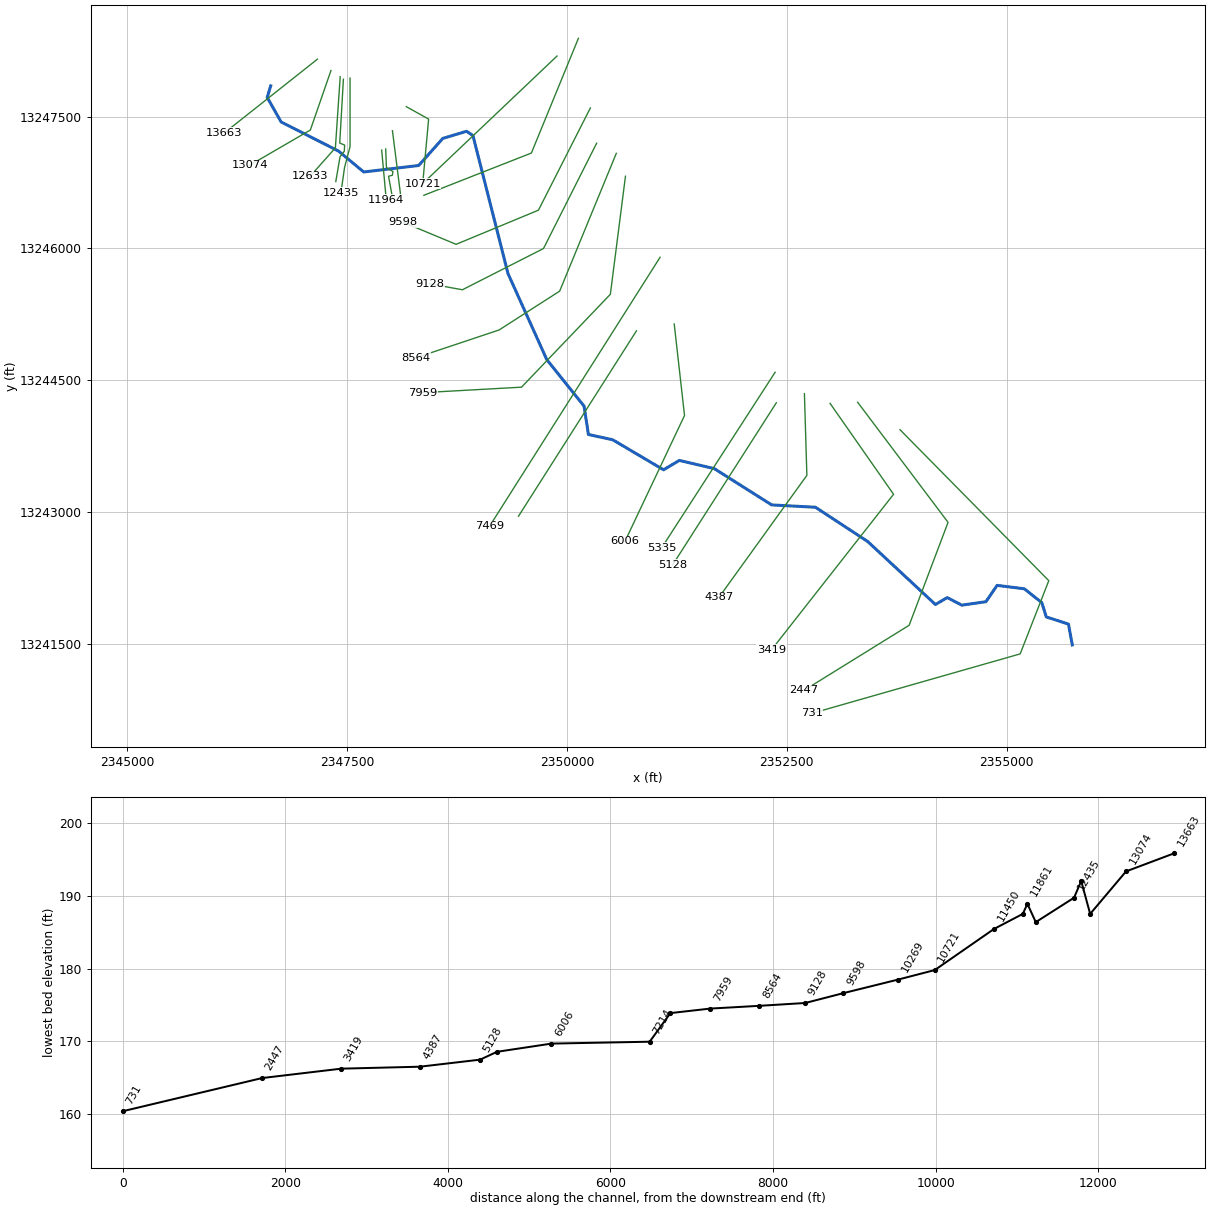
--- BAYOU CREEK TRIB 1.prj (project) ---

Proj Title=BAYOU CREEK TRIB 1 Base Level Engineering
Current Plan=p01
Default Exp/Contr=0.3,0.1
English Units
Geom File=g01
Flow File=f01
Plan File=p01
BEGIN DESCRIPTION:
BAYOU CREEK TRIB 1
END DESCRIPTION:

--- BAYOU CREEK TRIB 1.p01 (plan) ---

Plan Title=Multiple Run
Short Identifier=Multiple
Geom File=g01
Flow File=f01
Subcritical Flow
K Sum by GR= 0
Std Step Tol= 0.01
Critical Tol= 0.01
Num of Std Step Trials= 20
Max Error Tol= 0.3
Flow Tol Ratio= 0.001
Split Flow NTrial= 30
Split Flow Tol= 0.02
Split Flow Ratio= 0.02
Log Output Level= 0
Friction Slope Method= 1
Unsteady Friction Slope Method= 2
Unsteady Bridges Friction Slope Method= 1
Parabolic Critical Depth
Global Vel Dist=  1 , 1 , 1
Global Log Level= 0
CheckData=True
Encroach Param= -1, 0, 0, 0
BEGIN DESCRIPTION:
Multiple Run
END DESCRIPTION:

--- BAYOU CREEK TRIB 1.f01 (steady flow) ---

Flow Title=Multiple
Number of Profiles=7
Profile Names=10-year,25-year,50-year,1pct_min,100-year,1pct_plu,500-year
River Rch & RM= BAYOU CREEK TRIB,Reach-1,13663
     572     783     954     846    1144    1547    1652
River Rch & RM= BAYOU CREEK TRIB,Reach-1,7214
     624     857    1046     930    1258    1701    1825
River Rch & RM= BAYOU CREEK TRIB,Reach-1,5128
     781    1085    1333    1193    1613    2182    2372
Boundary for River Rch & Prof#=BAYOU CREEK TRIB,Reach-1,1
Up Type=0
Dn Type=3
Dn Slope=0.005
Boundary for River Rch & Prof#=BAYOU CREEK TRIB,Reach-1,2
Up Type=0
Dn Type=3
Dn Slope=0.005
Boundary for River Rch & Prof#=BAYOU CREEK TRIB,Reach-1,3
Up Type=0
Dn Type=3
Dn Slope=0.005
Boundary for River Rch & Prof#=BAYOU CREEK TRIB,Reach-1,4
Up Type=0
Dn Type=3
Dn Slope=0.005
Boundary for River Rch & Prof#=BAYOU CREEK TRIB,Reach-1,5
Up Type=0
Dn Type=3
Dn Slope=0.005
Boundary for River Rch & Prof#=BAYOU CREEK TRIB,Reach-1,6
Up Type=0
Dn Type=3
Dn Slope=0.005
Boundary for River Rch & Prof#=BAYOU CREEK TRIB,Reach-1,7
Up Type=0
Dn Type=3
Dn Slope=0.005

--- BAYOU CREEK TRIB 1.g01 (geometry) ---

Geom Title=Existing Conditions

River Reach=BAYOU CREEK TRIB,Reach-1
Reach XY= 30
      2346630.52     13247849.89      2346590.86     13247718.47
      2346749.50     13247438.73      2347401.66     13247107.82
      2347688.87     13246869.75      2348313.95     13246943.38
      2348587.89     13247251.55      2348858.45     13247332.96
      2348931.06     13247283.90      2349329.96     13245712.33
      2349771.16     13244733.41      2350194.85     13244204.67
      2350244.35     13243881.57      2350520.02     13243821.77
      2351098.96     13243479.80      2351277.93     13243586.62
      2351676.13     13243493.02      2352328.99     13243079.91
      2352826.33     13243053.49      2353421.06     13242663.21
      2354191.30     13241946.33      2354325.47     13242025.08
      2354490.81     13241939.06      2354765.79     13241978.55
      2354892.52     13242164.04      2355202.07     13242125.32
      2355401.21     13241967.81      2355452.17     13241804.91
      2355704.12     13241723.43      2355747.72     13241486.86

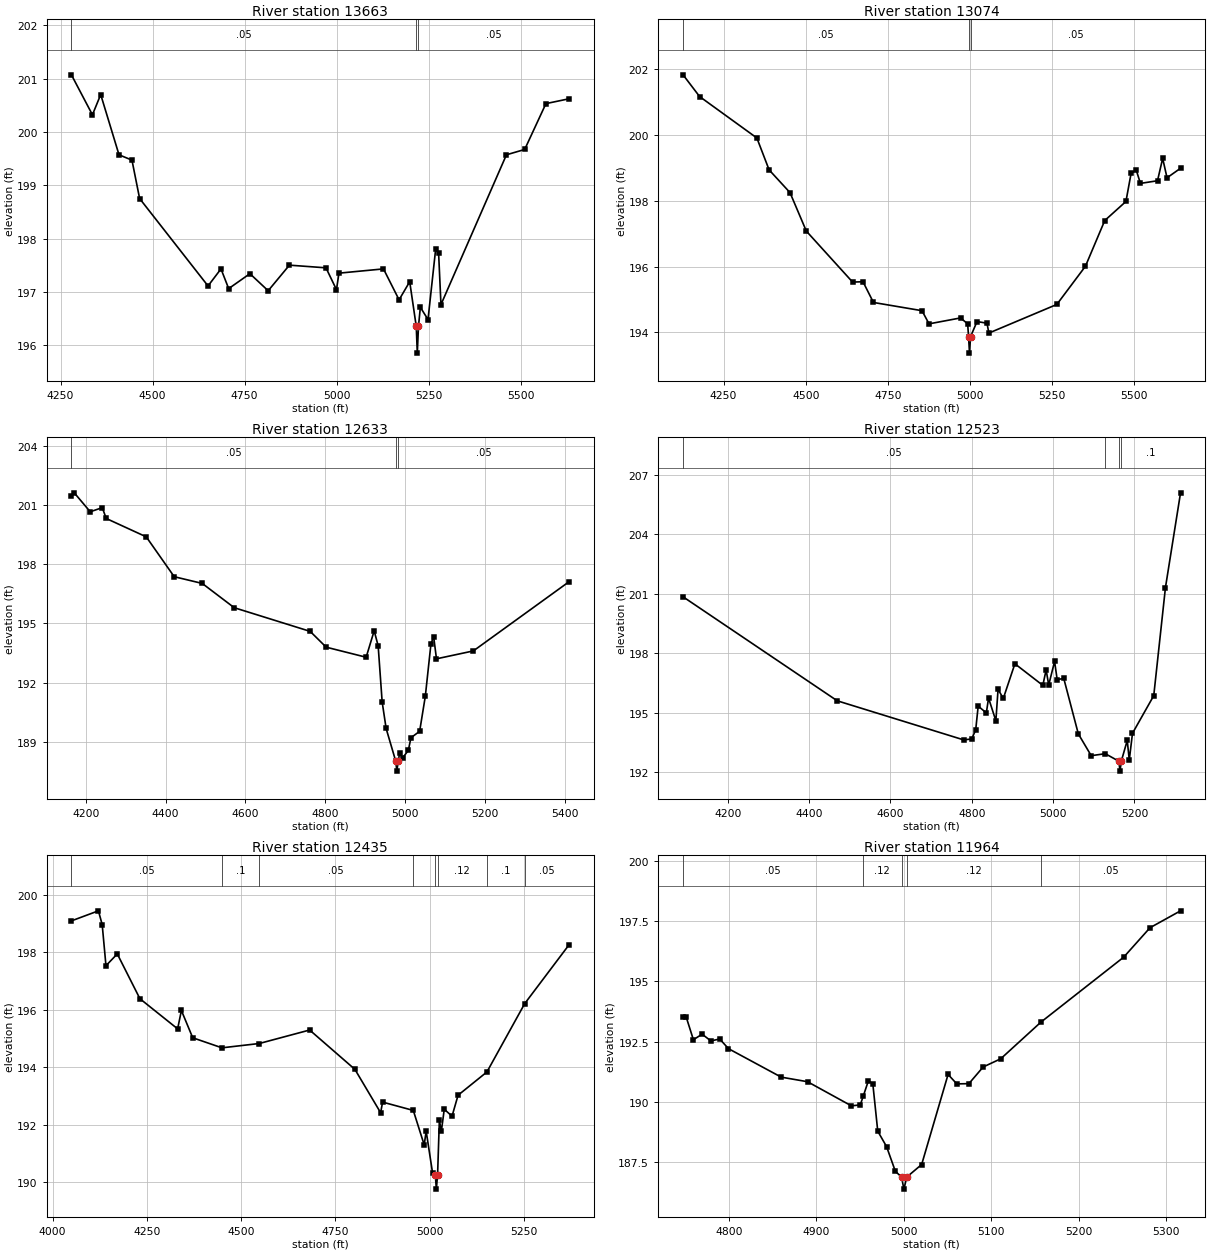
Type RM Length L Ch R = 1,13663,589,589,589
BEGIN DESCRIPTION:
BAYOU CREEK TRIB 1 15.0
END DESCRIPTION:
XS GIS Cut Line= 2
      2347162.04     13248153.72      2346102.95     13247313.83
#Sta/Elev= 30
  4279.5  201.07  4336.6  200.32  4359.1  200.70  4408.8  199.57  4444.0  199.47
  4464.8  198.75  4650.7  197.11  4685.9  197.43  4706.8  197.06  4764.5  197.34
  4814.1  197.02  4871.8  197.50  4971.2  197.45  4999.7  197.04  5006.4  197.35
  5127.4  197.43  5169.8  196.85  5198.7  197.19  5216.5  196.35  5219.3  195.85
  5222.5  196.35  5227.6  196.71  5248.4  196.48  5269.2  197.80  5277.2  197.73
  5283.6  196.76  5461.5  199.57  5511.1  199.67  5568.8  200.53  5631.2  200.62
#Mann=3,-1,0
  4279.5    0.05       0  5216.5   0.035       0  5222.5    0.05       0
Bank Sta=5216.5,5222.5
Exp/Cntr=0.3,0.1

Type RM Length L Ch R = 1,13074,441,441,441
BEGIN DESCRIPTION:
BAYOU CREEK TRIB 1 14.0
END DESCRIPTION:
XS GIS Cut Line= 3
      2347316.08     13248024.34      2347081.71     13247347.27
      2346392.18     13246946.56
#Sta/Elev= 30
  4126.8  201.83  4177.1  201.17  4351.4  199.91  4388.7  198.94  4452.2  198.25
  4501.9  197.08  4642.7  195.53  4674.4  195.54  4706.2  194.91  4853.9  194.66
  4875.4  194.26  4971.4  194.44  4992.9  194.26  4995.7  193.87  4998.5  193.37
  5001.7  193.87  5021.4  194.33  5051.7  194.28  5057.5  193.98  5264.3  194.85
  5351.3  196.01  5410.1  197.40  5474.6  197.98  5490.4  198.84  5506.1  198.93
  5518.7  198.53  5570.7  198.61  5586.4  199.29  5599.7  198.70  5640.8  198.99
#Mann=3,-1,0
  4126.8    0.05       0  4995.7   0.035       0  5001.7    0.05       0
Bank Sta=4995.7,5001.7
Exp/Cntr=0.3,0.1

Type RM Length L Ch R = 1,12633,110,110,110
BEGIN DESCRIPTION:
Mapping XS 50c83c66
END DESCRIPTION:
XS GIS Cut Line= 3
      2347421.12     13247953.99      2347366.43     13247144.14
      2347077.39     13246818.64
#Sta/Elev= 30
  4163.8  201.47  4170.9  201.62  4211.0  200.66  4241.1  200.87  4251.1  200.32
  4351.4  199.39  4421.5  197.37  4491.7  197.03  4571.9  195.80  4762.3  194.60
  4802.4  193.80  4902.6  193.29  4922.7  194.63  4932.7  193.87  4942.7  191.03
  4952.7  189.68  4976.8  188.02  4979.6  187.52  4982.8  188.02  4986.5  188.42
  4994.0  188.19  5008.3  188.57  5014.9  189.21  5036.7  189.54  5050.9  191.31
  5065.1  193.98  5071.8  194.33  5078.9  193.21  5171.3  193.61  5410.8  197.11
#Mann=3,-1,0
  4163.8    0.05       0  4976.8    0.03       0  4982.8    0.05       0
Bank Sta=4976.8,4982.8
Exp/Cntr=0.3,0.1

Type RM Length L Ch R = 1,12523,88,88,88
BEGIN DESCRIPTION:
Mapping XS e7cf51d1
END DESCRIPTION:
XS GIS Cut Line= 6
      2347457.58     13247925.42      2347415.91     13247199.70
      2347471.47     13247175.39      2347468.00     13247105.95
      2347419.39     13247043.45      2347371.04     13246760.31
#Sta/Elev= 30
  4090.0  200.85  4469.2  195.60  4779.7  193.63  4799.7  193.67  4809.7  194.13
  4815.8  195.33  4835.9  194.99  4841.3  195.74  4859.3  194.59  4864.7  196.18
  4877.6  195.72  4906.1  197.47  4974.8  196.38  4982.9  197.16  4989.3  196.40
  5003.7  197.59  5010.1  196.67  5026.3  196.73  5062.1  193.93  5093.8  192.83
  5128.4  192.93  5161.8  192.55  5164.6  192.05  5167.8  192.55  5182.4  193.60
  5187.4  192.61  5195.3  193.96  5247.6  195.86  5276.4  201.32  5313.5  206.10
#Mann=4,-1,0
  4090.0    0.05       0  5128.4     0.1       0  5161.8    0.03       0
  5167.8     0.1       0
Bank Sta=5161.8,5167.8
Exp/Cntr=0.3,0.1

Type RM Length L Ch R = 1,12435,471,471,471
BEGIN DESCRIPTION:
Mapping XS 5c08a5d4
END DESCRIPTION:
XS GIS Cut Line= 4
      2347533.10     13247938.41      2347533.10     13247157.16
      2347470.60     13246921.05      2347429.11     13246630.60
#Sta/Elev= 30
  4050.0  199.09  4121.6  199.44  4131.6  198.96  4141.6  197.53  4171.6  197.94
  4231.6  196.38  4331.6  195.33  4341.6  195.97  4371.6  195.02  4449.1  194.67
  4547.9  194.82  4681.6  195.29  4801.6  193.92  4869.8  192.41  4875.0  192.78
  4956.4  192.49  4985.3  191.29  4990.5  191.77  5007.4  190.32  5014.8  190.25
  5017.5  189.75  5020.8  190.25  5025.5  192.15  5030.7  191.76  5038.5  192.53
  5059.1  192.29  5075.1  193.02  5151.6  193.83  5251.8  196.21  5368.9  198.25
#Mann=8,-1,0
  4050.0    0.05       0  4449.1     0.1       0  4547.9    0.05       0
  4956.4    0.12       0  5014.8    0.07       0  5020.8    0.12       0
  5151.6     0.1       0  5251.8    0.05       0
Bank Sta=5014.8,5020.8
Exp/Cntr=0.3,0.1

Type RM Length L Ch R = 1,11964,103,103,103
BEGIN DESCRIPTION:
Mapping XS 8eae6e06
END DESCRIPTION:
XS GIS Cut Line= 2
      2347892.91     13247118.56      2347944.99     13246552.15
#Sta/Elev= 30
  4747.6  193.54  4751.0  193.54  4759.4  192.58  4769.4  192.81  4779.4  192.53
  4789.5  192.61  4799.5  192.21  4859.8  191.03  4889.9  190.84  4940.1  189.84
  4950.2  189.88  4953.5  190.23  4959.6  190.89  4964.6  190.74  4970.2  188.79
  4980.3  188.15  4990.3  187.13  4997.4  186.89  5000.1  186.39  5003.4  186.89
  5020.4  187.41  5050.6  191.14  5060.6  190.75  5074.4  190.76  5090.7  191.45
  5110.8  191.79  5156.8  193.31  5251.4  196.00  5281.5  197.22  5316.4  197.92
#Mann=5,-1,0
  4747.6    0.05       0  4953.5    0.12       0  4997.4    0.07       0
  5003.4    0.12       0  5156.8    0.05       0
Bank Sta=4997.4,5003.4
Exp/Cntr=0.3,0.1

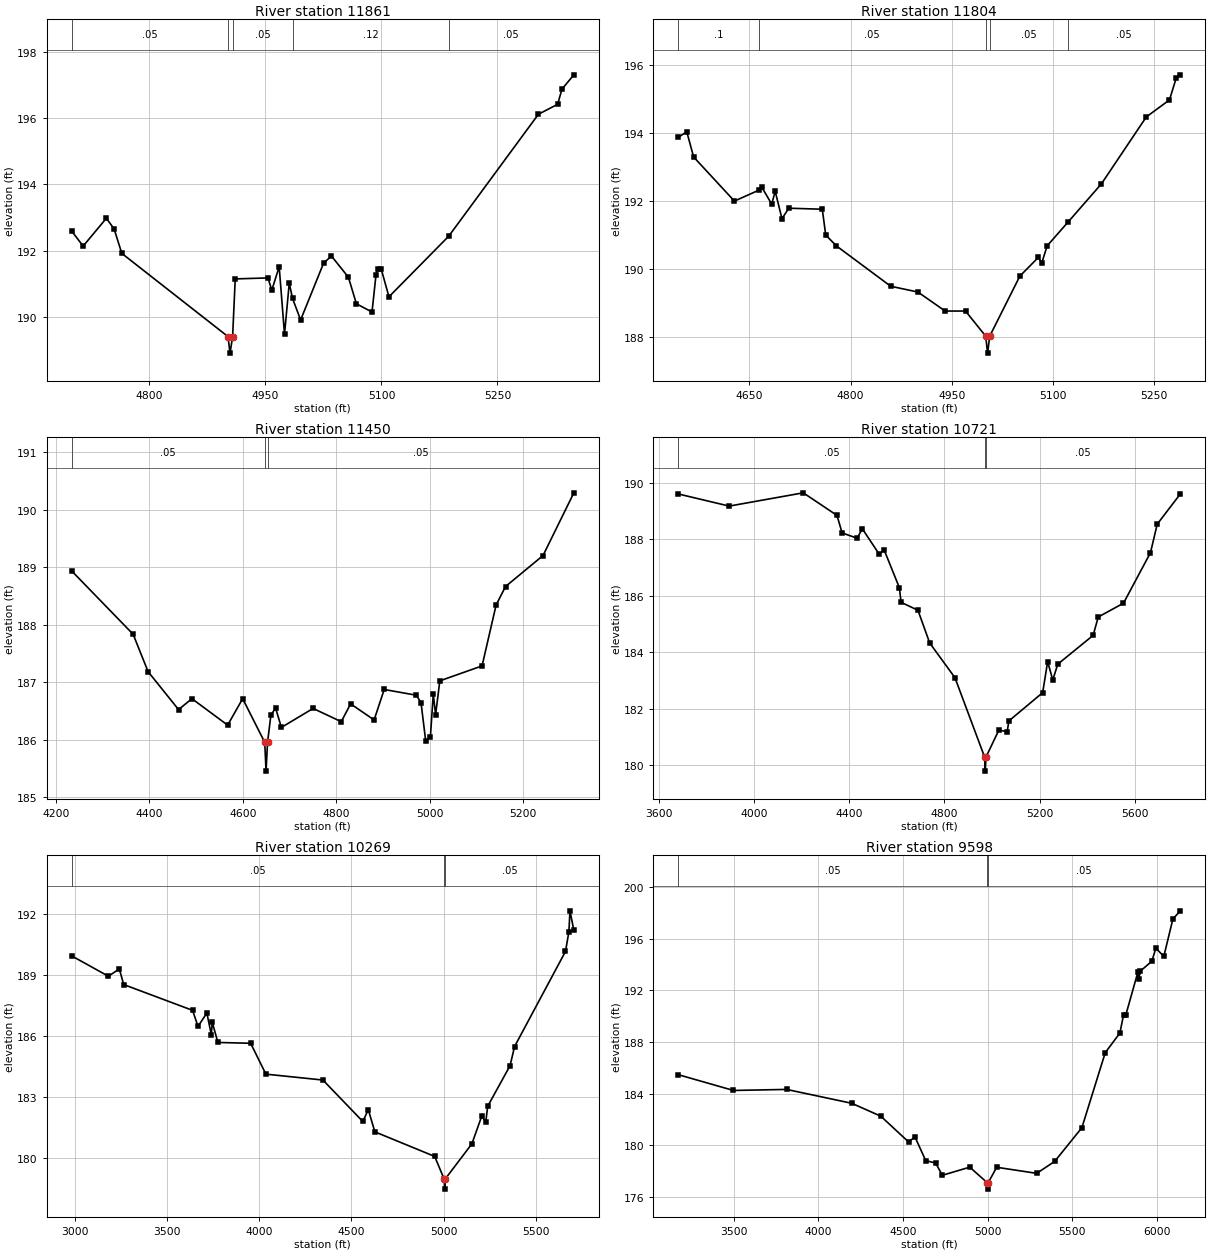
Type RM Length L Ch R = 1,11861,57,57,57
BEGIN DESCRIPTION:
Mapping XS b74dcba6
END DESCRIPTION:
XS GIS Cut Line= 6
      2347938.48     13247131.54      2347947.16     13246918.88
      2348020.95     13246875.48      2348014.44     13246832.08
      2347971.03     13246821.23      2348016.59     13246571.78
#Sta/Elev= 30
  4699.7  192.59  4714.4  192.14  4744.4  192.98  4754.4  192.66  4764.4  191.92
  4901.6  189.41  4904.3  188.91  4907.6  189.41  4911.0  191.15  4953.3  191.18
  4958.3  190.81  4967.8  191.52  4974.7  189.48  4980.8  191.02  4985.1  190.56
  4995.5  189.91  5025.3  191.63  5035.4  191.84  5057.3  191.20  5067.6  190.40
  5087.8  190.15  5093.0  191.28  5095.1  191.44  5099.8  191.44  5109.7  190.61
  5187.0  192.44  5302.9  196.12  5327.7  196.42  5333.4  196.88  5348.7  197.31
#Mann=5,-1,0
  4699.7    0.05       0  4901.6    0.07       0  4907.6    0.05       0
  4985.1    0.12       0  5187.0    0.05       0
Bank Sta=4901.6,4907.6
Exp/Cntr=0.3,0.1

Type RM Length L Ch R = 1,11804,354,354,354
BEGIN DESCRIPTION:
Mapping XS 7559fcaa
END DESCRIPTION:
XS GIS Cut Line= 2
      2348015.30     13247339.46      2348108.93     13246600.87
#Sta/Elev= 30
  4544.5  193.88  4557.2  194.04  4567.3  193.30  4627.8  192.00  4663.9  192.32
  4668.1  192.42  4683.1  191.91  4688.3  192.29  4698.3  191.48  4708.4  191.79
  4758.1  191.76  4763.2  191.00  4779.0  190.68  4859.6  189.49  4899.9  189.32
  4940.3  188.76  4970.5  188.76  5000.4  188.02  5003.2  187.52  5006.4  188.02
  5051.1  189.79  5078.5  190.34  5083.5  190.17  5091.5  190.68  5122.9  191.39
  5172.1  192.51  5238.6  194.48  5272.9  194.98  5283.0  195.63  5289.0  195.72
#Mann=5,-1,0
  4544.5     0.1       0  4663.9    0.05       0  5000.4    0.03       0
  5006.4    0.05       0  5122.9    0.05       0
Bank Sta=5000.4,5006.4
Exp/Cntr=0.3,0.1

Type RM Length L Ch R = 1,11450,729,729,729
BEGIN DESCRIPTION:
Mapping XS c1b86c2c
END DESCRIPTION:
XS GIS Cut Line= 3
      2348173.02     13247612.89      2348426.91     13247471.83
      2348355.35     13246691.25
#Sta/Elev= 30
  4233.8  188.93  4365.1  187.83  4397.1  187.18  4462.3  186.52  4490.9  186.71
  4567.3  186.25  4599.5  186.71  4646.7  185.95  4649.5  185.45  4652.7  185.95
  4659.8  186.42  4669.8  186.55  4682.3  186.21  4750.2  186.54  4810.4  186.31
  4830.5  186.62  4880.7  186.34  4902.3  186.87  4971.1  186.77  4981.1  186.64
  4991.2  185.97  5001.2  186.05  5007.3  186.79  5012.3  186.43  5021.3  187.02
  5111.7  187.28  5141.8  188.34  5161.9  188.66  5242.2  189.20  5308.1  190.29
#Mann=3,-1,0
  4233.8    0.05       0  4646.7   0.035       0  4652.7    0.05       0
Bank Sta=4646.7,4652.7
Exp/Cntr=0.3,0.1

Type RM Length L Ch R = 1,10721,452,452,452
BEGIN DESCRIPTION:
BAYOU CREEK TRIB 1 13.0
END DESCRIPTION:
XS GIS Cut Line= 2
      2349887.37     13248189.40      2348359.56     13246737.87
#Sta/Elev= 30
  3682.8  189.61  3896.6  189.18  4207.6  189.65  4349.2  188.85  4370.6  188.23
  4434.1  188.04  4455.2  188.38  4526.0  187.48  4547.4  187.62  4610.9  186.29
  4618.2  185.77  4688.9  185.49  4738.3  184.33  4844.3  183.10  4968.7  180.29
  4971.4  179.79  4974.7  180.29  5028.3  181.24  5063.5  181.19  5070.8  181.57
  5212.4  182.57  5233.4  183.67  5254.8  183.02  5275.9  183.58  5424.3  184.60
  5445.7  185.25  5551.7  185.74  5665.0  187.53  5693.3  188.54  5790.2  189.61
#Mann=3,-1,0
  3682.8    0.05       0  4968.7   0.035       0  4974.7    0.05       0
Bank Sta=4968.7,4974.7
Exp/Cntr=0.3,0.1

Type RM Length L Ch R = 1,10269,671,671,671
BEGIN DESCRIPTION:
BAYOU CREEK TRIB 1 12.0
END DESCRIPTION:
XS GIS Cut Line= 3
      2350130.42     13248390.80      2349595.69     13247085.22
      2348372.65     13246604.40
#Sta/Elev= 30
  2982.0  189.96  3180.8  188.96  3240.0  189.32  3264.0  188.55  3637.8  187.28
  3667.2  186.49  3715.2  187.15  3739.2  186.09  3744.6  186.69  3775.1  185.70
  3952.8  185.66  4035.6  184.14  4345.2  183.85  4561.6  181.81  4591.4  182.39
  4627.0  181.30  4951.7  180.09  5002.9  178.98  5005.7  178.48  5008.9  178.98
  5153.6  180.71  5207.3  182.08  5228.8  181.78  5239.5  182.56  5360.9  184.56
  5385.3  185.50  5661.6  190.18  5680.1  191.15  5686.0  192.18  5707.0  191.22
#Mann=3,-1,0
  2982.0    0.05       0  5002.9   0.035       0  5008.9    0.05       0
Bank Sta=5002.9,5008.9
Exp/Cntr=0.3,0.1

Type RM Length L Ch R = 1,9598,470,470,470
BEGIN DESCRIPTION:
BAYOU CREEK TRIB 1 11.0
END DESCRIPTION:
XS GIS Cut Line= 4
      2350266.40     13247598.09      2349676.12     13246434.91
      2348739.40     13246046.15      2348137.72     13246296.86
#Sta/Elev= 30
  3170.2  185.47  3496.8  184.25  3810.8  184.33  4196.2  183.26  4368.7  182.26
  4533.6  180.26  4570.3  180.67  4634.5  178.82  4693.0  178.64  4732.7  177.69
  4894.8  178.32  4998.1  177.12  5000.9  176.62  5004.1  177.12  5054.3  178.31
  5290.8  177.84  5397.1  178.76  5558.3  181.37  5696.4  187.17  5783.1  188.69
  5804.8  190.09  5818.3  190.09  5889.8  193.41  5895.2  192.89  5902.3  193.46
  5972.1  194.24  5996.0  195.25  6043.1  194.62  6096.7  197.51  6140.6  198.14
#Mann=3,-1,0
  3170.2    0.05       0  4998.1   0.035       0  5004.1    0.05       0
Bank Sta=4998.1,5004.1
Exp/Cntr=0.3,0.1

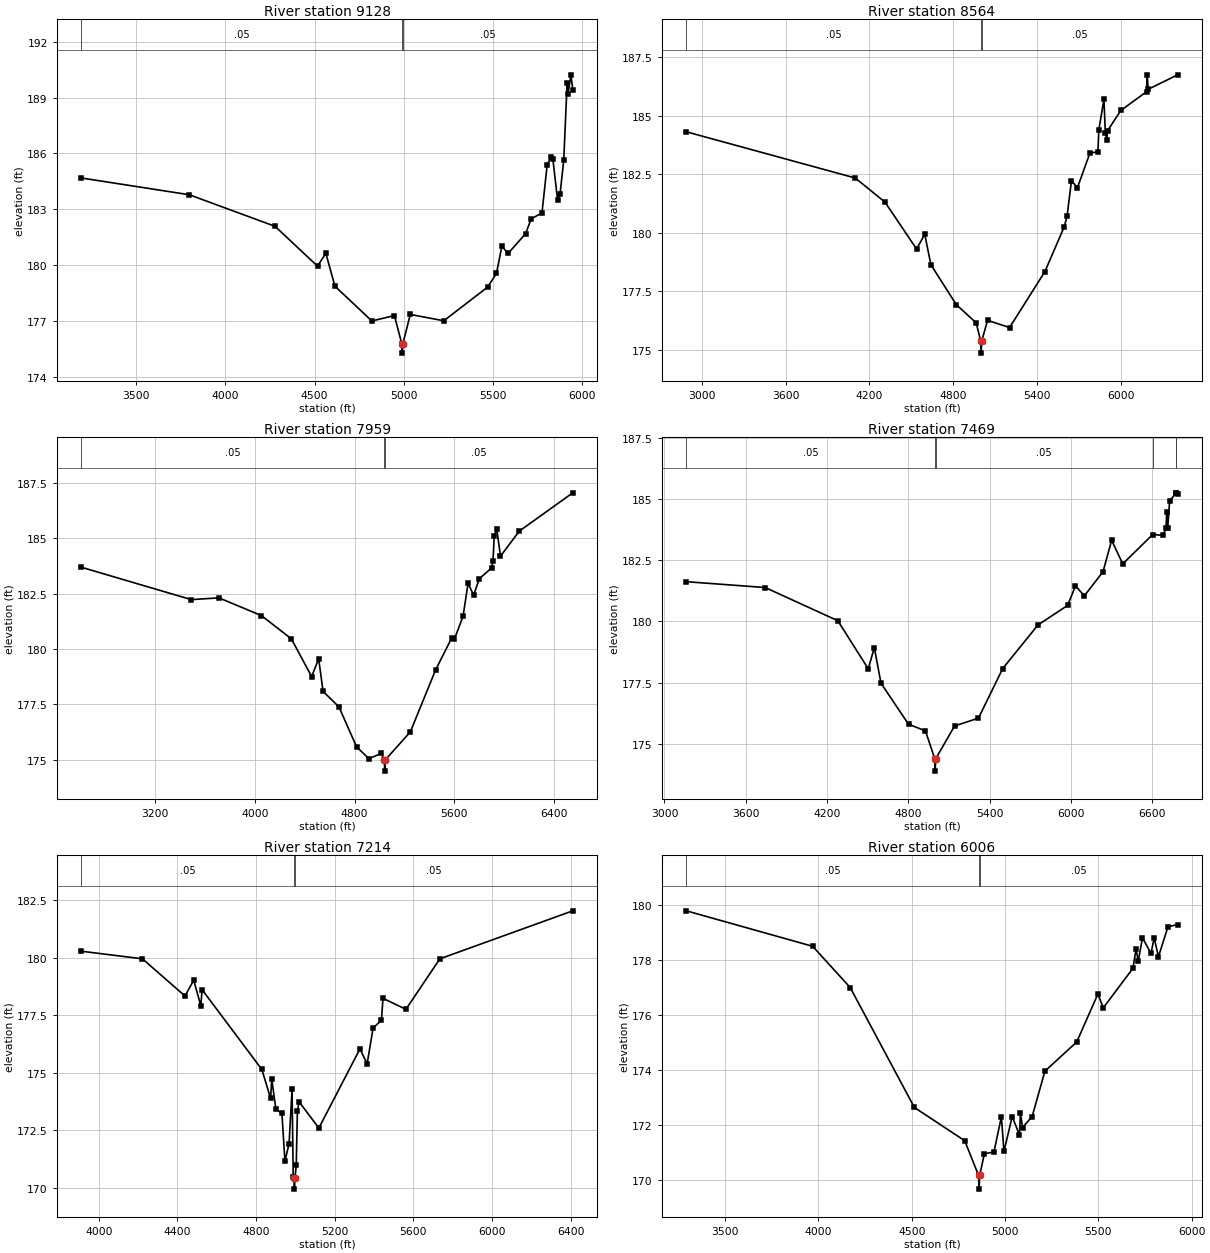
Type RM Length L Ch R = 1,9128,564,564,564
BEGIN DESCRIPTION:
BAYOU CREEK TRIB 1 10.0
END DESCRIPTION:
XS GIS Cut Line= 4
      2350337.71     13247196.83      2349733.42     13245998.27
      2348810.97     13245528.99      2348437.73     13245596.85
#Sta/Elev= 30
  3192.0  184.68  3796.7  183.78  4278.3  182.08  4516.3  179.94  4563.1  180.63
  4614.1  178.86  4821.2  176.99  4947.8  177.28  4989.3  175.76  4992.0  175.26
  4995.3  175.76  5036.8  177.34  5225.1  177.00  5470.5  178.81  5520.6  179.55
  5550.4  181.00  5586.5  180.63  5684.3  181.69  5714.8  182.48  5775.8  182.80
  5805.0  185.40  5826.6  185.79  5836.8  185.71  5863.5  183.48  5877.5  183.84
  5897.8  185.63  5916.8  189.77  5921.9  189.20  5938.4  190.23  5948.6  189.44
#Mann=3,-1,0
  3192.0    0.05       0  4989.3   0.035       0  4995.3    0.05       0
Bank Sta=4989.3,4995.3
Exp/Cntr=0.3,0.1

Type RM Length L Ch R = 1,8564,605,605,605
BEGIN DESCRIPTION:
BAYOU CREEK TRIB 1 9.0
END DESCRIPTION:
XS GIS Cut Line= 4
      2350561.53     13247081.59      2349917.22     13245513.23
      2349228.21     13245071.19      2348276.75     13244753.08
#Sta/Elev= 30
  2888.7  184.31  4097.7  182.34  4311.0  181.31  4537.1  179.31  4595.5  179.94
  4639.7  178.64  4821.3  176.94  4963.8  176.16  4996.8  175.37  4999.6  174.87
  5002.8  175.37  5045.4  176.27  5202.7  175.96  5456.1  178.35  5594.2  180.26
  5614.3  180.70  5645.9  182.22  5689.0  181.93  5778.5  183.41  5835.7  183.45
  5841.6  184.39  5878.5  185.69  5888.4  184.28  5899.0  183.98  5904.8  184.36
  5999.5  185.22  6183.6  186.02  6189.1  186.72  6194.3  186.12  6406.1  186.74
#Mann=3,-1,0
  2888.7    0.05       0  4996.8   0.035       0  5002.8    0.05       0
Bank Sta=4996.8,5002.8
Exp/Cntr=0.3,0.1

Type RM Length L Ch R = 1,7959,490,490,490
BEGIN DESCRIPTION:
BAYOU CREEK TRIB 1 8.0
END DESCRIPTION:
XS GIS Cut Line= 4
      2350665.71     13246821.21      2350493.83     13245477.44
      2349483.42     13244420.15      2348358.44     13244357.65
#Sta/Elev= 30
  2607.9  183.69  3489.4  182.23  3711.2  182.31  4052.2  181.51  4292.8  180.46
  4455.4  178.76  4512.0  179.56  4547.2  178.09  4674.6  177.39  4816.1  175.59
  4915.2  175.05  5014.3  175.29  5039.3  174.99  5042.1  174.49  5045.3  174.99
  5247.7  176.26  5450.8  179.06  5581.0  180.51  5601.1  180.44  5671.2  181.48
  5711.2  182.97  5755.6  182.43  5801.4  183.17  5901.5  183.67  5911.5  183.99
  5921.5  185.12  5941.6  185.41  5971.6  184.19  6121.9  185.32  6551.8  187.05
#Mann=3,-1,0
  2607.9    0.05       0  5039.3   0.035       0  5045.3    0.05       0
Bank Sta=5039.3,5045.3
Exp/Cntr=0.3,0.1

Type RM Length L Ch R = 1,7469,255,255,255
BEGIN DESCRIPTION:
BAYOU CREEK TRIB 1 7.0
END DESCRIPTION:
XS GIS Cut Line= 2
      2351059.68     13245899.04      2349118.83     13242835.25
#Sta/Elev= 30
  3161.4  181.63  3744.0  181.39  4279.8  180.03  4504.4  178.06  4549.0  178.93
  4598.4  177.47  4801.8  175.79  4926.4  175.52  4995.8  174.37  4998.6  173.87
  5001.8  174.37  5141.6  175.72  5317.9  176.04  5496.7  178.07  5757.8  179.86
  5976.4  180.66  6034.0  181.46  6099.7  181.05  6237.4  182.04  6301.0  183.32
  6383.2  182.36  6603.8  183.56  6679.8  183.53  6701.9  183.81  6707.8  184.47
  6715.3  183.83  6729.0  184.95  6777.4  185.25  6779.5  185.27  6788.2  185.21
#Mann=6,-1,0
  3161.4    0.05       0  4995.8   0.035       0  5001.8    0.05       0
  6603.8    0.08       0  6777.4    0.05       0  6779.5    0.08       0
Bank Sta=4995.8,5001.8
Exp/Cntr=0.3,0.1

Type RM Length L Ch R = 1,7214,1208,1208,1208
BEGIN DESCRIPTION:
BAYOU CREEK TRIB 1 6.0
END DESCRIPTION:
XS GIS Cut Line= 2
      2350790.55     13245061.32      2349449.42     13242951.97
#Sta/Elev= 30
  3911.5  180.29  4221.6  179.96  4438.2  178.34  4482.5  179.03  4518.9  177.91
  4524.8  178.62  4829.3  175.14  4873.7  173.88  4879.6  174.71  4900.8  173.41
  4931.3  173.23  4946.5  171.15  4967.7  171.91  4982.9  174.27  4988.8  170.46
  4992.2  170.43  4994.9  169.93  4998.2  170.43  5004.1  170.96  5010.0  173.34
  5018.9  173.73  5119.3  172.59  5328.4  176.04  5364.8  175.39  5395.3  176.95
  5437.6  177.28  5445.5  178.24  5562.1  177.76  5734.9  179.96  6411.1  182.05
#Mann=3,-1,0
  3911.5    0.05       0  4992.2   0.035       0  4998.2    0.05       0
Bank Sta=4992.2,4998.2
Exp/Cntr=0.3,0.1

Type RM Length L Ch R = 1,6006,671,671,671
BEGIN DESCRIPTION:
BAYOU CREEK TRIB 1 5.0
END DESCRIPTION:
XS GIS Cut Line= 3
      2351220.26     13245139.48      2351337.44     13244097.81
      2350660.36     13242665.53
#Sta/Elev= 30
  3292.5  179.79  3969.4  178.50  4170.6  177.00  4514.4  172.64  4784.2  171.43
  4858.3  170.17  4861.1  169.67  4864.3  170.17  4889.6  170.96  4940.7  171.02
  4980.7  172.30  4994.4  171.04  5038.6  172.31  5077.3  171.64  5082.9  172.43
  5093.9  171.91  5145.5  172.31  5213.8  173.96  5384.2  175.02  5498.0  176.77
  5526.3  176.26  5685.6  177.70  5702.3  178.40  5713.9  177.96  5736.7  178.81
  5782.2  178.24  5799.4  178.81  5822.2  178.12  5873.2  179.21  5925.0  179.29
#Mann=3,-1,0
  3292.5    0.05       0  4858.3   0.035       0  4864.3    0.05       0
Bank Sta=4858.3,4864.3
Exp/Cntr=0.3,0.1

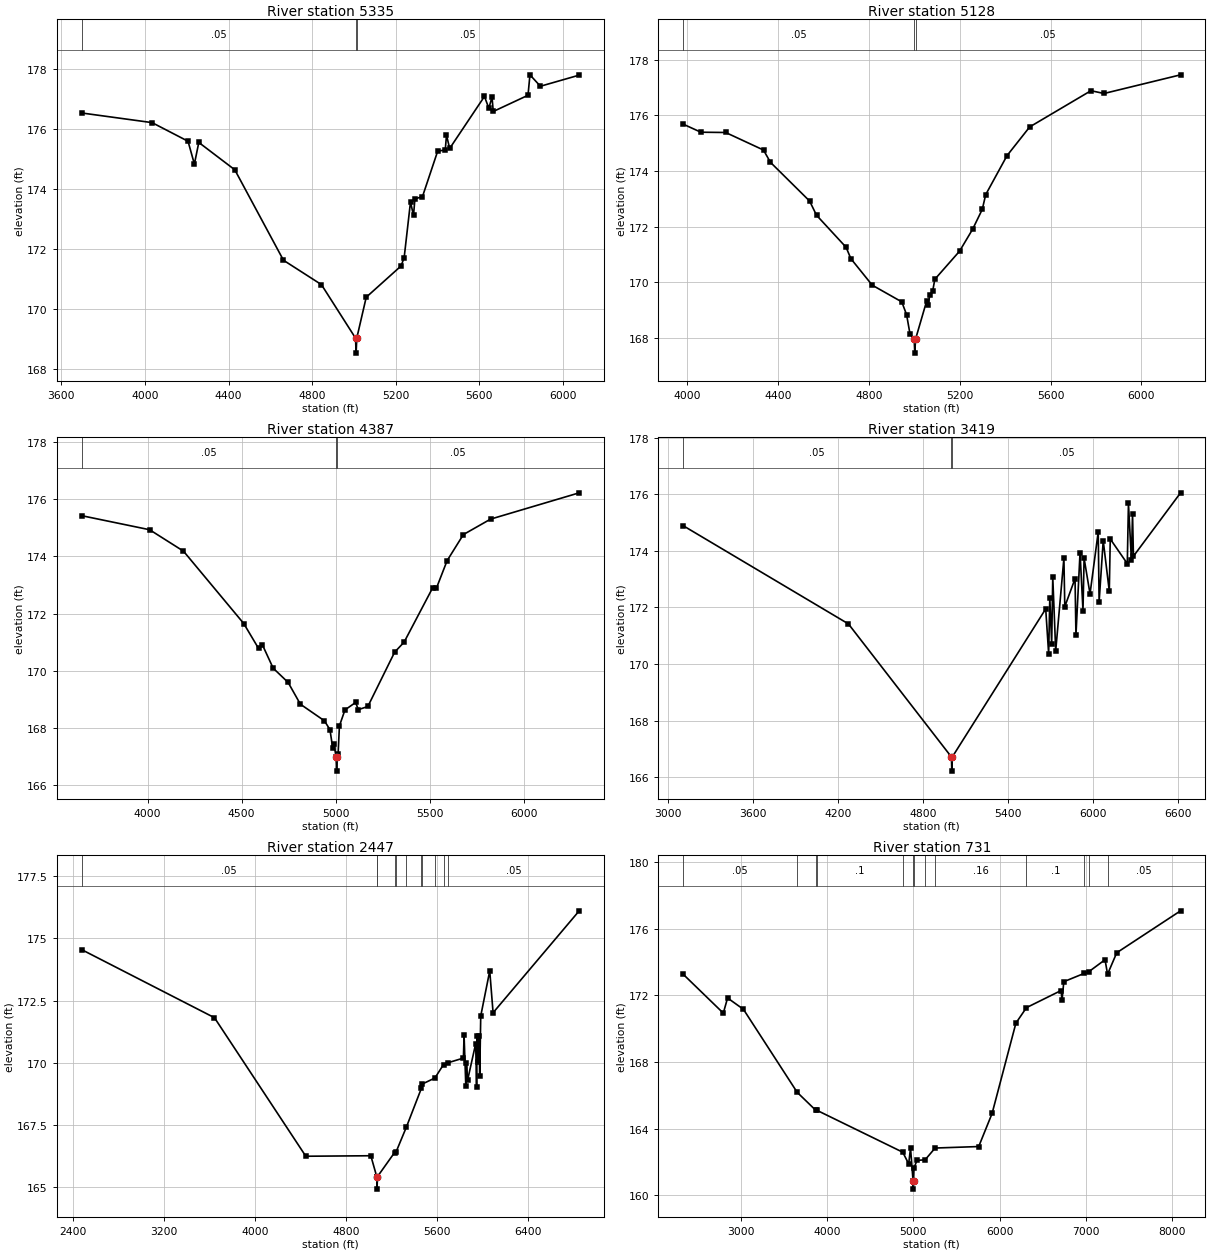
Type RM Length L Ch R = 1,5335,207,207,207
BEGIN DESCRIPTION:
BAYOU CREEK TRIB 1 4.0
END DESCRIPTION:
XS GIS Cut Line= 2
      2352367.80     13244589.96      2351076.75     13242590.91
#Sta/Elev= 30
  3697.8  176.53  4033.9  176.21  4206.1  175.59  4236.5  174.83  4257.6  175.55
  4429.8  174.64  4662.7  171.63  4844.2  170.82  5007.4  169.04  5010.2  168.54
  5013.4  169.04  5058.6  170.40  5225.2  171.44  5240.1  171.72  5270.4  173.57
  5284.8  173.12  5291.5  173.67  5327.8  173.75  5400.4  175.26  5436.7  175.30
  5442.6  175.79  5457.8  175.35  5624.1  177.08  5645.2  176.69  5660.4  177.06
  5666.3  176.58  5832.6  177.12  5841.8  177.80  5891.9  177.42  6077.5  177.79
#Mann=3,-1,0
  3697.8    0.05       0  5007.4   0.035       0  5013.4    0.05       0
Bank Sta=5007.4,5013.4
Exp/Cntr=0.3,0.1

Type RM Length L Ch R = 1,5128,741,741,741
BEGIN DESCRIPTION:
BAYOU CREEK TRIB 1 3.0
END DESCRIPTION:
XS GIS Cut Line= 2
      2352381.70     13244242.75      2351201.92     13242396.75
#Sta/Elev= 30
  3981.8  175.68  4060.1  175.39  4169.2  175.38  4335.8  174.75  4366.3  174.31
  4538.8  172.92  4569.3  172.41  4699.5  171.26  4720.7  170.85  4814.6  169.90
  4944.8  169.30  4966.0  168.84  4981.2  168.14  4999.4  167.96  5002.1  167.46
  5005.4  167.96  5054.0  169.32  5059.9  169.18  5068.8  169.56  5081.0  169.69
  5090.3  170.11  5199.3  171.12  5257.0  171.91  5299.3  172.62  5314.5  173.15
  5408.4  174.55  5508.2  175.58  5778.0  176.88  5835.6  176.78  6172.6  177.45
#Mann=3,-1,0
  3981.8    0.05       0  4999.4   0.035       0  5005.4    0.05       0
Bank Sta=4999.4,5005.4
Exp/Cntr=0.3,0.1

Type RM Length L Ch R = 1,4387,968,968,968
BEGIN DESCRIPTION:
Mapping XS 0d4d93e3
END DESCRIPTION:
XS GIS Cut Line= 3
      2352701.16     13244346.90      2352728.94     13243416.39
      2351728.92     13242027.47
#Sta/Elev= 30
  3650.6  175.42  4010.8  174.93  4190.9  174.18  4511.0  171.65  4589.6  170.78
  4610.5  170.90  4667.2  170.09  4746.8  169.59  4811.8  168.83  4939.5  168.25
  4968.9  167.94  4983.6  167.30  4989.8  167.44  5001.5  166.99  5004.2  166.49
  5007.5  166.99  5012.2  167.08  5019.2  168.07  5048.6  168.63  5105.1  168.89
  5119.8  168.64  5170.2  168.75  5312.6  170.65  5362.9  171.00  5513.8  172.89
  5534.7  172.89  5591.4  173.85  5677.6  174.76  5821.9  175.30  6293.0  176.22
#Mann=3,-1,0
  3650.6    0.05       0  5001.5   0.035       0  5007.5    0.05       0
Bank Sta=5001.5,5007.5
Exp/Cntr=0.3,0.1

Type RM Length L Ch R = 1,3419,972,972,972
BEGIN DESCRIPTION:
BAYOU CREEK TRIB 1 2.0
END DESCRIPTION:
XS GIS Cut Line= 3
      2352992.80     13244235.87      2353715.05     13243201.11
      2352326.79     13241431.08
#Sta/Elev= 30
  3108.7  174.89  4275.6  171.42  5002.7  166.72  5005.4  166.22  5008.7  166.72
  5668.3  171.95  5689.1  170.36  5697.2  172.35  5710.4  170.72  5718.0  173.08
  5738.8  170.47  5796.7  173.74  5803.0  172.03  5875.3  173.02  5881.7  171.02
  5910.6  173.94  5931.4  171.89  5939.2  173.74  5981.1  172.48  6038.9  174.67
  6045.3  172.20  6074.2  174.36  6117.1  172.58  6123.9  174.42  6244.2  173.55
  6252.3  175.68  6273.1  173.69  6281.2  175.31  6287.5  173.81  6620.1  176.05
#Mann=3,-1,0
  3108.7    0.05       0  5002.7   0.035       0  5008.7    0.05       0
Bank Sta=5002.7,5008.7
Exp/Cntr=0.3,0.1

Type RM Length L Ch R = 1,2447,1716,1716,1716
BEGIN DESCRIPTION:
Mapping XS 4a4414e1
END DESCRIPTION:
XS GIS Cut Line= 4
      2353306.11     13244248.95      2354334.78     13242881.72
      2353892.07     13241709.85      2352694.15     13240967.66
#Sta/Elev= 30
  2476.8  174.54  3643.2  171.81  4446.2  166.25  5017.8  166.27  5069.9  165.43
  5072.6  164.93  5075.9  165.43  5226.8  166.40  5238.6  166.41  5331.3  167.43
  5461.8  168.97  5466.2  169.14  5581.2  169.39  5656.8  169.93  5694.6  170.00
  5831.7  170.19  5837.6  171.10  5852.9  169.06  5858.8  170.00  5868.3  169.30
  5939.7  170.77  5947.5  169.04  5953.3  171.08  5962.8  170.02  5968.7  171.09
  5975.0  169.46  5984.1  171.88  6063.2  173.69  6092.6  172.01  6849.7  176.10
#Mann=11,-1,0
  2476.8    0.05       0  5069.9   0.035       0  5075.9    0.05       0
  5226.8    0.16       0  5238.6     0.1       0  5331.3    0.16       0
  5461.8     0.1       0  5466.2    0.16       0  5581.2     0.1       0
  5656.8    0.16       0  5694.6    0.05       0
Bank Sta=5069.9,5075.9
Exp/Cntr=0.3,0.1

Type RM Length L Ch R = 1,731,0,0,0
BEGIN DESCRIPTION:
BAYOU CREEK TRIB 1 1.0
END DESCRIPTION:
XS GIS Cut Line= 4
      2353787.94     13243936.38      2355480.62     13242217.66
      2355155.09     13241384.33      2352785.27     13240707.23
#Sta/Elev= 30
  2328.5  173.28  2794.7  170.94  2844.2  171.85  3028.1  171.17  3651.9  166.18
  3867.3  165.10  3880.0  165.10  4876.7  162.58  4945.6  161.88  4967.1  162.83
  4996.3  160.86  4999.1  160.36  5002.3  160.86  5007.3  161.64  5042.5  162.09
  5135.9  162.12  5252.3  162.83  5758.2  162.92  5913.5  164.91  6189.8  170.34
  6312.3  171.27  6714.3  172.30  6724.7  171.70  6745.5  172.83  6982.4  173.33
  7033.0  173.42  7223.9  174.15  7253.3  173.28  7359.8  174.57  8100.1  177.09
#Mann=13,-1,0
  2328.5    0.05       0  3651.9     0.1       0  3867.3    0.16       0
  3880.0     0.1       0  4876.7    0.12       0  4996.3    0.07       0
  5002.3    0.12       0  5135.9     0.1       0  5252.3    0.16       0
  6312.3     0.1       0  6982.4    0.16       0  7033.0     0.1       0
  7253.3    0.05       0
Bank Sta=4996.3,5002.3
Exp/Cntr=0.3,0.1

Chan Stop Cuts=-1