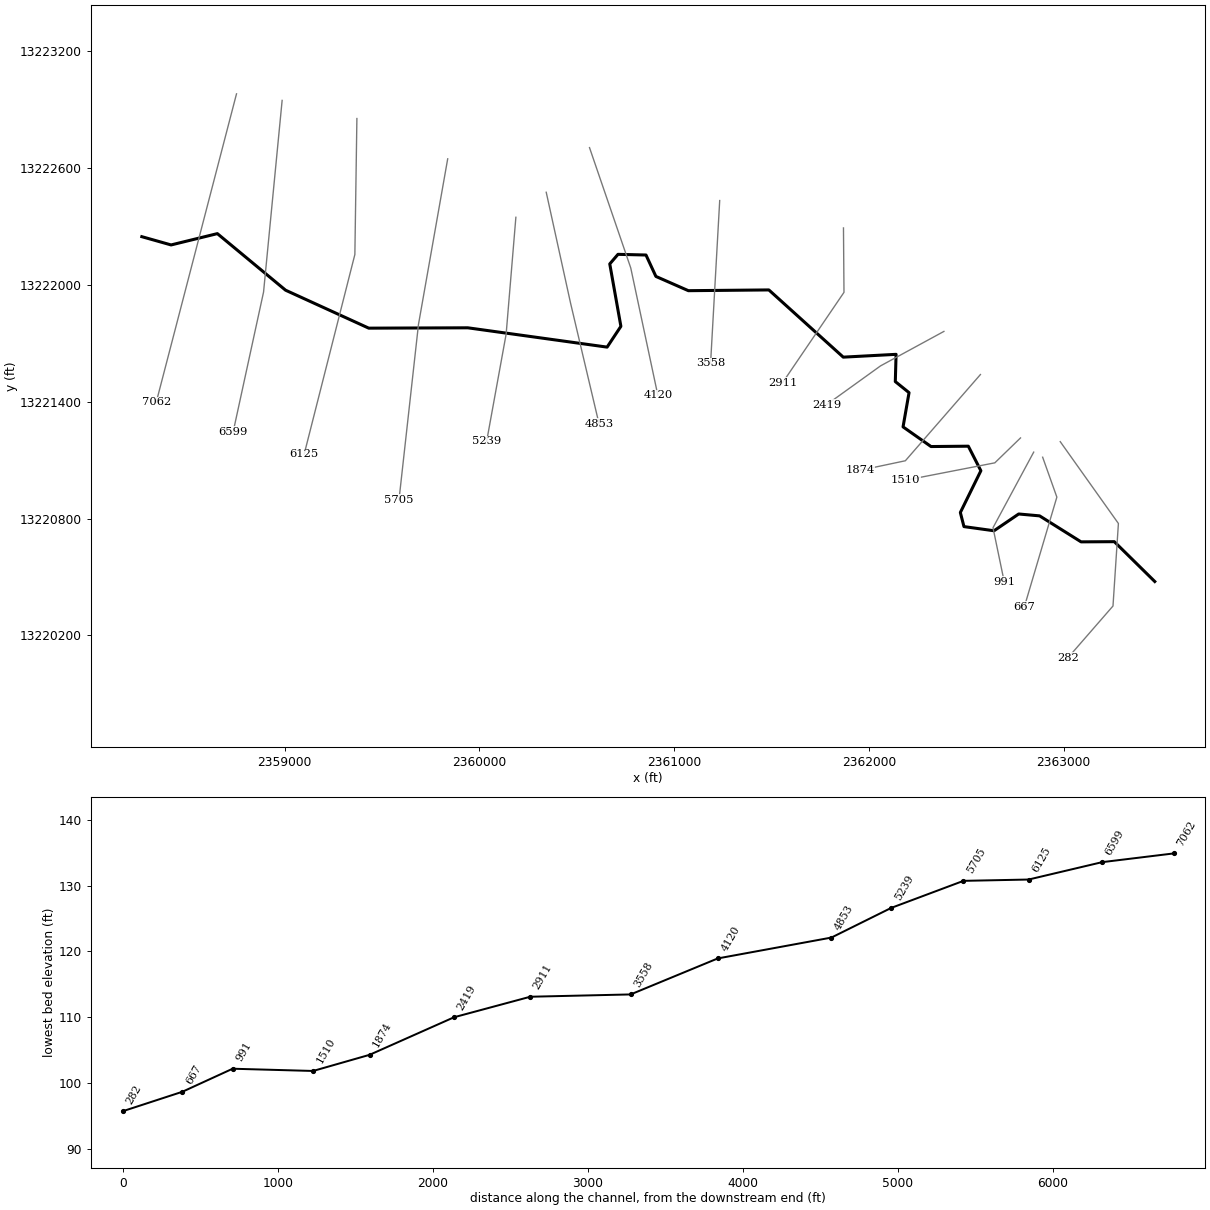
--- BAYOU CREEK TRIB 2.prj (project) ---

Proj Title=BAYOU CREEK TRIB 2 Base Level Engineering
Current Plan=p01
Default Exp/Contr=0.3,0.1
English Units
Geom File=g01
Flow File=f01
Plan File=p01
Y Axis Title=Elevation
X Axis Title(PF)=Main Channel Distance
X Axis Title(XS)=Station
BEGIN DESCRIPTION:
BAYOU CREEK TRIB 2
END DESCRIPTION:
DSS Export Rating Curves= 0
DSS Export Rating Curve Sorted= 0
DSS Export Volume Flow Curves= 0
DXF OffsetX= 0
DXF OffsetY= 0
DXF ScaleX= 1
DXF ScaleY= 10

--- BAYOU CREEK TRIB 2.p01 (plan) ---

Plan Title=Multiple Run
Short Identifier=Multiple
Geom File=g01
Flow File=f01
Subcritical Flow
K Sum by GR= 0
Std Step Tol= 0.01
Critical Tol= 0.01
Num of Std Step Trials= 20
Max Error Tol= 0.3
Flow Tol Ratio= 0.001
Split Flow NTrial= 30
Split Flow Tol= 0.02
Split Flow Ratio= 0.02
Log Output Level= 0
Friction Slope Method= 1
Unsteady Friction Slope Method= 2
Unsteady Bridges Friction Slope Method= 1
Parabolic Critical Depth
Global Vel Dist=  1 , 1 , 1
Global Log Level= 0
CheckData=True
Encroach Param= -1, 0, 0, 0
BEGIN DESCRIPTION:
Multiple Run
END DESCRIPTION:

--- BAYOU CREEK TRIB 2.f01 (steady flow) ---

Flow Title=Multiple
Program Version=4.10
Number of Profiles= 7
Profile Names=10-year,25-year,50-year,1pct_min,100-year,1pct_plu,500-year
River Rch & RM=BAYOU CREEK TRIB,Reach-1         ,7062
     393     528     634     556     752    1017    1060
River Rch & RM=BAYOU CREEK TRIB,Reach-1         ,3558
     497     679     827     735     994    1344    1439
Boundary for River Rch & Prof#=BAYOU CREEK TRIB,Reach-1         , 1
Up Type= 0
Dn Type= 3
Dn Slope=0.0077
Boundary for River Rch & Prof#=BAYOU CREEK TRIB,Reach-1         , 2
Up Type= 0
Dn Type= 3
Dn Slope=0.0077
Boundary for River Rch & Prof#=BAYOU CREEK TRIB,Reach-1         , 3
Up Type= 0
Dn Type= 3
Dn Slope=0.0077
Boundary for River Rch & Prof#=BAYOU CREEK TRIB,Reach-1         , 4
Up Type= 0
Dn Type= 3
Dn Slope=0.0077
Boundary for River Rch & Prof#=BAYOU CREEK TRIB,Reach-1         , 5
Up Type= 0
Dn Type= 3
Dn Slope=0.0077
Boundary for River Rch & Prof#=BAYOU CREEK TRIB,Reach-1         , 6
Up Type= 0
Dn Type= 3
Dn Slope=0.0077
Boundary for River Rch & Prof#=BAYOU CREEK TRIB,Reach-1         , 7
Up Type= 0
Dn Type= 3
Dn Slope=0.0077
DSS Import GetInterval= 0
DSS Import GetPeak= 0
DSS Import FillOption= 0

--- BAYOU CREEK TRIB 2.g01 (geometry) ---

Geom Title=Existing Conditions
Program Version=4.10

River Reach=BAYOU CREEK TRIB,Reach-1
Reach XY= 30
      2358267.33      13222247.2      2358417.68     13222204.76
      2358655.14     13222262.85      2359005.44     13221972.37
      2359432.43     13221777.55      2359941.01     13221779.33
      2360656.13     13221680.17      2360726.85     13221786.89
      2360669.73     13222107.31      2360711.97     13222156.52
      2360855.74     13222153.02      2360906.58     13222043.14
      2361073.27     13221969.91      2361486.53      13221973.8
       2361868.5      13221628.7      2362139.63      13221643.1
       2362135.7     13221503.18       2362206.2     13221446.41
      2362175.46     13221270.67      2362319.03     13221169.75
      2362510.53     13221171.55      2362574.96     13221045.51
      2362469.54     13220831.08      2362488.17     13220758.71
      2362642.45      13220737.4      2362769.16      13220823.5
      2362876.45     13220813.86      2363089.33     13220680.43
      2363260.04     13220681.35      2363467.72     13220476.85

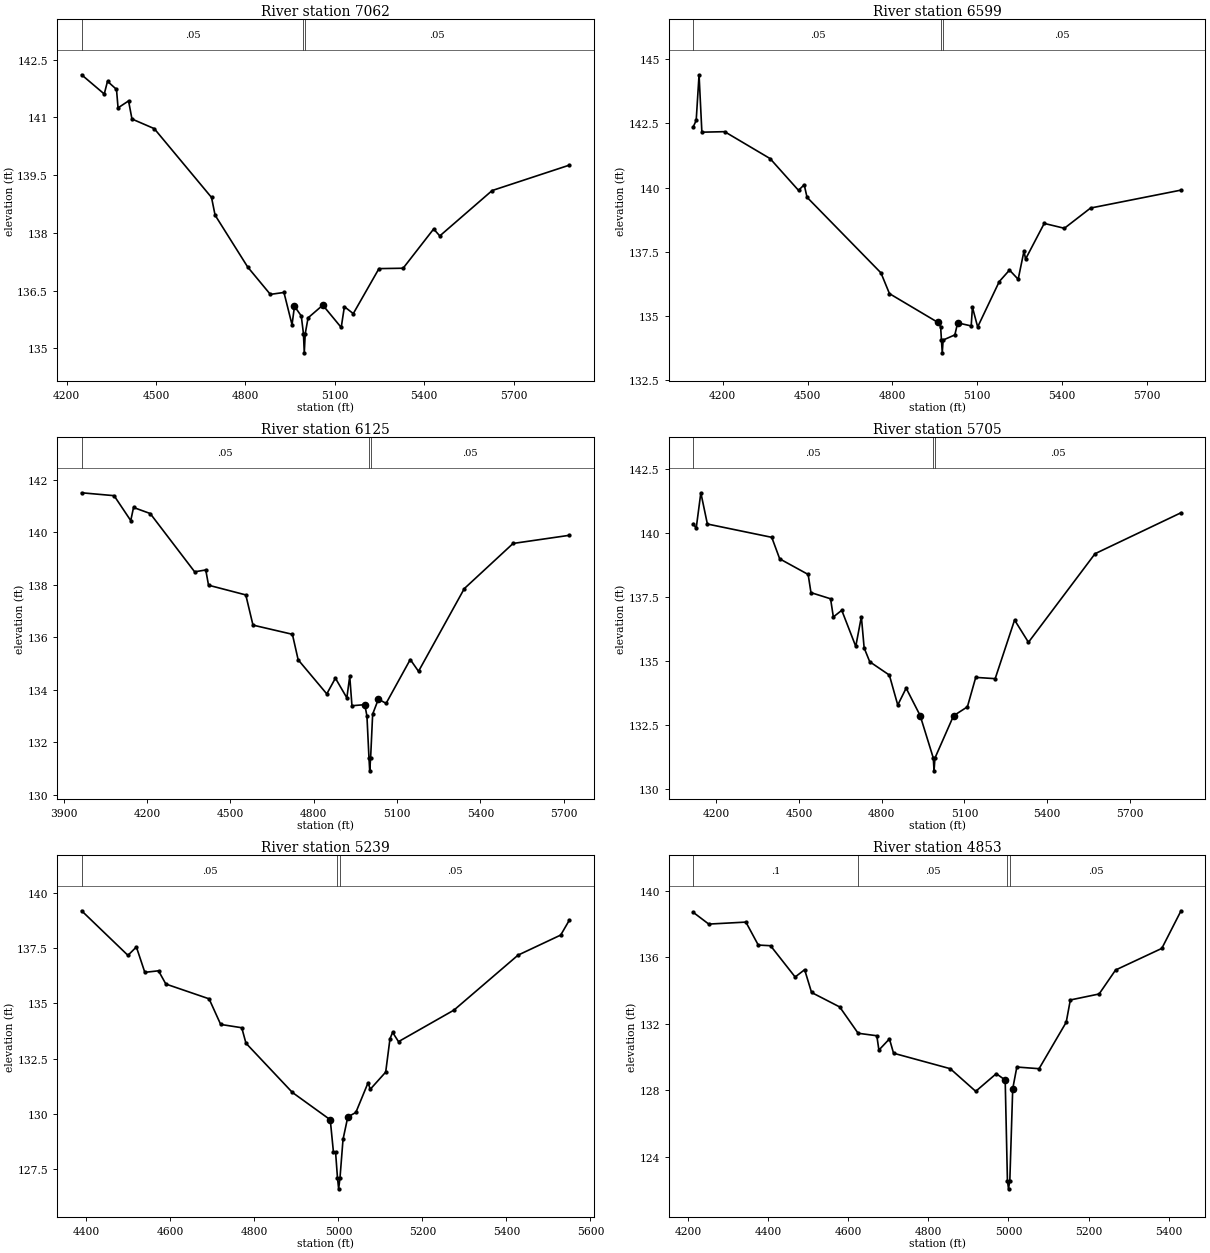
Type RM Length L Ch R = 1 ,7062    ,463,463,463
BEGIN DESCRIPTION:
BAYOU CREEK TRIB 2 13.0
END DESCRIPTION:
XS GIS Cut Line= 2
      2358753.46     13222980.39      2358341.15     13221396.27
#Sta/Elev= 30
  4250.3  142.11  4326.3  141.61  4337.2  141.94  4367.4  141.73  4372.6  141.25
  4407.9  141.43  4419.3  140.96  4494.1  140.71  4686.4  138.92  4698.3  138.46
  4807.9  137.11  4883.8   136.4  4929.5  136.45  4956.6  135.61  4964.8  136.09
  4987.6  135.84  4994.9  135.38  4997.7  134.88  5000.9  135.38  5010.5  135.79
  5059.9  136.12  5121.7  135.54  5132.3  136.08  5162.2   135.9  5248.4  137.07
  5329.5  137.08  5431.9   138.1  5452.6  137.92  5628.3   139.1  5887.2  139.76
#Mann= 3 ,-1 , 0
  4250.3     .05       0  4994.9    .035       0  5000.9     .05       0
Bank Sta=4964.8,5059.9
XS Rating Curve= 0 ,0
Exp/Cntr=0.3,0.1

Type RM Length L Ch R = 1 ,6599    ,474,474,474
BEGIN DESCRIPTION:
BAYOU CREEK TRIB 2 12.0
END DESCRIPTION:
XS GIS Cut Line= 3
      2358987.72     13222946.83      2358892.36     13221963.07
      2358736.11     13221244.32
#Sta/Elev= 30
  4096.3  142.38  4106.3  142.62  4116.4   144.4  4126.4  142.16  4206.8  142.18
  4367.5  141.13    4468  139.89  4488.1  140.11  4498.1  139.62  4759.4  136.67
  4789.5  135.86  4960.3  134.74  4970.3  134.57  4973.3  134.05  4976.1  133.55
  4979.3  134.05  5020.6  134.25  5030.6  134.72  5078.4   134.6  5082.8  135.33
  5101.3  134.56  5177.6  136.33  5213.8  136.78  5244.5  136.42    5265  137.52
  5270.7  137.21  5336.6   138.6  5407.8  138.41  5500.4   139.2  5820.2   139.9
#Mann= 3 ,-1 , 0
  4096.3     .05       0  4973.3    .035       0  4979.3     .05       0
Bank Sta=4960.3,5030.6
XS Rating Curve= 0 ,0
Exp/Cntr=0.3,0.1

Type RM Length L Ch R = 1 ,6125    ,420,420,420
BEGIN DESCRIPTION:
BAYOU CREEK TRIB 2 11.0
END DESCRIPTION:
XS GIS Cut Line= 3
      2359371.53     13222853.73      2359361.11     13222155.78
      2359100.96     13221130.81
#Sta/Elev= 30
  3964.6   141.5  4081.5  141.39  4141.5  140.44  4151.5  140.94  4211.5  140.71
  4371.5  138.49  4411.5  138.56  4421.5  137.98  4555.6  137.61  4581.5  136.46
  4723.4  136.11  4744.1  135.14  4847.2  133.84  4878.2  134.44  4919.4  133.69
  4929.8  134.51  4937.8  133.39  4983.9  133.43  4991.7     133    4999  131.41
  5001.7  130.91    5005  131.41  5012.3  133.07  5032.9  133.64  5060.7  133.48
  5147.7  135.15  5177.4   134.7  5342.2  137.85  5517.8  139.57  5720.1  139.88
#Mann= 3 ,-1 , 0
  3964.6     .05       0    4999    .035       0    5005     .05       0
Bank Sta=4983.9,5032.9
XS Rating Curve= 0 ,0
Exp/Cntr=0.3,0.1

Type RM Length L Ch R = 1 ,5705    ,466,466,466
BEGIN DESCRIPTION:
BAYOU CREEK TRIB 2 10.0
END DESCRIPTION:
XS GIS Cut Line= 3
      2359837.72     13222646.86      2359687.72     13221796.85
      2359587.72     13220896.83
#Sta/Elev= 30
  4116.7  140.36  4126.9  140.18  4143.8  141.57  4167.5  140.35    4401  139.83
  4429.8  138.99    4533  138.38  4543.2  137.67  4614.3  137.43  4624.4  136.72
  4654.9  136.98  4705.7  135.57    4726  136.73  4736.1  135.51  4756.4  134.97
  4827.5  134.45    4858  133.28  4888.4  133.94  4939.2  132.87  4986.9  131.21
  4989.6  130.71  4992.9  131.21  5060.3  132.86  5110.6  133.21  5140.8  134.36
  5211.3  134.31  5281.7   136.6    5332  135.73  5573.5  139.19  5885.4  140.79
#Mann= 3 ,-1 , 0
  4116.7     .05       0  4986.9    .035       0  4992.9     .05       0
Bank Sta=4939.2,5060.3
XS Rating Curve= 0 ,0
Exp/Cntr=0.3,0.1

Type RM Length L Ch R = 1 ,5239    ,386,386,386
BEGIN DESCRIPTION:
BAYOU CREEK TRIB 2 9.0
END DESCRIPTION:
XS GIS Cut Line= 3
      2360187.72     13222346.81      2360137.72     13221746.85
      2360037.71     13221196.81
#Sta/Elev= 30
  4388.4   139.2  4498.7  137.18  4518.8  137.56  4538.9  136.41  4571.5  136.48
    4589  135.88  4691.9  135.21  4719.5  134.05  4769.7   133.9  4779.7   133.2
  4890.1  130.97  4980.4  129.73  4987.9  128.28    4993  128.28  4997.6   127.1
  5000.4   126.6  5003.6   127.1  5010.8  128.84  5022.2  129.86  5041.3  130.06
  5070.5  131.41  5075.6  131.11  5112.4  131.89  5122.6   133.4  5128.9  133.69
  5142.9  133.27    5275   134.7  5427.5  137.19  5529.1   138.1  5549.5  138.77
#Mann= 3 ,-1 , 0
  4388.4     .05       0  4997.6    .035       0  5003.6     .05       0
Bank Sta=4980.4,5022.2
XS Rating Curve= 0 ,0
Exp/Cntr=0.3,0.1

Type RM Length L Ch R = 1 ,4853    ,733,733,733
BEGIN DESCRIPTION:
BAYOU CREEK TRIB 2 8.0
END DESCRIPTION:
XS GIS Cut Line= 3
      2360343.54     13222475.19      2360468.53     13221905.78
      2360614.37     13221287.72
#Sta/Elev= 30
    4213   138.7  4251.5     138  4344.2  138.12  4375.1  136.74  4405.8   136.7
  4467.2  134.82  4490.9  135.26  4508.2  133.89  4578.5  133.02  4624.5  131.44
  4671.2  131.29  4676.4  130.43  4702.7   131.1    4713  130.24  4854.6  129.31
  4918.2  127.95  4969.5  129.01  4991.8  128.63  4997.4  122.59  5000.1  122.09
  5003.4  122.59  5010.6   128.1  5020.9  129.41  5076.4  129.31  5144.2   132.1
  5154.5  133.44  5226.4   133.8  5267.5  135.24    5383  136.54    5431   138.8
#Mann= 4 ,-1 , 0
    4213      .1       0  4624.5     .05       0  4997.4    .035       0
  5003.4     .05       0
Bank Sta=4991.8,5010.6
XS Rating Curve= 0 ,0
Exp/Cntr=0.3,0.1

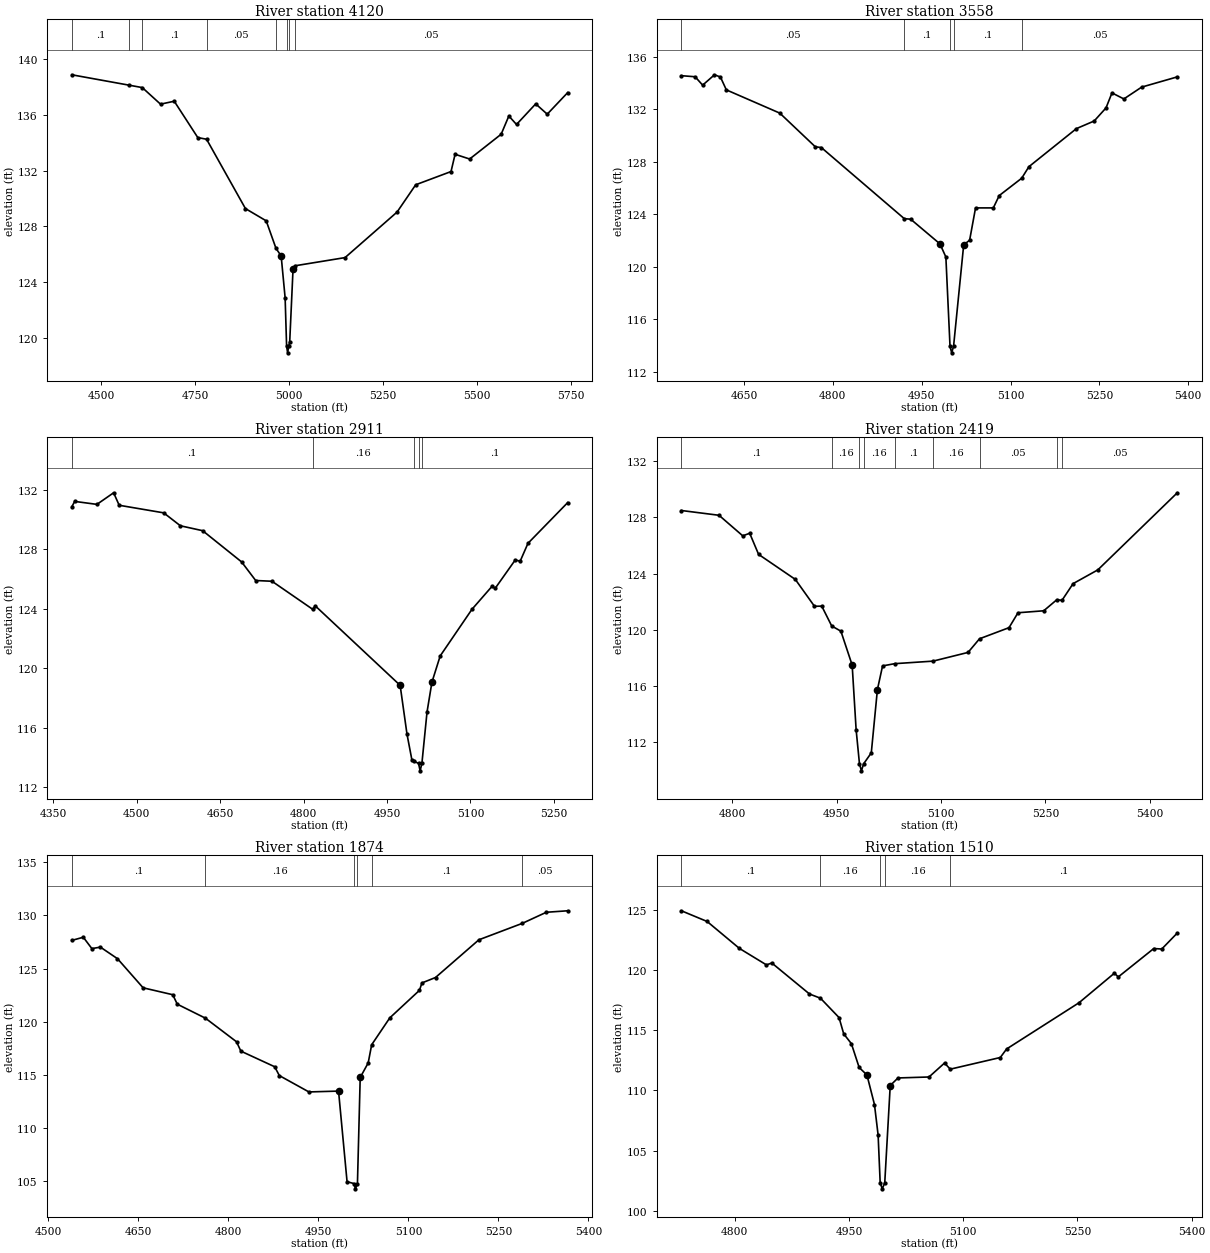
Type RM Length L Ch R = 1 ,4120    ,562,562,562
BEGIN DESCRIPTION:
BAYOU CREEK TRIB 2 7.0
END DESCRIPTION:
XS GIS Cut Line= 3
      2360565.76     13222704.36      2360777.56     13222086.34
      2360916.45     13221433.56
#Sta/Elev= 30
  4421.2  138.89  4574.5  138.14    4609  137.97  4657.5  136.78  4694.1  136.99
  4756.8  134.38  4780.2  134.26  4883.7  129.28    4939   128.4  4965.1  126.42
  4978.8  125.88  4989.4  122.87  4993.3  119.42    4996  118.92  4999.3  119.42
  5001.6  119.72  5010.5  124.96  5015.2  125.17    5149  125.76  5287.5  129.03
  5337.1  130.99  5431.2  131.94    5442  133.18  5480.8  132.84  5564.7  134.62
  5585.2  135.93  5605.6  135.32  5656.7   136.8  5687.4  136.06  5741.9  137.61
#Mann= 8 ,-1 , 0
  4421.2      .1       0  4574.5     .05       0    4609      .1       0
  4780.2     .05       0  4965.1     .16       0  4993.3     .07       0
  4999.3     .16       0  5015.2     .05       0
Bank Sta=4978.8,5010.5
XS Rating Curve= 0 ,0
Exp/Cntr=0.3,0.1

Type RM Length L Ch R = 1 ,3558    ,647,647,647
BEGIN DESCRIPTION:
Mapping XS b088642f
END DESCRIPTION:
XS GIS Cut Line= 2
      2361234.16     13222432.66      2361187.28     13221596.77
#Sta/Elev= 30
  4544.3  134.56  4567.5  134.48  4580.2  133.84  4600.2  134.63  4610.2  134.46
  4620.2  133.48  4710.4  131.71  4770.5  129.14  4780.5  129.09  4920.6  123.67
  4931.4  123.63  4980.8  121.75  4990.8  120.75  4997.8  113.95  5000.6  113.45
  5003.8  113.95  5020.9  121.68  5030.9  122.03  5040.9  124.49  5070.9  124.49
  5080.9  125.43  5118.8  126.75    5131  127.63  5211.2  130.53  5241.2  131.11
  5261.2  132.11  5271.2  133.25  5291.3  132.79  5321.3  133.69  5381.5  134.47
#Mann= 5 ,-1 , 0
  4544.3     .05       0  4920.6      .1       0  4997.8     .07       0
  5003.8      .1       0  5118.8     .05       0
Bank Sta=4980.8,5020.9
XS Rating Curve= 0 ,0
Exp/Cntr=0.3,0.1

Type RM Length L Ch R = 1 ,2911    ,492,492,492
BEGIN DESCRIPTION:
BAYOU CREEK TRIB 2 6.0
END DESCRIPTION:
XS GIS Cut Line= 3
      2361869.57     13222292.04      2361872.18     13221961.34
      2361557.08     13221497.81
#Sta/Elev= 30
  4383.5  130.85  4388.7  131.22  4428.7  131.02  4458.7   131.8  4468.7  130.96
  4548.7  130.45  4578.7  129.58  4618.7  129.25  4688.7  127.15    4714   125.9
  4743.3  125.85  4816.2  123.97  4821.2  124.19  4973.6  118.85  4985.9  115.57
  4994.8  113.82  4998.1  113.75  5006.7   113.6  5009.5   113.1  5012.7   113.6
  5021.9  117.05  5030.7  119.06  5045.6  120.83  5102.6  123.96  5138.5   125.5
  5144.5  125.38  5180.4  127.28  5189.3   127.2  5203.3   128.4  5274.7  131.14
#Mann= 5 ,-1 , 0
  4383.5      .1       0  4816.2     .16       0  4998.1      .1       0
  5006.7     .07       0  5012.7      .1       0
Bank Sta=4973.6,5030.7
XS Rating Curve= 0 ,0
Exp/Cntr=0.3,0.1

Type RM Length L Ch R = 1 ,2419    ,545,545,545
BEGIN DESCRIPTION:
BAYOU CREEK TRIB 2 5.0
END DESCRIPTION:
XS GIS Cut Line= 3
      2362385.24     13221760.84      2362059.68     13221583.73
      2361781.86     13221383.81
#Sta/Elev= 30
  4726.7  128.49  4780.8  128.15  4814.9  126.69  4824.9  126.87  4837.7  125.37
  4890.5  123.59    4918  121.68  4928.5  121.69  4942.8  120.28    4956  119.91
  4972.2   117.5  4977.9   112.9  4982.7  110.48  4985.5  109.98  4988.7  110.48
  4999.7  111.26  5008.5  115.76  5015.9  117.44  5033.4   117.6  5088.4  117.78
  5138.8   118.4  5155.3  119.37  5197.7  120.16  5210.6  121.22  5247.6  121.36
  5266.5  122.15  5273.8   122.1  5289.8  123.29  5325.4  124.27  5439.6  129.75
#Mann= 9 ,-1 , 0
  4726.7      .1       0  4942.8     .16       0  4982.7     .07       0
  4988.7     .16       0  5033.4      .1       0  5088.4     .16       0
  5155.3     .05       0  5266.5      .1       0  5273.8     .05       0
Bank Sta=4972.2,5008.5
XS Rating Curve= 0 ,0
Exp/Cntr=0.3,0.1

Type RM Length L Ch R = 1 ,1874    ,364,364,364
BEGIN DESCRIPTION:
BAYOU CREEK TRIB 2 4.0
END DESCRIPTION:
XS GIS Cut Line= 3
      2362572.67     13221539.43      2362187.28     13221096.75
      2361952.88     13221047.27
#Sta/Elev= 30
    4539  127.65  4558.2  127.95  4572.5  126.88  4586.7  127.02  4615.2  125.93
  4657.9  123.19  4707.3  122.54  4714.8  121.65  4761.8  120.33  4813.6  118.11
  4820.8  117.23  4877.2  115.76  4884.9  114.93  4934.2  113.39  4983.6  113.47
  4997.8  104.94  5009.1  104.77  5011.8  104.27  5015.1  104.77  5019.7  114.75
    5033  116.12  5038.8  117.83    5069  120.36  5118.4  122.95  5122.6  123.65
  5145.2  124.16  5217.5  127.71    5290  129.26  5329.9   130.3  5365.5  130.44
#Mann= 6 ,-1 , 0
    4539      .1       0  4761.8     .16       0  5009.1     .07       0
  5015.1     .16       0  5038.8      .1       0    5290     .05       0
Bank Sta=4983.6,5019.7
XS Rating Curve= 0 ,0
Exp/Cntr=0.3,0.1

Type RM Length L Ch R = 1 ,1510    ,519,519,519
BEGIN DESCRIPTION:
BAYOU CREEK TRIB 2 3.0
END DESCRIPTION:
XS GIS Cut Line= 3
      2362778.43     13221213.95      2362646.62     13221086.12
      2362187.73     13220996.86
#Sta/Elev= 30
    4730  124.94  4763.8  124.05  4806.2  121.81  4841.7  120.44  4848.7   120.6
  4898.2  118.02  4912.6  117.67    4937  116.06  4943.1  114.71  4953.2  113.89
  4963.4  111.91  4973.6  111.29  4983.5  108.83  4988.3  106.29    4991  102.32
  4993.7  101.82    4997  102.32  5004.2  110.41  5014.4  111.04  5055.1  111.12
  5075.5  112.28    5083  111.77  5148.7  112.74    5157  113.45    5252  117.29
  5298.5  119.75  5303.6  119.44  5350.2   121.8  5360.7  121.76  5381.1  123.09
#Mann= 5 ,-1 , 0
    4730      .1       0  4912.6     .16       0    4991     .07       0
    4997     .16       0    5083      .1       0
Bank Sta=4973.6,5004.2
XS Rating Curve= 0 ,0
Exp/Cntr=0.3,0.1

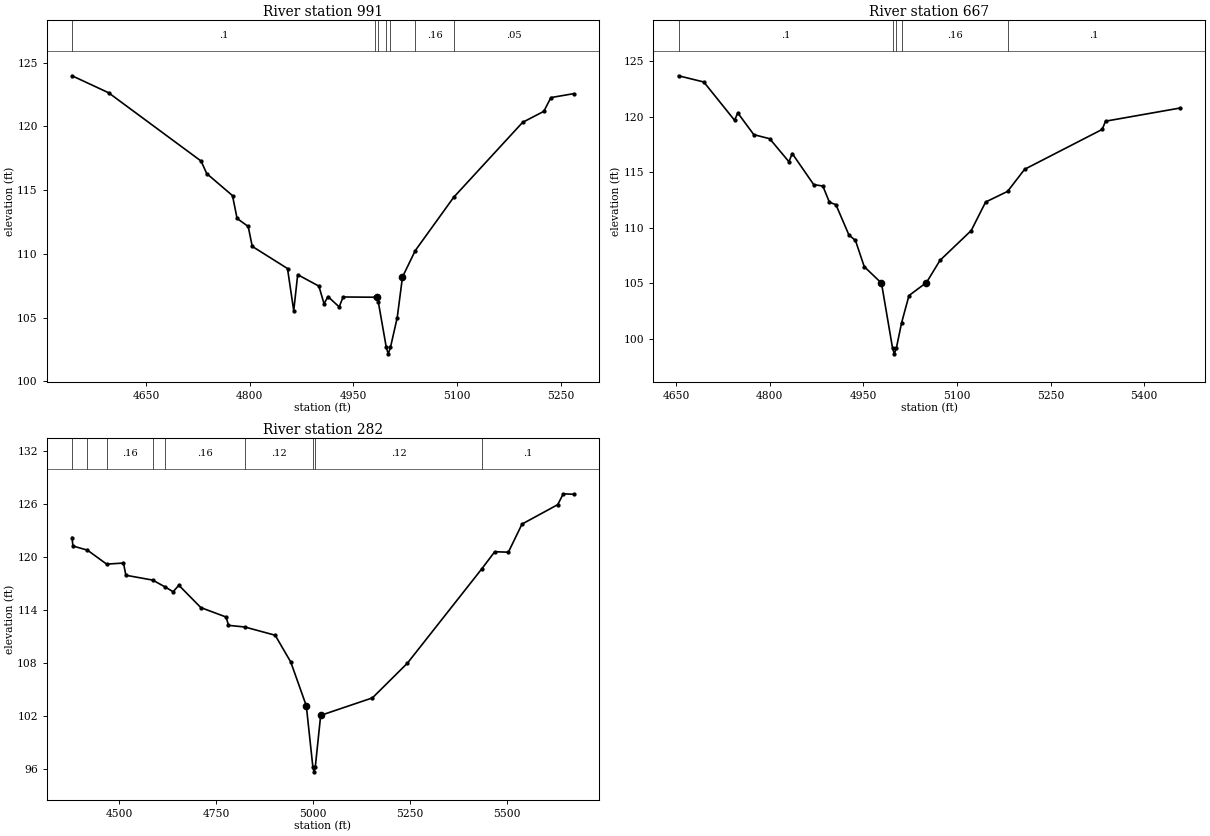
Type RM Length L Ch R = 1 ,991     ,324,324,324
BEGIN DESCRIPTION:
BAYOU CREEK TRIB 2 2.0
END DESCRIPTION:
XS GIS Cut Line= 3
      2362846.15     13221141.06      2362637.26     13220753.01
       2362695.1     13220474.35
#Sta/Elev= 30
  4543.3  123.97    4596  122.64  4729.8  117.28  4737.9   116.3  4775.2  114.57
  4781.8  112.78  4797.9  112.15  4803.7  110.59  4854.7  108.85  4863.7  105.54
  4869.4  108.37  4900.1  107.47  4907.5  106.09  4913.2  106.65  4929.4  105.84
  4935.1  106.62  4981.3   106.6    4984   106.6  4986.1  106.19  4997.5  102.66
  5000.3  102.16  5003.5  102.66  5013.3  105.01  5020.9  108.19  5039.4  110.26
  5094.9  114.44  5194.6  120.32  5225.2  121.18  5235.4  122.26  5268.6  122.57
#Mann= 7 ,-1 , 0
  4543.3      .1       0  4981.3     .16       0  4986.1      .1       0
  4997.5     .07       0  5003.5      .1       0  5039.4     .16       0
  5094.9     .05       0
Bank Sta=4984,5020.9
XS Rating Curve= 0 ,0
Exp/Cntr=0.3,0.1

Type RM Length L Ch R = 1 ,667     ,385,385,385
BEGIN DESCRIPTION:
Mapping XS 8ca8ecfa
END DESCRIPTION:
XS GIS Cut Line= 3
      2362892.13     13221115.01      2362965.06     13220910.12
      2362798.41     13220347.67
#Sta/Elev= 30
  4653.7   123.7  4694.2  123.14  4743.4   119.7  4748.7  120.35  4774.3   118.4
  4799.8  118.03  4830.6  115.96  4835.9   116.7  4870.3   113.9    4885  113.77
  4895.4  112.32  4905.9  112.09  4926.7  109.37  4937.2  108.87  4951.3  106.51
  4978.9  105.03  4996.7   99.16  4999.5   98.66  5002.7   99.16  5011.2  101.47
    5023  103.91    5051  105.08  5072.7  107.08  5122.7  109.76  5145.8  112.33
    5181  113.29  5208.3  115.28  5332.6  118.87  5337.9  119.61  5457.8   120.8
#Mann= 5 ,-1 , 0
  4653.7      .1       0  4996.7     .07       0  5002.7      .1       0
  5011.2     .16       0    5181      .1       0
Bank Sta=4978.9,5051
XS Rating Curve= 0 ,0
Exp/Cntr=0.3,0.1

Type RM Length L Ch R = 1 ,282     ,0,0,0
BEGIN DESCRIPTION:
BAYOU CREEK TRIB 2 1.0
END DESCRIPTION:
XS GIS Cut Line= 4
      2362982.43     13221194.84      2363281.03     13220774.71
      2363253.25     13220351.09      2363021.64     13220084.91
#Sta/Elev= 30
  4379.3  122.22  4381.4  121.26  4418.9  120.79  4468.3  119.21  4511.8  119.33
  4517.9  117.95  4587.1   117.4    4620   116.6  4639.7  116.08  4654.4  116.82
    4711  114.29  4776.2  113.22  4782.3  112.28  4824.6  112.09  4902.6  111.16
  4942.7  108.13  4982.8  103.17  4999.8    96.2  5002.6    95.7  5005.8    96.2
  5019.8  102.09  5153.1  104.07  5243.3     108  5435.5  118.71  5468.2  120.61
  5503.4  120.56  5538.5  123.74  5630.6  125.94  5644.8  127.17  5672.1  127.11
#Mann= 9 ,-1 , 0
  4379.3      .1       0  4418.9     .05       0  4468.3     .16       0
  4587.1      .1       0    4620     .16       0  4824.6     .12       0
  4999.8     .07       0  5005.8     .12       0  5435.5      .1       0
Bank Sta=4982.8,5019.8
XS Rating Curve= 0 ,0
Exp/Cntr=0.3,0.1

Chan Stop Cuts=-1
Use User Specified Reach Order=0
Composite Channel Slope=5