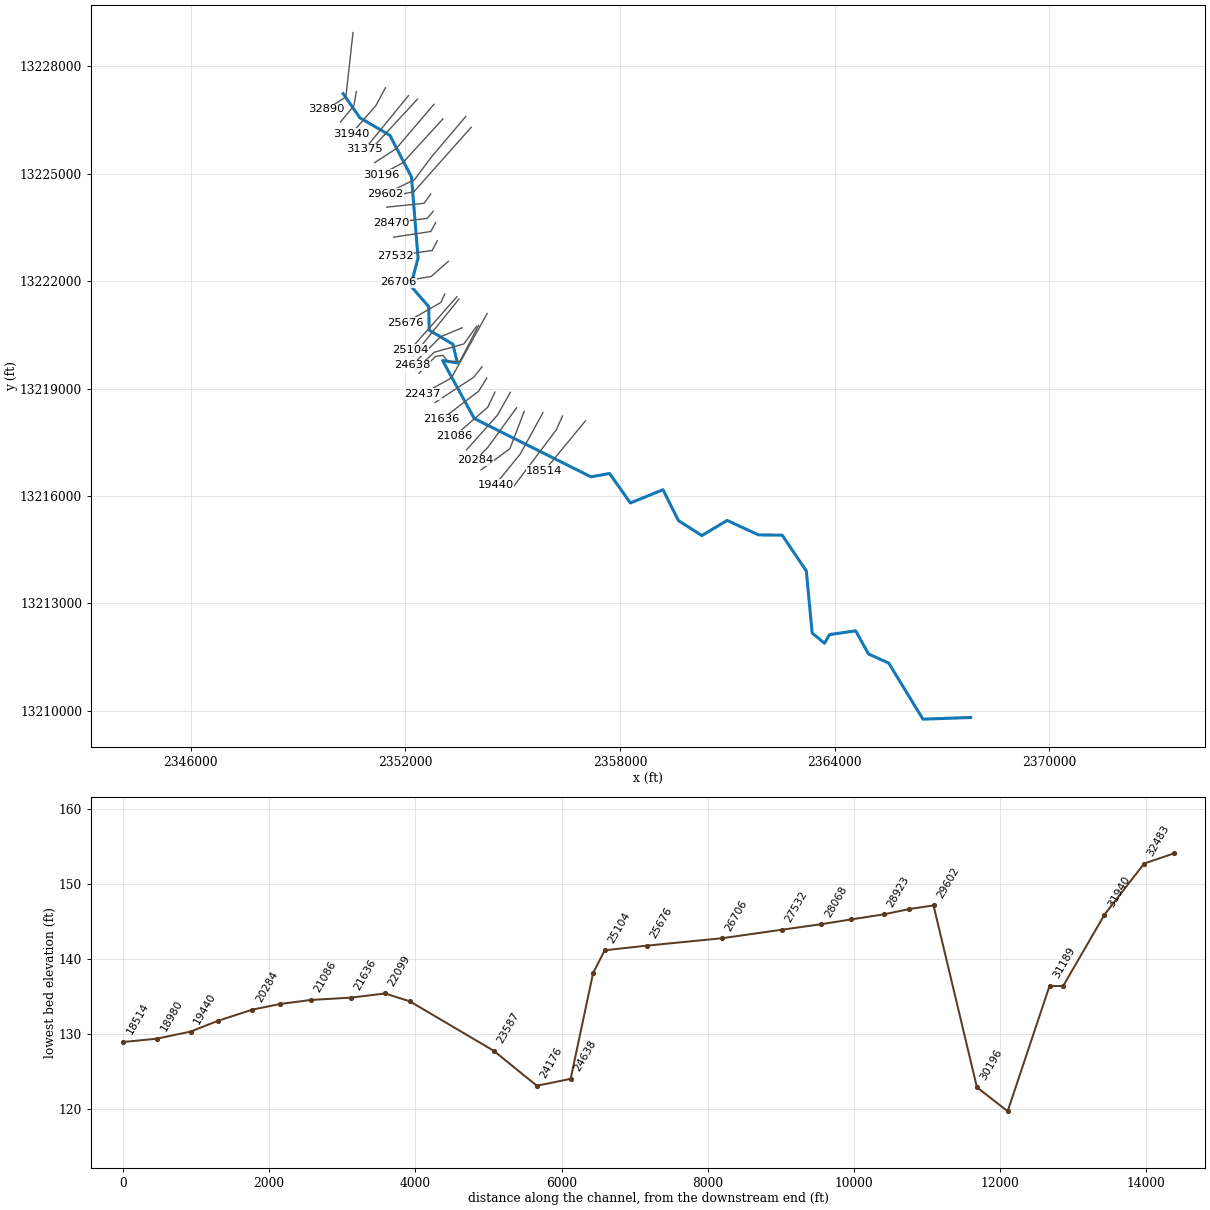
--- BAYOU CREEK TRIB 3.prj (project) ---

Proj Title=BAYOU CREEK TRIB 3 Base Level Engineering
Current Plan=p01
Default Exp/Contr=0.3,0.1
English Units
Geom File=g01
Flow File=f01
Plan File=p01
Y Axis Title=Elevation
X Axis Title(PF)=Main Channel Distance
X Axis Title(XS)=Station
BEGIN DESCRIPTION:
BAYOU CREEK TRIB 3
END DESCRIPTION:
DSS Export Rating Curves= 0
DSS Export Rating Curve Sorted= 0
DSS Export Volume Flow Curves= 0
DXF OffsetX= 0
DXF OffsetY= 0
DXF ScaleX= 1
DXF ScaleY= 10

--- BAYOU CREEK TRIB 3.p01 (plan) ---

Plan Title=Multiple Run
Short Identifier=Multiple
Geom File=g01
Flow File=f01
Subcritical Flow
K Sum by GR= 0
Std Step Tol= 0.01
Critical Tol= 0.01
Num of Std Step Trials= 20
Max Error Tol= 0.3
Flow Tol Ratio= 0.001
Split Flow NTrial= 30
Split Flow Tol= 0.02
Split Flow Ratio= 0.02
Log Output Level= 0
Friction Slope Method= 1
Unsteady Friction Slope Method= 2
Unsteady Bridges Friction Slope Method= 1
Parabolic Critical Depth
Global Vel Dist=  1 , 1 , 1
Global Log Level= 0
CheckData=True
Encroach Param= -1, 0, 0, 0
BEGIN DESCRIPTION:
Multiple Run
END DESCRIPTION:

--- BAYOU CREEK TRIB 3.f01 (steady flow) ---

Flow Title=Multiple
Number of Profiles=7
Profile Names=10-year,25-year,50-year,1pct_min,100-year,1pct_plu,500-year
River Rch & RM= BAYOU CREEK TRIB,Reach-1,32890
     538     723     868     759    1027    1389    1442
River Rch & RM= BAYOU CREEK TRIB,Reach-1,24945
     643     873    1056     929    1256    1699    1786
River Rch & RM= BAYOU CREEK TRIB,Reach-1,24638
     902    1250    1534    1368    1850    2502    2705
River Rch & RM= BAYOU CREEK TRIB,Reach-1,15011
    1136    1600    1984    1788    2418    3270    3608
River Rch & RM= BAYOU CREEK TRIB,Reach-1,6482
    1225    1730    2149    1941    2625    3550    3931
Boundary for River Rch & Prof#=BAYOU CREEK TRIB,Reach-1,1
Up Type=0
Dn Type=3
Dn Slope=0.005
Boundary for River Rch & Prof#=BAYOU CREEK TRIB,Reach-1,2
Up Type=0
Dn Type=3
Dn Slope=0.005
Boundary for River Rch & Prof#=BAYOU CREEK TRIB,Reach-1,3
Up Type=0
Dn Type=3
Dn Slope=0.005
Boundary for River Rch & Prof#=BAYOU CREEK TRIB,Reach-1,4
Up Type=0
Dn Type=3
Dn Slope=0.005
Boundary for River Rch & Prof#=BAYOU CREEK TRIB,Reach-1,5
Up Type=0
Dn Type=3
Dn Slope=0.005
Boundary for River Rch & Prof#=BAYOU CREEK TRIB,Reach-1,6
Up Type=0
Dn Type=3
Dn Slope=0.005
Boundary for River Rch & Prof#=BAYOU CREEK TRIB,Reach-1,7
Up Type=0
Dn Type=3
Dn Slope=0.005

--- BAYOU CREEK TRIB 3.g01 (geometry) ---

Geom Title=Existing Conditions
Program Version=4.10

River Reach=BAYOU CREEK TRIB,Reach-1
Reach XY= 30
      2350263.97      13227236.9      2350730.77     13226563.14
      2351568.13     13226076.33      2352171.48     13224912.02
      2352355.83     13222646.91       2352150.5     13221868.08
       2352654.2     13221285.29      2352665.81     13220630.29
       2353327.5     13220239.45      2353456.41     13219714.71
      2353039.98     13219782.88      2353925.41     13218161.58
      2357184.98     13216531.59      2357706.65     13216625.22
      2358288.88     13215800.95      2359200.25     13216171.66
      2359634.37     13215306.11      2360284.98     13214890.92
      2360993.13     13215313.47      2361868.84     13214909.55
      2362530.28     13214901.48      2363205.69     13213900.92
      2363368.03      13212167.6      2363712.82     13211881.19
      2363854.96     13212123.04      2364584.42     13212229.03
      2364943.06     13211581.29      2365507.72     13211326.75
      2366464.49     13209760.21      2367797.72     13209806.85

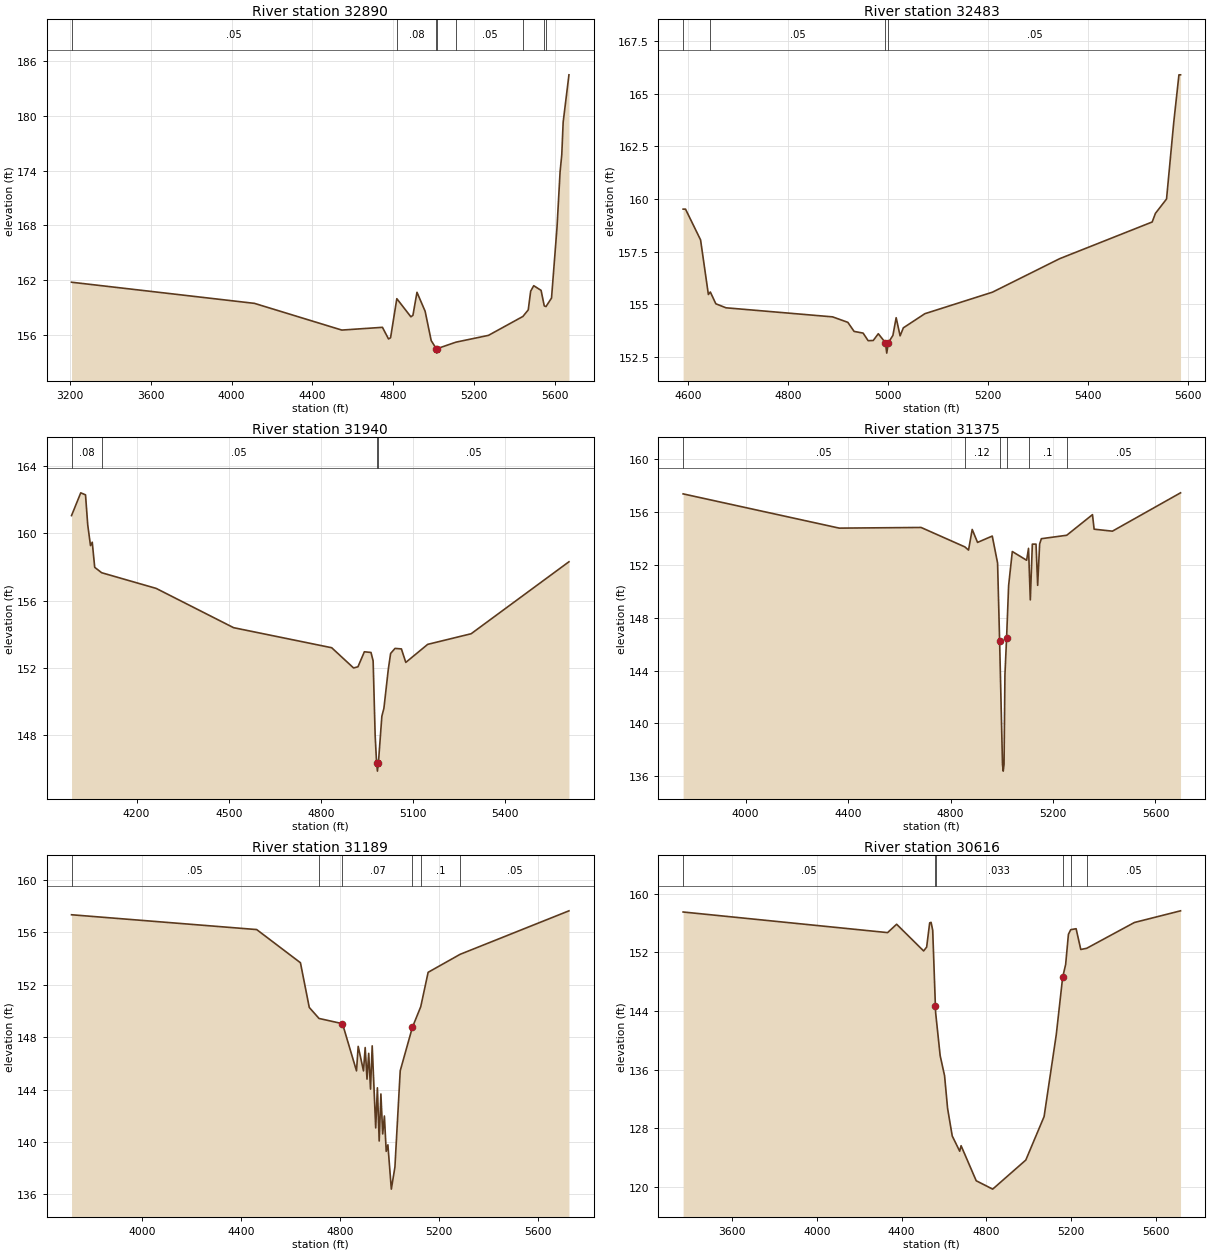
Type RM Length L Ch R = 1 ,32890   ,407,407,407
BEGIN DESCRIPTION:
BAYOU CREEK TRIB 3 56.0
END DESCRIPTION:
XS GIS Cut Line= 3
      2350537.73      13228946.9      2350337.72     13227146.85
      2349787.76     13226796.88
#Sta/Elev= 30
  3207.7  161.79  4113.3  159.48  4545.9  156.56  4747.2  156.86  4777.3  155.59
  4787.4  155.72  4818.4  159.99    4888  158.01  4898.1  158.17  4918.2  160.69
  4958.5  158.62  4988.6  155.41  5013.3  154.54  5016.1  154.04  5019.3  154.54
  5111.3  155.24    5272  155.98  5442.8  158.05  5469.2  158.77  5481.1  160.81
  5496.3  161.41  5532.7   160.9  5548.5   159.2    5557  159.13  5584.4  160.06
  5611.5  167.76  5626.7  173.83  5635.2  175.74    5642  179.28  5670.7  184.46
#Mann= 8 ,-1 , 0
  3207.7     .05       0  4818.4     .08       0  5013.3     .07       0
  5019.3     .08       0  5111.3     .05       0  5442.8      .1       0
  5548.5     .05       0    5557     .08       0
Bank Sta=5013.3,5019.3
XS Rating Curve= 0 ,0
Exp/Cntr=0.3,0.1

Type RM Length L Ch R = 1 ,32483   ,543,543,543
BEGIN DESCRIPTION:
BAYOU CREEK TRIB 3 55.0
END DESCRIPTION:
XS GIS Cut Line= 3
      2350631.55     13227301.27      2350560.56     13226898.17
      2350187.72     13226446.86
#Sta/Elev= 30
  4590.7  159.52  4595.5  159.52  4625.6  158.06  4641.2  155.47  4645.1  155.59
  4656.1  155.03  4676.4  154.84  4889.6  154.41  4920.1  154.15  4932.6  153.72
  4950.6  153.64  4960.7  153.28  4970.9  153.29    4981  153.61  4995.1  153.19
  4997.9  152.69  5001.1  153.19  5010.2  153.53  5016.7  154.37  5024.6  153.51
  5031.1  153.89  5074.1  154.56  5209.2  155.58  5343.7  157.17  5528.7  158.91
  5535.2  159.32  5557.4     160  5571.7  163.61  5582.2  165.89  5585.4  165.89
#Mann= 4 ,-1 , 0
  4590.7     .08       0  4645.1     .05       0  4995.1    .035       0
  5001.1     .05       0
Bank Sta=4995.1,5001.1
XS Rating Curve= 0 ,0
Exp/Cntr=0.3,0.1

Type RM Length L Ch R = 1 ,31940   ,565,565,565
BEGIN DESCRIPTION:
BAYOU CREEK TRIB 3 54.0
END DESCRIPTION:
XS GIS Cut Line= 3
      2351443.46      13227403.3      2351176.01     13226903.73
      2350483.31     13226112.06
#Sta/Elev= 30
  3988.3  161.04  4018.3  162.39  4033.8  162.27    4041  160.49    4050  159.26
  4055.7  159.46  4063.7  157.97  4086.3  157.65  4263.7  156.72  4515.6  154.39
  4834.9   153.2  4906.1     152  4920.3  152.07  4941.2  152.96  4962.7  152.92
  4969.7  152.42  4976.3  147.99  4980.9  146.38  4983.7  145.88  4986.9  146.38
  4998.1  149.14  5004.8  149.61    5019  151.91  5026.6  152.86  5040.9  153.16
  5061.7  153.13    5076  152.33  5147.2   153.4  5288.6  154.03  5606.9   158.3
#Mann= 4 ,-1 , 0
  3988.3     .08       0  4086.3     .05       0  4980.9    .035       0
  4986.9     .05       0
Bank Sta=4980.9,4986.9
XS Rating Curve= 0 ,0
Exp/Cntr=0.3,0.1

Type RM Length L Ch R = 1 ,31375   ,186,186,186
BEGIN DESCRIPTION:
BAYOU CREEK TRIB 3 53.0
END DESCRIPTION:
XS GIS Cut Line= 2
      2352087.47     13227184.97      2350859.14     13225680.79
#Sta/Elev= 30
  3755.8  157.36  4365.4  154.77  4684.8  154.82  4855.8  153.35  4870.1  153.11
  4884.4  154.67  4905.3  153.69  4962.7  154.17  4983.5  152.13  4991.4  146.25
  5002.7  136.89  5005.5  136.39  5008.7  136.89  5012.2  143.68  5018.7  146.49
  5026.6  150.43    5041     153  5096.9  152.34  5104.3  153.24  5111.3  149.34
  5119.2  153.56  5133.6  153.56    5140  150.44  5147.7  153.57  5154.4  153.97
  5253.4  154.23    5354  155.79  5360.4  154.69  5431.8  154.54  5697.8  157.44
#Mann= 6 ,-1 , 0
  3755.8     .05       0  4855.8     .12       0  4991.4     .07       0
  5018.7     .12       0  5104.3      .1       0  5253.4     .05       0
Bank Sta=4991.4,5018.7
XS Rating Curve= 0 ,0
Exp/Cntr=0.3,0.1

Type RM Length L Ch R = 1 ,31189   ,573,573,573
BEGIN DESCRIPTION:
BAYOU CREEK TRIB 3 52.0
END DESCRIPTION:
XS GIS Cut Line= 2
      2352337.44     13227085.99       2350972.9     13225606.87
#Sta/Elev= 30
  3714.2  157.33  4463.3   156.2  4640.3  153.67    4676  150.26  4715.4  149.42
  4810.4  149.02  4867.1  145.42  4873.9  147.29  4895.4  145.42  4902.2   147.2
  4909.6  144.79  4916.4  146.76  4923.8  144.03  4930.6  147.33  4944.8  141.07
  4951.6  144.13  4958.9  140.07  4965.8  143.66  4973.1  140.61  4979.9  141.98
  4987.3  139.28  4994.1  139.78    5008   136.4  5022.5  138.08    5044  145.43
  5093.3  148.75  5126.9  150.31  5156.9  152.94  5286.1  154.31  5726.6  157.63
#Mann= 6 ,-1 , 0
  3714.2     .05       0  4715.4      .1       0  4810.4     .07       0
  5093.3     .07       0  5126.9      .1       0  5286.1     .05       0
Bank Sta=4810.4,5093.3
XS Rating Curve= 0 ,0
Exp/Cntr=0.3,0.1

Type RM Length L Ch R = 1 ,30616   ,420,420,420
BEGIN DESCRIPTION:
BAYOU CREEK TRIB 3 51.0
END DESCRIPTION:
XS GIS Cut Line= 3
      2352800.99     13226943.35      2351737.72     13225696.85
      2351142.31     13225312.08
#Sta/Elev= 30
  3369.2  157.51    4334   154.7  4376.7  155.84  4504.2   152.2  4518.4  152.73
  4532.7  156.03  4539.3   156.1    4547  155.02  4559.6  144.73  4560.7  143.81
  4582.1  137.94    4603  135.18  4617.2  130.73  4639.2  126.97  4674.4   124.9
  4680.9  125.65  4752.3  120.87    4830  119.73  4986.2  123.69  5072.6  129.62
    5130  140.78  5160.3  148.63  5174.3  150.35  5187.4  154.47  5198.4   155.1
  5223.7  155.23  5245.7   152.4  5273.5  152.56  5498.8  156.08  5716.5  157.67
#Mann= 6 ,-1 , 0
  3369.2     .05       0  4559.6     .07       0  4560.7    .033       0
  5160.3     .05       0  5198.4      .1       0  5273.5     .05       0
Bank Sta=4559.6,5160.3
XS Rating Curve= 0 ,0
Exp/Cntr=0.3,0.1

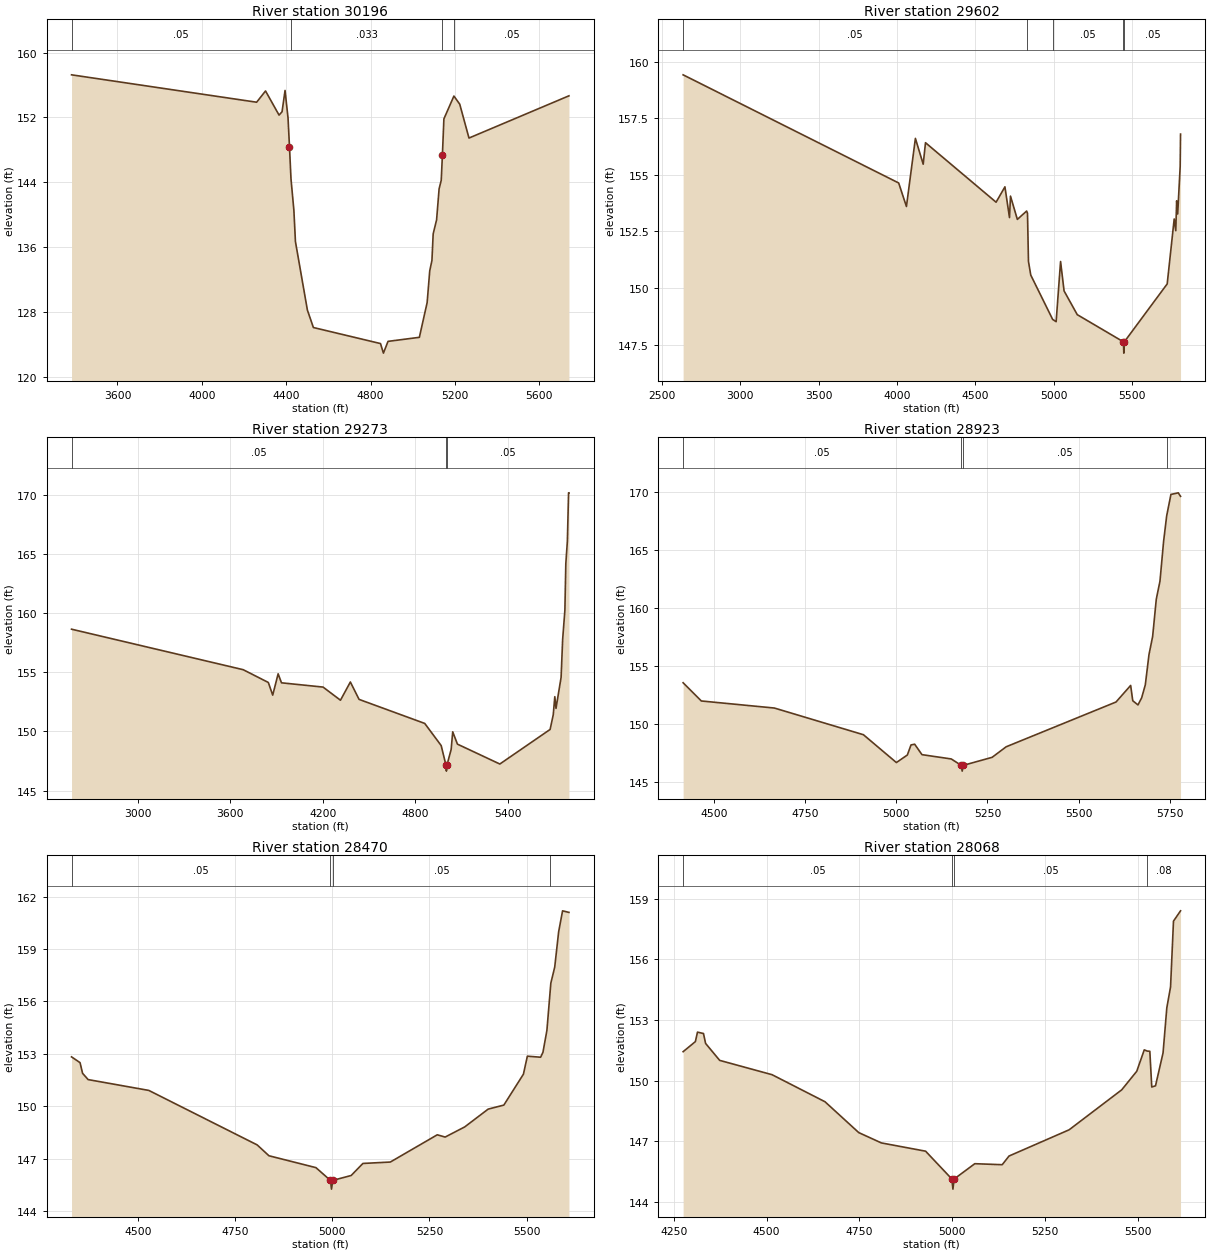
Type RM Length L Ch R = 1 ,30196   ,594,594,594
BEGIN DESCRIPTION:
BAYOU CREEK TRIB 3 50.0
END DESCRIPTION:
XS GIS Cut Line= 3
        2353051.     13226533.63      2351922.24      13225303.2
      2351314.93      13224978.1
#Sta/Elev= 30
  3382.3  157.25    4260  153.87  4302.2  155.26  4366.3  152.28  4380.5  152.69
  4394.7  155.32  4408.9  151.92  4415.7   148.4  4422.9  144.41  4436.6  140.53
    4444  136.67  4500.7  128.22  4529.1  126.07  4847.3  124.09  4861.2  122.91
    4883  124.36  5031.6  124.86  5068.5  129.15  5080.8  133.07  5091.2  134.34
  5097.1  137.63  5113.3  139.36  5125.2  143.18  5135.3  144.24  5140.9  147.37
  5147.9  151.81  5195.4  154.63    5223  153.63  5266.9  149.45  5740.9  154.66
#Mann= 4 ,-1 , 0
  3382.3     .05       0  4422.9    .033       0  5140.9     .07       0
  5195.4     .05       0
Bank Sta=4415.7,5140.9
XS Rating Curve= 0 ,0
Exp/Cntr=0.3,0.1

Type RM Length L Ch R = 1 ,29602   ,329,329,329
BEGIN DESCRIPTION:
BAYOU CREEK TRIB 3 49.0
END DESCRIPTION:
XS GIS Cut Line= 4
      2353689.92     13226603.11      2352724.62      13225464.2
      2352259.34      13224839.2      2351451.44     13224440.41
#Sta/Elev= 30
  2636.4  159.42  4011.5  154.64  4060.9   153.6  4118.1  156.61  4167.9  155.47
  4182.5  156.42  4632.9  153.79  4689.2  154.47  4718.4  153.11  4724.7  154.06
  4768.5  153.03  4827.7   153.4  4833.2   153.3  4839.4  151.17    4854  150.57
  4993.7  148.61  5015.9  148.51  5044.2  151.17  5066.5  149.87  5150.6  148.82
    5445  147.62  5447.7  147.12    5451  147.62  5724.4  150.18    5769  153.05
  5779.1  152.53  5784.7  153.85  5791.3  153.27  5807.2  155.37  5809.5   156.8
#Mann= 5 ,-1 , 0
  2636.4     .05       0  4827.7      .1       0  4993.7     .05       0
    5445    .035       0    5451     .05       0
Bank Sta=5445,5451
XS Rating Curve= 0 ,0
Exp/Cntr=0.3,0.1

Type RM Length L Ch R = 1 ,29273   ,350,350,350
BEGIN DESCRIPTION:
BAYOU CREEK TRIB 3 48.0
END DESCRIPTION:
XS GIS Cut Line= 3
      2353837.69     13226296.82      2352237.72     13224496.85
      2351437.73     13224346.86
#Sta/Elev= 30
  2572.2  158.63  3683.9  155.21    3847  154.13  3875.4  153.06  3910.5  154.86
  3932.3   154.1  4201.5  153.74  4314.4  152.63  4378.4  154.17  4434.8   152.7
  4860.1  150.67  4966.7   148.8  4997.8  147.14  5000.6  146.64  5003.8  147.14
  5031.3  148.47  5041.5  149.96    5072  148.92  5346.7  147.24  5672.3  150.16
  5692.7   151.4  5702.8  152.93  5710.5  151.94  5743.5  154.56  5753.7  157.79
  5768.1  160.24  5774.1  164.16  5784.2  166.07  5791.9  170.15  5794.4  170.15
#Mann= 3 ,-1 , 0
  2572.2     .05       0  4997.8    .035       0  5003.8     .05       0
Bank Sta=4997.8,5003.8
XS Rating Curve= 0 ,0
Exp/Cntr=0.3,0.1

Type RM Length L Ch R = 1 ,28923   ,453,453,453
BEGIN DESCRIPTION:
BAYOU CREEK TRIB 3 47.0
END DESCRIPTION:
XS GIS Cut Line= 3
      2352710.61     13224434.31      2352521.32     13224175.61
      2351481.48     13224068.48
#Sta/Elev= 30
  4414.3  153.55  4464.2  151.98    4665  151.37  4909.4  149.07  4999.9  146.67
    5030  147.32  5040.1  148.19  5050.1  148.25  5070.2  147.35  5150.6  146.98
  5177.8  146.43  5180.6  145.93  5183.8  146.43  5262.8  147.12  5301.4  148.03
    5603  151.89  5643.2  153.32    5649     152  5663.3  151.64  5673.4  152.25
  5683.5  153.38  5693.5  155.97  5703.6  157.55  5713.6  160.76  5723.7  162.31
  5733.7  165.75  5742.1  167.94  5753.8  169.79  5773.9  169.93  5780.2  169.63
#Mann= 4 ,-1 , 0
  4414.3     .05       0  5177.8    .035       0  5183.8     .05       0
  5742.1     .08       0
Bank Sta=5177.8,5183.8
XS Rating Curve= 0 ,0
Exp/Cntr=0.3,0.1

Type RM Length L Ch R = 1 ,28470   ,402,402,402
BEGIN DESCRIPTION:
BAYOU CREEK TRIB 3 46.0
END DESCRIPTION:
XS GIS Cut Line= 3
      2352780.02      13223954.8      2352609.65     13223752.88
      2351601.42     13223633.16
#Sta/Elev= 30
  4329.3  152.82  4351.2  152.49  4357.7  151.88    4372  151.52  4528.1   150.9
  4806.9  147.78  4837.1  147.16    4958  146.48  4995.2  145.75    4998  145.25
  5001.2  145.75  5048.6  146.03  5078.8  146.72  5149.3   146.8  5270.1  148.36
  5290.3  148.23  5340.6  148.81    5401  149.83  5441.3  150.06  5491.7  151.83
  5501.8  152.86    5536   152.8    5542  153.09  5552.1  154.34  5560.2  156.51
  5562.2  157.04  5572.2  157.96  5582.3  159.98  5592.4  161.18  5608.8  161.09
#Mann= 4 ,-1 , 0
  4329.3     .05       0  4995.2    .035       0  5001.2     .05       0
  5560.2     .08       0
Bank Sta=4995.2,5001.2
XS Rating Curve= 0 ,0
Exp/Cntr=0.3,0.1

Type RM Length L Ch R = 1 ,28068   ,536,536,536
BEGIN DESCRIPTION:
BAYOU CREEK TRIB 3 45.0
END DESCRIPTION:
XS GIS Cut Line= 3
      2352849.42     13223639.33       2352710.6     13223386.94
      2351671.11     13223229.44
#Sta/Elev= 30
  4275.3  151.43  4308.3  151.93    4314   152.4  4330.1  152.33  4335.8  151.84
  4373.7     151  4514.8  150.29  4657.3  148.95  4748.3  147.42    4809  146.91
  4928.2   146.5    4999  145.12  5001.8  144.62    5005  145.12  5060.7  145.88
  5134.5  145.83  5152.9  146.26  5314.7  147.56  5456.3  149.54  5496.8  150.46
    5517  151.52  5525.1  151.46    5532  151.45  5537.2  149.68  5547.3  149.74
  5567.6  151.37  5577.7   153.6  5587.8  154.64  5595.7   157.9  5614.7  158.41
#Mann= 4 ,-1 , 0
  4275.3     .05       0    4999    .035       0    5005     .05       0
  5525.1     .08       0
Bank Sta=4999,5005
XS Rating Curve= 0 ,0
Exp/Cntr=0.3,0.1

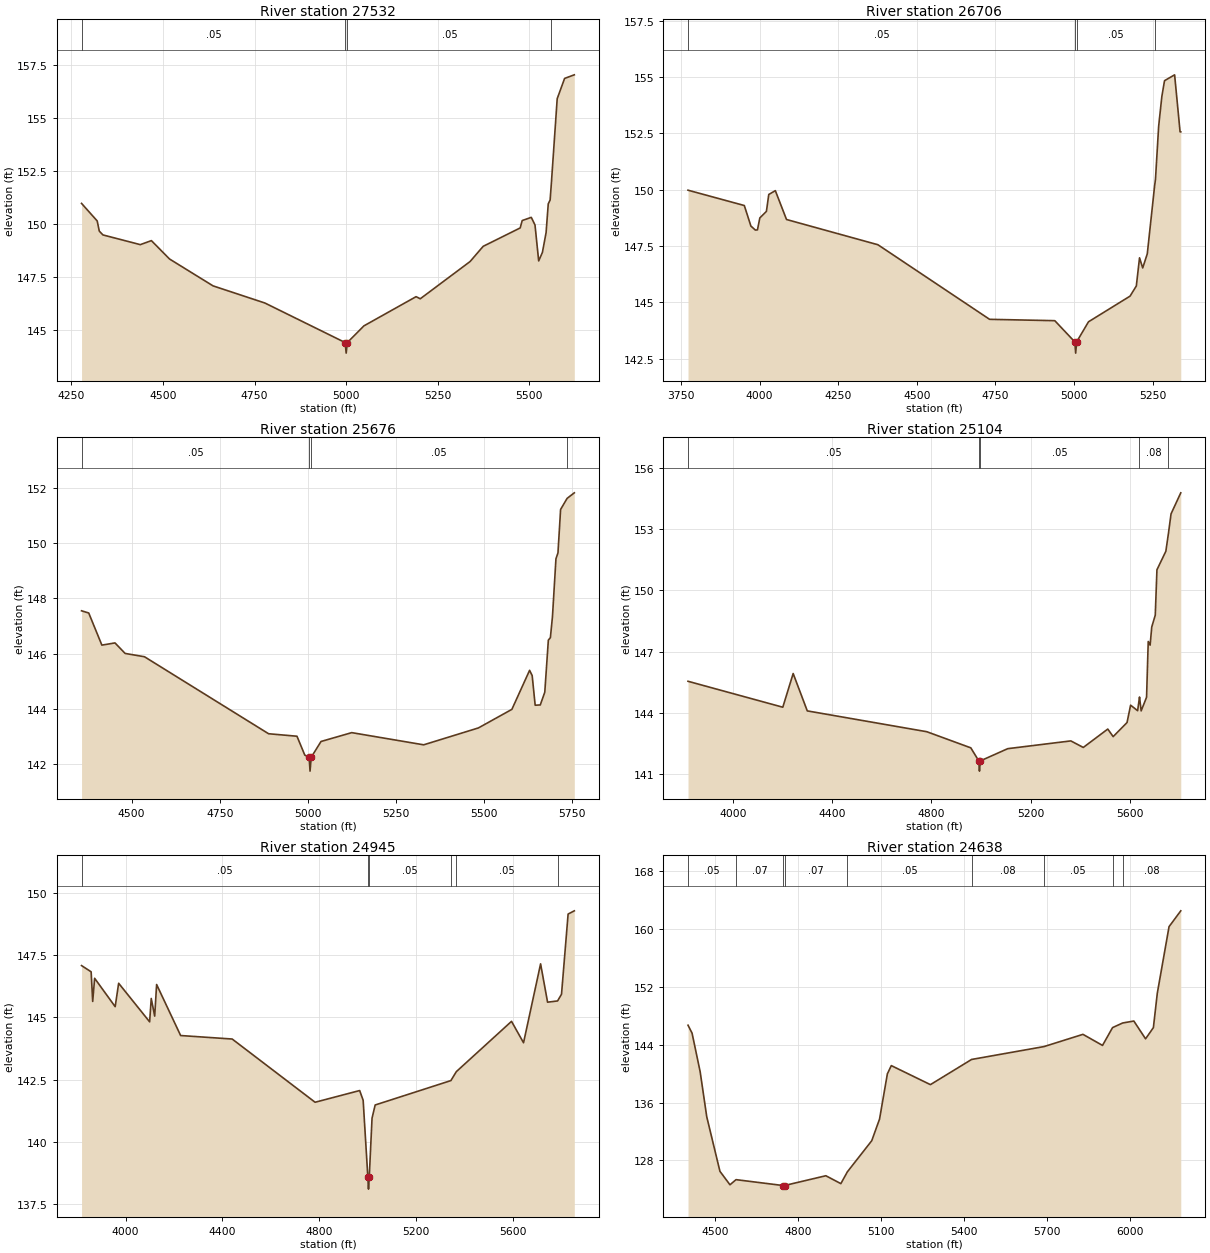
Type RM Length L Ch R = 1 ,27532   ,826,826,826
BEGIN DESCRIPTION:
BAYOU CREEK TRIB 3 44.0
END DESCRIPTION:
XS GIS Cut Line= 3
      2352893.55     13223128.22      2352748.46     13222856.96
      2351721.46     13222712.05
#Sta/Elev= 30
    4278  150.97  4320.7  150.14  4326.4  149.66  4336.3  149.48  4438.3  149.02
  4468.6  149.21  4518.2  148.34  4636.9  147.07  4778.3  146.26  4997.4  144.39
  5000.2  143.89  5003.4  144.39  5048.7  145.18    5191  146.56  5202.4  146.46
  5338.3  148.22  5374.1  148.94  5475.1  149.81  5480.6  150.16  5505.4  150.31
  5515.5  149.95  5525.6  148.25  5535.7  148.65  5545.8  149.59  5551.7  150.95
  5556.8  151.13  5560.3  151.95  5576.1  155.92  5596.3  156.88  5622.8  157.05
#Mann= 4 ,-1 , 0
    4278     .05       0  4997.4    .035       0  5003.4     .05       0
  5560.3     .08       0
Bank Sta=4997.4,5003.4
XS Rating Curve= 0 ,0
Exp/Cntr=0.3,0.1

Type RM Length L Ch R = 1 ,26706   ,1030,1030,1030
BEGIN DESCRIPTION:
BAYOU CREEK TRIB 3 43.0
END DESCRIPTION:
XS GIS Cut Line= 3
      2353202.77     13222554.14      2352723.22     13222131.39
       2351808.4     13221973.66
#Sta/Elev= 30
  3772.2  149.98  3951.3   149.3  3972.2  148.39  3986.5  148.21  3993.1  148.22
  4000.7  148.75  4021.6  149.04  4029.1  149.79    4050  149.96  4085.5  148.68
  4376.3  147.56  4731.6  144.25    4939  144.19  5002.6  143.25  5005.4  142.75
  5008.6  143.25  5046.2  144.14  5178.5  145.28  5198.4  145.73  5208.6  146.98
  5218.7  146.53  5233.3  147.16  5256.6  150.18  5259.3  150.46  5269.5  152.83
  5279.6  154.14  5288.1  154.84  5320.2   155.1  5337.6  152.57  5339.8  152.57
#Mann= 4 ,-1 , 0
  3772.2     .05       0  5002.6    .035       0  5008.6     .05       0
  5256.6     .08       0
Bank Sta=5002.6,5008.6
XS Rating Curve= 0 ,0
Exp/Cntr=0.3,0.1

Type RM Length L Ch R = 1 ,25676   ,572,572,572
BEGIN DESCRIPTION:
BAYOU CREEK TRIB 3 42.0
END DESCRIPTION:
XS GIS Cut Line= 3
      2353101.78     13221639.26      2352994.52     13221405.81
      2352003.95     13220837.97
#Sta/Elev= 30
  4357.7  147.55  4378.1  147.47  4415.4  146.31  4452.6  146.39  4481.4  146.01
  4536.4  145.89  4888.6  143.11  4969.2  143.02  4991.3  142.34  5003.6  142.26
  5006.3  141.76  5009.6  142.26  5037.4  142.83  5124.6  143.15  5328.8  142.71
  5484.2  143.32  5579.2  143.99  5629.5   145.4  5636.8  145.21  5645.3  144.14
  5659.8  144.15  5672.6  144.61  5682.7  146.49  5688.5  146.58  5694.4  147.34
  5704.3  149.43    5710  149.64  5717.5  151.21    5736  151.61  5756.4  151.81
#Mann= 4 ,-1 , 0
  4357.7     .05       0  5003.6    .035       0  5009.6     .05       0
    5736     .08       0
Bank Sta=5003.6,5009.6
XS Rating Curve= 0 ,0
Exp/Cntr=0.3,0.1

Type RM Length L Ch R = 1 ,25104   ,159,159,159
BEGIN DESCRIPTION:
Mapping XS c2f0695d
END DESCRIPTION:
XS GIS Cut Line= 2
      2353439.89      13221563.5      2352125.15     13220074.33
#Sta/Elev= 30
  3819.2  145.55  4201.3  144.28  4243.1  145.93    4300   144.1  4781.9  143.08
  4959.3  142.29  4991.4  141.65  4994.1  141.15  4997.4  141.65  5108.2  142.25
  5362.4  142.63  5412.7  142.31  5511.4  143.21  5533.1  142.84  5589.1  143.53
  5603.4  144.38  5631.8  144.11    5637  144.57  5639.4  144.78    5646   144.1
  5667.8  144.77  5674.5   147.5  5682.1  147.32  5688.7  148.21  5702.9  148.79
  5709.6  151.01  5745.6  151.92  5755.8  152.78  5766.5  153.75  5805.7  154.78
#Mann= 5 ,-1 , 0
  3819.2     .05       0  4991.4    .035       0  4997.4     .05       0
    5637     .08       0  5755.8      .1       0
Bank Sta=4991.4,4997.4
XS Rating Curve= 0 ,0
Exp/Cntr=0.3,0.1

Type RM Length L Ch R = 1 ,24945   ,307,307,307
BEGIN DESCRIPTION:
BAYOU CREEK TRIB 3 41.0
END DESCRIPTION:
XS GIS Cut Line= 2
      2353498.91     13221500.99      2352223.11     13219916.34
#Sta/Elev= 30
  3818.4  147.08    3858  146.83  3864.4  145.64  3872.4  146.57  3957.2  145.43
  3971.6  146.37  4099.5  144.82  4106.1  145.76  4120.4  145.05  4128.3  146.32
  4227.5  144.27  4440.3  144.13  4782.6  141.59  4966.6  142.06    4981  141.67
  5000.3   138.6  5003.1   138.1  5006.3   138.6  5017.7  140.95  5030.6  141.48
  5343.2  142.46  5365.8  142.82  5593.6  144.84  5643.2  143.98  5713.6  147.15
  5742.4  145.61  5783.8  145.66    5800  145.93  5827.2  149.15  5852.8  149.28
#Mann= 6 ,-1 , 0
  3818.4     .05       0  5000.3    .035       0  5006.3     .05       0
  5343.2     .08       0  5365.8     .05       0  5783.8     .08       0
Bank Sta=5000.3,5006.3
XS Rating Curve= 0 ,0
Exp/Cntr=0.3,0.1

Type RM Length L Ch R = 1 ,24638   ,462,462,462
BEGIN DESCRIPTION:
BAYOU CREEK TRIB 3 40.0
END DESCRIPTION:
XS GIS Cut Line= 3
      2353587.73     13220696.86      2352987.72     13220446.85
      2352187.71     13219646.84
#Sta/Elev= 30
  4402.5  146.69  4417.1   145.6  4446.4  140.26  4470.2  134.04  4517.9   126.5
  4554.2  124.64  4576.1  125.35  4745.6  124.54  4748.4  124.04  4751.6  124.54
  4900.8  125.89    4955   124.8  4978.6  126.43  5066.7  130.73  5094.9  133.72
  5123.2  139.97  5137.4  141.11  5278.8  138.48  5427.7  141.96  5689.6  143.74
  5830.3  145.43    5901   143.9  5937.2  146.36  5973.8     147  6014.2  147.27
  6056.6  144.81  6084.9  146.36    6099   151.1  6141.5  160.31  6183.9   162.5
#Mann= 9 ,-1 , 0
  4402.5     .05       0  4576.1     .07       0  4745.6    .035       0
  4751.6     .07       0  4978.6     .05       0  5427.7     .08       0
  5689.6     .05       0  5937.2      .1       0  5973.8     .08       0
Bank Sta=4745.6,4751.6
XS Rating Curve= 0 ,0
Exp/Cntr=0.3,0.1

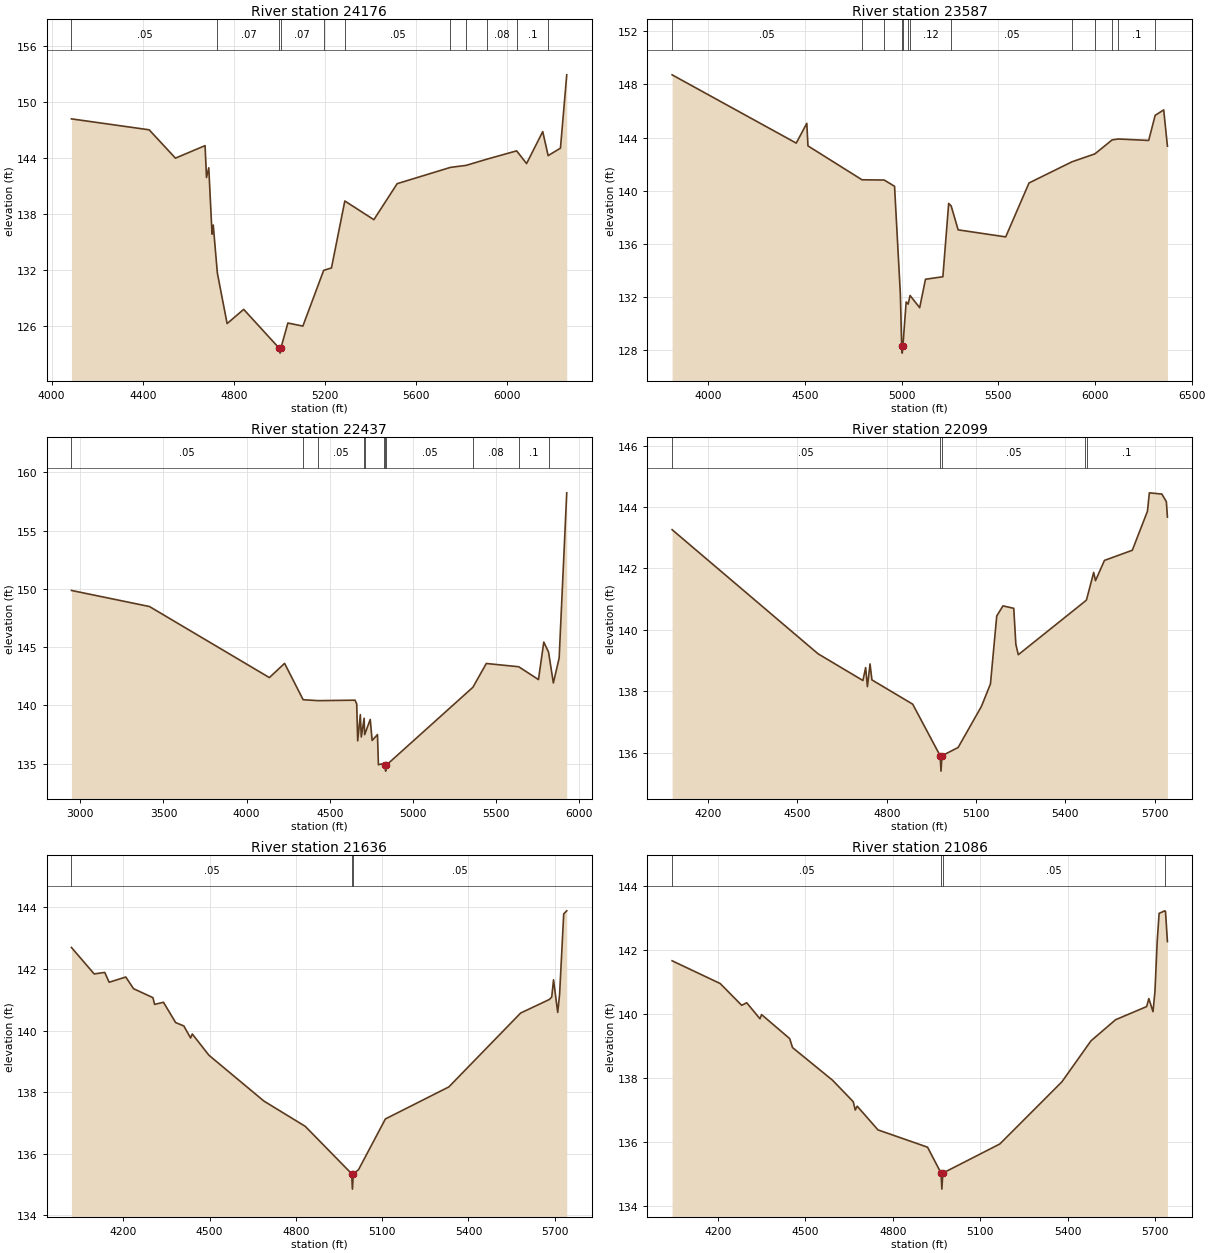
Type RM Length L Ch R = 1 ,24176   ,589,589,589
BEGIN DESCRIPTION:
BAYOU CREEK TRIB 3 39.0
END DESCRIPTION:
XS GIS Cut Line= 4
      2353988.48     13220733.61      2353637.72     13220246.85
      2352811.43      13220014.9      2352287.11     13219528.77
#Sta/Elev= 30
  4087.1  148.17  4428.2     147  4543.5  143.97  4673.5  145.31  4679.7   141.9
  4689.7  142.94  4704.1  135.84  4709.3  136.82  4727.4  131.68  4770.2  126.28
  4842.9   127.8  4999.7  123.62  5002.5  123.12  5005.7  123.62  5036.8  126.34
  5102.5  126.01  5193.8  131.97    5228  132.23  5286.6  139.39  5414.1  137.39
  5516.2  141.24  5749.8  142.98  5819.3   143.2  5910.1  143.86  6040.5  144.75
  6084.1  143.39    6155  146.81  6178.7  144.24  6232.7  145.04  6260.3  152.88
#Mann= 11 ,-1 , 0
  4087.1     .05       0  4727.4     .07       0  4999.7     .07       0
  5005.7     .07       0  5193.8     .12       0  5286.6     .05       0
  5749.8     .08       0  5819.3     .05       0  5910.1     .08       0
  6040.5      .1       0  6178.7     .08       0
Bank Sta=4999.7,5005.7
XS Rating Curve= 0 ,0
Exp/Cntr=0.3,0.1

Type RM Length L Ch R = 1 ,23587   ,1150,1150,1150
BEGIN DESCRIPTION:
Mapping XS 29a23b31
END DESCRIPTION:
XS GIS Cut Line= 6
      2354047.53     13220764.87      2353523.23     13219757.95
      2353186.43     13219754.48      2353057.96     13219924.62
      2352846.15     13219900.31      2352381.82     13219425.59
#Sta/Elev= 30
  3812.1  148.72  4454.3  143.58  4508.9  145.07    4515  143.37  4794.3  140.82
  4909.2   140.8  4962.9  140.33  4992.9  132.23  4999.9  128.27  5002.6  127.77
  5005.9  128.27  5022.9  131.62  5033.2  131.46  5043.1  132.11  5092.9  131.19
  5122.9  133.33  5212.9  133.52  5242.9  139.04  5255.9  138.85  5291.9  137.05
  5537.9  136.52  5658.6  140.58  5880.4  142.17  5999.4  142.77  6088.4  143.82
  6120.7  143.89  6277.6  143.78  6311.2  145.67  6355.4  146.08  6374.6  143.35
#Mann= 13 ,-1 , 0
  3812.1     .05       0  4794.3     .07       0  4909.2     .05       0
  4999.9    .035       0  5005.9     .05       0  5033.2     .07       0
  5043.1     .12       0  5255.9     .05       0  5880.4     .08       0
  5999.4     .05       0  6088.4     .08       0  6120.7      .1       0
  6311.2     .08       0
Bank Sta=4999.9,5005.9
XS Rating Curve= 0 ,0
Exp/Cntr=0.3,0.1

Type RM Length L Ch R = 1 ,22437   ,338,338,338
BEGIN DESCRIPTION:
BAYOU CREEK TRIB 3 38.0
END DESCRIPTION:
XS GIS Cut Line= 3
       2354287.7     13221096.82      2353287.72     13219296.85
      2352487.68     13218846.83
#Sta/Elev= 30
    2947  149.87    3416  148.49  4136.7  142.39  4228.2  143.61  4339.7  140.49
  4429.6  140.41  4651.5  140.45  4661.7  140.12  4667.5  136.96  4683.5  139.21
  4689.2  137.29  4706.3   138.9  4709.3  137.49    4743   138.8  4754.4  136.99
  4786.4   137.5  4792.2  134.91  4823.7  135.02  4832.6  134.86  4835.4  134.36
  4838.6  134.86  5360.1  141.56  5440.5   143.6  5635.4  143.32  5754.1  142.22
    5786  145.44  5814.7  144.58  5843.6  141.93  5878.4  144.07    5924  158.25
#Mann= 11 ,-1 , 0
    2947     .05       0  4339.7     .07       0  4429.6     .05       0
  4706.3     .12       0  4709.3     .07       0  4823.7     .05       0
  4832.6    .035       0  4838.6     .05       0  5360.1     .08       0
  5635.4      .1       0  5814.7     .08       0
Bank Sta=4832.6,4838.6
XS Rating Curve= 0 ,0
Exp/Cntr=0.3,0.1

Type RM Length L Ch R = 1 ,22099   ,463,463,463
BEGIN DESCRIPTION:
BAYOU CREEK TRIB 3 37.0
END DESCRIPTION:
XS GIS Cut Line= 3
      2354142.91     13219608.08      2353913.75     13219316.42
      2352831.56     13218608.83
#Sta/Elev= 30
    4079  143.26  4569.3  139.22    4720  138.35  4729.1  138.77  4735.1  138.15
  4743.9  138.89  4750.2  138.37  4887.2  137.58  4979.5   135.9  4982.3   135.4
  4985.5   135.9  5039.8  136.17  5118.2  137.51  5148.4  138.24  5169.5  140.45
  5190.5  140.78  5226.7   140.7  5233.7  139.53  5241.9  139.19  5466.2  140.93
  5471.2  140.98  5495.2  141.87  5501.2   141.6  5531.4  142.26  5624.9  142.59
  5675.8  143.86  5682.2  144.46  5724.3  144.42  5739.4  144.17  5742.9  143.67
#Mann= 5 ,-1 , 0
    4079     .05       0  4979.5    .035       0  4985.5     .05       0
  5466.2     .08       0  5471.2      .1       0
Bank Sta=4979.5,4985.5
XS Rating Curve= 0 ,0
Exp/Cntr=0.3,0.1

Type RM Length L Ch R = 1 ,21636   ,550,550,550
BEGIN DESCRIPTION:
BAYOU CREEK TRIB 3 36.0
END DESCRIPTION:
XS GIS Cut Line= 3
      2354274.87     13219288.65      2354045.69     13218920.58
       2353017.9      13218142.8
#Sta/Elev= 30
  4019.3   142.7  4098.5  141.84  4135.1  141.89  4150.5  141.57  4208.3  141.74
  4235.4  141.36  4302.7  141.07  4308.6  140.85  4339.3  140.92  4381.8  140.26
  4410.2  140.15  4433.7  139.76  4439.6  139.89  4497.4   139.2  4688.8  137.71
  4832.4  136.89  4993.8  135.35  4996.5  134.85  4999.8  135.35  5017.6  135.48
  5111.2  137.13  5331.8  138.17  5581.5  140.57  5681.3  141.01  5689.6  141.09
  5695.9  141.65  5710.4  140.59  5716.9  141.17  5731.3  143.79  5741.8  143.89
#Mann= 3 ,-1 , 0
  4019.3     .05       0  4993.8    .035       0  4999.8     .05       0
Bank Sta=4993.8,4999.8
XS Rating Curve= 0 ,0
Exp/Cntr=0.3,0.1

Type RM Length L Ch R = 1 ,21086   ,423,423,423
BEGIN DESCRIPTION:
BAYOU CREEK TRIB 3 35.0
END DESCRIPTION:
XS GIS Cut Line= 3
      2354504.04     13218899.77      2354302.64     13218476.14
      2353373.11     13217671.48
#Sta/Elev= 30
  4042.9  141.67  4207.8  140.96  4281.5  140.28  4298.7  140.36  4344.1  139.86
  4349.7  139.99  4446.1  139.24  4455.8  138.96  4593.1  137.94    4664  137.27
  4670.9  137.01  4677.6  137.13  4748.8  136.39  4918.8  135.85  4965.2  135.04
  4967.9  134.54  4971.2  135.04  5166.7  135.95  5379.5  137.89  5479.2  139.17
  5563.7  139.83  5670.1  140.24  5677.7  140.49    5692  140.08  5698.6  140.71
  5706.3  142.27  5712.9  143.15  5732.2  143.23  5734.8  143.21  5741.4  142.27
#Mann= 4 ,-1 , 0
  4042.9     .05       0  4965.2    .035       0  4971.2     .05       0
  5732.2     .08       0
Bank Sta=4965.2,4971.2
XS Rating Curve= 0 ,0
Exp/Cntr=0.3,0.1

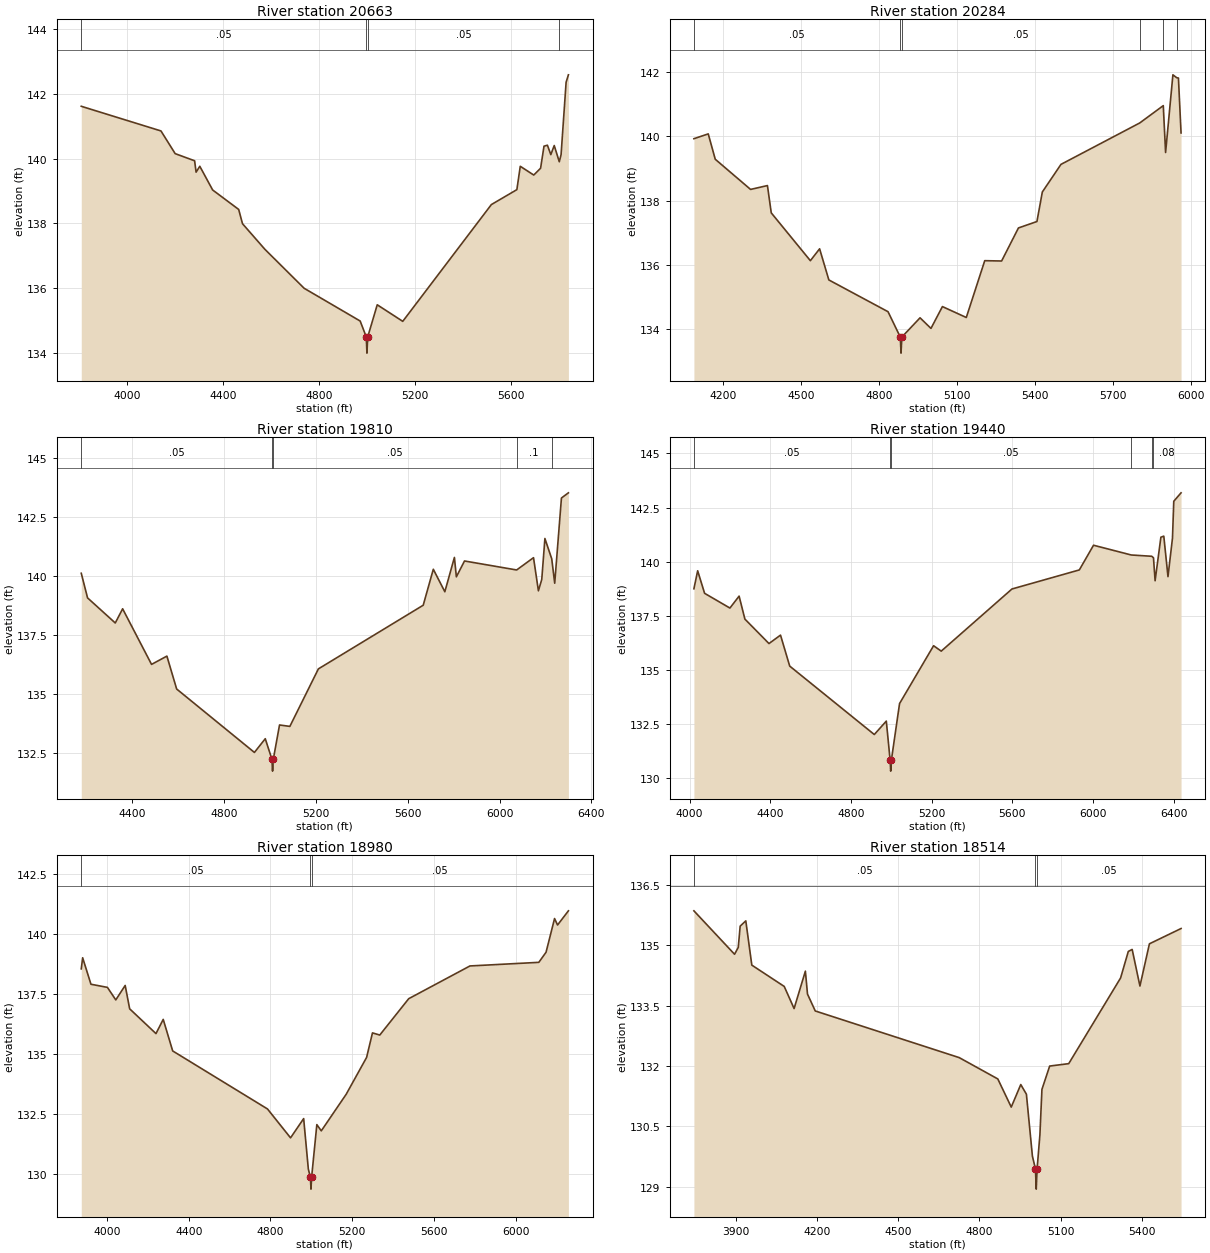
Type RM Length L Ch R = 1 ,20663   ,379,379,379
BEGIN DESCRIPTION:
BAYOU CREEK TRIB 3 34.0
END DESCRIPTION:
XS GIS Cut Line= 3
      2354934.57      13218892.8      2354573.47     13218253.92
      2353712.57     13217288.88
#Sta/Elev= 30
  3810.9  141.61  4142.5  140.85  4201.7  140.15  4282.5  139.93  4288.7  139.58
  4304.2  139.76  4357.6  139.03  4465.9  138.43  4481.8  137.99  4575.1   137.2
  4738.2     136  4971.4  134.99  4996.9   134.5  4999.6     134  5002.9   134.5
  5042.5  135.49  5148.7  134.98  5517.4  138.58  5623.5  139.04  5637.7  139.76
  5693.8  139.49  5722.2   139.7  5736.4  140.38  5750.6  140.41  5764.8  140.12
    5779   140.4    5800   139.9  5807.5  140.12  5828.4  142.35    5838  142.58
#Mann= 4 ,-1 , 0
  3810.9     .05       0  4996.9    .035       0  5002.9     .05       0
    5800     .08       0
Bank Sta=4996.9,5002.9
XS Rating Curve= 0 ,0
Exp/Cntr=0.3,0.1

Type RM Length L Ch R = 1 ,20284   ,474,474,474
BEGIN DESCRIPTION:
BAYOU CREEK TRIB 3 33.0
END DESCRIPTION:
XS GIS Cut Line= 3
      2355108.21     13218462.28      2354302.64     13217351.14
      2353949.34     13216990.92
#Sta/Elev= 30
  4086.1  139.93  4141.3  140.08  4168.3  139.29  4304.4  138.35  4369.4  138.47
  4384.1  137.62  4534.8  136.13  4570.4   136.5    4606  135.53  4834.1  134.54
  4881.3  133.75  4884.1  133.25  4887.3  133.75  4957.4  134.35  4999.5  134.02
  5043.6   134.7  5135.6  134.36  5206.7  136.13  5271.7  136.12  5336.6  137.15
  5407.8  137.35  5428.6  138.27  5500.4  139.13  5803.8  140.42  5894.6  140.96
  5903.5   139.5  5931.7  141.92  5946.3  141.83    5953  141.82  5963.1  140.11
#Mann= 6 ,-1 , 0
  4086.1     .05       0  4881.3    .035       0  4887.3     .05       0
  5803.8      .1       0  5894.6     .05       0  5946.3     .08       0
Bank Sta=4881.3,4887.3
XS Rating Curve= 0 ,0
Exp/Cntr=0.3,0.1

Type RM Length L Ch R = 1 ,19810   ,370,370,370
BEGIN DESCRIPTION:
BAYOU CREEK TRIB 3 32.0
END DESCRIPTION:
XS GIS Cut Line= 3
      2355323.48     13218365.06      2354920.69     13217316.42
      2354115.15     13216726.15
#Sta/Elev= 30
    4178  140.11  4205.4  139.07  4326.1  138.01  4358.2  138.61  4484.1  136.26
    4551  136.61  4593.5  135.22  4932.2  132.54  4979.5  133.12  5008.5  132.25
  5011.3  131.75  5014.5  132.25  5041.6   133.7  5086.6  133.64  5210.9  136.07
  5667.5  138.76  5711.5  140.28  5761.7  139.33  5803.4  140.78  5811.9  139.96
  5847.4  140.63  6074.5  140.25    6148  140.77  6169.3  139.37  6183.9  139.85
  6197.6  141.58  6227.4  140.72  6240.3  139.69  6269.6  143.29    6300  143.51
#Mann= 5 ,-1 , 0
    4178     .05       0  5008.5    .035       0  5014.5     .05       0
  6074.5      .1       0  6227.4     .08       0
Bank Sta=5008.5,5014.5
XS Rating Curve= 0 ,0
Exp/Cntr=0.3,0.1

Type RM Length L Ch R = 1 ,19440   ,460,460,460
BEGIN DESCRIPTION:
BAYOU CREEK TRIB 3 31.0
END DESCRIPTION:
XS GIS Cut Line= 3
       2355844.3     13218323.36      2355212.36     13217170.58
       2354517.9      13216316.4
#Sta/Elev= 30
  4021.8  138.75  4040.4  139.58  4074.8  138.54  4200.3  137.86  4245.9  138.41
  4274.6  137.35    4394  136.22  4451.2  136.61  4496.8  135.18  4916.3  132.02
  4975.8  132.64  4994.8  130.83  4997.6  130.33  5000.8  130.83  5041.5  133.45
  5210.2  136.12  5248.1  135.87  5598.9  138.74  5932.9  139.62  6003.3  140.76
  6190.4  140.31  6292.1  140.25  6300.6  140.18  6308.6  139.12  6337.3  141.13
  6351.7  141.18  6372.5  139.31  6394.8  141.09  6401.2  142.79  6437.3  143.18
#Mann= 6 ,-1 , 0
  4021.8     .05       0  4994.8    .035       0  5000.8     .05       0
  6190.4     .08       0  6292.1     .05       0  6300.6     .08       0
Bank Sta=4994.8,5000.8
XS Rating Curve= 0 ,0
Exp/Cntr=0.3,0.1

Type RM Length L Ch R = 1 ,18980   ,466,466,466
BEGIN DESCRIPTION:
BAYOU CREEK TRIB 3 30.0
END DESCRIPTION:
XS GIS Cut Line= 3
      2356392.92     13218233.09       2356219.3     13217844.19
      2355038.83      13216281.8
#Sta/Elev= 30
  3874.3  138.54  3881.1     139  3921.7   137.9  4002.3  137.77  4043.2  137.25
  4089.2  137.85  4111.1  136.88  4239.9  135.85  4275.4  136.44  4321.7  135.13
  4785.7  132.72  4898.5  131.52  4962.7  132.32  4985.6  130.22  4995.7  129.89
  4998.5  129.39  5001.7  129.89  5027.2  132.07  5048.9  131.81  5170.8  133.33
  5270.7  134.86  5299.5  135.88  5335.2  135.79  5476.8   137.3  5776.5  138.66
  6113.6  138.81    6149  139.23  6190.6  140.63  6205.2  140.36  6258.4  140.95
#Mann= 3 ,-1 , 0
  3874.3     .05       0  4995.7    .035       0  5001.7     .05       0
Bank Sta=4995.7,5001.7
XS Rating Curve= 0 ,0
Exp/Cntr=0.3,0.1

Type RM Length L Ch R = 1 ,18514   ,173,173,173
BEGIN DESCRIPTION:
BAYOU CREEK TRIB 3 29.0
END DESCRIPTION:
XS GIS Cut Line= 2
      2357031.92     13218093.28      2355886.11     13216704.42
#Sta/Elev= 30
  3744.7  135.86  3894.9  134.78  3908.6  134.95  3915.7  135.48  3936.5  135.61
  3958.7  134.51  4078.5  133.98    4115  133.43  4156.7  134.36  4164.5  133.79
  4193.2  133.37  4725.3  132.21  4867.9  131.68  4917.6  130.98  4952.8  131.54
  4973.6   131.3  4995.8  129.76  5007.1  129.44  5009.9  128.94  5013.1  129.44
  5023.5  130.29    5031  131.42  5059.6     132    5130  132.06  5321.7  134.19
  5350.2  134.85  5364.5   134.9  5393.2  133.99  5428.3  135.04  5545.2  135.42
#Mann= 3 ,-1 , 0
  3744.7     .05       0  5007.1    .035       0  5013.1     .05       0
Bank Sta=5007.1,5013.1
XS Rating Curve= 0 ,0
Exp/Cntr=0.3,0.1