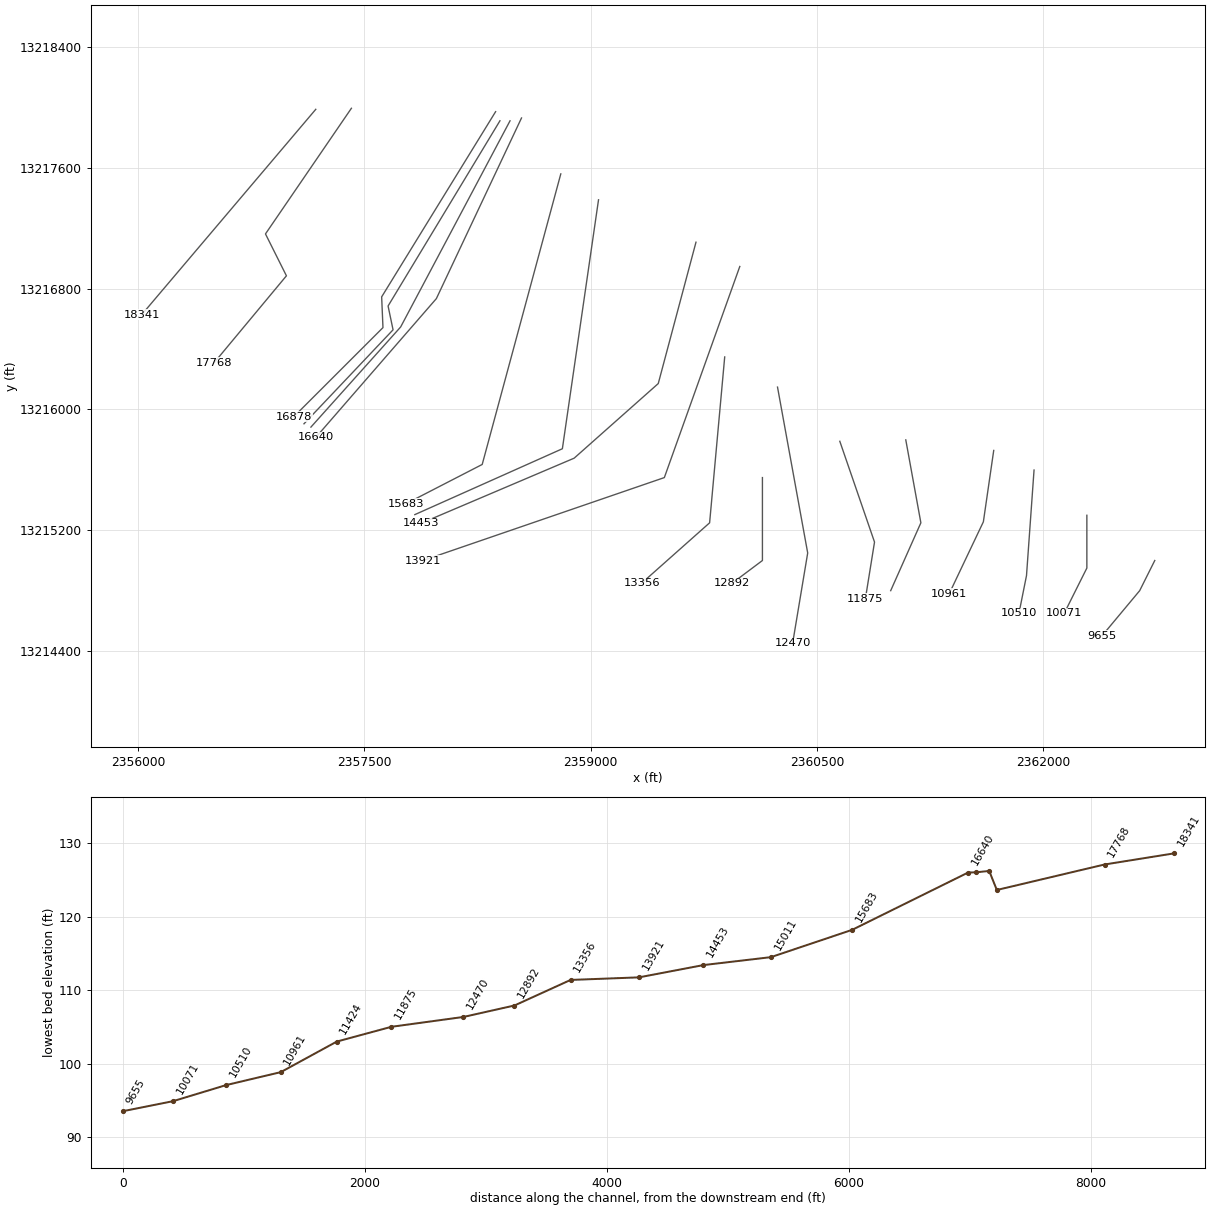
HEC-RAS study BAYOU CREEK TRIB 3.prj: BAYOU CREEK TRIB 3 Base Level Engineering

--- BAYOU CREEK TRIB 3.g01 (geometry) --- (continued)

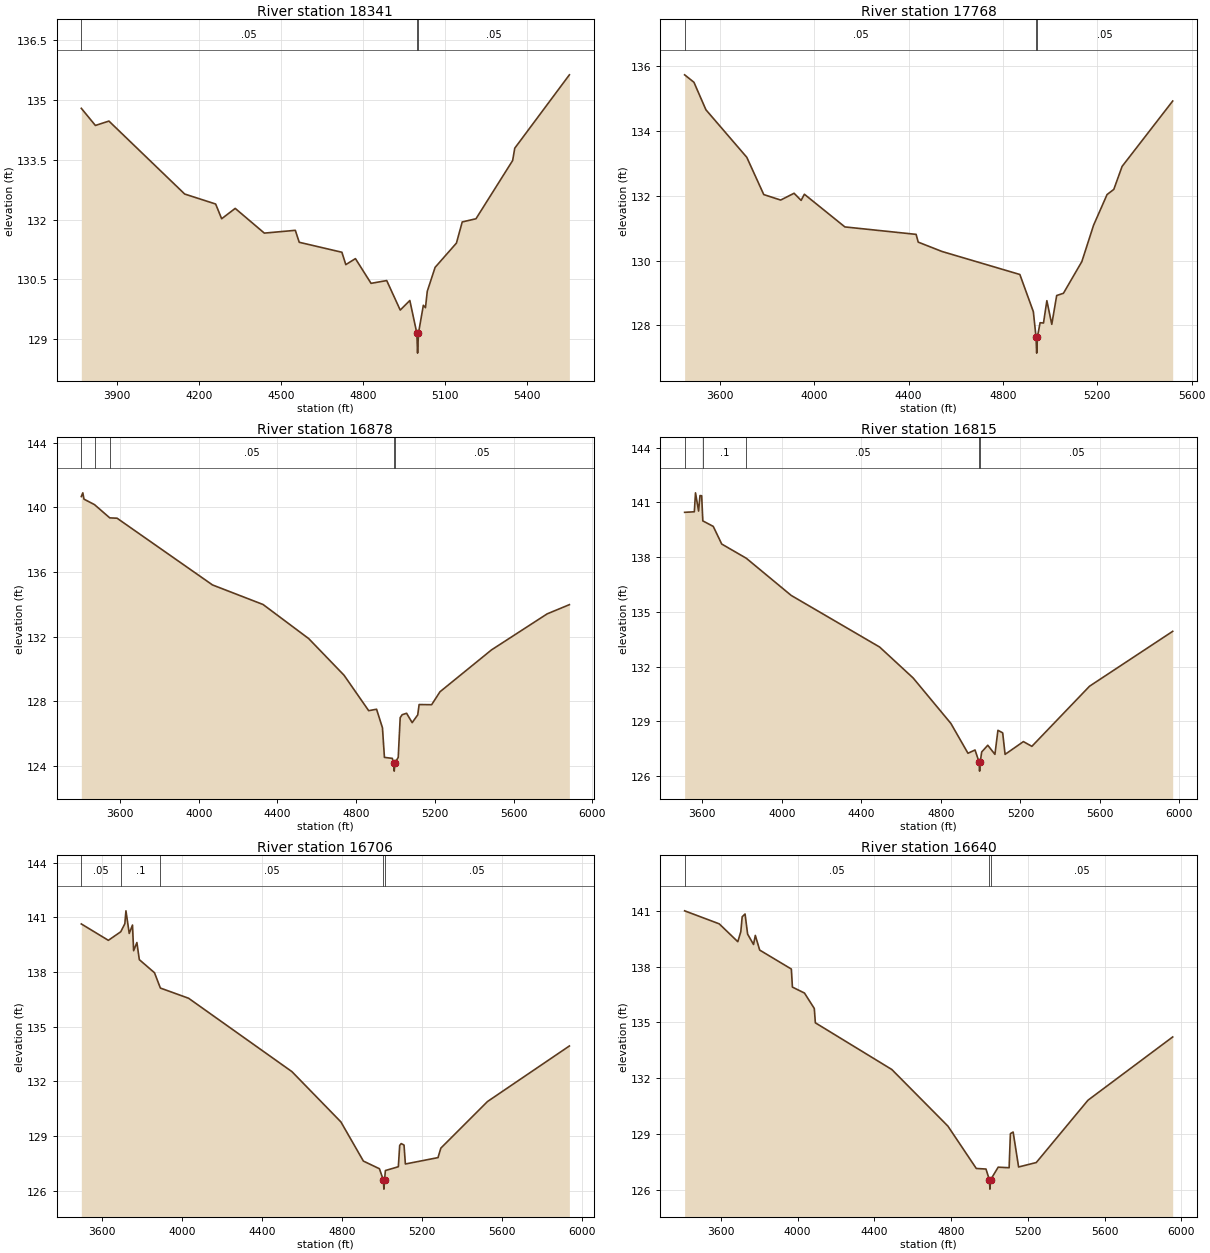
Type RM Length L Ch R = 1 ,18341   ,573,573,573
BEGIN DESCRIPTION:
BAYOU CREEK TRIB 3 28.0
END DESCRIPTION:
XS GIS Cut Line= 2
      2357177.76     13217989.12      2356024.97       13216628.
#Sta/Elev= 30
    3770  134.79  3821.5  134.36  3870.9  134.47  4147.8  132.64  4260.9  132.39
  4282.9  132.02  4332.4  132.28  4438.9  131.66  4552.1  131.73  4566.4  131.43
  4722.3  131.18  4736.6  130.87  4771.8  131.02  4828.9   130.4  4886.1  130.47
  4935.5  129.73  4970.6  129.97  4996.2  129.15  4998.9  128.65  5002.2  129.15
    5020  129.85  5027.8  129.79  5034.3   130.2  5062.9   130.8  5140.9  131.41
  5162.1  131.94  5212.3  132.02  5346.3  133.48  5354.1  133.79  5553.7  135.63
#Mann= 3 ,-1 , 0
    3770     .05       0  4996.2    .035       0  5002.2     .05       0
Bank Sta=4996.2,5002.2
XS Rating Curve= 0 ,0
Exp/Cntr=0.3,0.1

Type RM Length L Ch R = 1 ,17768   ,890,890,890
BEGIN DESCRIPTION:
BAYOU CREEK TRIB 3 27.0
END DESCRIPTION:
XS GIS Cut Line= 4
      2357413.87     13217996.06      2356844.44     13217162.76
      2356983.33     13216884.98      2356504.16     13216308.58
#Sta/Elev= 30
  3450.2  135.74  3489.7  135.51  3540.5  134.66  3713.9  133.19  3785.7  132.04
  3857.4  131.87  3914.3  132.08  3944.1  131.86  3957.9  132.05  4129.7  131.04
  4431.7  130.81  4440.6  130.57  4541.9  130.28  4871.6  129.57  4928.8  128.42
  4940.1  127.64  4942.9  127.14  4946.1  127.64  4957.4  128.08  4971.8  128.07
  4986.1  128.76  5006.9  128.03  5027.7  128.92  5056.4  128.99  5134.5  129.97
    5184  131.09  5241.3  132.04  5269.9   132.2  5305.1  132.91  5519.6  134.93
#Mann= 3 ,-1 , 0
  3450.2     .05       0  4940.1    .035       0  4946.1     .05       0
Bank Sta=4940.1,4946.1
XS Rating Curve= 0 ,0
Exp/Cntr=0.3,0.1

Type RM Length L Ch R = 1 ,16878   ,63,63,63
BEGIN DESCRIPTION:
Mapping XS 8b47258b
END DESCRIPTION:
XS GIS Cut Line= 4
      2358369.59     13217973.63      2357614.41     13216745.37
      2357623.09     13216541.37      2357033.17     13215951.45
#Sta/Elev= 30
  3403.3  140.66  3410.9  140.89  3416.8   140.5  3470.3  140.16  3547.8  139.34
  3584.9  139.32    4070  135.19  4326.9  133.98  4558.9  131.87  4738.7   129.6
  4863.7  127.41  4903.7   127.5  4933.7  126.35  4943.7  124.52  4983.8  124.46
  4990.8  124.17  4993.5  123.67  4996.8  124.17  5013.8  124.52  5023.8  126.98
  5033.8  127.16  5056.3  127.25  5084.6  126.67  5112.9  127.15    5120  127.79
  5183.6  127.78    5226  128.58  5487.7  131.17  5770.5   133.4  5883.6  133.97
#Mann= 5 ,-1 , 0
  3403.3     .05       0  3470.3      .1       0  3547.8     .05       0
  4990.8    .035       0  4996.8     .05       0
Bank Sta=4990.8,4996.8
XS Rating Curve= 0 ,0
Exp/Cntr=0.3,0.1

Type RM Length L Ch R = 1 ,16815   ,109,109,109
BEGIN DESCRIPTION:
Mapping XS b6c75993
END DESCRIPTION:
XS GIS Cut Line= 4
      2358398.28      13217913.1      2357656.94     13216684.77
      2357689.93     13216526.79      2357099.66     13215903.54
#Sta/Elev= 30
  3511.4  140.46  3560.2  140.49  3566.1  141.53  3581.6  140.53  3588.8  141.38
  3597.1  141.37  3601.3  140.37  3602.9  139.99  3655.3  139.69    3698  138.72
  3821.5  137.94  4047.4   135.9  4491.9  133.07  4660.7  131.37  4850.2  128.88
  4936.4  127.24  4971.9  127.42  4992.1  126.76  4994.8  126.26  4998.1  126.76
  5005.3  127.31  5035.9  127.68  5071.9  127.18    5087   128.5  5110.9  128.36
    5123  127.18  5215.2  127.88  5257.7  127.62  5547.8  130.92  5965.9  133.93
#Mann= 5 ,-1 , 0
  3511.4     .05       0  3601.3      .1       0  3821.5     .05       0
  4992.1    .035       0  4998.1     .05       0
Bank Sta=4992.1,4998.1
XS Rating Curve= 0 ,0
Exp/Cntr=0.3,0.1

Type RM Length L Ch R = 1 ,16706   ,66,66,66
BEGIN DESCRIPTION:
Mapping XS 9ea1b3bd
END DESCRIPTION:
XS GIS Cut Line= 3
      2358465.09     13217912.88      2357740.28     13216545.71
      2357145.72     13215881.72
#Sta/Elev= 30
  3495.9  140.64    3631  139.74  3692.9  140.21  3713.3  140.65  3718.9  141.36
  3735.3  140.12  3751.6  140.58  3757.3  139.17  3773.6  139.62  3785.7  138.68
  3861.6  137.96  3890.9  137.12  4031.9  136.56  4548.4  132.53    4793  129.77
  4905.3  127.62  4985.4   127.2  5005.1  126.58  5007.8  126.08  5011.1  126.58
  5015.2   127.1    5080  127.31  5086.7  128.48  5094.2  128.58  5108.4   128.5
  5115.1  127.46  5278.1  127.81  5292.3  128.33  5525.5  130.89  5934.6  133.94
#Mann= 5 ,-1 , 0
  3495.9     .05       0  3692.9      .1       0  3890.9     .05       0
  5005.1    .035       0  5011.1     .05       0
Bank Sta=5005.1,5011.1
XS Rating Curve= 0 ,0
Exp/Cntr=0.3,0.1

Type RM Length L Ch R = 1 ,16640   ,957,957,957
BEGIN DESCRIPTION:
Mapping XS 6cae5c27
END DESCRIPTION:
XS GIS Cut Line= 3
      2358541.15     13217931.65      2357976.91     13216733.73
      2357178.31     13215813.61
#Sta/Elev= 30
  3411.9     141  3592.2   140.3  3688.9  139.34  3704.6  139.88  3711.7  140.68
  3726.7  140.83    3740  139.75  3770.9  139.19  3780.1  139.68  3802.9  138.89
  3967.9  137.87  3973.4   136.9  4036.2  136.58  4087.4  135.75  4092.9  134.98
  4491.3  132.47  4783.2  129.43  4931.3  127.15  4981.7  127.12  4999.6  126.54
  5002.3  126.04  5005.6  126.54  5045.3  127.22  5102.3  127.19  5108.9  129.02
  5123.2  129.11  5151.7  127.23  5243.8  127.47  5513.2  130.82  5954.4  134.22
#Mann= 3 ,-1 , 0
  3411.9     .05       0  4999.6    .035       0  5005.6     .05       0
Bank Sta=4999.6,5005.6
XS Rating Curve= 0 ,0
Exp/Cntr=0.3,0.1

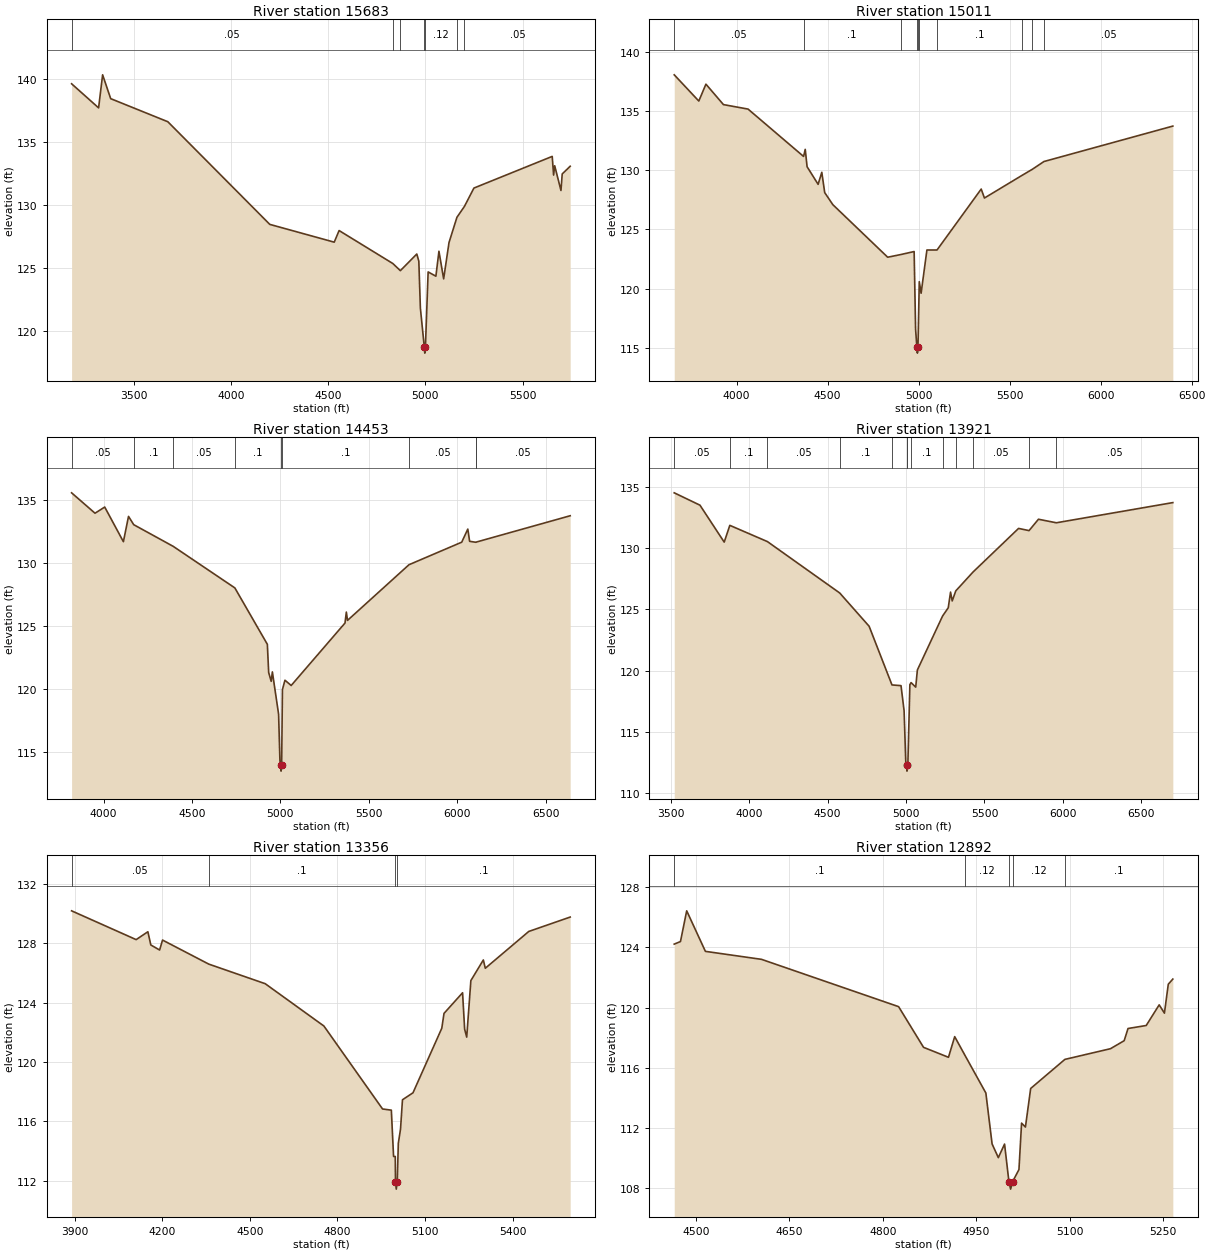
Type RM Length L Ch R = 1 ,15683   ,672,672,672
BEGIN DESCRIPTION:
BAYOU CREEK TRIB 3 26.0
END DESCRIPTION:
XS GIS Cut Line= 3
      2358801.55     13217560.95      2358280.73     13215633.91
      2357775.48     13215373.47
#Sta/Elev= 30
  3180.5  139.61  3319.4   137.7  3340.1  140.32  3381.6  138.43  3675.5   136.6
  4199.9  128.46  4531.4  127.05  4556.5  127.97  4832.5  125.36  4871.6  124.79
  4956.1  126.11  4966.5  125.54  4974.5  121.83  4994.5  118.75  4997.3  118.25
  5000.5  118.75  5014.4  124.69  5054.3  124.35    5070  126.33  5094.2  124.14
  5121.8  127.02  5162.5  129.02  5201.3  129.89  5249.9  131.34  5652.6  133.85
  5659.8  132.37  5665.4  133.11  5697.6  131.15  5704.1  132.46  5745.1  133.07
#Mann= 7 ,-1 , 0
  3180.5     .05       0  4832.5      .1       0  4871.6     .12       0
  4994.5     .07       0  5000.5     .12       0  5162.5      .1       0
  5201.3     .05       0
Bank Sta=4994.5,5000.5
XS Rating Curve= 0 ,0
Exp/Cntr=0.3,0.1

Type RM Length L Ch R = 1 ,15011   ,558,558,558
BEGIN DESCRIPTION:
BAYOU CREEK TRIB 3 25.0
END DESCRIPTION:
XS GIS Cut Line= 3
      2359051.56     13217389.14      2358811.98     13215738.07
       2357834.2     13215301.19
#Sta/Elev= 30
  3657.3  138.09  3792.3  135.87  3831.4   137.3  3927.6  135.57  4062.9  135.19
  4367.9  131.18    4377  131.78  4387.2  130.31  4447.8  128.82    4468  129.84
    4484  128.12  4528.6   127.1  4829.9  122.65  4900.4  122.87  4975.3  123.13
  4983.3  116.55  4990.4  115.03  4993.2  114.53  4996.4  115.03  5000.7  118.39
  5003.5  120.58  5013.6   119.6  5045.5  123.26    5101  123.26  5343.8  128.42
  5361.6  127.66  5567.2  129.57  5625.4   130.1  5688.5  130.75  6396.6  133.75
#Mann= 10 ,-1 , 0
  3657.3     .05       0  4367.9      .1       0  4900.4     .12       0
  4990.4     .07       0  4996.4     .12       0  5000.7     .16       0
    5101      .1       0  5567.2     .05       0  5625.4      .1       0
  5688.5     .05       0
Bank Sta=4990.4,4996.4
XS Rating Curve= 0 ,0
Exp/Cntr=0.3,0.1

Type RM Length L Ch R = 1 ,14453   ,532,532,532
BEGIN DESCRIPTION:
BAYOU CREEK TRIB 3 24.0
END DESCRIPTION:
XS GIS Cut Line= 4
       2359697.4     13217107.87      2359447.39     13216170.37
       2358890.1     13215675.57      2357874.49     13215243.29
#Sta/Elev= 30
  3819.4  135.55  3951.9  133.93  4006.7  134.42  4112.3  131.67  4141.3  133.68
  4170.7  133.02  4393.9   131.3  4742.5     128  4926.3  123.52  4933.8  121.28
  4948.1  120.58  4954.7  121.33  4989.9  117.97  4997.4   114.3  5001.1  113.95
  5003.8  113.45  5007.1  113.95  5011.6  119.93  5025.8  120.67    5061  120.25
  5365.4  125.21  5372.9  126.08  5379.6  125.42  5727.1  129.84  6025.3  131.63
  6059.8  132.67    6070   131.7  6106.4  131.62  6107.8  131.64  6638.7  133.73
#Mann= 9 ,-1 , 0
  3819.4     .05       0  4170.7      .1       0  4393.9     .05       0
  4742.5      .1       0  5001.1     .07       0  5007.1      .1       0
  5727.1     .05       0  6106.4      .1       0  6107.8     .05       0
Bank Sta=5001.1,5007.1
XS Rating Curve= 0 ,0
Exp/Cntr=0.3,0.1

Type RM Length L Ch R = 1 ,13921   ,565,565,565
BEGIN DESCRIPTION:
BAYOU CREEK TRIB 3 23.0
END DESCRIPTION:
XS GIS Cut Line= 3
      2359987.71     13216946.83      2359487.72     13215546.85
      2357887.69     13214996.84
#Sta/Elev= 30
  3522.5  134.54  3686.5  133.53    3841  130.51  3876.9  131.88  4116.7  130.55
  4577.3  126.35  4764.8  123.63  4910.5  118.83  4968.2  118.77  4987.8  116.72
    4999  112.34  5003.4  112.28  5006.2  111.78  5009.4  112.28  5011.7  112.28
  5024.7  118.85  5032.3  119.02  5061.9  118.65  5072.5  120.05    5233  124.46
  5269.3  125.14    5284  126.42  5294.6   125.7  5317.3  126.52  5427.1  128.06
  5717.6  131.63  5784.4  131.45  5844.4  132.38  5958.4  132.09    6701  133.74
#Mann= 13 ,-1 , 0
  3522.5     .05       0  3876.9      .1       0  4116.7     .05       0
  4577.3      .1       0  4910.5     .16       0  5003.4     .07       0
  5009.4     .16       0  5032.3      .1       0    5233     .05       0
  5317.3      .1       0  5427.1     .05       0  5784.4      .1       0
  5958.4     .05       0
Bank Sta=5003.4,5009.4
XS Rating Curve= 0 ,0
Exp/Cntr=0.3,0.1

Type RM Length L Ch R = 1 ,13356   ,464,464,464
BEGIN DESCRIPTION:
BAYOU CREEK TRIB 3 22.0
END DESCRIPTION:
XS GIS Cut Line= 3
      2359887.72      13216346.9      2359787.72     13215246.85
      2359337.69     13214846.83
#Sta/Elev= 30
  3889.9  130.18  4110.9  128.24    4151  128.77  4161.1  127.88  4191.2  127.54
  4201.2  128.21  4359.5  126.59  4552.7  125.27  4753.5  122.42  4954.3  116.83
  4984.4  116.75    4992  113.63  4997.8  113.63  4998.6  111.93  5001.3  111.43
  5004.6  111.93  5008.3  114.52  5015.8  115.47  5022.5  117.45  5058.5  117.92
  5157.1  122.27  5164.7  123.27  5228.2  124.66  5235.3  122.21  5242.4  121.67
  5256.6  125.48  5299.3  126.87    5306  126.31  5454.8  128.79  5596.6  129.76
#Mann= 4 ,-1 , 0
  3889.9     .05       0  4359.5      .1       0  4998.6     .07       0
  5004.6      .1       0
Bank Sta=4998.6,5004.6
XS Rating Curve= 0 ,0
Exp/Cntr=0.3,0.1

Type RM Length L Ch R = 1 ,12892   ,422,422,422
BEGIN DESCRIPTION:
BAYOU CREEK TRIB 3 21.0
END DESCRIPTION:
XS GIS Cut Line= 3
      2360137.72     13215546.85      2360137.72     13214996.85
      2359937.72     13214846.85
#Sta/Elev= 30
  4465.4  124.21  4475.4  124.38  4485.4  126.42  4515.4  123.73  4605.4   123.2
  4825.4  120.06  4865.4  117.36  4905.4   116.7  4915.4  118.07  4932.4  116.79
  4965.4  114.33  4975.4  110.95  4985.4  110.04  4995.4  110.94  5002.4  108.45
  5005.1  107.95  5008.4  108.45  5018.5  109.25  5022.7  112.33  5028.9  112.07
  5037.3  114.63  5092.2  116.56  5165.4  117.27  5187.3   117.8  5193.5  118.61
  5222.7  118.81  5243.5  120.18  5251.9  119.63  5258.1  121.55  5265.4  121.89
#Mann= 5 ,-1 , 0
  4465.4      .1       0  4932.4     .12       0  5002.4     .07       0
  5008.4     .12       0  5092.2      .1       0
Bank Sta=5002.4,5008.4
XS Rating Curve= 0 ,0
Exp/Cntr=0.3,0.1

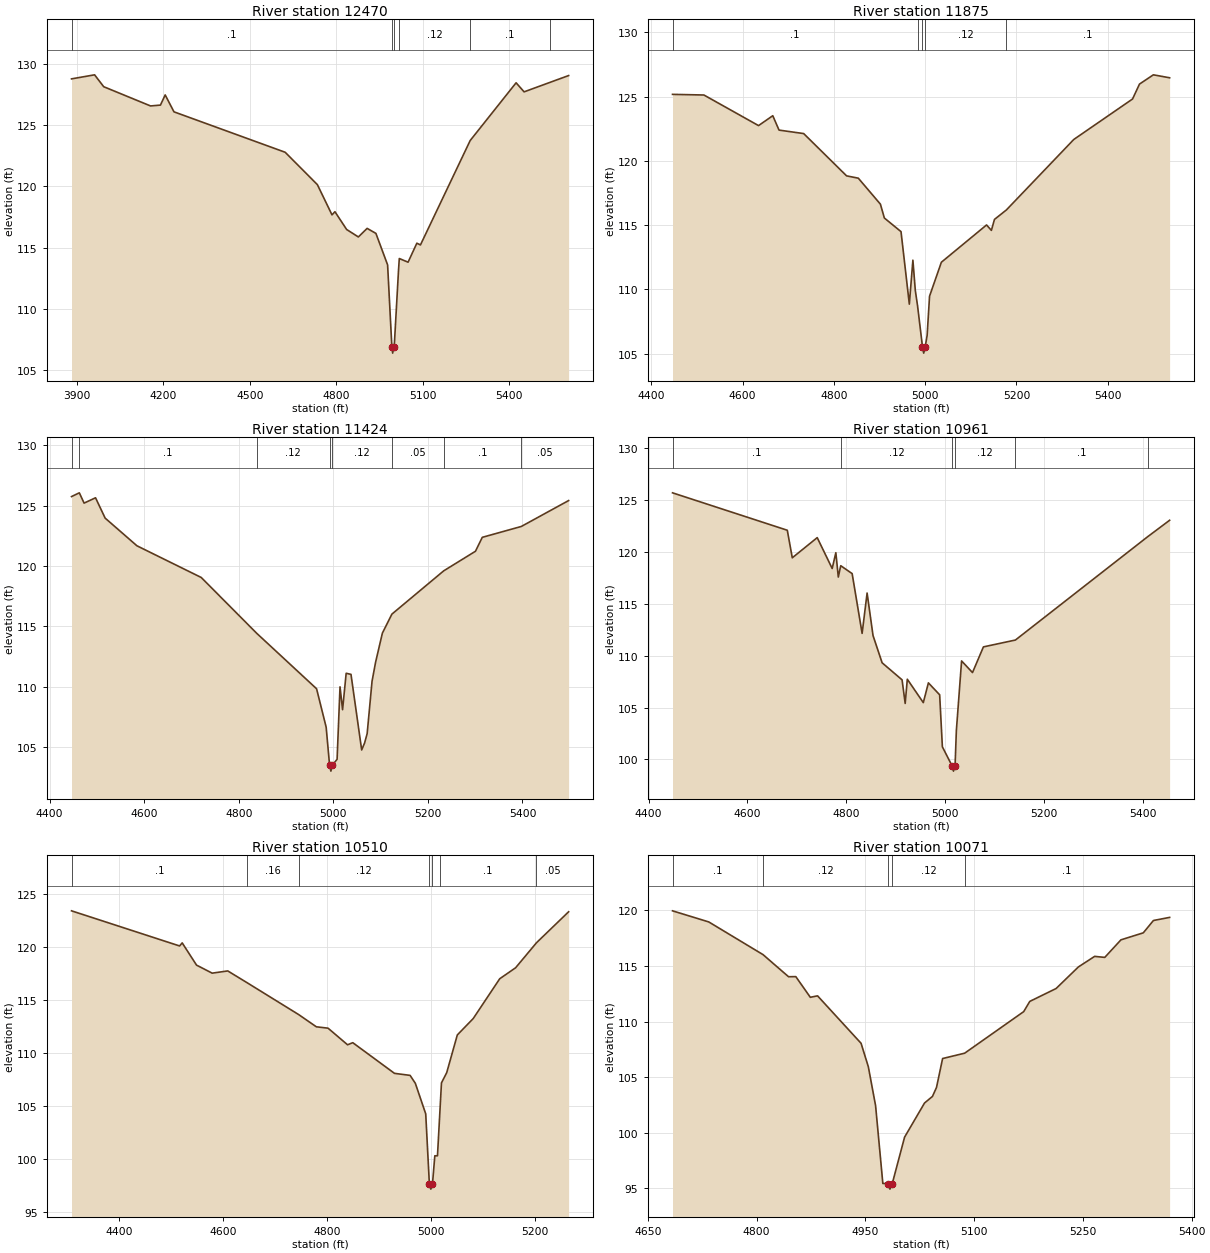
Type RM Length L Ch R = 1 ,12470   ,595,595,595
BEGIN DESCRIPTION:
BAYOU CREEK TRIB 3 20.0
END DESCRIPTION:
XS GIS Cut Line= 3
      2360237.71     13216146.89      2360437.72     13215046.85
      2360337.73      13214446.9
#Sta/Elev= 30
  3880.8  128.77  3960.9   129.1  3992.6  128.13  4155.3  126.56  4189.6  126.63
  4206.1  127.46  4236.6  126.08  4622.8  122.78  4734.6  120.14  4785.4  117.67
  4795.6  117.93  4836.2  116.48  4876.9  115.87  4907.4  116.57  4937.9  116.16
  4978.5  113.59  4993.3  106.89  4996.1  106.39  4999.3  106.89  5001.4  106.89
  5016.5  113.19  5019.1  114.11  5049.6  113.81    5080  115.36  5092.6  115.22
  5265.3  123.74  5424.7  128.45  5452.5  127.71  5543.1  128.49  5607.1  129.04
#Mann= 6 ,-1 , 0
  3880.8      .1       0  4993.3     .07       0  4999.3      .1       0
  5016.5     .12       0  5265.3      .1       0  5543.1     .05       0
Bank Sta=4993.3,4999.3
XS Rating Curve= 0 ,0
Exp/Cntr=0.3,0.1

Type RM Length L Ch R = 1 ,11875   ,451,451,451
BEGIN DESCRIPTION:
BAYOU CREEK TRIB 3 19.0
END DESCRIPTION:
XS GIS Cut Line= 3
      2360650.53     13215787.54      2360880.55     13215119.15
      2360819.81     13214741.67
#Sta/Elev= 30
  4446.3  125.18  4515.1  125.13  4634.8  122.75    4666  123.52  4679.7   122.4
  4733.7  122.13  4827.7  118.84  4853.4  118.66  4901.8  116.64  4910.5  115.56
    4947   114.5  4965.2  108.86    4973  112.28  4978.3  109.93  4983.3  108.71
    4994  105.55  4996.7  105.05    5000  105.55  5004.2  106.43  5009.5  109.48
  5035.4  112.12  5134.4  115.02    5145   114.6  5151.7  115.45  5177.9  116.19
  5325.5  121.67  5454.3  124.82  5469.5  125.98  5499.9   126.7  5535.5  126.47
#Mann= 5 ,-1 , 0
  4446.3      .1       0  4983.3     .12       0    4994     .07       0
    5000     .12       0  5177.9      .1       0
Bank Sta=4994,5000
XS Rating Curve= 0 ,0
Exp/Cntr=0.3,0.1

Type RM Length L Ch R = 1 ,11424   ,463,463,463
BEGIN DESCRIPTION:
BAYOU CREEK TRIB 3 18.0
END DESCRIPTION:
XS GIS Cut Line= 3
      2361087.73     13215796.81      2361187.72     13215246.85
      2360987.73     13214796.87
#Sta/Elev= 30
  4446.2  125.74  4462.7  126.05  4472.8   125.2    4497  125.64  4517.3  123.96
  4584.6  121.67  4720.6  119.05  4837.8  114.44  4964.5  109.85  4984.8  106.67
    4992  103.54  4994.8  103.04    4998  103.54  5007.9  104.02  5014.1  110.01
  5019.5  108.12  5027.1  111.13  5037.3  111.04  5059.9  104.79    5066  105.36
  5071.5  106.14  5081.8  110.46  5089.3  112.04  5103.7  114.45  5123.8  116.02
  5233.4   119.6  5300.6  121.22    5315  122.37  5397.6  123.27  5497.6  125.41
#Mann= 8 ,-1 , 0
  4446.2     .05       0  4462.7      .1       0  4837.8     .12       0
    4992     .07       0    4998     .12       0  5123.8     .05       0
  5233.4      .1       0  5397.6     .05       0
Bank Sta=4992,4998
XS Rating Curve= 0 ,0
Exp/Cntr=0.3,0.1

Type RM Length L Ch R = 1 ,10961   ,451,451,451
BEGIN DESCRIPTION:
BAYOU CREEK TRIB 3 17.0
END DESCRIPTION:
XS GIS Cut Line= 3
      2361670.49     13215726.83      2361601.88     13215253.49
      2361375.36     13214776.31
#Sta/Elev= 30
  4448.4  125.65  4680.8  122.05  4690.9   119.4  4741.4  121.34  4771.7  118.37
  4779.1  119.89  4784.1  117.55    4789  118.64  4812.1  117.88  4832.3  112.13
  4842.4  116.01  4854.4  111.92  4872.8   109.3  4913.2  107.66  4919.5  105.39
  4923.8  107.72  4956.2  105.47  4966.5  107.37  4989.3  106.22  4994.8  101.22
  5014.5   99.38  5017.3   98.88  5020.5   99.38  5023.1  102.76  5033.7  109.48
  5055.8  108.36  5077.9  110.83  5142.7  111.49  5410.5  121.43  5454.9  123.01
#Mann= 6 ,-1 , 0
  4448.4      .1       0    4789     .12       0  5014.5     .07       0
  5020.5     .12       0  5142.7      .1       0  5410.5     .05       0
Bank Sta=5014.5,5020.5
XS Rating Curve= 0 ,0
Exp/Cntr=0.3,0.1

Type RM Length L Ch R = 1 ,10510   ,439,439,439
BEGIN DESCRIPTION:
BAYOU CREEK TRIB 3 16.0
END DESCRIPTION:
XS GIS Cut Line= 3
      2361937.72     13215596.83      2361887.72     13214896.85
      2361837.72     13214646.86
#Sta/Elev= 30
  4307.7  123.42  4515.7   120.1  4520.7  120.39  4548.3  118.29  4578.4  117.53
  4608.4  117.74  4645.5  116.63  4744.7  113.62  4778.9  112.46  4801.4  112.33
    4839  110.76    4849  110.96  4929.3  108.06  4959.3  107.87  4969.4  107.12
  4989.4  104.23  4996.4   97.62  4999.2   97.12  5002.4   97.62  5006.9  100.27
    5012  100.27    5016  103.85  5019.7  107.16  5029.8  108.13  5050.2  111.69
  5080.8  113.24  5131.8     117  5162.4  118.04  5202.5   120.4  5264.4  123.33
#Mann= 7 ,-1 , 0
  4307.7      .1       0  4645.5     .16       0  4744.7     .12       0
  4996.4     .07       0  5002.4     .12       0    5016      .1       0
  5202.5     .05       0
Bank Sta=4996.4,5002.4
XS Rating Curve= 0 ,0
Exp/Cntr=0.3,0.1

Type RM Length L Ch R = 1 ,10071   ,416,416,416
BEGIN DESCRIPTION:
BAYOU CREEK TRIB 3 15.0
END DESCRIPTION:
XS GIS Cut Line= 3
      2362287.72     13215296.86      2362287.72     13214946.85
      2362137.73     13214646.87
#Sta/Elev= 30
  4684.2  119.97  4734.2  118.97    4809  116.03  4844.2  114.04  4854.2  114.05
  4874.2  112.19  4884.2  112.32  4944.2  108.05  4954.2  105.94  4964.2  102.44
  4974.2   95.44  4981.2   95.43    4984   94.93  4987.2   95.43  5004.2   99.61
  5031.7  102.68  5042.6  103.27  5048.2  104.08  5056.6  106.68    5087  107.16
  5168.4   110.9  5176.8  111.82  5213.1  112.98  5243.8  114.92  5266.2  115.87
  5280.2  115.78  5302.5  117.36  5333.3  117.99  5347.3   119.1  5369.6  119.38
#Mann= 5 ,-1 , 0
  4684.2      .1       0    4809     .12       0  4981.2     .07       0
  4987.2     .12       0    5087      .1       0
Bank Sta=4981.2,4987.2
XS Rating Curve= 0 ,0
Exp/Cntr=0.3,0.1

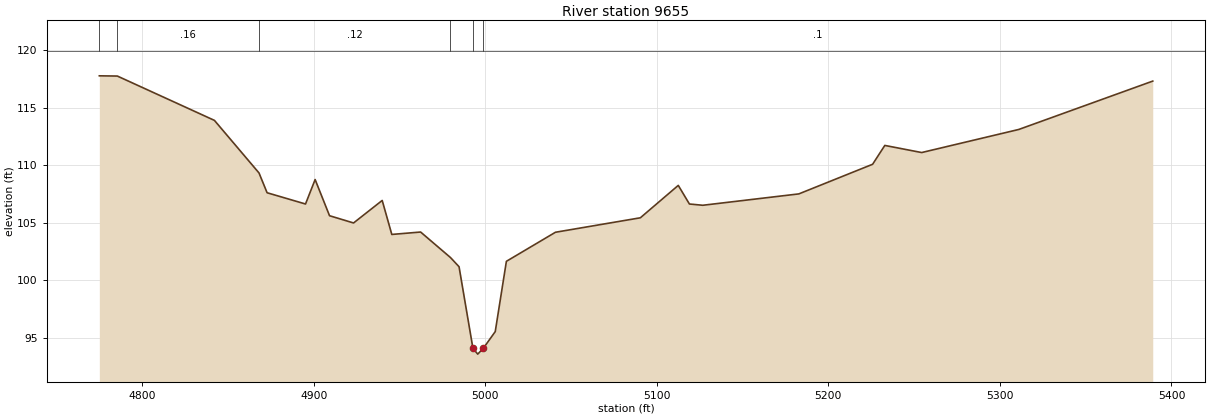
Type RM Length L Ch R = 1 ,9655    ,460,460,460
BEGIN DESCRIPTION:
BAYOU CREEK TRIB 3 14.0
END DESCRIPTION:
XS GIS Cut Line= 3
      2362737.73     13214996.87      2362637.72     13214796.85
      2362387.75     13214496.88
#Sta/Elev= 30
    4775  117.79  4785.5  117.77  4842.1  113.91  4868.1  109.33  4872.8  107.61
  4895.2  106.63  4900.8  108.76  4909.2  105.61  4923.2  104.98  4939.9  106.94
  4945.5  103.98  4962.3  104.19  4979.7  101.97  4984.7  101.17  4992.8   94.06
  4995.6   93.56  4998.8   94.06  5005.8   95.52  5012.3  101.64  5040.9  104.17
  5090.4  105.43  5112.5  108.25    5119  106.63  5126.8  106.52  5182.8  107.51
  5225.8  110.09  5232.9  111.73  5254.4  111.11    5311  113.12  5389.1  117.33
#Mann= 6 ,-1 , 0
    4775      .1       0  4785.5     .16       0  4868.1     .12       0
  4979.7      .1       0  4992.8     .07       0  4998.8      .1       0
Bank Sta=4992.8,4998.8
XS Rating Curve= 0 ,0
Exp/Cntr=0.3,0.1