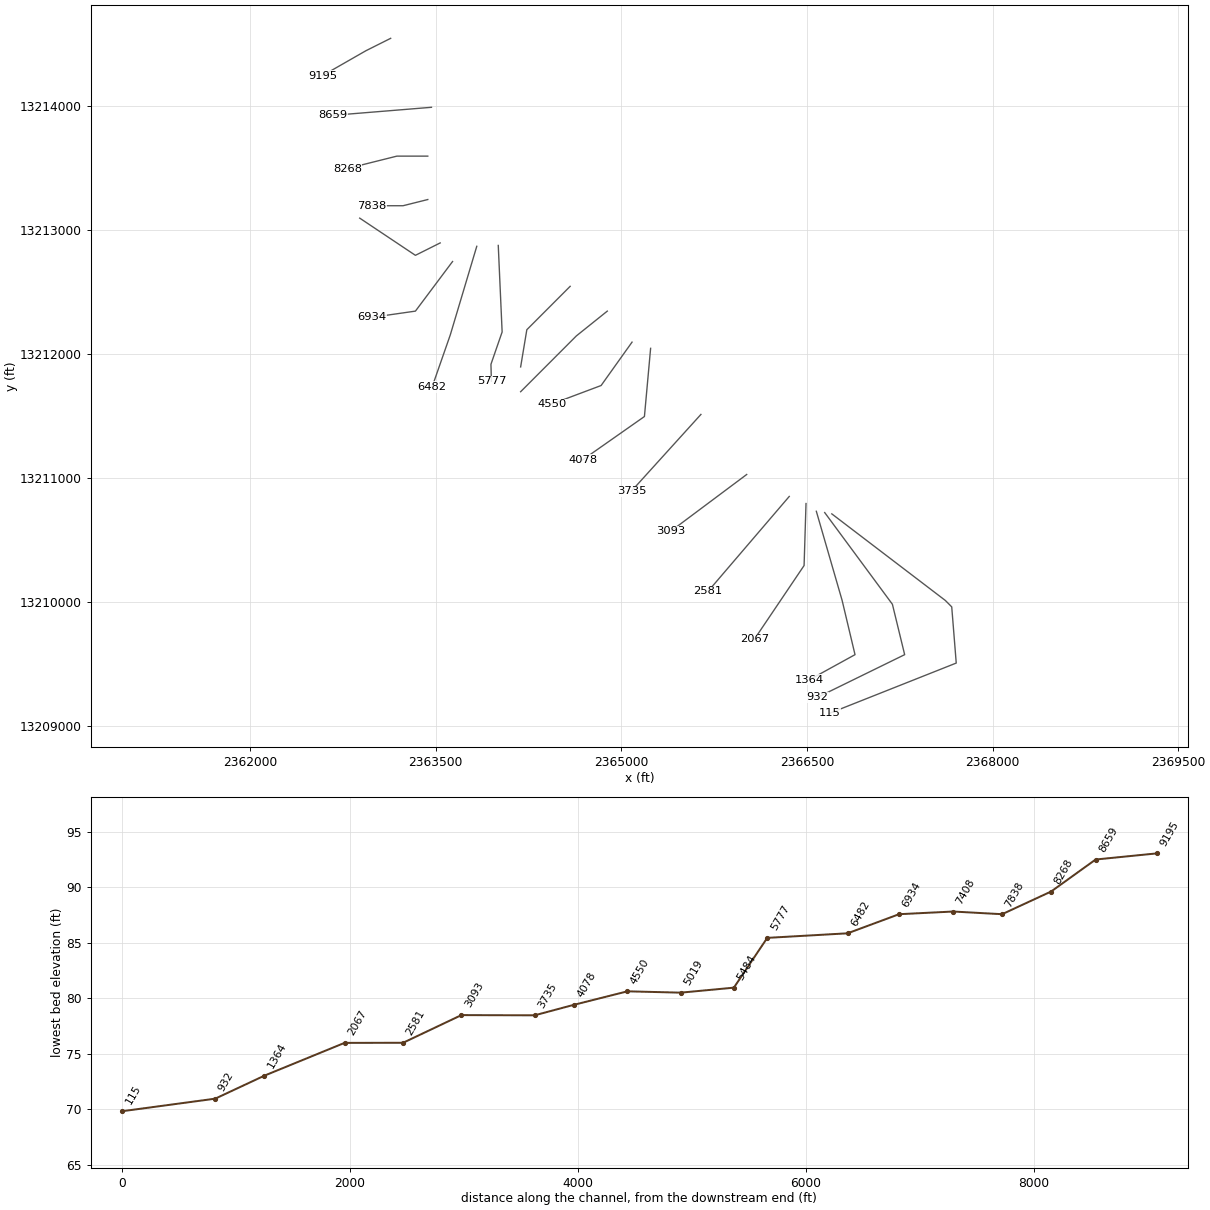
HEC-RAS study BAYOU CREEK TRIB 3.prj: BAYOU CREEK TRIB 3 Base Level Engineering

--- BAYOU CREEK TRIB 3.g01 (geometry) --- (continued)

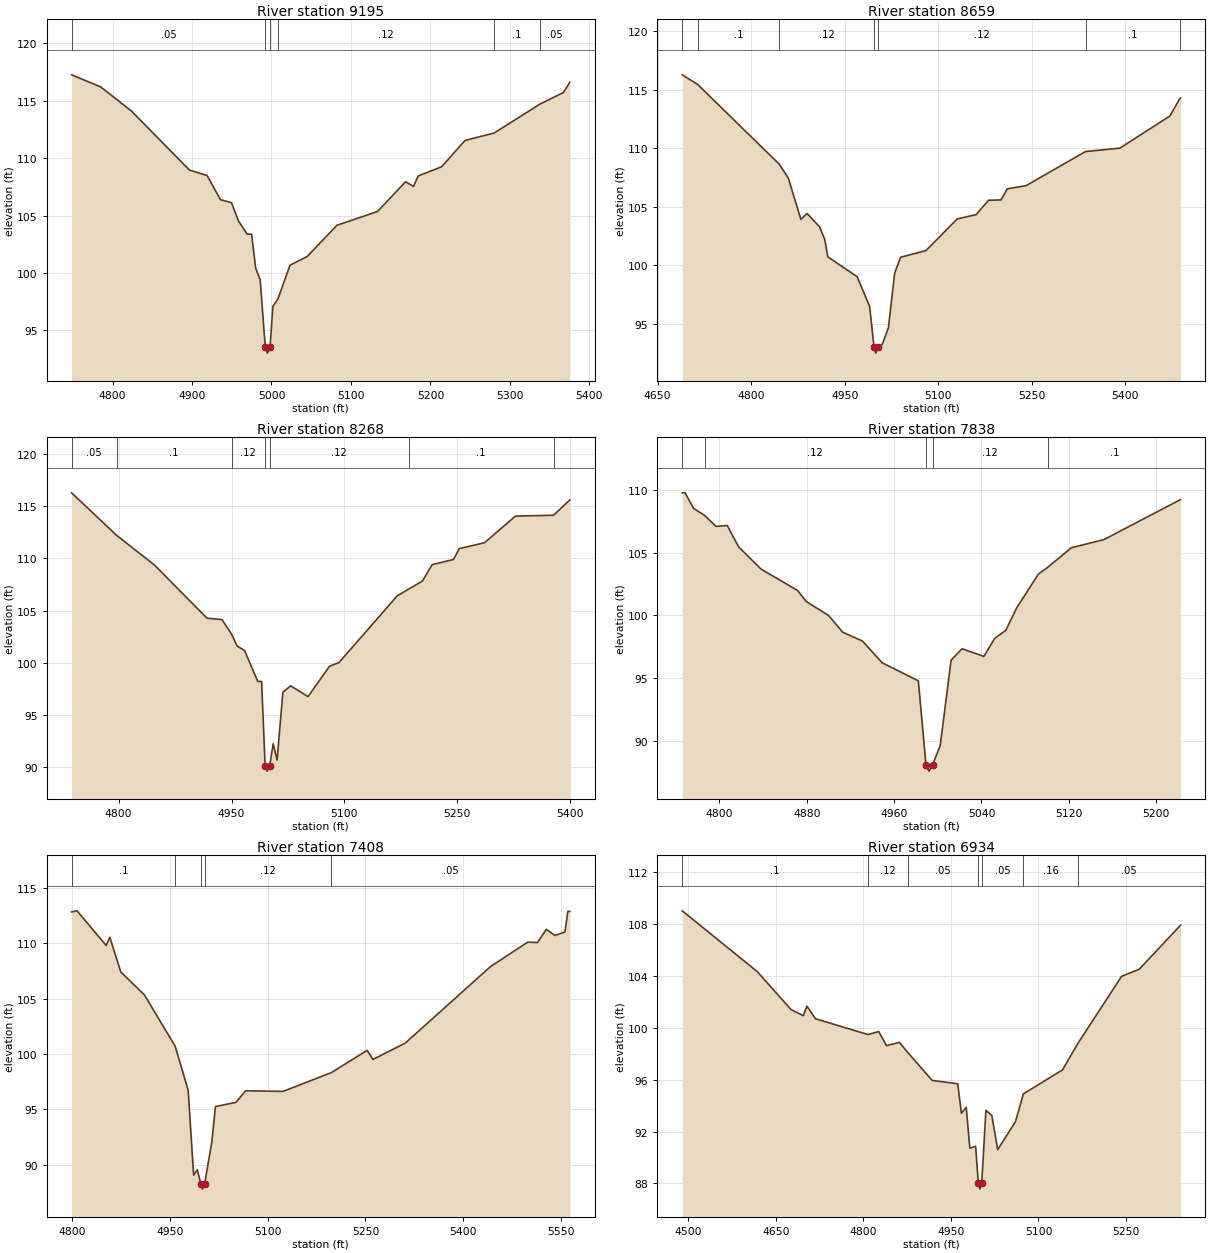
Type RM Length L Ch R = 1 ,9195    ,536,536,536
BEGIN DESCRIPTION:
BAYOU CREEK TRIB 3 13.0
END DESCRIPTION:
XS GIS Cut Line= 3
      2363137.75     13214546.87      2362937.72     13214446.85
      2362587.68     13214246.83
#Sta/Elev= 30
  4748.5  117.24  4784.9   116.2    4824  114.08  4896.7  108.96    4919  108.48
  4935.8  106.38  4949.8  106.11  4958.2  104.56  4969.3  103.38    4975  103.38
  4980.1  100.43  4985.8    99.4  4992.2   93.53  4994.9   93.03  4998.2   93.53
  5001.7   97.08  5008.2   97.76  5023.3  100.68  5044.8  101.43  5082.3  104.15
  5133.4  105.35  5168.7  107.94  5178.7  107.53  5184.5  108.44    5214  109.24
  5243.5  111.53  5280.2  112.18  5337.9   114.7  5367.3   115.7  5375.3  116.59
#Mann= 6 ,-1 , 0
  4748.5     .05       0  4992.2     .03       0  4998.2     .05       0
  5008.2     .12       0  5280.2      .1       0  5337.9     .05       0
Bank Sta=4992.2,4998.2
XS Rating Curve= 0 ,0
Exp/Cntr=0.3,0.1

Type RM Length L Ch R = 1 ,8659    ,391,391,391
BEGIN DESCRIPTION:
BAYOU CREEK TRIB 3 12.0
END DESCRIPTION:
XS GIS Cut Line= 2
      2363467.34     13213990.68      2362670.78     13213925.74
#Sta/Elev= 30
  4689.5  116.28  4714.3  115.45  4845.2  108.63  4859.7  107.44  4879.7  103.92
  4889.8  104.42  4909.8  103.28    4918   102.2    4923  100.71    4970   99.02
  4990.1   96.46  4997.1   92.98  4999.9   92.48  5003.1   92.98  5010.2    93.2
  5020.2   94.66  5030.2   99.32  5039.7  100.68  5080.4  101.25  5130.6  103.96
  5160.7  104.32  5180.7  105.55  5200.8  105.58  5210.8  106.53  5240.9   106.8
  5336.4  109.72  5391.4  110.01  5471.7  112.76  5487.2  114.21  5488.7   114.3
#Mann= 7 ,-1 , 0
  4689.5     .05       0  4714.3      .1       0  4845.2     .12       0
  4997.1     .07       0  5003.1     .12       0  5336.4      .1       0
  5487.2     .05       0
Bank Sta=4997.1,5003.1
XS Rating Curve= 0 ,0
Exp/Cntr=0.3,0.1

Type RM Length L Ch R = 1 ,8268    ,430,430,430
BEGIN DESCRIPTION:
BAYOU CREEK TRIB 3 11.0
END DESCRIPTION:
XS GIS Cut Line= 3
       2363437.7     13213596.85      2363187.72     13213596.85
      2362787.71     13213496.85
#Sta/Elev= 30
  4737.4  116.29  4797.3  112.21  4847.4  109.38  4917.4  104.27  4937.4  104.13
  4950.1  102.73  4957.4  101.61  4967.4  101.16  4984.9    98.2    4990    98.2
  4994.7    90.1  4997.4    89.6  5000.7    90.1  5005.4   92.23  5010.6   90.66
  5018.3   97.17  5028.6   97.78  5051.8   96.75  5080.2   99.65    5093  100.02
  5170.3  106.41  5185.8  107.07  5203.8  107.83  5216.7   109.4  5245.1   109.9
  5252.8  110.94  5286.3   111.5  5327.5  114.06  5378.1  114.14  5399.7  115.61
#Mann= 7 ,-1 , 0
  4737.4     .05       0  4797.3      .1       0  4950.1     .12       0
  4994.7     .07       0  5000.7     .12       0  5185.8      .1       0
  5378.1     .05       0
Bank Sta=4994.7,5000.7
XS Rating Curve= 0 ,0
Exp/Cntr=0.3,0.1

Type RM Length L Ch R = 1 ,7838    ,430,430,430
BEGIN DESCRIPTION:
BAYOU CREEK TRIB 3 10.0
END DESCRIPTION:
XS GIS Cut Line= 3
      2363437.71     13213246.85      2363237.72     13213196.85
      2362987.77     13213196.85
#Sta/Elev= 30
  4766.1  109.78  4768.7  109.78  4776.4  108.54  4786.5  107.98    4797   107.1
  4807.3  107.17  4817.6  105.47  4838.2  103.69  4871.7  101.98  4879.5  101.11
  4900.1   99.98    4913   98.65    4931   97.95  4949.1   96.21  4982.2   94.77
  4989.2   88.06    4992   87.56  4995.2   88.06  5002.2   89.58  5012.2   96.42
  5022.2   97.33  5042.2   96.72  5052.2   98.17  5062.2   98.79  5072.2  100.59
  5092.2   103.3  5100.9  103.85  5122.2  105.39  5152.2  106.05  5222.2  109.24
#Mann= 5 ,-1 , 0
  4766.1      .1       0  4786.5     .12       0  4989.2     .07       0
  4995.2     .12       0  5100.9      .1       0
Bank Sta=4989.2,4995.2
XS Rating Curve= 0 ,0
Exp/Cntr=0.3,0.1

Type RM Length L Ch R = 1 ,7408    ,474,474,474
BEGIN DESCRIPTION:
BAYOU CREEK TRIB 3 9.0
END DESCRIPTION:
XS GIS Cut Line= 3
      2363537.75     13212896.87      2363337.72     13212796.85
      2362887.69     13213096.87
#Sta/Elev= 30
  4799.1  112.85  4807.5  112.95  4852.2  109.82  4857.8  110.56  4874.6  107.43
  4910.9  105.35    4958  100.72    4978   96.74  4986.4   89.07    4992   89.55
  4997.4    88.3  5000.1    87.8  5003.4    88.3  5014.3   92.07  5019.9   95.26
  5051.3   95.64  5066.3   96.69  5123.4   96.63  5197.4   98.32  5252.6  100.34
  5261.6   99.52  5311.2     101  5441.9  107.91    5499  110.12    5514  110.08
  5527.5  111.28    5541  110.72  5556.1  111.04  5560.6   112.9  5563.6   112.9
#Mann= 5 ,-1 , 0
  4799.1      .1       0    4958     .12       0  4997.4     .07       0
  5003.4     .12       0  5197.4     .05       0
Bank Sta=4997.4,5003.4
XS Rating Curve= 0 ,0
Exp/Cntr=0.3,0.1

Type RM Length L Ch R = 1 ,6934    ,452,452,452
BEGIN DESCRIPTION:
BAYOU CREEK TRIB 3 8.0
END DESCRIPTION:
XS GIS Cut Line= 3
      2363637.75     13212746.89      2363337.72     13212346.85
      2362987.72     13212296.85
#Sta/Elev= 30
  4489.7  109.04  4617.9  104.36  4676.2  101.41    4697  100.95  4703.3  101.68
  4717.9  100.71  4807.9   99.49  4826.2   99.72  4839.7   98.63  4861.6   98.89
  4875.6   98.13  4917.9   95.95  4961.6   95.69  4967.9   93.42  4976.2   93.87
  4982.4   90.72  4992.3   90.86  4996.8   88.06  4999.6   87.56  5002.8   88.06
  5009.9   93.64    5020   93.25  5030.1   90.61  5060.5   92.76  5074.1   94.91
  5141.3   96.77  5167.4    98.8  5242.3  103.98  5272.6  104.53  5343.3  107.93
#Mann= 7 ,-1 , 0
  4489.7      .1       0  4807.9     .12       0  4875.6     .05       0
  4996.8     .04       0  5002.8     .05       0  5074.1     .16       0
  5167.4     .05       0
Bank Sta=4996.8,5002.8
XS Rating Curve= 0 ,0
Exp/Cntr=0.3,0.1

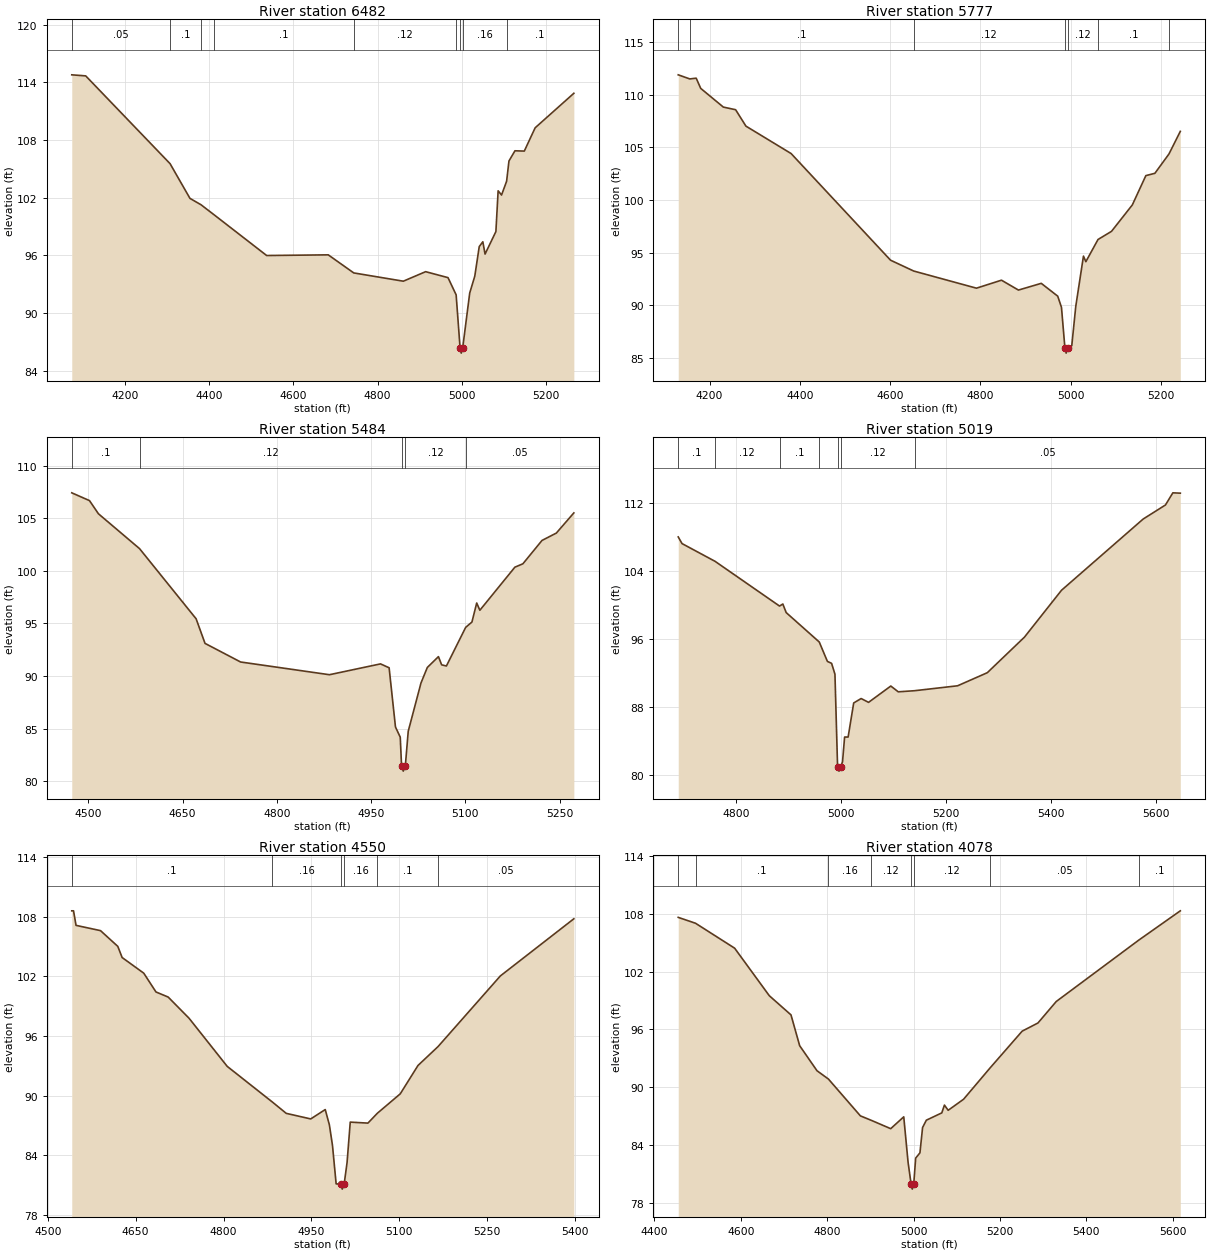
Type RM Length L Ch R = 1 ,6482    ,705,705,705
BEGIN DESCRIPTION:
BAYOU CREEK TRIB 3 7.0
END DESCRIPTION:
XS GIS Cut Line= 3
      2363833.35     13212869.72      2363619.32     13212154.83
      2363472.48     13211735.01
#Sta/Elev= 30
  4074.6  114.78  4107.7  114.67  4307.8  105.54    4355  101.93  4381.2  101.27
  4411.8  100.24  4536.9   95.99    4683   96.06  4743.5   94.18  4861.1   93.32
    4914   94.31  4967.1   93.69  4986.4    91.9  4995.8   86.34  4998.5   85.84
  5001.8   86.34  5018.6   92.09  5030.6   93.84  5041.2   96.92  5049.7   97.42
    5055   96.14  5080.7   98.48    5086  102.72  5094.1  102.28  5106.1  103.71
  5111.7  105.82  5125.9  106.88  5148.1  106.85  5173.8  109.27  5265.6  112.86
#Mann= 9 ,-1 , 0
  4074.6     .05       0  4307.8      .1       0  4381.2     .05       0
  4411.8      .1       0  4743.5     .12       0  4986.4     .16       0
  4995.8     .07       0  5001.8     .16       0  5106.1      .1       0
Bank Sta=4995.8,5001.8
XS Rating Curve= 0 ,0
Exp/Cntr=0.3,0.1

Type RM Length L Ch R = 1 ,5777    ,293,293,293
BEGIN DESCRIPTION:
BAYOU CREEK TRIB 3 6.0
END DESCRIPTION:
XS GIS Cut Line= 4
      2364006.94     13212876.64      2364038.19      13212178.7
      2363947.92     13211918.28      2363951.36     13211780.59
#Sta/Elev= 30
  4130.6  111.91  4156.2  111.52  4170.4  111.59  4180.4  110.62  4230.5  108.84
  4257.7  108.59  4280.5  107.03  4380.6  104.42  4600.9   94.27  4652.2   93.24
  4791.1   91.61  4846.5   92.37  4884.1   91.43  4934.6   92.07  4971.1   90.85
  4979.4   89.79    4987   85.93  4989.7   85.43    4993   85.93  5002.2   86.13
  5011.1   89.89  5028.1   94.66  5033.4   94.13  5060.3   96.24  5090.3   97.02
  5136.3   99.53  5166.3  102.32  5186.3  102.54  5217.5  104.38  5242.6  106.53
#Mann= 7 ,-1 , 0
  4130.6     .05       0  4156.2      .1       0  4652.2     .12       0
    4987     .07       0    4993     .12       0  5060.3      .1       0
  5217.5     .05       0
Bank Sta=4987,4993
XS Rating Curve= 0 ,0
Exp/Cntr=0.3,0.1

Type RM Length L Ch R = 1 ,5484    ,465,465,465
BEGIN DESCRIPTION:
BAYOU CREEK TRIB 3 5.0
END DESCRIPTION:
XS GIS Cut Line= 3
      2364587.69     13212546.82      2364237.72     13212196.85
      2364187.72     13211896.82
#Sta/Elev= 30
  4473.5  107.42  4501.7  106.68  4515.9  105.43  4581.4  102.11  4671.4   95.44
  4685.6    93.1  4742.2   91.33  4883.6   90.12  4964.9   91.15  4978.6   90.78
  4988.7   85.15  4996.3   84.18  4998.4   81.45  5001.1   80.95  5004.4   81.45
    5009   84.74  5029.3   89.33  5039.4   90.81  5057.1   91.84  5062.2   91.06
  5069.8   90.95  5100.4   94.62  5110.4   95.13    5118   96.94    5123   96.25
  5178.8  100.35  5191.5  100.67  5221.9  102.89  5244.7  103.59  5272.6  105.51
#Mann= 5 ,-1 , 0
  4473.5      .1       0  4581.4     .12       0  4998.4     .07       0
  5004.4     .12       0  5100.4     .05       0
Bank Sta=4998.4,5004.4
XS Rating Curve= 0 ,0
Exp/Cntr=0.3,0.1

Type RM Length L Ch R = 1 ,5019    ,469,469,469
BEGIN DESCRIPTION:
BAYOU CREEK TRIB 3 4.0
END DESCRIPTION:
XS GIS Cut Line= 3
      2364887.74     13212346.87      2364637.72     13212146.85
      2364187.71     13211696.84
#Sta/Elev= 30
  4690.5  108.05  4697.7  107.27  4760.7  105.18  4883.5   99.92  4889.8  100.16
  4896.2   99.15  4959.2   95.69  4974.7   93.41  4982.7   93.18  4989.1    91.9
  4994.1      81  4996.8    80.5  5000.1      81  5003.5   81.59  5007.5   84.51
  5014.2   84.51  5024.8   88.52    5039   89.04  5053.1   88.59  5095.5   90.51
  5109.7   89.83  5140.8   89.96  5222.8   90.54  5279.4   92.08  5350.1   96.26
  5420.8  101.78  5576.4  110.16  5618.8  111.81  5632.9  113.24  5647.1   113.2
#Mann= 7 ,-1 , 0
  4690.5      .1       0  4760.7     .12       0  4883.5      .1       0
  4959.2     .12       0  4994.1     .07       0  5000.1     .12       0
  5140.8     .05       0
Bank Sta=4994.1,5000.1
XS Rating Curve= 0 ,0
Exp/Cntr=0.3,0.1

Type RM Length L Ch R = 1 ,4550    ,472,472,472
BEGIN DESCRIPTION:
BAYOU CREEK TRIB 3 3.0
END DESCRIPTION:
XS GIS Cut Line= 3
       2365087.7     13212096.83      2364837.72     13211746.85
      2364437.71     13211596.85
#Sta/Elev= 30
  4540.9  108.57  4543.9  108.57  4548.2  107.11    4590  106.58  4619.5     105
  4626.9  103.88  4663.8  102.31  4684.7  100.42  4705.5   99.91  4741.2   97.78
  4806.3   92.95  4883.6   89.36  4907.1   88.23  4948.9   87.67  4973.7   88.61
  4980.8   87.07  4986.1      85  4992.3   81.15    5000   81.12  5002.8   80.62
    5006   81.12    5011    83.3  5016.4   87.35  5046.6   87.25  5062.7   88.24
  5101.8   90.19  5132.1   93.04  5166.4   94.94  5272.7  102.03  5398.2  107.77
#Mann= 6 ,-1 , 0
  4540.9      .1       0  4883.6     .16       0    5000     .07       0
    5006     .16       0  5062.7      .1       0  5166.4     .05       0
Bank Sta=5000,5006
XS Rating Curve= 0 ,0
Exp/Cntr=0.3,0.1

Type RM Length L Ch R = 1 ,4078    ,343,343,343
BEGIN DESCRIPTION:
BAYOU CREEK TRIB 3 2.0
END DESCRIPTION:
XS GIS Cut Line= 3
      2365237.72     13212046.88      2365187.72     13211496.85
      2364687.74     13211146.87
#Sta/Elev= 30
    4455  107.63    4495  107.02  4585.6  104.43  4665.9   99.49  4716.1    97.5
  4736.2    94.3  4776.3    91.7  4802.9   90.83  4876.8   87.01  4902.4   86.54
    4947   85.68  4977.2   86.91  4987.2    82.2  4994.3    79.9    4997    79.4
  5000.3    79.9  5004.8   82.62  5014.7   83.17  5020.8    85.8  5029.5   86.56
  5065.3   87.32  5071.4   88.13  5080.1   87.59  5115.8   88.74  5177.3      92
  5251.4   95.81    5288   96.66  5330.3   98.89  5521.2  105.26  5617.6  108.31
#Mann= 8 ,-1 , 0
    4455     .05       0    4495      .1       0  4802.9     .16       0
  4902.4     .12       0  4994.3     .07       0  5000.3     .12       0
  5177.3     .05       0  5521.2      .1       0
Bank Sta=4994.3,5000.3
XS Rating Curve= 0 ,0
Exp/Cntr=0.3,0.1

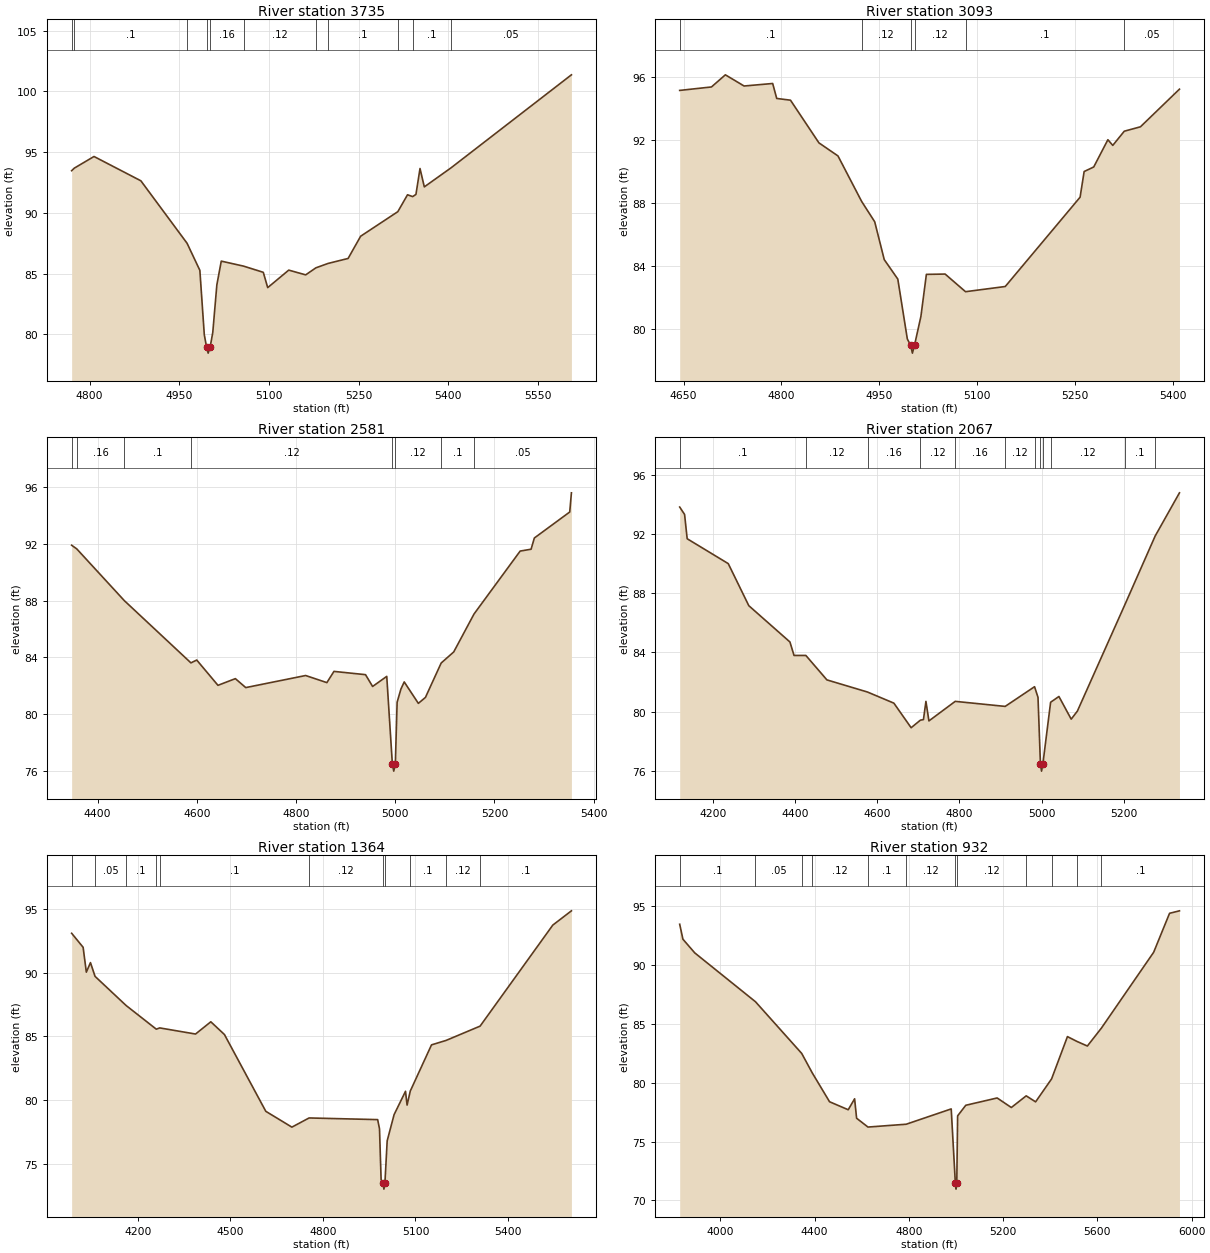
Type RM Length L Ch R = 1 ,3735    ,642,642,642
BEGIN DESCRIPTION:
Mapping XS 0cd750d3
END DESCRIPTION:
XS GIS Cut Line= 2
      2365644.08     13211513.75      2365082.18     13210894.62
#Sta/Elev= 30
    4770   93.47  4774.4   93.68  4807.4   94.64  4885.8   92.64  4963.1    87.5
  4984.5   85.27  4991.9   79.98  4995.7   78.96  4998.4   78.46  5001.7   78.96
  5006.1   80.16  5012.9   84.07  5020.3   86.03  5057.5   85.62  5090.6   85.11
    5098   83.85  5133.2   85.29  5161.5    84.9  5178.7   85.48    5199   85.84
  5232.5   86.25  5253.5   88.08  5315.7    90.1  5331.9   91.49  5340.5   91.34
    5346   91.52  5352.8   93.65    5360   92.14  5404.8   93.71  5606.1  101.36
#Mann= 11 ,-1 , 0
    4770     .05       0  4774.4      .1       0  4963.1     .16       0
  4995.7     .07       0  5001.7     .16       0  5057.5     .12       0
  5178.7     .16       0    5199      .1       0  5315.7     .05       0
  5340.5      .1       0  5404.8     .05       0
Bank Sta=4995.7,5001.7
XS Rating Curve= 0 ,0
Exp/Cntr=0.3,0.1

Type RM Length L Ch R = 1 ,3093    ,512,512,512
BEGIN DESCRIPTION:
Mapping XS 01d787f5
END DESCRIPTION:
XS GIS Cut Line= 2
      2366013.85     13211029.37      2365399.81     13210571.44
#Sta/Elev= 30
  4644.1   95.16  4692.8   95.38  4714.1   96.15  4742.8   95.44  4786.6    95.6
  4792.8   94.65  4813.9   94.54  4857.5   91.83  4886.7      91    4923   88.11
    4943   86.82  4957.6   84.42  4978.4   83.18    4993   79.38    4998   78.98
  5000.8   78.48    5004   78.98  5013.8   80.81  5022.2   83.48  5050.9    83.5
  5082.2   82.38  5143.1   82.71  5257.8   88.38    5264   90.01  5278.7    90.3
  5300.4   92.03  5307.9   91.67  5325.5   92.57  5350.3   92.85  5410.1   95.24
#Mann= 6 ,-1 , 0
  4644.1      .1       0    4923     .12       0    4998     .07       0
    5004     .12       0  5082.2      .1       0  5325.5     .05       0
Bank Sta=4998,5004
XS Rating Curve= 0 ,0
Exp/Cntr=0.3,0.1

Type RM Length L Ch R = 1 ,2581    ,514,514,514
BEGIN DESCRIPTION:
Mapping XS 265b3d92
END DESCRIPTION:
XS GIS Cut Line= 2
      2366357.61     13210852.27      2365702.07     13210087.48
#Sta/Elev= 30
  4347.9   91.89    4358   91.64  4454.1   87.99  4588.3   83.61    4600   83.81
  4642.8   82.03  4677.9    82.5  4698.8   81.87  4819.5   82.72  4862.3   82.22
  4876.6   83.01  4940.2   82.78  4954.5   81.95    4983   82.66  4994.3   76.49
  4997.1   75.99  5000.3   76.49  5003.9   80.84  5011.6   81.77  5018.2   82.27
  5046.7   80.76    5061   81.18  5092.7    83.6    5118   84.38  5158.9   87.05
  5251.9   91.48  5273.9   91.61  5280.5    92.4  5351.8   94.23  5355.2   95.58
#Mann= 8 ,-1 , 0
  4347.9     .12       0    4358     .16       0  4454.1      .1       0
  4588.3     .12       0  4994.3     .07       0  5000.3     .12       0
  5092.7      .1       0  5158.9     .05       0
Bank Sta=4994.3,5000.3
XS Rating Curve= 0 ,0
Exp/Cntr=0.3,0.1

Type RM Length L Ch R = 1 ,2067    ,703,703,703
BEGIN DESCRIPTION:
Mapping XS 51710047
END DESCRIPTION:
XS GIS Cut Line= 3
      2366493.05     13210795.01      2366477.43     13210295.02
      2366076.58     13209701.55
#Sta/Elev= 30
  4119.3   93.81  4131.2   93.31  4137.5   91.67  4237.5   89.99  4287.5   87.15
  4387.6    84.7  4397.6   83.79  4426.4   83.79  4477.6   82.14  4576.4   81.32
  4640.6   80.57  4682.6   78.91  4705.1   79.42  4712.6   79.46  4718.6   80.69
  4725.9   79.37  4789.9   80.69  4911.5   80.35    4983   81.68  4991.4   80.96
  4997.3   76.48    5000   75.98  5003.3   76.48  5022.1   80.63  5042.3   81.02
  5072.2   79.49  5087.2   80.03  5202.7   87.21  5276.5   91.85  5335.7   94.77
#Mann= 12 ,-1 , 0
  4119.3      .1       0  4426.4     .12       0  4576.4     .16       0
  4705.1     .12       0  4789.9     .16       0  4911.5     .12       0
    4983     .16       0  4997.3     .07       0  5003.3     .16       0
  5022.1     .12       0  5202.7      .1       0  5276.5     .05       0
Bank Sta=4997.3,5003.3
XS Rating Curve= 0 ,0
Exp/Cntr=0.3,0.1

Type RM Length L Ch R = 1 ,1364    ,432,432,432
BEGIN DESCRIPTION:
Mapping XS 0dc58f7e
END DESCRIPTION:
XS GIS Cut Line= 4
      2366576.38     13210732.56      2366784.72     13210013.77
      2366888.89     13209576.27      2366519.11     13209373.15
#Sta/Elev= 30
  3985.6   93.09  4022.8   91.99  4033.2   90.04  4046.6   90.79  4061.5   89.71
    4162   87.43    4260   85.57  4271.1   85.67  4387.2   85.19  4436.7   86.15
  4480.9   85.15    4615   79.13  4699.5   77.89  4755.2   78.61  4977.5   78.48
  4983.5   77.76  4988.7   73.77  4995.1   73.53  4997.8   73.03  5001.1   73.53
  5008.4   76.82  5030.8   78.87  5067.8    80.7  5072.9   79.62  5083.3   80.72
  5152.1   84.34  5199.4   84.69  5309.6   85.81  5545.2   93.73  5605.6   94.85
#Mann= 11 ,-1 , 0
  3985.6      .1       0  4061.5     .05       0    4162      .1       0
    4260     .05       0  4271.1      .1       0  4755.2     .12       0
  4995.1     .07       0  5001.1     .12       0  5083.3      .1       0
  5199.4     .12       0  5309.6      .1       0
Bank Sta=4995.1,5001.1
XS Rating Curve= 0 ,0
Exp/Cntr=0.3,0.1

Type RM Length L Ch R = 1 ,932     ,817,817,817
BEGIN DESCRIPTION:
Mapping XS fbb5824b
END DESCRIPTION:
XS GIS Cut Line= 4
      2366644.07     13210722.14      2367190.97     13209982.52
      2367289.93     13209576.27      2366586.84     13209232.54
#Sta/Elev= 30
  3827.8   93.45  3841.5   92.18  3891.6   91.02  4149.4   86.87  4345.6   82.48
    4390   80.84  4463.6   78.38  4542.9    77.7    4570   78.63  4578.4   76.98
  4626.7   76.23  4788.8   76.47  4979.9   77.77  4997.5   71.46  5000.3   70.96
  5003.5   71.46  5007.1   77.18  5041.7   78.08  5174.8    78.7    5235   77.89
  5298.1   78.88    5338   78.37  5405.8   80.32  5473.1   83.91  5513.5    83.5
  5557.6   83.11  5617.1   84.63  5838.9   91.07  5906.4   94.38  5948.4   94.59
#Mann= 12 ,-1 , 0
  3827.8      .1       0  4149.4     .05       0  4345.6      .1       0
    4390     .12       0  4626.7      .1       0  4788.8     .12       0
  4997.5     .07       0  5003.5     .12       0  5298.1      .1       0
  5405.8     .05       0  5513.5     .12       0  5617.1      .1       0
Bank Sta=4997.5,5003.5
XS Rating Curve= 0 ,0
Exp/Cntr=0.3,0.1

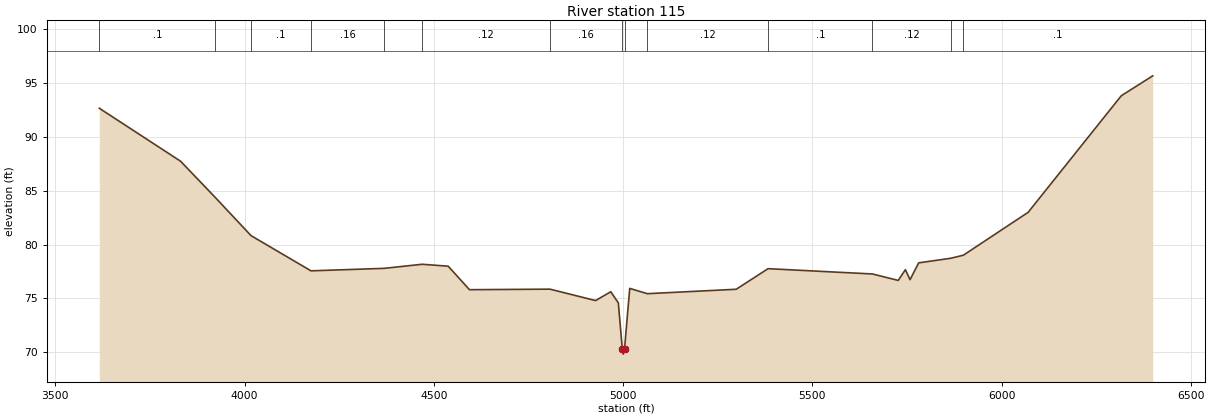
Type RM Length L Ch R = 1 ,115     ,0,0,0
BEGIN DESCRIPTION:
BAYOU CREEK TRIB 3 1.0
END DESCRIPTION:
XS GIS Cut Line= 5
      2366701.41     13210711.67      2367618.05     13210013.77
      2367670.14     13209961.68       2367706.6     13209508.56
      2366681.64     13209102.74
#Sta/Elev= 30
  3616.4   92.65  3831.2   87.73  3923.2   84.35  4017.1   80.83  4175.5   77.56
  4368.3   77.79  4469.5   78.17    4538   77.99  4594.2   75.81  4806.8   75.86
  4927.2    74.8  4967.4   75.62  4987.4   74.59  4997.8   70.33  5000.5   69.83
  5003.8   70.33  5017.5   75.93  5064.2   75.44  5298.8   75.85  5382.9   77.76
  5658.7   77.27  5726.8   76.67  5745.7   77.67    5758   76.74  5780.8    78.3
  5865.9   78.73  5898.8   79.01  6069.9   82.99    6316   93.81  6399.1   95.66
#Mann= 14 ,-1 , 0
  3616.4      .1       0  3923.2     .05       0  4017.1      .1       0
  4175.5     .16       0  4368.3      .1       0  4469.5     .12       0
  4806.8     .16       0  4997.8     .07       0  5003.8     .16       0
  5064.2     .12       0  5382.9      .1       0  5658.7     .12       0
  5865.9     .05       0  5898.8      .1       0
Bank Sta=4997.8,5003.8
XS Rating Curve= 0 ,0
Exp/Cntr=0.3,0.1

Chan Stop Cuts=-1
Use User Specified Reach Order=0
Composite Channel Slope=5