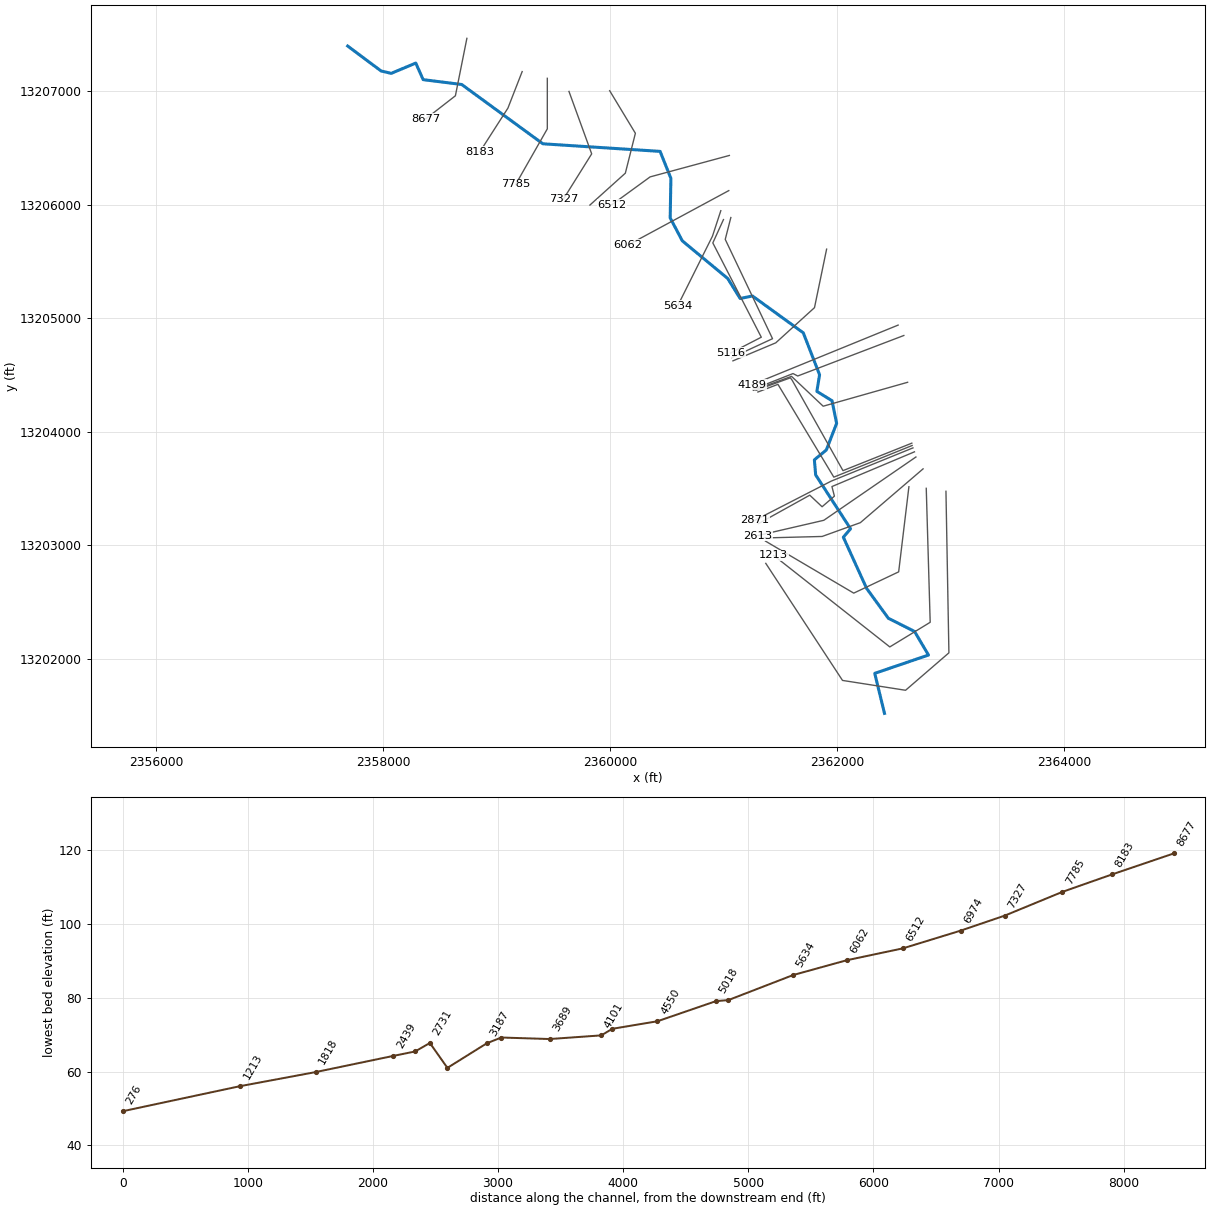
--- BAYOU CREEK TRIB 4.prj (project) ---

Proj Title=BAYOU CREEK TRIB 4 Base Level Engineering
Current Plan=p01
Default Exp/Contr=0.3,0.1
English Units
Geom File=g01
Flow File=f01
Plan File=p01
Y Axis Title=Elevation
X Axis Title(PF)=Main Channel Distance
X Axis Title(XS)=Station
BEGIN DESCRIPTION:
BAYOU CREEK TRIB 4
END DESCRIPTION:
DSS Export Rating Curves= 0
DSS Export Rating Curve Sorted= 0
DSS Export Volume Flow Curves= 0
DXF OffsetX= 0
DXF OffsetY= 0
DXF ScaleX= 1
DXF ScaleY= 10

--- BAYOU CREEK TRIB 4.p01 (plan) ---

Plan Title=Multiple Run
Short Identifier=Multiple
Geom File=g01
Flow File=f01
Subcritical Flow
K Sum by GR= 0
Std Step Tol= 0.01
Critical Tol= 0.01
Num of Std Step Trials= 20
Max Error Tol= 0.3
Flow Tol Ratio= 0.001
Split Flow NTrial= 30
Split Flow Tol= 0.02
Split Flow Ratio= 0.02
Log Output Level= 0
Friction Slope Method= 1
Unsteady Friction Slope Method= 2
Unsteady Bridges Friction Slope Method= 1
Parabolic Critical Depth
Global Vel Dist=  1 , 1 , 1
Global Log Level= 0
CheckData=True
Encroach Param= -1, 0, 0, 0
BEGIN DESCRIPTION:
Multiple Run
END DESCRIPTION:

--- BAYOU CREEK TRIB 4.f01 (steady flow) ---

Flow Title=Multiple
Program Version=4.10
Number of Profiles= 7
Profile Names=10-year,25-year,50-year,1pct_min,100-year,1pct_plu,500-year
River Rch & RM=BAYOU CREEK TRIB,Reach-1         ,8677
     323     425     504     435     589     796     807
River Rch & RM=BAYOU CREEK TRIB,Reach-1         ,7327
     632     870    1063     947    1280    1731    1863
River Rch & RM=BAYOU CREEK TRIB,Reach-1         ,4101
     715     994    1222    1095    1481    2003    2183
Boundary for River Rch & Prof#=BAYOU CREEK TRIB,Reach-1         , 1
Up Type= 0
Dn Type= 3
Dn Slope=0.005
Boundary for River Rch & Prof#=BAYOU CREEK TRIB,Reach-1         , 2
Up Type= 0
Dn Type= 3
Dn Slope=0.005
Boundary for River Rch & Prof#=BAYOU CREEK TRIB,Reach-1         , 3
Up Type= 0
Dn Type= 3
Dn Slope=0.005
Boundary for River Rch & Prof#=BAYOU CREEK TRIB,Reach-1         , 4
Up Type= 0
Dn Type= 3
Dn Slope=0.005
Boundary for River Rch & Prof#=BAYOU CREEK TRIB,Reach-1         , 5
Up Type= 0
Dn Type= 3
Dn Slope=0.005
Boundary for River Rch & Prof#=BAYOU CREEK TRIB,Reach-1         , 6
Up Type= 0
Dn Type= 3
Dn Slope=0.005
Boundary for River Rch & Prof#=BAYOU CREEK TRIB,Reach-1         , 7
Up Type= 0
Dn Type= 3
Dn Slope=0.005
DSS Import GetInterval= 0
DSS Import GetPeak= 0
DSS Import FillOption= 0

--- BAYOU CREEK TRIB 4.g01 (geometry) ---

Geom Title=Existing Conditions
Program Version=4.10

River Reach=BAYOU CREEK TRIB,Reach-1
Reach XY= 30
      2357687.72     13207396.85      2357982.31     13207177.04
      2358071.72     13207156.21      2358287.72     13207246.85
      2358352.97     13207100.65      2358692.38     13207058.12
      2359407.66     13206535.55      2360440.65     13206468.71
      2360535.57     13206231.65      2360529.54     13205882.48
      2360636.19     13205680.46      2361036.18     13205348.85
      2361146.25      13205172.4      2361254.25     13205194.67
      2361702.08     13204870.02      2361845.63     13204500.77
      2361821.93     13204353.93      2361955.46     13204271.63
      2361995.99     13204072.16      2361905.22     13203837.84
      2361799.96     13203750.85       2361811.3       13203618.
      2362118.57     13203143.33       2362055.2     13203069.32
      2362260.39     13202617.97      2362451.88     13202354.79
      2362682.49     13202238.63      2362805.28     13202030.86
      2362331.82     13201869.41      2362417.72     13201516.86

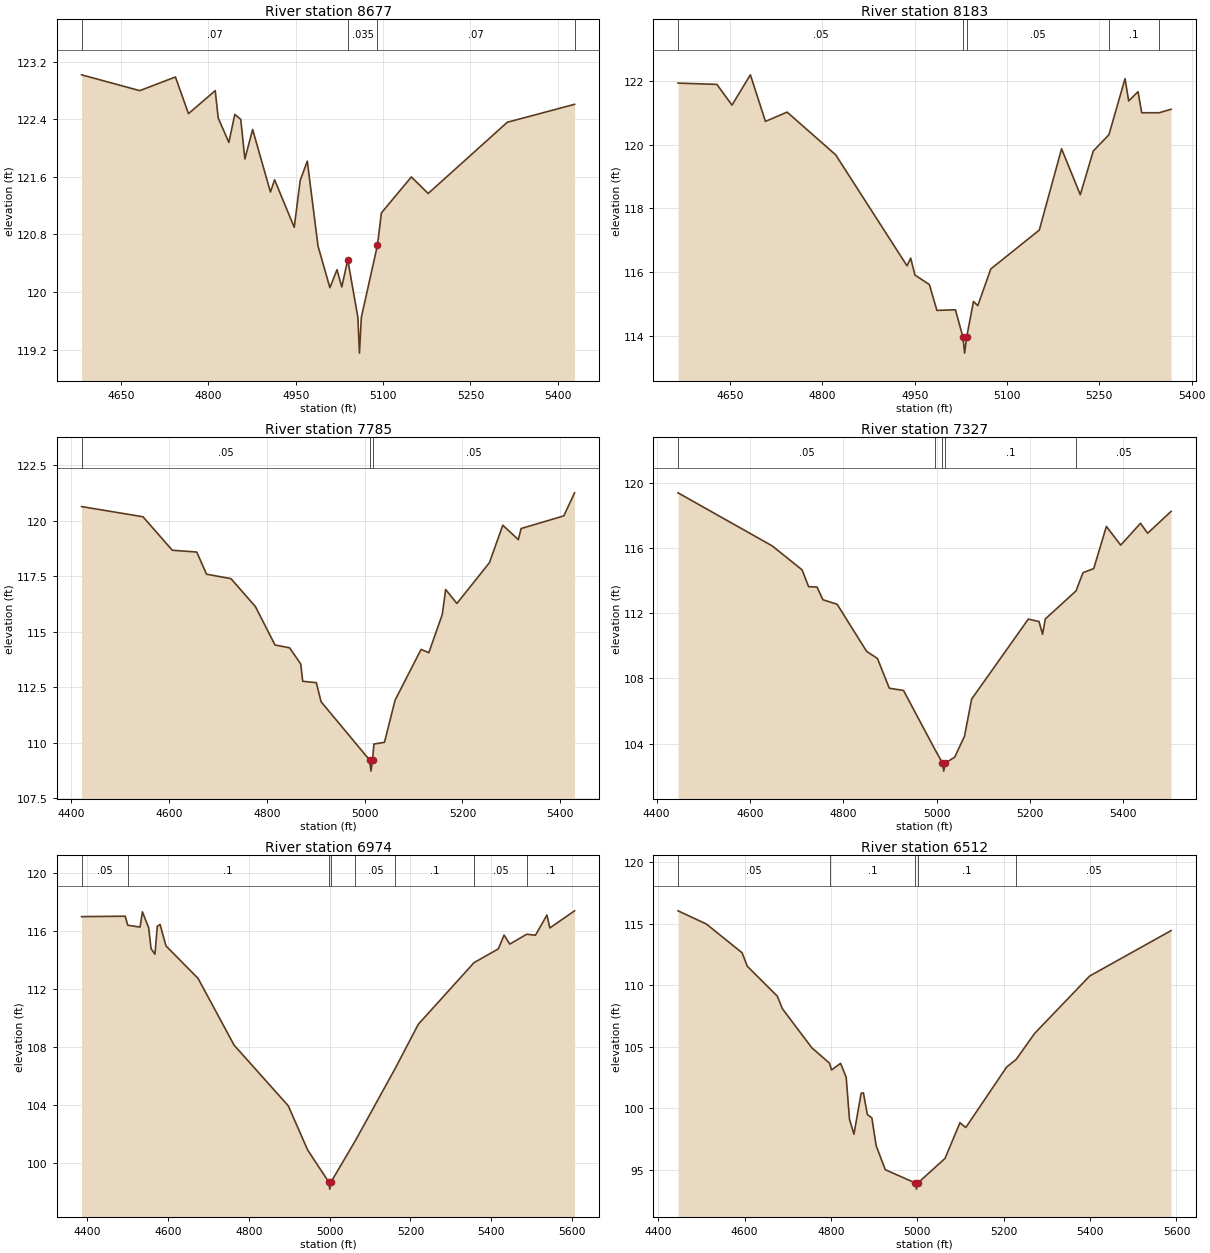
Type RM Length L Ch R = 1 ,8677    ,494,494,494
BEGIN DESCRIPTION:
BAYOU CREEK TRIB 4 16.0
END DESCRIPTION:
XS GIS Cut Line= 3
       2358738.1     13207464.78      2358636.84     13206958.51
      2358376.51     13206756.03
#Sta/Elev= 30
  4582.5  123.02  4682.4   122.8  4743.6  122.99    4766  122.48  4811.9   122.8
    4817  122.42  4835.3  122.08  4845.5  122.47  4855.7   122.4  4862.8  121.85
  4876.1  122.26  4906.7  121.39  4913.8  121.56  4947.5   120.9  4957.7  121.55
  4969.9  121.82  4988.3  120.64  5008.7  120.06  5020.9  120.31  5029.1  120.07
  5039.3  120.45  5056.7  119.65  5059.4  119.15  5062.7  119.65  5090.3  120.65
  5097.1   121.1  5148.5   121.6  5177.4  121.37  5313.1  122.36  5428.6  122.61
#Mann= 4 ,-1 , 0
  4582.5     .07       0  5039.3    .035       0  5090.3     .07       0
  5428.6     .05       0
Bank Sta=5039.3,5090.3
XS Rating Curve= 0 ,0
Exp/Cntr=0.3,0.1

Type RM Length L Ch R = 1 ,8183    ,398,398,398
BEGIN DESCRIPTION:
BAYOU CREEK TRIB 4 15.0
END DESCRIPTION:
XS GIS Cut Line= 3
      2359225.21     13207171.83       2359099.7     13206850.03
      2358853.81     13206466.73
#Sta/Elev= 30
  4565.7  121.93  4628.8  121.89  4653.3  121.24  4683.2  122.19  4707.7  120.73
  4742.9  121.02  4821.8  119.68  4937.6   116.2  4943.6  116.44  4950.5  115.91
    4974  115.61  4986.2   114.8  5016.3  114.82  5028.5  113.96  5031.2  113.46
  5034.5  113.96  5045.6  115.08  5052.6  114.95  5073.7   116.1  5152.5  117.32
  5188.7  119.87  5219.1  118.43  5240.2   119.8  5265.6  120.31  5291.8  122.07
  5297.7  121.37  5312.9  121.66  5318.9     121  5347.2     121  5366.5  121.11
#Mann= 5 ,-1 , 0
  4565.7     .05       0  5028.5     .03       0  5034.5     .05       0
  5265.6      .1       0  5347.2     .05       0
Bank Sta=5028.5,5034.5
XS Rating Curve= 0 ,0
Exp/Cntr=0.3,0.1

Type RM Length L Ch R = 1 ,7785    ,458,458,458
BEGIN DESCRIPTION:
BAYOU CREEK TRIB 4 14.0
END DESCRIPTION:
XS GIS Cut Line= 3
       2359446.8     13207112.56       2359446.8     13206667.27
      2359168.16      13206177.7
#Sta/Elev= 30
  4420.7  120.64  4546.4  120.18  4606.4  118.67  4656.4  118.59  4676.4  117.59
  4726.4  117.39  4776.4  116.13  4816.4   114.4  4846.4  114.27  4869.1  113.54
  4873.2  112.76    4901   112.7  4910.7  111.84    5010  109.21  5012.8  108.71
    5016  109.21  5018.8  109.93  5040.4  110.01  5062.1  111.91  5115.3   114.2
  5131.1  114.05  5158.6  115.77  5165.6   116.9  5188.6  116.27  5255.1  118.11
  5282.5   119.8  5314.2  119.15    5320  119.65  5407.3  120.22  5429.3  121.26
#Mann= 3 ,-1 , 0
  4420.7     .05       0    5010     .03       0    5016     .05       0
Bank Sta=5010,5016
XS Rating Curve= 0 ,0
Exp/Cntr=0.3,0.1

Type RM Length L Ch R = 1 ,7327    ,353,353,353
BEGIN DESCRIPTION:
BAYOU CREEK TRIB 4 13.0
END DESCRIPTION:
XS GIS Cut Line= 3
      2359637.73     13206996.82      2359837.72     13206446.85
      2359587.72     13206046.85
#Sta/Elev= 30
  4445.9  119.39    4648  116.13  4711.9  114.66  4725.8  113.63  4743.8  113.61
  4756.4  112.83    4787  112.55  4850.2  109.66  4873.5  109.22  4898.8   107.4
  4929.3  107.26    4997  103.62  5012.8  102.81  5015.5  102.31  5018.8  102.81
  5038.8  103.16    5060  104.45  5075.3  106.73  5196.8  111.64  5219.8  111.49
  5227.4  110.71  5233.3  111.65  5299.1  113.37  5314.1  114.49  5337.1  114.74
  5364.2  117.33  5394.9  116.18  5437.3  117.52  5452.7  116.91  5502.8  118.25
#Mann= 5 ,-1 , 0
  4445.9     .05       0    4997      .1       0  5012.8     .07       0
  5018.8      .1       0  5299.1     .05       0
Bank Sta=5012.8,5018.8
XS Rating Curve= 0 ,0
Exp/Cntr=0.3,0.1

Type RM Length L Ch R = 1 ,6974    ,462,462,462
BEGIN DESCRIPTION:
BAYOU CREEK TRIB 4 12.0
END DESCRIPTION:
XS GIS Cut Line= 4
      2359996.27     13207003.22      2360222.84     13206628.21
       2360134.3     13206276.64      2359822.25      13205995.8
#Sta/Elev= 30
  4385.9  116.99  4493.9  117.02  4500.3   116.4  4530.7  116.27  4536.6  117.32
  4552.1  116.22  4557.9  114.79  4567.6   114.4  4573.4  116.33  4580.3  116.45
  4594.8  114.98  4674.3  112.74  4763.6  108.14  4897.6  103.97  4945.7  100.92
  4997.7   98.73  5000.5   98.23  5003.7   98.73    5064  101.58  5162.8  106.56
  5219.6  109.58  5357.4  113.82  5417.7  114.77  5431.9  115.72  5446.1   115.1
  5487.9  115.78  5509.6  115.71    5538   117.1  5545.2  116.21  5606.4  117.39
#Mann= 8 ,-1 , 0
  4385.9     .05       0  4500.3      .1       0  4997.7     .07       0
  5003.7      .1       0    5064     .05       0  5162.8      .1       0
  5357.4     .05       0  5487.9      .1       0
Bank Sta=4997.7,5003.7
XS Rating Curve= 0 ,0
Exp/Cntr=0.3,0.1

Type RM Length L Ch R = 1 ,6512    ,450,450,450
BEGIN DESCRIPTION:
BAYOU CREEK TRIB 4 11.0
END DESCRIPTION:
XS GIS Cut Line= 3
      2361050.92     13206432.88       2360352.7     13206243.99
      2360014.52     13205998.01
#Sta/Elev= 30
  4445.9  116.05  4511.4  114.98  4594.2  112.64  4606.4  111.54  4675.8  109.11
  4687.5  108.09  4755.5  104.92  4796.6  103.66  4801.4  103.11  4822.2  103.65
  4835.2  102.52  4842.9    99.1  4853.2   97.89  4869.9  101.22  4875.1  101.25
  4884.3   99.48  4894.7   99.21  4904.6   96.96  4925.7      95  4995.3   93.92
    4998   93.42  5001.3   93.92  5064.1   95.92  5098.7   98.82  5112.2   98.43
  5206.6  103.34  5228.9  103.97  5271.5  106.08    5399  110.75  5587.4  114.44
#Mann= 5 ,-1 , 0
  4445.9     .05       0  4796.6      .1       0  4995.3     .07       0
  5001.3      .1       0  5228.9     .05       0
Bank Sta=4995.3,5001.3
XS Rating Curve= 0 ,0
Exp/Cntr=0.3,0.1

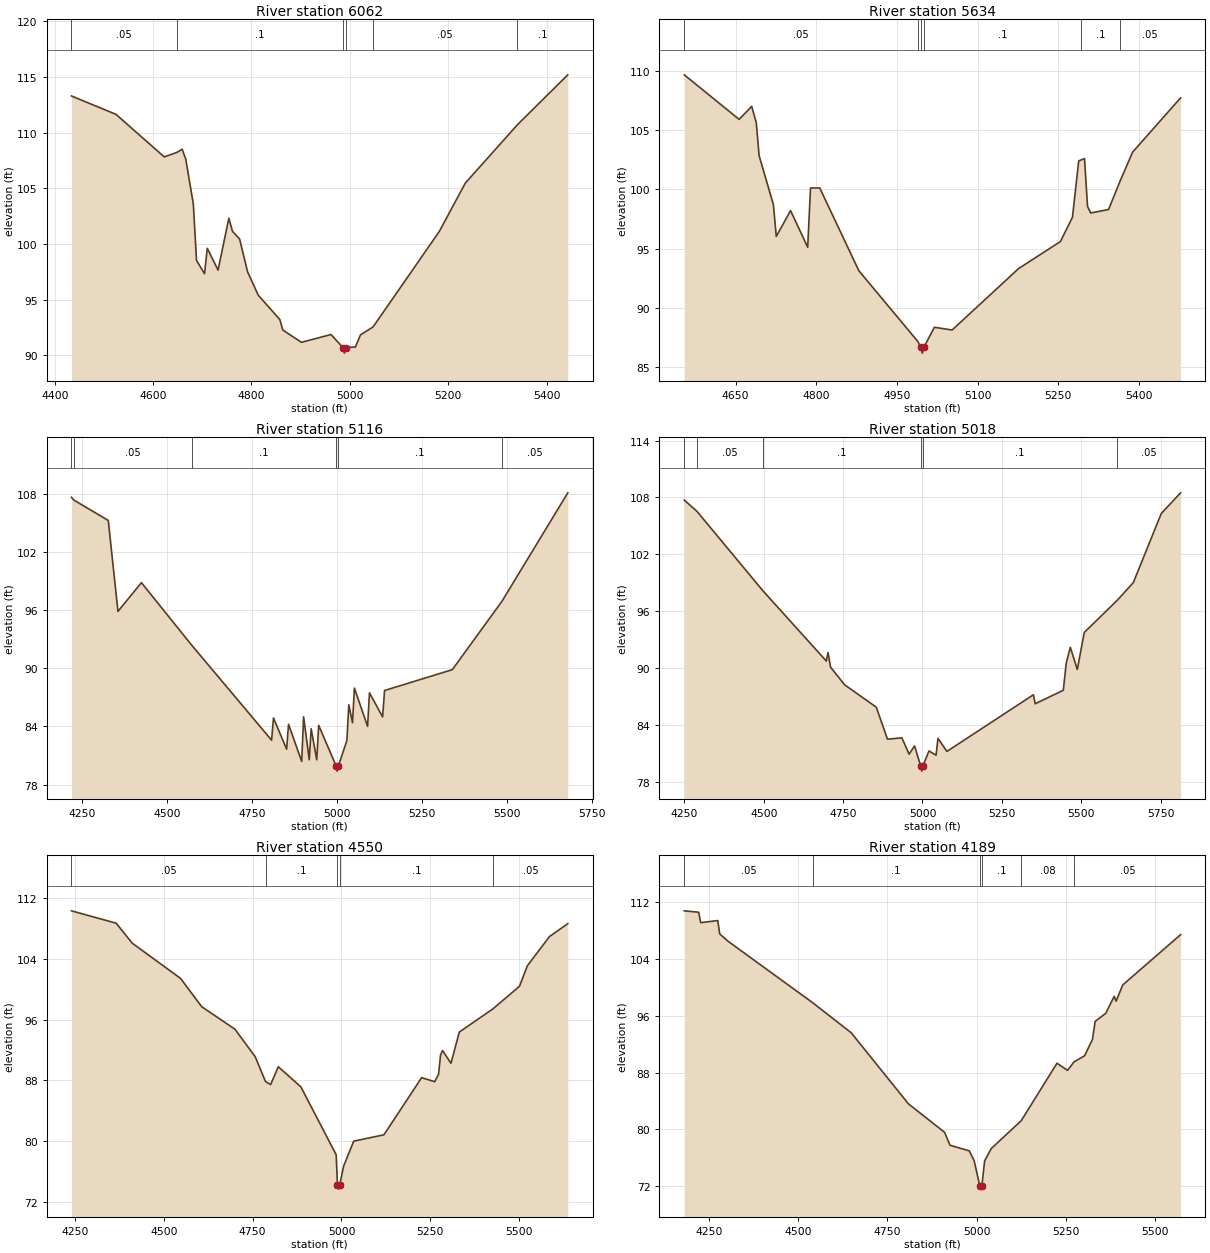
Type RM Length L Ch R = 1 ,6062    ,428,428,428
BEGIN DESCRIPTION:
BAYOU CREEK TRIB 4 10.0
END DESCRIPTION:
XS GIS Cut Line= 2
      2361045.72     13206122.98      2360157.75     13205643.84
#Sta/Elev= 30
  4434.1  113.28  4524.6  111.63  4622.7  107.81  4648.6  108.22  4659.1   108.5
  4666.4  107.61  4681.8  103.59  4688.3   98.52  4704.5   97.32  4710.2    99.6
  4732.1   97.64    4754   102.3  4761.4  101.13  4775.9  100.44  4792.1   97.49
    4814   95.38  4857.8    93.2  4863.6   92.27  4901.6   91.16  4961.6   91.86
  4986.1   90.69  4988.9   90.19  4992.1   90.69  5011.3   90.74  5021.6   91.83
  5047.2   92.54  5181.8  101.11  5234.8  105.46  5340.7   110.7  5443.1  115.18
#Mann= 6 ,-1 , 0
  4434.1     .05       0  4648.6      .1       0  4986.1     .07       0
  4992.1      .1       0  5047.2     .05       0  5340.7      .1       0
Bank Sta=4986.1,4992.1
XS Rating Curve= 0 ,0
Exp/Cntr=0.3,0.1

Type RM Length L Ch R = 1 ,5634    ,518,518,518
BEGIN DESCRIPTION:
BAYOU CREEK TRIB 4 9.0
END DESCRIPTION:
XS GIS Cut Line= 3
      2360975.44     13205945.92      2360901.88      13205721.4
      2360595.24     13205107.38
#Sta/Elev= 30
  4554.7  109.65  4656.7  105.89    4680  106.99  4688.6   105.6  4693.8  102.83
  4720.4    98.7  4725.7   96.02  4752.3    98.2  4784.1   95.11  4789.4  100.11
  4806.5  100.11  4879.2   93.13  4989.1   87.15  4994.2   86.68    4997   86.18
  5000.2   86.68  5019.6   88.36  5052.6   88.13  5176.1   93.31  5253.9   95.59
  5276.3   97.64  5287.9  102.39  5292.8  102.48  5298.7  102.59  5304.3   98.55
  5310.2      98  5343.4   98.29    5364   100.6  5388.1  103.13  5477.3  107.71
#Mann= 6 ,-1 , 0
  4554.7     .05       0  4989.1      .1       0  4994.2    .035       0
  5000.2      .1       0  5292.8      .1       0    5364     .05       0
Bank Sta=4994.2,5000.2
XS Rating Curve= 0 ,0
Exp/Cntr=0.3,0.1

Type RM Length L Ch R = 1 ,5116    ,98,98,98
BEGIN DESCRIPTION:
Mapping XS 708452ad
END DESCRIPTION:
XS GIS Cut Line= 4
      2360998.87     13205867.78      2360905.13     13205662.06
      2361332.21     13204831.33      2361063.99     13204693.32
#Sta/Elev= 30
  4218.3  107.62    4225  107.34  4326.7  105.23  4355.2   95.86  4424.3   98.82
    4572   92.39  4807.7   82.58  4813.3   84.87    4852   81.65  4857.6   84.22
  4896.4   80.39    4902   84.99  4918.6   80.56  4924.2   83.76  4940.7   80.56
  4946.4   84.11  4998.2   79.89  5000.9   79.39  5004.2   79.89  5029.5   82.55
  5035.1   86.23    5046   84.38  5051.6   87.95  5090.4   84.01    5096   87.46
  5134.7   84.98  5140.4    87.7    5340   89.85  5486.4   96.91  5680.1  108.08
#Mann= 6 ,-1 , 0
  4218.3      .1       0    4225     .05       0    4572      .1       0
  4998.2     .07       0  5004.2      .1       0  5486.4     .05       0
Bank Sta=4998.2,5004.2
XS Rating Curve= 0 ,0
Exp/Cntr=0.3,0.1

Type RM Length L Ch R = 1 ,5018    ,468,468,468
BEGIN DESCRIPTION:
BAYOU CREEK TRIB 4 8.0
END DESCRIPTION:
XS GIS Cut Line= 4
      2361063.97     13205885.98      2361014.51     13205693.31
      2361431.17     13204818.31      2361072.52     13204651.98
#Sta/Elev= 30
  4249.8  107.72  4289.4  106.55  4497.3   98.16  4697.2   90.74  4702.7   91.63
  4710.6   90.09  4754.9   88.23  4854.6   85.87  4889.9   82.49  4935.3   82.63
    4958   80.91  4975.2   81.78  4994.9   79.62  4997.7   79.12  5000.9   79.62
  5020.6   81.25  5042.9    80.8  5048.9   82.58  5077.1    81.2  5349.6   87.18
  5355.1   86.23  5443.7   87.65  5453.1   90.55  5465.8   92.19  5487.8   89.85
  5509.9   93.76  5612.5   97.11  5664.2   99.01  5752.4  106.31  5813.2  108.49
#Mann= 6 ,-1 , 0
  4249.8      .1       0  4289.4     .05       0  4497.3      .1       0
  4994.9     .07       0  5000.9      .1       0  5612.5     .05       0
Bank Sta=4994.9,5000.9
XS Rating Curve= 0 ,0
Exp/Cntr=0.3,0.1

Type RM Length L Ch R = 1 ,4550    ,361,361,361
BEGIN DESCRIPTION:
BAYOU CREEK TRIB 4 7.0
END DESCRIPTION:
XS GIS Cut Line= 4
      2361907.74     13205607.42      2361800.96     13205091.75
      2361459.82     13204781.85      2361082.45      13204623.1
#Sta/Elev= 30
  4240.1  110.34  4365.9  108.71    4411  106.08    4547  101.44  4606.7    97.7
  4700.2   94.74  4757.2   91.11  4786.3   87.83  4800.6   87.44  4822.2   89.79
  4885.7   87.14  4985.1   78.19  4988.8   74.16  4991.6   73.66  4994.8   74.16
    5006   76.69  5034.4   79.98  5119.5   80.82  5225.6   88.35  5262.4   87.82
  5273.3    88.8  5278.9   91.35  5284.4   91.93  5308.1   90.25  5331.8   94.37
  5426.4   97.42  5501.1   100.4  5522.8  103.07  5585.5  106.95    5637  108.65
#Mann= 5 ,-1 , 0
  4240.1     .05       0  4786.3      .1       0  4988.8     .07       0
  4994.8      .1       0  5426.4     .05       0
Bank Sta=4988.8,4994.8
XS Rating Curve= 0 ,0
Exp/Cntr=0.3,0.1

Type RM Length L Ch R = 1 ,4189    ,88,88,88
BEGIN DESCRIPTION:
BAYOU CREEK TRIB 4 6.0
END DESCRIPTION:
XS GIS Cut Line= 2
      2362537.95     13204938.11      2361248.85     13204412.05
#Sta/Elev= 30
    4180  110.75  4220.5  110.55  4225.9  109.09    4274  109.38  4279.4   107.5
  4303.4  106.45  4540.1   97.83  4648.3    93.6  4808.7   83.61  4910.2    79.6
  4925.5   77.78  4979.5   76.99  4993.1   75.62  5008.8   72.11  5011.5   71.61
  5014.8   72.11  5022.7    75.6  5041.2   77.32  5125.5   81.25  5225.6   89.32
  5255.1   88.31  5273.4   89.51  5303.1   90.37  5325.1   92.67  5332.6    95.2
    5362   96.32    5386   98.72  5391.4   98.05  5410.1  100.33  5572.3   107.4
#Mann= 6 ,-1 , 0
    4180     .05       0  4540.1      .1       0  5008.8     .07       0
  5014.8      .1       0  5125.5     .08       0  5273.4     .05       0
Bank Sta=5008.8,5014.8
XS Rating Curve= 0 ,0
Exp/Cntr=0.3,0.1

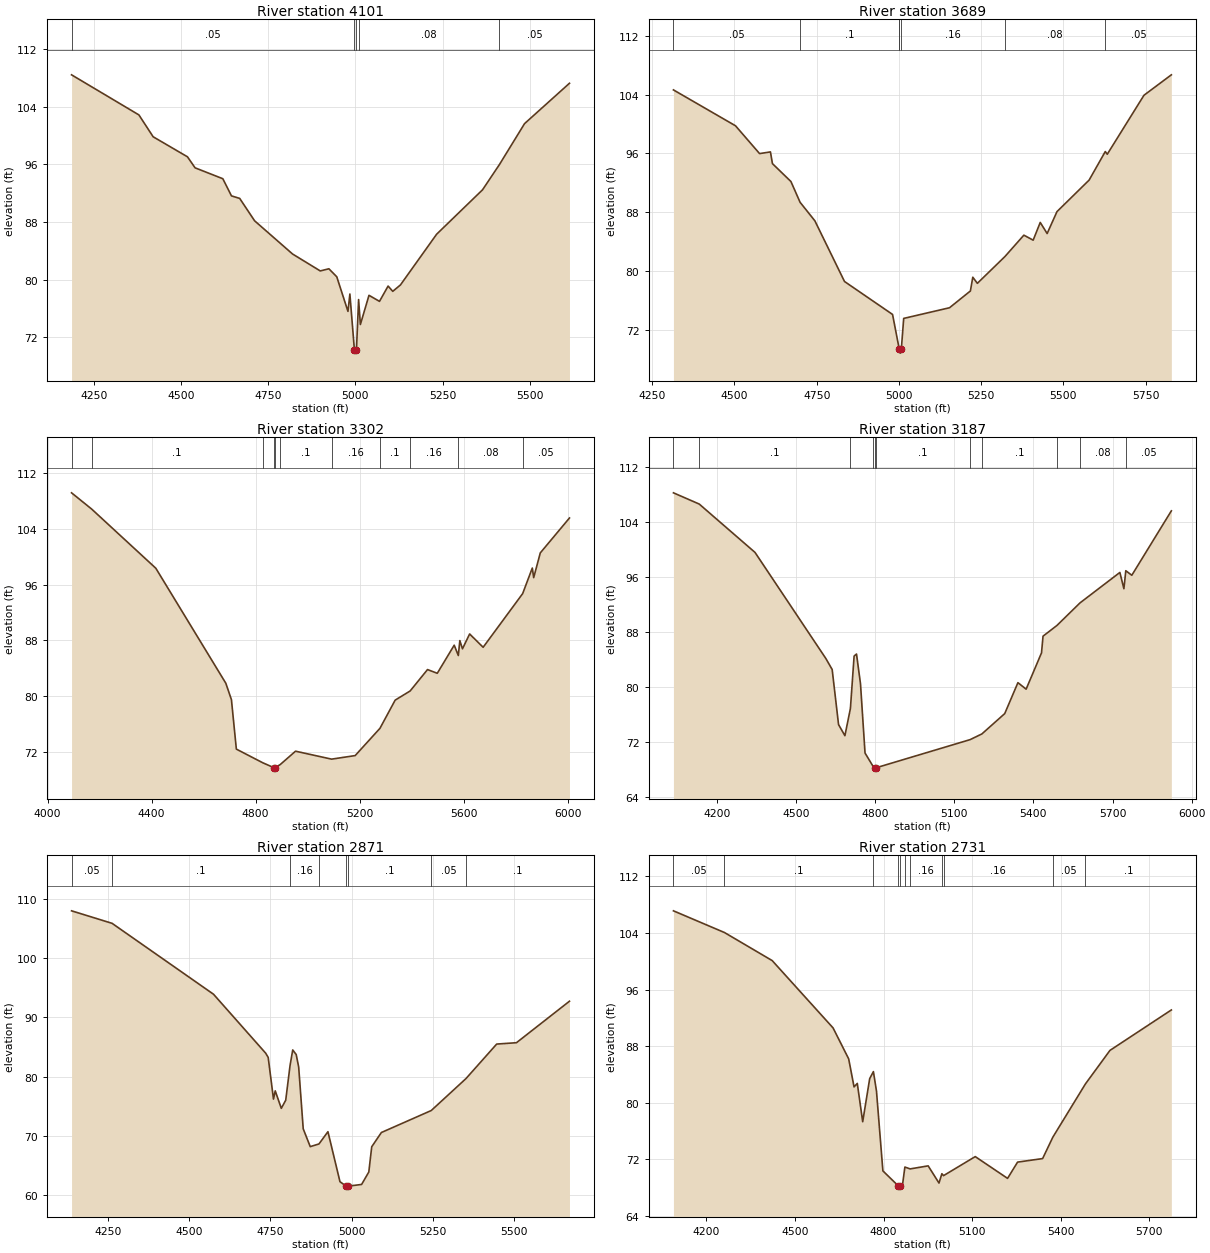
Type RM Length L Ch R = 1 ,4101    ,412,412,412
BEGIN DESCRIPTION:
Mapping XS 83c8cd18
END DESCRIPTION:
XS GIS Cut Line= 4
      2362588.15     13204846.42      2361653.22     13204489.64
      2361611.82     13204510.92      2361257.81     13204371.82
#Sta/Elev= 30
  4186.1  108.43  4379.2  102.87    4420   99.84  4518.4   97.06  4540.3   95.53
  4619.8   94.02  4644.6   91.64  4668.2   91.29    4711   88.18  4819.7   83.58
  4899.2   81.23  4923.9   81.53  4946.5   80.42  4978.6   75.62  4984.1   78.03
    4997   70.33  4999.8   69.83    5003   70.33  5009.1   77.26  5014.2    73.8
  5038.9   77.85    5069   77.01  5093.7   79.13  5107.1    78.4  5129.1   79.29
  5232.8   86.32  5364.4   92.48  5412.7   95.97  5484.9  101.66  5613.7  107.26
#Mann= 5 ,-1 , 0
  4186.1     .05       0    4997     .04       0    5003     .05       0
  5009.1     .08       0  5412.7     .05       0
Bank Sta=4997,5003
XS Rating Curve= 0 ,0
Exp/Cntr=0.3,0.1

Type RM Length L Ch R = 1 ,3689    ,387,387,387
BEGIN DESCRIPTION:
BAYOU CREEK TRIB 4 5.0
END DESCRIPTION:
XS GIS Cut Line= 4
      2362621.51     13204434.14      2361877.44     13204223.32
      2361598.79     13204486.34      2361262.83     13204363.93
#Sta/Elev= 30
  4314.4  104.63  4503.2   99.75  4576.3   95.97  4609.4    96.2  4615.4   94.61
  4671.7   92.17  4699.5   89.35  4744.5   86.83  4834.6   78.58  4980.7    74.1
  5001.2   69.36  5001.3   69.34  5004.1   68.84  5007.3   69.34  5014.6   73.56
  5153.9   75.01  5217.4   77.29  5224.7   79.16  5238.6   78.33  5322.6   81.98
    5380   84.88  5408.3    84.2  5429.8   86.61  5450.8    85.1  5480.7   88.08
  5578.5   92.37  5627.6   96.25  5633.6   95.88  5745.2   103.9  5828.5  106.68
#Mann= 7 ,-1 , 0
  4314.4     .05       0  4699.5      .1       0  5001.2     .16       0
  5001.3     .07       0  5007.3     .16       0  5322.6     .08       0
  5627.6     .05       0
Bank Sta=5001.3,5007.3
XS Rating Curve= 0 ,0
Exp/Cntr=0.3,0.1

Type RM Length L Ch R = 1 ,3302    ,115,115,115
BEGIN DESCRIPTION:
Mapping XS 3427c72c
END DESCRIPTION:
XS GIS Cut Line= 5
      2362658.67     13203897.79      2362051.92     13203655.61
        2361604.     13204452.48      2361588.38     13204473.32
      2361286.34     13204363.96
#Sta/Elev= 30
    4092  109.18  4169.6  106.84    4416   98.36  4685.2   81.86  4706.8    79.5
  4725.7   72.41  4827.2   70.45  4869.9   69.75  4872.7   69.25  4875.9   69.75
    4895   70.21  4953.3   72.11    5092   70.97  5182.6   71.48  5277.9   75.39
  5336.5   79.44    5394   80.75  5460.8   83.82  5498.4   83.29  5563.5   87.32
  5579.3   85.84  5585.1   87.98  5595.3    86.8  5622.8   88.93  5674.7   87.02
  5826.7   94.72  5863.8   98.39  5869.1   97.01  5894.5  100.56  6006.7  105.57
#Mann= 11 ,-1 , 0
    4092     .05       0  4169.6      .1       0  4827.2     .16       0
  4869.9     .07       0  4875.9     .16       0    4895      .1       0
    5092     .16       0  5277.9      .1       0    5394     .16       0
  5579.3     .08       0  5826.7     .05       0
Bank Sta=4869.9,4875.9
XS Rating Curve= 0 ,0
Exp/Cntr=0.3,0.1

Type RM Length L Ch R = 1 ,3187    ,316,316,316
BEGIN DESCRIPTION:
BAYOU CREEK TRIB 4 4.0
END DESCRIPTION:
XS GIS Cut Line= 4
      2362661.31     13203876.97      2361971.19     13203598.32
        2361479.     13204416.03      2361302.34     13204348.48
#Sta/Elev= 30
  4035.2  108.29  4133.1  106.65  4344.5    99.6  4612.9   84.14    4637   82.53
  4661.2    74.5  4685.3   72.88  4706.2   76.85  4720.2   84.49  4729.3   84.78
  4744.4   80.45  4761.6   70.35  4790.3   68.52  4798.4   68.21  4801.2   67.71
  4804.4   68.21  5159.8    72.3  5204.6   73.13  5291.3    76.1  5341.3   80.61
  5372.4   79.66  5430.7   84.95  5436.5   87.39  5489.2   88.95  5576.7   92.24
  5727.8   96.68  5743.1   94.31  5750.3   96.93  5773.1   96.27    5923  105.66
#Mann= 11 ,-1 , 0
  4035.2     .05       0  4133.1      .1       0  4706.2     .16       0
  4790.3      .1       0  4798.4     .07       0  4804.4      .1       0
  5159.8     .16       0  5204.6      .1       0  5489.2     .05       0
  5576.7     .08       0  5750.3     .05       0
Bank Sta=4798.4,4804.4
XS Rating Curve= 0 ,0
Exp/Cntr=0.3,0.1

Type RM Length L Ch R = 1 ,2871    ,140,140,140
BEGIN DESCRIPTION:
Mapping XS f6dfae3f
END DESCRIPTION:
XS GIS Cut Line= 3
       2362668.7     13203856.14      2361948.19     13203563.16
      2361275.87     13203218.11
#Sta/Elev= 30
  4137.3  107.97  4262.1  105.86  4574.5    93.9  4735.1   83.96  4742.9   83.24
  4759.2   76.21  4764.6    77.6  4783.3   74.65  4796.9   76.02  4810.2   81.87
  4818.5    84.5  4829.2   83.72  4836.8   81.63  4850.8   71.19  4872.4   68.19
  4899.3   68.64  4926.9   70.71    4964   62.27  4983.2   61.52  4985.9   61.02
  4989.2   61.52  5030.6   61.81  5052.8   63.91  5061.8   68.17  5091.5   70.57
  5245.1   74.28  5352.1   79.67  5446.6   85.49  5507.5   85.72  5670.8   92.72
#Mann= 8 ,-1 , 0
  4137.3     .05       0  4262.1      .1       0  4810.2     .16       0
  4899.3      .1       0  4983.2     .07       0  4989.2      .1       0
  5245.1     .05       0  5352.1      .1       0
Bank Sta=4983.2,4989.2
XS Rating Curve= 0 ,0
Exp/Cntr=0.3,0.1

Type RM Length L Ch R = 1 ,2731    ,118,118,118
BEGIN DESCRIPTION:
BAYOU CREEK TRIB 4 3.0
END DESCRIPTION:
XS GIS Cut Line= 6
      2362681.72     13203821.42       2361954.7     13203515.42
       2361976.4     13203430.78      2361867.89     13203337.47
      2361759.38     13203439.46      2361305.85     13203187.74
#Sta/Elev= 30
  4088.1  107.13    4261  104.06  4422.7  100.09  4628.9   90.57  4681.8   86.19
    4700   82.23    4711   82.72  4729.3    77.3    4753    83.4  4765.6   84.39
    4776   81.63  4797.7   70.35  4848.9   68.27  4851.7   67.77  4854.9   68.27
  4864.2   68.37  4872.2   70.89  4890.1   70.63  4951.1   71.06  4987.8   68.63
  4997.5   69.95  5003.3   69.68  5110.6   72.37  5220.1   69.29    5254   71.59
  5338.9   72.09  5373.4   75.11  5483.9   82.65    5567   87.39    5775   93.11
#Mann= 11 ,-1 , 0
  4088.1     .05       0    4261      .1       0  4765.6     .16       0
  4848.9     .07       0  4854.9     .16       0  4872.2      .1       0
  4890.1     .16       0  4997.5      .1       0  5003.3     .16       0
  5373.4     .05       0  5483.9      .1       0
Bank Sta=4848.9,4854.9
XS Rating Curve= 0 ,0
Exp/Cntr=0.3,0.1

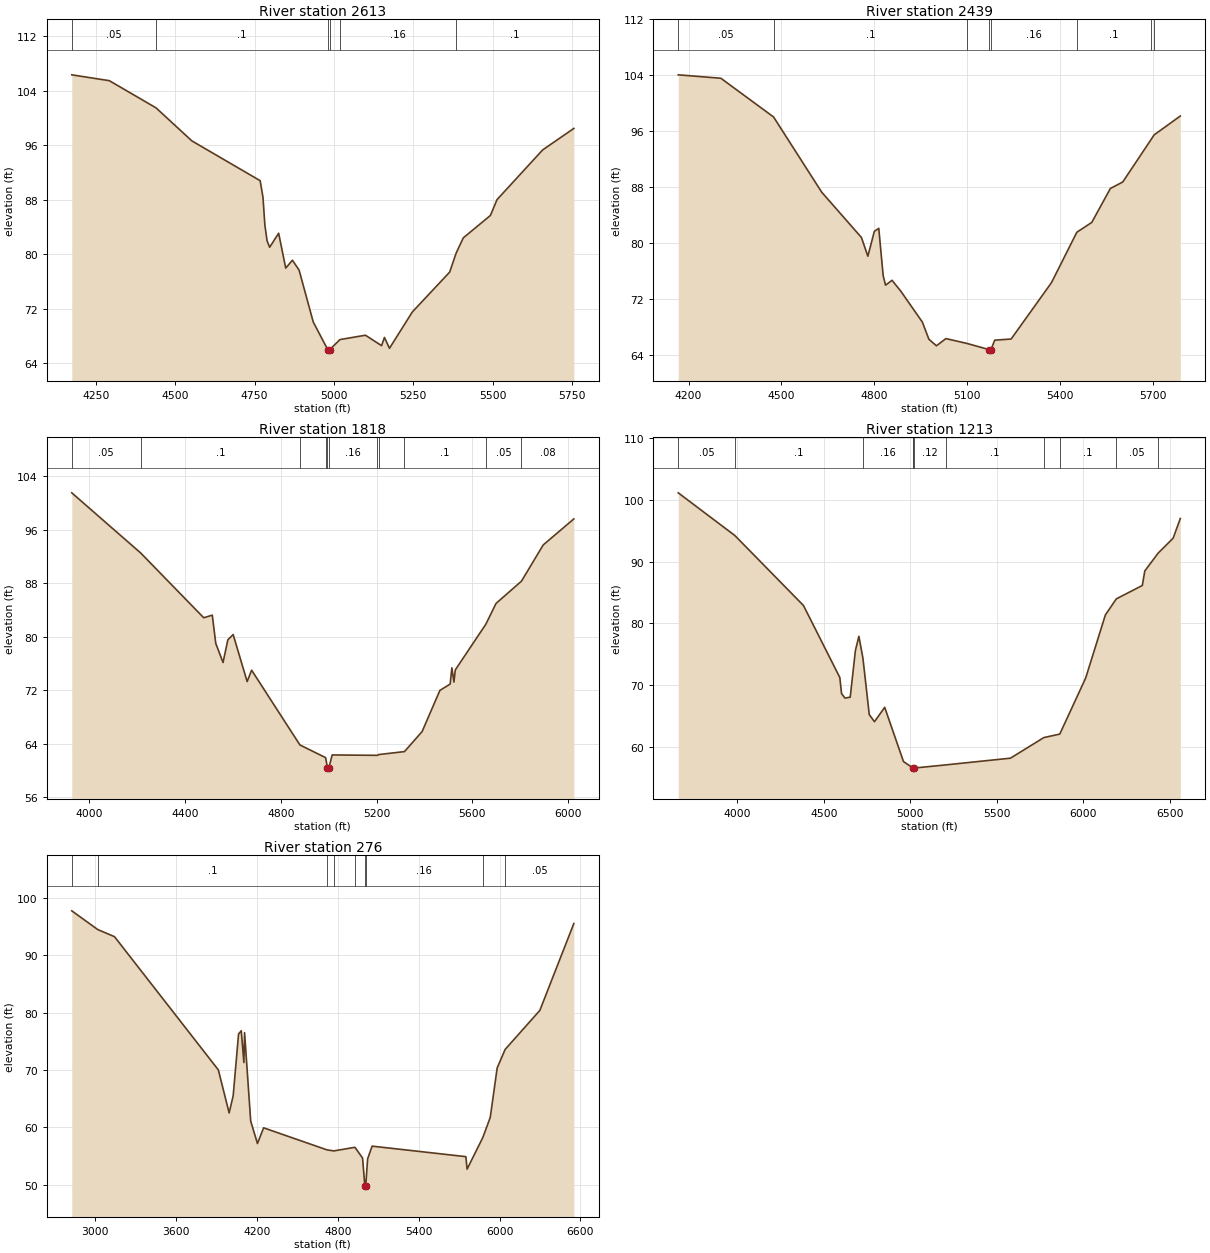
Type RM Length L Ch R = 1 ,2613    ,174,174,174
BEGIN DESCRIPTION:
Mapping XS 8d9a13e1
END DESCRIPTION:
XS GIS Cut Line= 3
      2362694.68     13203775.81      2361883.08     13203218.11
      2361302.07      13203083.7
#Sta/Elev= 30
  4174.5  106.35  4292.8  105.49  4439.8   101.5  4552.6   96.65  4767.8    90.8
  4776.6   88.38  4782.7   84.24  4789.6   81.97  4797.6   81.02    4826   83.08
  4848.3   77.96  4869.3   79.12  4890.3   77.68  4934.9   70.05  4980.7   65.97
  4983.5   65.47  4986.7   65.97    5019   67.46  5099.3    68.1  5150.1   66.57
  5159.2   67.78    5175   66.18  5246.9   71.51  5364.7   77.38  5384.9   80.16
  5407.4    82.4  5492.8   85.69  5513.7   88.02  5657.4   95.32  5755.6   98.48
#Mann= 6 ,-1 , 0
  4174.5     .05       0  4439.8      .1       0  4980.7     .07       0
  4986.7      .1       0    5019     .16       0  5384.9      .1       0
Bank Sta=4980.7,4986.7
XS Rating Curve= 0 ,0
Exp/Cntr=0.3,0.1

Type RM Length L Ch R = 1 ,2439    ,621,621,621
BEGIN DESCRIPTION:
BAYOU CREEK TRIB 4 2.0
END DESCRIPTION:
XS GIS Cut Line= 4
      2362757.68     13203671.26      2362205.06     13203197.26
      2361868.23     13203075.67      2361331.67     13203061.89
#Sta/Elev= 30
  4166.5  104.08  4304.3  103.59  4474.7   98.05  4630.3   87.29  4758.7   80.81
  4779.5   78.13  4800.4   81.69  4814.7   82.12  4828.9   75.36  4836.6   73.99
  4857.5   74.69    4886   73.13  4955.5   68.72  4976.8   66.25  5001.1   65.32
  5031.8   66.35  5100.3   65.65  5171.5   64.77  5174.3   64.27  5177.5   64.77
  5189.4   66.12  5242.6   66.29  5373.2   74.37  5454.9   81.56  5503.3   82.97
  5563.3   87.82  5603.3   88.75  5695.8   94.88  5704.3   95.47  5789.4   98.19
#Mann= 8 ,-1 , 0
  4166.5     .05       0  4474.7      .1       0  5100.3     .16       0
  5171.5     .07       0  5177.5     .16       0  5454.9      .1       0
  5695.8     .08       0  5704.3      .1       0
Bank Sta=5171.5,5177.5
XS Rating Curve= 0 ,0
Exp/Cntr=0.3,0.1

Type RM Length L Ch R = 1 ,1818    ,605,605,605
BEGIN DESCRIPTION:
Mapping XS 9917152d
END DESCRIPTION:
XS GIS Cut Line= 4
       2362632.9     13203513.78      2362542.62     13202763.83
      2362146.79     13202576.33      2361369.05     13203034.64
#Sta/Elev= 30
  3927.6  101.49  4215.5   92.49  4478.5   82.81  4514.3    83.2  4528.8   78.98
  4559.1   76.12  4579.2   79.51  4601.4    80.3  4659.8   73.27  4678.5   74.97
  4880.2   63.79  4987.3    61.9  4995.2   60.38    4998   59.88  5001.2   60.38
  5014.7    62.3  5203.9   62.24  5209.8   62.36  5316.6    62.8  5390.3    65.8
  5464.5   71.95  5507.4    72.9  5514.5   75.33  5523.1    73.2  5528.9   75.02
  5656.4   81.85  5698.8   84.95    5805   88.28  5895.9    93.7  6023.7   97.59
#Mann= 11 ,-1 , 0
  3927.6     .05       0  4215.5      .1       0  4880.2     .12       0
  4987.3     .16       0  4995.2     .07       0  5001.2     .16       0
  5203.9      .1       0  5209.8     .16       0  5316.6      .1       0
  5656.4     .05       0    5805     .08       0
Bank Sta=4995.2,5001.2
XS Rating Curve= 0 ,0
Exp/Cntr=0.3,0.1

Type RM Length L Ch R = 1 ,1213    ,937,937,937
BEGIN DESCRIPTION:
Mapping XS fdb82c04
END DESCRIPTION:
XS GIS Cut Line= 4
      2362785.68     13203499.96       2362820.4     13202319.38
       2362464.5     13202102.37      2361441.47     13202908.65
#Sta/Elev= 30
  3659.3  101.17    3986   94.26  4382.7   82.91  4592.8   71.23  4602.8   68.63
  4622.8    67.9  4652.8   68.05  4682.8   75.61  4702.9   77.92  4726.4   74.34
  4762.9   65.22  4792.9   64.07  4852.1    66.4  4960.6   57.61  5014.4   56.59
  5016.2   56.56    5019   56.06  5022.2   56.56  5208.1   57.08  5578.7   58.16
  5771.6    61.5  5863.4   62.06  6013.2   71.16    6127   81.38  6190.1   83.98
  6340.3   86.15  6354.7   88.51  6432.4   91.42  6518.3   93.81  6559.8   97.01
#Mann= 11 ,-1 , 0
  3659.3     .05       0    3986      .1       0  4726.4     .16       0
  5014.4     .12       0  5016.2     .07       0  5022.2     .12       0
  5208.1      .1       0  5771.6     .16       0  5863.4      .1       0
  6190.1     .05       0  6432.4     .08       0
Bank Sta=5016.2,5022.2
XS Rating Curve= 0 ,0
Exp/Cntr=0.3,0.1

Type RM Length L Ch R = 1 ,276     ,0,0,0
BEGIN DESCRIPTION:
BAYOU CREEK TRIB 4 1.0
END DESCRIPTION:
XS GIS Cut Line= 5
      2362959.29     13203473.88      2362985.33     13202050.28
      2362603.39     13201720.42      2362047.83     13201807.23
      2361371.74      13202838.7
#Sta/Elev= 30
  2827.3    97.7  3019.4   94.45  3144.4    93.2  3914.5   70.02  3994.5   62.53
  4024.5   65.51  4064.5   76.26  4084.5   76.83    4104    71.3    4109    76.5
  4154.5   61.12  4204.6    57.2  4250.3   59.94  4720.5    56.1    4771   55.92
  4927.6   56.55  4984.2   54.68  5001.4   49.77  5004.2   49.27  5007.4   49.77
  5021.9   54.55  5055.1   56.75  5750.5   54.92  5759.6   52.75    5876   58.24
  5931.4   61.75  5982.7   70.36  6041.8   73.58  6299.2   80.37  6551.4   95.49
#Mann= 9 ,-1 , 0
  2827.3     .05       0  3019.4      .1       0  4720.5     .16       0
    4771     .12       0  4927.6     .16       0  5001.4     .07       0
  5007.4     .16       0    5876      .1       0  6041.8     .05       0
Bank Sta=5001.4,5007.4
XS Rating Curve= 0 ,0
Exp/Cntr=0.3,0.1

Chan Stop Cuts=-1
Use User Specified Reach Order=0
Composite Channel Slope=5