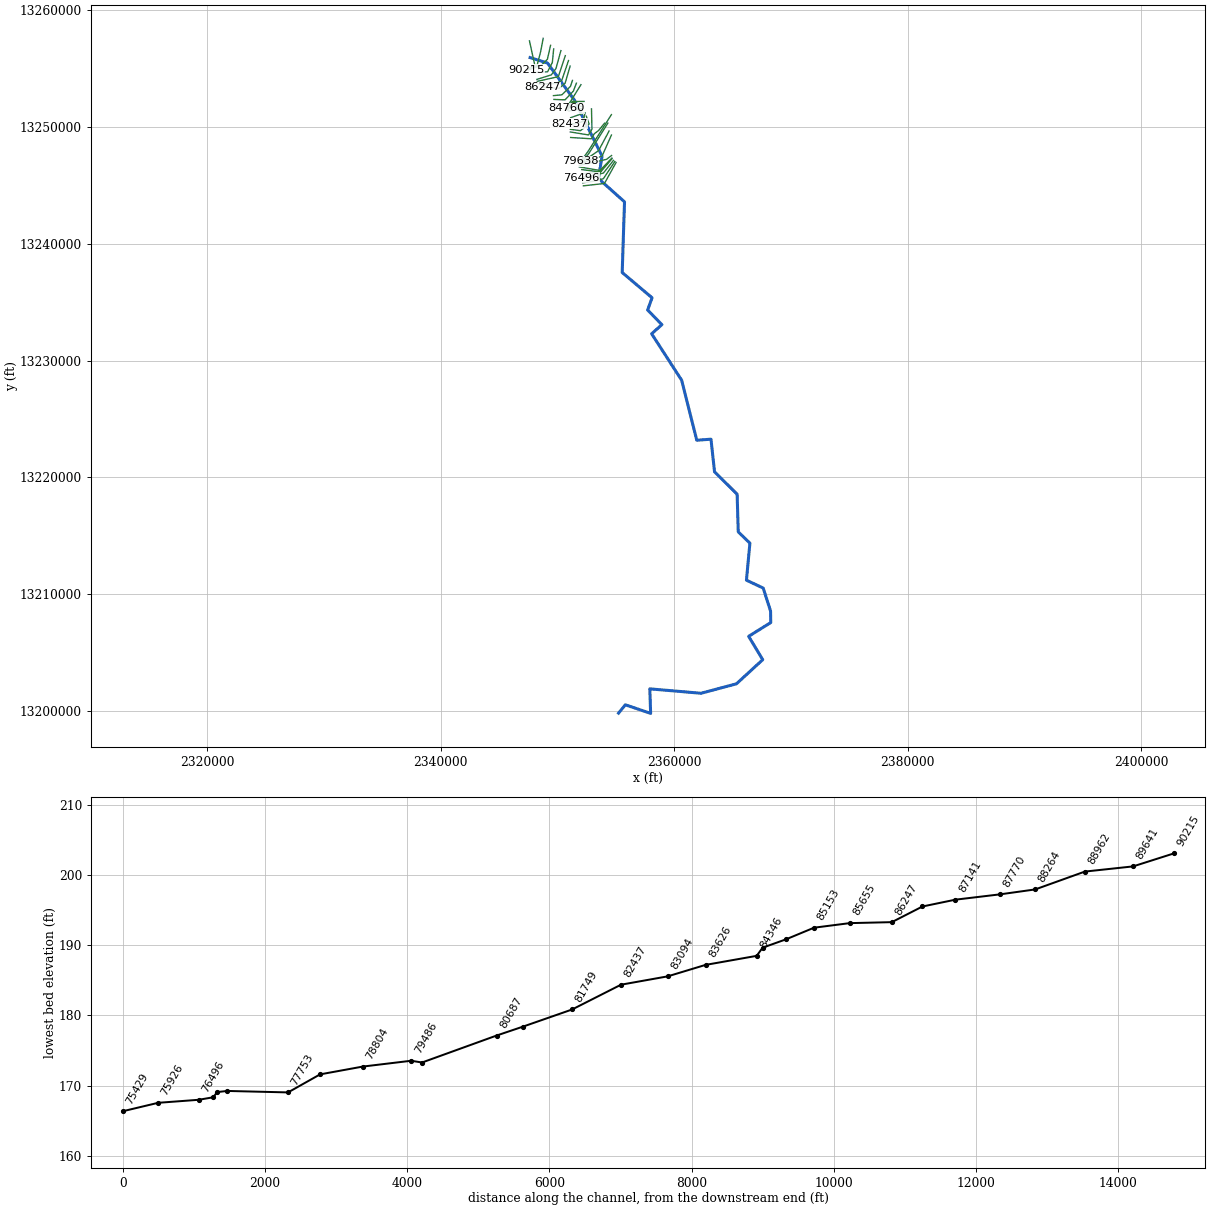
--- BAYOU CREEK.prj (project) ---

Proj Title=BAYOU CREEK Base Level Engineering
Current Plan=p01
Default Exp/Contr=0.3,0.1
English Units
Geom File=g01
Flow File=f01
Plan File=p01
Y Axis Title=Elevation
X Axis Title(PF)=Main Channel Distance
X Axis Title(XS)=Station
BEGIN DESCRIPTION:
BAYOU CREEK
END DESCRIPTION:
DSS Export Rating Curves= 0
DSS Export Rating Curve Sorted= 0
DSS Export Volume Flow Curves= 0
DXF OffsetX= 0
DXF OffsetY= 0
DXF ScaleX= 1
DXF ScaleY= 10

--- BAYOU CREEK.p01 (plan) ---

Plan Title=Multiple Run
Short Identifier=Multiple
Geom File=g01
Flow File=f01
Subcritical Flow
K Sum by GR= 0
Std Step Tol= 0.01
Critical Tol= 0.01
Num of Std Step Trials= 20
Max Error Tol= 0.3
Flow Tol Ratio= 0.001
Split Flow NTrial= 30
Split Flow Tol= 0.02
Split Flow Ratio= 0.02
Log Output Level= 0
Friction Slope Method= 1
Unsteady Friction Slope Method= 2
Unsteady Bridges Friction Slope Method= 1
Parabolic Critical Depth
Global Vel Dist=  1 , 1 , 1
Global Log Level= 0
CheckData=True
Encroach Param= -1, 0, 0, 0
BEGIN DESCRIPTION:
Multiple Run
END DESCRIPTION:

--- BAYOU CREEK.f01 (steady flow) ---

Flow Title=Multiple
Program Version=4.10
Number of Profiles= 7
Profile Names=10-year,25-year,50-year,1pct_min,100-year,1pct_plu,500-year
River Rch & RM=BAYOU CREEK,Reach-1         ,90215
     377     503     603     527     712     964     998
River Rch & RM=BAYOU CREEK,Reach-1         ,89641
     572     782     950     841    1137    1537    1636
River Rch & RM=BAYOU CREEK,Reach-1         ,84346
     623     855    1043     927    1253    1695    1816
River Rch & RM=BAYOU CREEK,Reach-1         ,80687
     935    1311    1622    1460    1975    2670    2939
River Rch & RM=BAYOU CREEK,Reach-1         ,79486
     935    1311    1622    1460    1975    2670    2939
River Rch & RM=BAYOU CREEK,Reach-1         ,78204
     935    1311    1622    1460    1975    2670    2939
River Rch & RM=BAYOU CREEK,Reach-1         ,75926
    1305    1856    2317    2103    2844    3846    4302
River Rch & RM=BAYOU CREEK,Reach-1         ,71327
    1846    2659    3349    3062    4141    5601    6361
River Rch & RM=BAYOU CREEK,Reach-1         ,69324
    1846    2659    3349    3062    4141    5601    6361
River Rch & RM=BAYOU CREEK,Reach-1         ,63409
    1994    2878    3630    3323    4494    6078    6921
River Rch & RM=BAYOU CREEK,Reach-1         ,59758
    2068    2991    3779    3464    4685    6336    7234
River Rch & RM=BAYOU CREEK,Reach-1         ,54881
    2186    3169    4009    3680    4977    6731    7706
River Rch & RM=BAYOU CREEK,Reach-1         ,52657
    2121    3062    3861    3533    4778    6462    7351
River Rch & RM=BAYOU CREEK,Reach-1         ,49226
    2467    3598    4571    4213    5698    7705    8893
River Rch & RM=BAYOU CREEK,Reach-1         ,40701
    2637    3851    4896    4516    6108    8260    9545
River Rch & RM=BAYOU CREEK,Reach-1         ,37546
    3371    4964    6347    5884    7958   10762   12562
River Rch & RM=BAYOU CREEK,Reach-1         ,33311
    3622    5339    6832    6338    8571   11591   13544
River Rch & RM=BAYOU CREEK,Reach-1         ,32814
    3622    5339    6832    6338    8571   11591   13544
River Rch & RM=BAYOU CREEK,Reach-1         ,26431
    4391    6516    8379    7807   10558   14279   16833
River Rch & RM=BAYOU CREEK,Reach-1         ,25812
    4391    6516    8379    7807   10558   14279   16833
River Rch & RM=BAYOU CREEK,Reach-1         ,21243
    4449    6606    8496    7919   10709   14483   17083
River Rch & RM=BAYOU CREEK,Reach-1         ,21114
    4407    6533    8395    7816   10570   14295   16825
River Rch & RM=BAYOU CREEK,Reach-1         ,18504
    4587    6811    8761    8166   11043   14935   17614
River Rch & RM=BAYOU CREEK,Reach-1         ,17967
    4587    6811    8761    8166   11043   14935   17614
River Rch & RM=BAYOU CREEK,Reach-1         ,15082
    4628    6859    8811    8201   11091   14999   17640
River Rch & RM=BAYOU CREEK,Reach-1         ,12063
    4980    7408    9541    8903   12040   16283   19246
River Rch & RM=BAYOU CREEK,Reach-1         ,11679
    4980    7408    9541    8903   12040   16283   19246
River Rch & RM=BAYOU CREEK,Reach-1         ,7966
    5007    7448    9593    8952   12106   16372   19351
River Rch & RM=BAYOU CREEK,Reach-1         ,4004
    5103    7599    9795    9146   12369   16728   19799
Boundary for River Rch & Prof#=BAYOU CREEK,Reach-1         , 1
Up Type= 0
Dn Type= 3
Dn Slope=0.001
Boundary for River Rch & Prof#=BAYOU CREEK,Reach-1         , 2
Up Type= 0
Dn Type= 3
Dn Slope=0.001
Boundary for River Rch & Prof#=BAYOU CREEK,Reach-1         , 3
Up Type= 0
Dn Type= 3
Dn Slope=0.001
Boundary for River Rch & Prof#=BAYOU CREEK,Reach-1         , 4
Up Type= 0
Dn Type= 3
Dn Slope=0.001
Boundary for River Rch & Prof#=BAYOU CREEK,Reach-1         , 5
Up Type= 0
Dn Type= 3
Dn Slope=0.001
Boundary for River Rch & Prof#=BAYOU CREEK,Reach-1         , 6
Up Type= 0
Dn Type= 3
Dn Slope=0.001
Boundary for River Rch & Prof#=BAYOU CREEK,Reach-1         , 7
Up Type= 0
Dn Type= 3
Dn Slope=0.001
DSS Import GetInterval= 0
DSS Import GetPeak= 0
DSS Import FillOption= 0

--- BAYOU CREEK.g01 (geometry) ---

Geom Title=Existing Conditions
Program Version=4.10

River Reach=BAYOU CREEK     ,Reach-1
Reach XY= 30
      2347667.72     13255956.86      2349160.86     13255488.34
      2351453.13     13252332.39      2353832.27     13247519.39
       2353520.7     13245598.04      2355757.33     13243600.09
       2355558.4     13237547.21       2358115.9     13235383.79
      2357739.61     13234335.35      2358957.83     13233081.92
      2358080.52     13232298.01      2360653.07     13228316.06
      2361945.25      13223180.5      2363162.47     13223269.79
      2363467.72     13220476.85      2365402.49     13218559.38
      2365499.37     13215332.99      2366496.67     13214361.65
      2366199.77     13211192.75       2367635.1     13210515.24
      2368266.48     13208546.69      2368280.02     13207560.05
      2366387.65     13206382.91      2367595.67     13204382.52
      2365346.71     13202319.26        2362317.     13201507.54
      2357923.17     13201884.67      2357994.43     13199784.41
      2355829.74     13200517.46      2355247.72     13199806.85

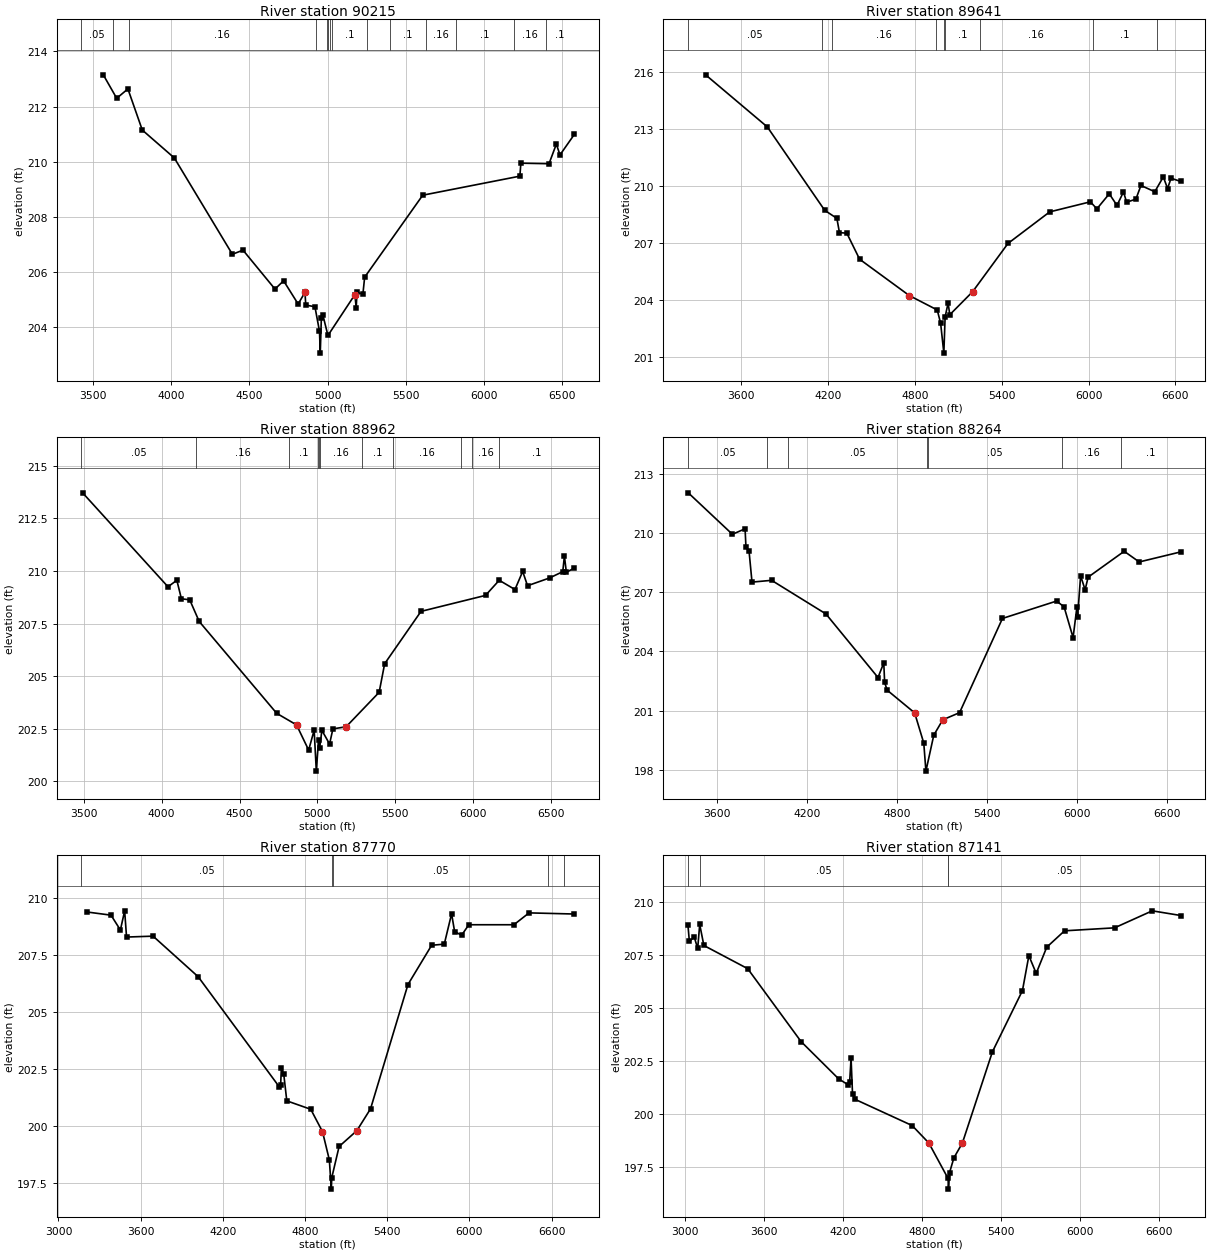
Type RM Length L Ch R = 1 ,90215   ,574,574,574
BEGIN DESCRIPTION:
BAYOU CREEK 122.0
END DESCRIPTION:
XS GIS Cut Line= 3
      2347616.82     13257390.73       2348082.1     13255258.76
      2347318.21     13254925.43
#Sta/Elev= 30
  3564.4  213.15  3650.2   212.3  3721.9  212.64    3814  211.15    4019  210.14
  4390.8  206.65  4458.8   206.8  4663.6  205.39  4718.7  205.69  4811.7  204.85
  4855.6  205.27  4860.7  204.81  4919.4  204.75  4948.6  203.86  4953.5  203.07
  4960.4  204.33  4970.6  204.44  5002.7  203.71  5175.3  205.19  5183.5  204.71
  5188.7  205.27  5226.5  205.21  5237.7  205.82  5609.5  208.79  6231.4  209.48
  6237.9  209.95  6418.1  209.93  6464.9  210.64  6488.4  210.25    6580  210.99
#Mann= 14 ,-1 , 0
  3424.4     .05       0  3625.5      .1       0  3725.9     .16       0
  4927.1      .1       0  4996.4     .07       0  5002.4      .1       0
  5018.9     .16       0  5031.8      .1       0  5251.6     .16       0
  5400.2      .1       0  5633.3     .16       0  5822.7      .1       0
  6192.8     .16       0  6397.9      .1       0
Bank Sta=4855.6,5175.3
XS Rating Curve= 0 ,0
Exp/Cntr=0.3,0.1

Type RM Length L Ch R = 1 ,89641   ,679,679,679
BEGIN DESCRIPTION:
Mapping XS c6a79b39
END DESCRIPTION:
XS GIS Cut Line= 4
      2348790.43     13257605.94       2348582.1     13256501.82
      2348262.66     13255258.76      2347451.43     13254925.95
#Sta/Elev= 30
  3353.3  215.86  3779.8  213.12  4176.7  208.73  4260.5  208.31  4278.4  207.56
  4329.3  207.53  4417.7  206.16  4760.8  204.25  4954.2  203.49  4977.6  202.79
  4999.8  201.22  5008.6  203.12  5029.3  203.86  5040.8  203.24  5198.6  204.45
  5443.1  206.99  5731.3  208.65  6012.3  209.18  6057.5  208.81    6143   209.6
  6196.4  208.99  6241.3   209.7  6262.9  209.16  6327.1  209.32  6361.9  210.04
  6457.5  209.71  6516.6  210.49    6546  209.88  6569.9  210.42  6637.2  210.25
#Mann= 9 ,-1 , 0
    3231     .05       0  4156.5      .1       0  4224.8     .16       0
  4948.1      .1       0  5002.3     .07       0  5008.3      .1       0
  5246.6     .16       0  6027.3      .1       0  6474.4     .16       0
Bank Sta=4760.8,5198.6
XS Rating Curve= 0 ,0
Exp/Cntr=0.3,0.1

Type RM Length L Ch R = 1 ,88962   ,698,698,698
BEGIN DESCRIPTION:
BAYOU CREEK 121.0
END DESCRIPTION:
XS GIS Cut Line= 4
      2349423.99      13257006.7      2349153.16     13255814.01
      2348621.91     13255293.18      2347497.65      13254904.1
#Sta/Elev= 30
  3492.5  213.72  4040.6  209.25  4097.4  209.56  4126.7  208.68  4180.1  208.63
  4240.9   207.6  4738.5  203.23  4865.8  202.68  4943.7  201.48    4979  202.43
  4992.9  200.48  5007.3  201.98  5014.4  201.59  5028.6  202.42    5078  201.77
  5099.3  202.49  5184.2  202.59  5396.2  204.23  5431.6  205.59    5665  208.08
  6079.1  208.84  6167.2  209.56  6268.2  209.12  6317.8  209.98  6348.9   209.3
  6490.4  209.67  6575.1  209.97  6585.6  210.71  6598.2  209.94  6649.2  210.14
#Mann= 11 ,-1 , 0
  3484.9     .05       0  4220.1     .16       0  4819.5      .1       0
  5005.8     .16       0  5008.4     .07       0  5014.4     .16       0
  5288.8      .1       0  5482.6     .16       0    5922      .1       0
    5993     .16       0  6167.9      .1       0
Bank Sta=4865.8,5184.2
XS Rating Curve= 0 ,0
Exp/Cntr=0.3,0.1

Type RM Length L Ch R = 1 ,88264   ,494,494,494
BEGIN DESCRIPTION:
BAYOU CREEK 120.0
END DESCRIPTION:
XS GIS Cut Line= 4
      2349689.62      13256699.4      2349575.04     13255532.76
      2349168.79      13254741.1      2347951.33     13254673.46
#Sta/Elev= 30
  3410.1  212.03  3704.1  209.93  3788.5  210.21  3794.5  209.27  3814.6  209.11
  3834.7  207.51  3965.3   207.6    4327   205.9  4674.2  202.68  4712.6  203.42
  4718.5  202.43  4735.1  202.04  4918.3  200.89  4979.2  199.36  4993.4  197.94
  5045.8  199.76    5106  200.54  5217.7   200.9  5503.3  205.67  5863.8  206.55
  5913.9  206.26    5974   204.7  5999.2  206.23  6004.2  205.75  6024.1  207.83
  6054.1  207.12  6074.2  207.76  6314.5  209.07  6414.7  208.53  6691.5  209.04
#Mann= 7 ,-1 , 0
  3407.6     .05       0  3936.7     .16       0  4075.9     .05       0
  5000.2    .035       0  5006.2     .05       0  5899.7     .16       0
    6295      .1       0
Bank Sta=4918.3,5106
XS Rating Curve= 0 ,0
Exp/Cntr=0.3,0.1

Type RM Length L Ch R = 1 ,87770   ,629,629,629
BEGIN DESCRIPTION:
BAYOU CREEK 119.0
END DESCRIPTION:
XS GIS Cut Line= 4
       2350309.4     13256553.56      2349886.41     13255017.14
       2349486.5     13254475.47      2348252.44     13254090.16
#Sta/Elev= 30
  3206.5  209.39  3383.5  209.25    3452   208.6  3483.1  209.44    3497  208.29
  3690.6  208.33  4020.1  206.55  4613.7  201.71  4622.2  201.82  4627.4  202.56
  4644.8  202.28    4667  201.11    4842  200.74  4927.6  199.76  4977.7  198.52
  4992.1  197.24  4995.3  197.74    5049  199.11  5178.1   199.8  5278.4  200.76
  5551.7  206.21  5724.6  207.93  5816.8  207.98  5870.2  209.31  5892.3  208.53
  5943.5  208.37  5995.9  208.83  6325.1  208.83  6435.9  209.35  6766.2   209.3
#Mann= 5 ,-1 , 0
  3167.6     .05       0  4998.6    .035       0  5004.6     .05       0
  6573.9      .1       0  6691.1     .16       0
Bank Sta=4927.6,5178.1
XS Rating Curve= 0 ,0
Exp/Cntr=0.3,0.1

Type RM Length L Ch R = 1 ,87141   ,463,463,463
BEGIN DESCRIPTION:
BAYOU CREEK 118.0
END DESCRIPTION:
XS GIS Cut Line= 3
       2350686.4     13256121.82      2350086.41     13254321.85
      2348286.45     13253921.86
#Sta/Elev= 30
  3023.8  208.92  3034.9  208.13  3071.8  208.34  3098.1   207.8  3113.4  208.93
    3145  207.94  3477.6  206.85  3882.9  203.42  4167.5  201.67  4241.8  201.38
  4251.8  201.54  4262.3  202.64  4273.4  200.95  4293.9   200.7  4726.1  199.47
  4852.6  198.65  4998.7  196.98  5001.5  196.48  5010.1  197.26  5042.7  197.95
  5107.4  198.65  5335.3  202.94  5563.3  205.82  5611.9  207.46  5667.6  206.63
  5747.7  207.86  5882.7  208.63  6262.4  208.77  6548.6  209.57    6765  209.35
#Mann= 4 ,-1 , 0
  3023.8     .05       0  3113.4     .05       0  4998.7    .035       0
  5001.5     .05       0
Bank Sta=4852.6,5107.4
XS Rating Curve= 0 ,0
Exp/Cntr=0.3,0.1

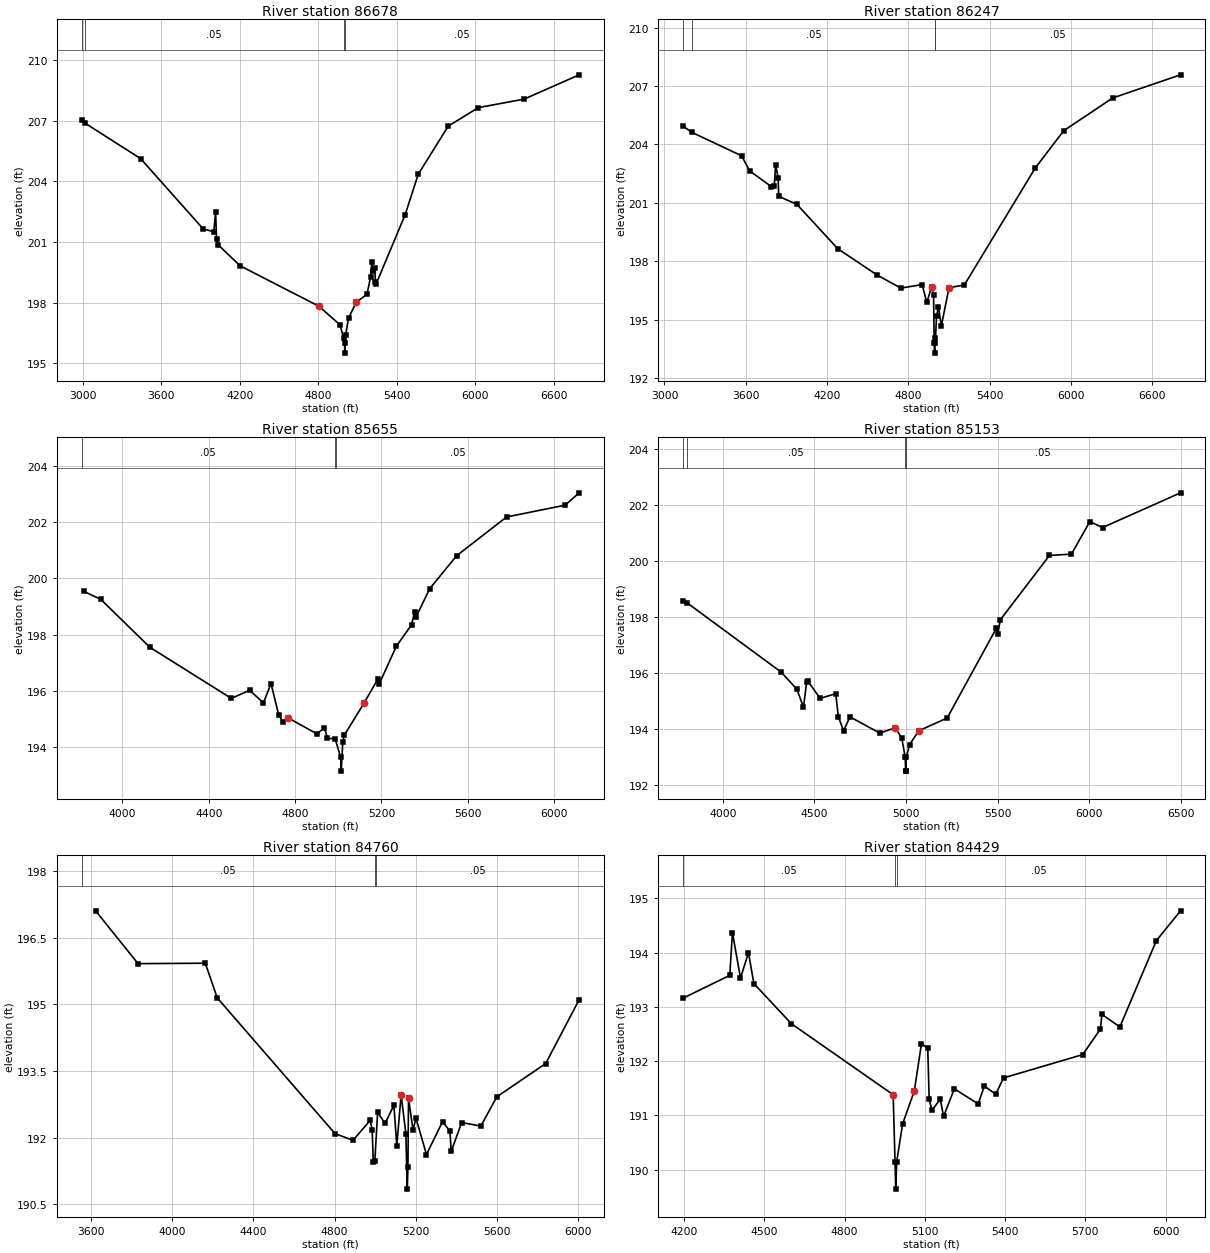
Type RM Length L Ch R = 1 ,86678   ,431,431,431
BEGIN DESCRIPTION:
BAYOU CREEK 117.0
END DESCRIPTION:
XS GIS Cut Line= 4
      2350960.59     13255703.94      2350383.32     13253998.17
      2349914.57     13253737.76      2348447.53     13253685.67
#Sta/Elev= 30
  2990.9  207.05  3014.8  206.88  3441.8  205.12  3921.1  201.64  4001.3  201.51
  4015.4  202.47  4022.4  201.15    4033  200.87    4204  199.82  4804.3  197.83
  4966.7  196.91  4994.2  196.24    5001  196.01  5003.8  195.51  5010.2  196.43
  5031.9  197.24  5091.4  198.03  5172.6  198.41  5200.1  199.25  5209.9     200
  5216.1  199.58  5232.1  199.71  5237.8  199.02  5244.3  198.95  5464.9  202.35
  5564.9  204.35  5795.1  206.73  6025.2  207.64  6375.4  208.06  6795.9  209.26
#Mann= 4 ,-1 , 0
  2990.9     .05       0  3014.8     .05       0  4994.2    .035       0
    5001     .05       0
Bank Sta=4804.3,5091.4
XS Rating Curve= 0 ,0
Exp/Cntr=0.3,0.1

Type RM Length L Ch R = 1 ,86247   ,592,592,592
BEGIN DESCRIPTION:
BAYOU CREEK 116.0
END DESCRIPTION:
XS GIS Cut Line= 4
      2351101.07     13255232.38      2350670.52     13253767.14
      2350142.75     13253315.75      2348698.27     13253419.92
#Sta/Elev= 30
  3137.1  204.94  3201.2  204.62  3570.2  203.41  3627.7  202.64  3789.1  201.83
  3810.2  201.87  3820.3  202.96  3838.3  202.28  3843.5  201.33  3976.7  200.92
  4278.9  198.64  4570.8  197.28  4744.8  196.62  4900.7   196.8  4935.8  195.88
    4971   196.7  4985.2  196.29  4989.9  193.78  4992.7  193.28  4995.9  193.78
  4999.5  194.04  5007.2  195.19  5021.5  195.66  5042.3  194.67  5099.4  196.64
  5212.5  196.78  5734.8  202.78  5945.3   204.7  6306.2  206.38    6807  207.57
#Mann= 4 ,-1 , 0
  3137.1     .05       0  3201.2     .05       0  4995.9    .035       0
  4999.5     .05       0
Bank Sta=4971,5099.4
XS Rating Curve= 0 ,0
Exp/Cntr=0.3,0.1

Type RM Length L Ch R = 1 ,85655   ,502,502,502
BEGIN DESCRIPTION:
BAYOU CREEK 115.0
END DESCRIPTION:
XS GIS Cut Line= 4
      2351299.82     13254001.32      2351130.56     13253493.53
      2350388.37     13252764.36      2349672.52     13252699.29
#Sta/Elev= 30
  3821.3  199.54  3899.8  199.26  4127.4  197.55  4504.7  195.73  4589.5  196.02
  4653.3  195.57  4688.5  196.26    4724  195.14  4745.1  194.88  4766.4  195.04
  4900.7  194.47    4936  194.68  4950.1  194.31  4985.6  194.29  5010.9  193.64
  5013.6  193.14  5020.9  194.17    5028  194.42  5119.9  195.57  5183.6  196.42
  5190.6  196.26  5268.4  197.58  5339.2  198.35  5353.3   198.8  5360.3  198.63
  5423.7  199.64  5548.3  200.81  5779.2  202.19  6050.3  202.61  6115.8  203.05
#Mann= 3 ,-1 , 0
  3811.6     .05       0  4984.4    .035       0  4990.4     .05       0
Bank Sta=4766.4,5119.9
XS Rating Curve= 0 ,0
Exp/Cntr=0.3,0.1

Type RM Length L Ch R = 1 ,85153   ,393,393,393
BEGIN DESCRIPTION:
BAYOU CREEK 114.0
END DESCRIPTION:
XS GIS Cut Line= 4
      2351638.36     13253766.95      2351377.95     13253089.88
      2350661.81     13252334.68      2349712.69     13252373.68
#Sta/Elev= 30
  3782.2  198.56  3803.7  198.51    4318  196.03  4403.7  195.42  4439.9  194.77
  4457.3  195.68  4464.6   195.7  4531.1  195.09    4616  195.26  4630.2  194.44
  4658.5  193.93  4693.7  194.43  4856.3  193.85  4941.3  194.04  4976.9  193.66
  4994.9  192.99  4997.7  192.49  4998.2  192.49  5000.9  192.99  5019.3  193.44
  5068.7  193.93  5224.4  194.39    5493   197.6  5500.3  197.38  5514.5   197.9
  5782.7   200.2  5902.8  200.25  6002.9  201.41  6072.9   201.2  6498.3  202.44
#Mann= 4 ,-1 , 0
  3782.2     .05       0  3803.7     .05       0  4994.9    .035       0
  4998.2     .05       0
Bank Sta=4941.3,5068.7
XS Rating Curve= 0 ,0
Exp/Cntr=0.3,0.1

Type RM Length L Ch R = 1 ,84760   ,331,331,331
BEGIN DESCRIPTION:
BAYOU CREEK 113.0
END DESCRIPTION:
XS GIS Cut Line= 2
      2352025.55     13253636.05      2350765.72     13251610.95
#Sta/Elev= 30
  3621.4  197.11  3830.8  195.92  4162.5  195.93  4221.1  195.15  4802.3  192.09
  4890.8  191.94  4975.8  192.39  4985.3  192.18  4991.1  191.44  4998.4  191.47
  5012.4  192.57    5049  192.32  5092.6  192.73  5106.8  191.82  5128.1  192.96
  5151.5  192.09  5158.5  190.84  5161.8  191.34  5164.7  192.89  5186.8  192.17
  5201.3  192.44  5253.2  191.62  5332.3  192.36  5368.9  192.15  5375.3  191.69
  5426.7  192.34  5521.2  192.26  5600.3  192.92  5841.1  193.67  6006.4  195.11
#Mann= 3 ,-1 , 0
  3552.7     .05       0  4996.9    .035       0  5002.9     .05       0
Bank Sta=5128.1,5164.7
XS Rating Curve= 0 ,0
Exp/Cntr=0.3,0.1

Type RM Length L Ch R = 1 ,84429   ,83,83,83
BEGIN DESCRIPTION:
Mapping XS 49c06120
END DESCRIPTION:
XS GIS Cut Line= 6
      2352292.56     13252202.05      2351677.12     13252197.64
      2351487.48      13252215.3      2351432.85      13252249.7
      2351240.21     13252166.28      2350822.44      13251508.3
#Sta/Elev= 30
  4196.3  193.16  4371.1  193.58  4381.1  194.37  4411.1  193.53  4441.1     194
  4461.1  193.43  4601.1  192.69  4981.9  191.38  4988.9  190.14  4991.7  189.64
  4994.9  190.14  5017.1  190.84  5060.9  191.45  5087.6  192.32  5111.1  192.24
  5116.5   191.3  5126.8  191.09    5158   191.3  5170.4  190.98  5210.5  191.49
  5299.7  191.21  5322.7  191.54  5365.1  191.39  5394.5  191.69  5690.6  192.12
  5756.4  192.59  5762.3  192.86  5829.3  192.63  5965.6  194.22  6056.1  194.77
#Mann= 3 ,-1 , 0
  4196.3     .05       0  4988.9     .04       0  4994.9     .05       0
Bank Sta=4981.9,5060.9
XS Rating Curve= 0 ,0
Exp/Cntr=0.3,0.1

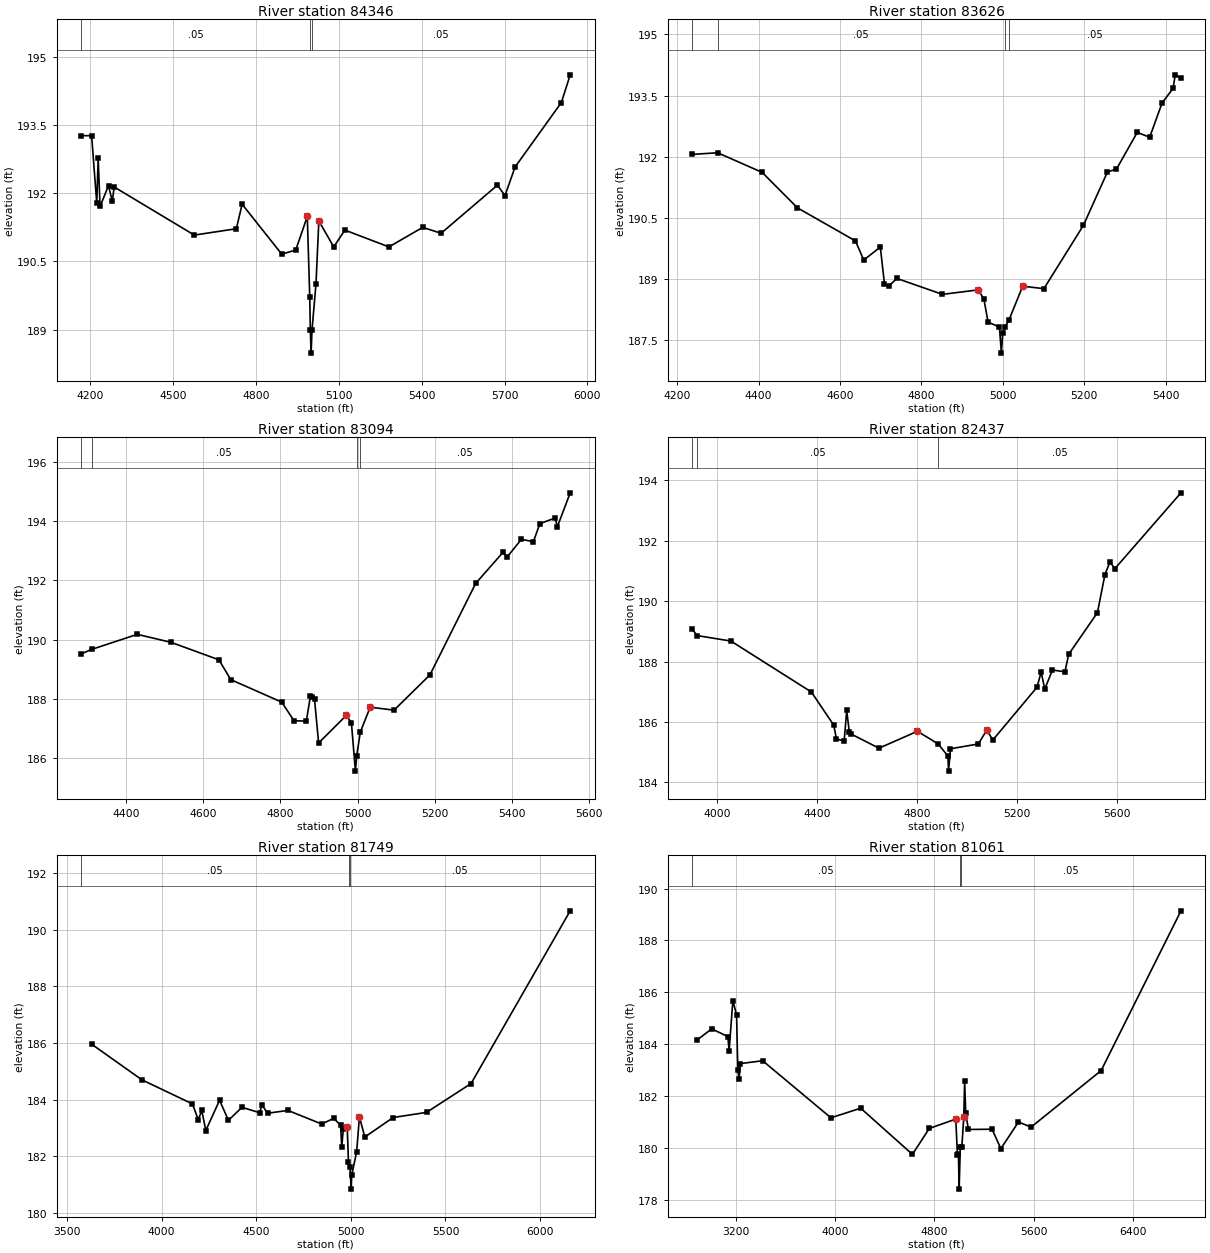
Type RM Length L Ch R = 1 ,84346   ,720,720,720
BEGIN DESCRIPTION:
Mapping XS 08cc6fa3
END DESCRIPTION:
XS GIS Cut Line= 5
      2352174.62     13251750.28      2351963.51     13251792.08
      2351454.19     13252142.28      2351294.56     13252099.39
      2350886.91     13251442.96
#Sta/Elev= 30
  4166.7  193.27  4204.3  193.27  4222.9  191.78    4228  192.78  4234.9  191.71
  4265.5  192.17  4279.3  191.82  4285.9  192.14  4576.3  191.08  4728.6  191.22
  4749.5  191.76    4893  190.66  4943.7  190.75  4985.6  191.49  4994.5  189.71
  4996.6  188.98  4999.4  188.48  5002.6  188.98  5017.1  190.01  5027.4  191.39
  5081.5  190.82  5121.5  191.19  5281.3  190.82  5403.7  191.25  5470.3  191.12
  5674.4  192.18  5701.7  191.95  5738.3  192.58    5906     194    5938  194.61
#Mann= 3 ,-1 , 0
  4166.7     .05       0  4996.6     .04       0  5002.6     .05       0
Bank Sta=4985.6,5027.4
XS Rating Curve= 0 ,0
Exp/Cntr=0.3,0.1

Type RM Length L Ch R = 1 ,83626   ,532,532,532
BEGIN DESCRIPTION:
BAYOU CREEK 111.0
END DESCRIPTION:
XS GIS Cut Line= 2
      2352172.22     13251604.15      2350992.19     13251378.56
#Sta/Elev= 30
  4236.2  192.06  4299.2   192.1  4408.5  191.62  4495.3  190.75  4637.8  189.94
  4658.2  189.47  4698.9  189.79  4709.1  188.89  4719.3  188.83  4739.7  189.02
  4851.6  188.63  4939.5  188.74  4953.5  188.51  4963.6  187.95  4991.5  187.83
  4996.4  187.19  4999.6  187.69  5004.4  187.82  5014.5  187.99  5048.7  188.83
  5100.8  188.77  5197.8  190.32    5257  191.63  5279.2   191.7  5330.2   192.6
  5360.7  192.48  5391.2  193.32  5418.4  193.68  5423.5  194.01  5437.6  193.93
#Mann= 4 ,-1 , 0
  4236.2     .05       0  4299.2     .05       0  5004.4    .035       0
  5014.5     .05       0
Bank Sta=4939.5,5048.7
XS Rating Curve= 0 ,0
Exp/Cntr=0.3,0.1

Type RM Length L Ch R = 1 ,83094   ,657,657,657
BEGIN DESCRIPTION:
Mapping XS ee0970bd
END DESCRIPTION:
XS GIS Cut Line= 2
      2352337.21     13251230.91      2351143.59     13250809.88
#Sta/Elev= 30
  4284.7  189.52  4311.3  189.67  4429.7  190.18  4517.2  189.91    4641  189.32
  4671.9  188.65  4803.7  187.89  4835.6  187.26  4867.4  187.25  4877.9  188.09
  4883.2  188.07  4888.6  187.98  4899.2  186.51  4970.7  187.44    4984   187.2
  4994.4  185.56  4997.6  186.06  5006.9  186.87  5032.6  187.72  5094.4  187.62
  5187.3  188.81  5305.7   191.9  5376.4  192.95    5387  192.79  5424.1  193.39
  5455.1  193.31  5471.8  193.92  5511.7  194.11    5517  193.81  5550.4  194.96
#Mann= 4 ,-1 , 0
  4284.7     .05       0  4311.3     .05       0  4997.6    .035       0
  5006.9     .05       0
Bank Sta=4970.7,5032.6
XS Rating Curve= 0 ,0
Exp/Cntr=0.3,0.1

Type RM Length L Ch R = 1 ,82437   ,688,688,688
BEGIN DESCRIPTION:
BAYOU CREEK 110.0
END DESCRIPTION:
XS GIS Cut Line= 4
      2352379.93     13251207.07       2352195.7     13250481.77
      2351544.66     13250294.27      2351013.42     13250278.64
#Sta/Elev= 30
  3900.3  189.08  3921.2  188.86  4055.9  188.68  4378.3  186.99    4468  185.89
  4478.3  185.44  4509.3  185.36  4519.6  186.38  4529.9  185.67    4537   185.6
  4648.6  185.13  4802.6  185.69  4885.9  185.27  4924.5  184.87  4927.3  184.37
    4935  185.11  5046.5  185.27  5080.2  185.73  5104.4   185.4  5281.3  187.15
  5297.8  187.65  5312.5  187.09  5343.1  187.72  5393.1  187.66  5408.1  188.24
  5523.2  189.62  5553.2  190.88  5573.2   191.3  5593.2  191.08  5857.6  193.59
#Mann= 3 ,-1 , 0
  3900.3     .05       0  3921.2     .05       0  4885.9     .05       0
Bank Sta=4802.6,5080.2
XS Rating Curve= 0 ,0
Exp/Cntr=0.3,0.1

Type RM Length L Ch R = 1 ,81749   ,688,688,688
BEGIN DESCRIPTION:
Mapping XS 09df478f
END DESCRIPTION:
XS GIS Cut Line= 4
      2352485.07     13250943.01       2352724.3     13250272.23
      2351978.52      13249695.3       2351115.5     13249812.56
#Sta/Elev= 30
  3632.9  185.95  3896.7   184.7  4163.4  183.85  4194.2  183.29  4212.7  183.62
    4234  182.91  4306.8  183.98  4353.4  183.27  4425.2  183.73  4517.7  183.54
  4531.1  183.81  4560.1  183.52  4667.8  183.62  4846.2  183.14  4909.7  183.34
  4945.8   183.1  4952.1  182.34  4960.2  182.95  4981.1  183.05  4987.5   181.8
  4995.6  181.62  5001.7  180.84  5004.9  181.34  5030.9  182.16  5045.4  183.39
    5074  182.68  5223.8  183.37  5399.8  183.55  5635.3  184.57  6158.9  190.67
#Mann= 3 ,-1 , 0
    3576     .05       0  4990.4    .035       0  4996.4     .05       0
Bank Sta=4981.1,5045.4
XS Rating Curve= 0 ,0
Exp/Cntr=0.3,0.1

Type RM Length L Ch R = 1 ,81061   ,374,374,374
BEGIN DESCRIPTION:
Mapping XS 95bf9d62
END DESCRIPTION:
XS GIS Cut Line= 4
      2352928.34     13251565.12        2352970.     13249828.99
      2352678.34     13249328.99      2351115.81     13249585.94
#Sta/Elev= 30
  2888.5  184.16  3006.8  184.59  3136.8  184.29  3146.8  183.74  3176.9  185.68
  3206.9  185.13  3216.9  183.01  3226.9  182.65  3236.9  183.25  3416.9  183.36
  3967.1  181.16  4207.1  181.53  4623.7  179.75  4759.7  180.75  4973.1  181.11
  4986.5  179.71  4994.6  179.76  5000.1  178.41  5009.6  180.04  5021.8  180.03
  5037.6   181.2  5044.4  182.56  5053.3  181.34  5074.8  180.71  5265.4  180.72
  5336.4  179.97  5478.2     181  5579.6   180.8  6144.1  182.98  6787.5  189.14
#Mann= 3 ,-1 , 0
  2847.8     .05       0  5006.5    .035       0  5012.5     .05       0
Bank Sta=4973.1,5037.6
XS Rating Curve= 0 ,0
Exp/Cntr=0.3,0.1

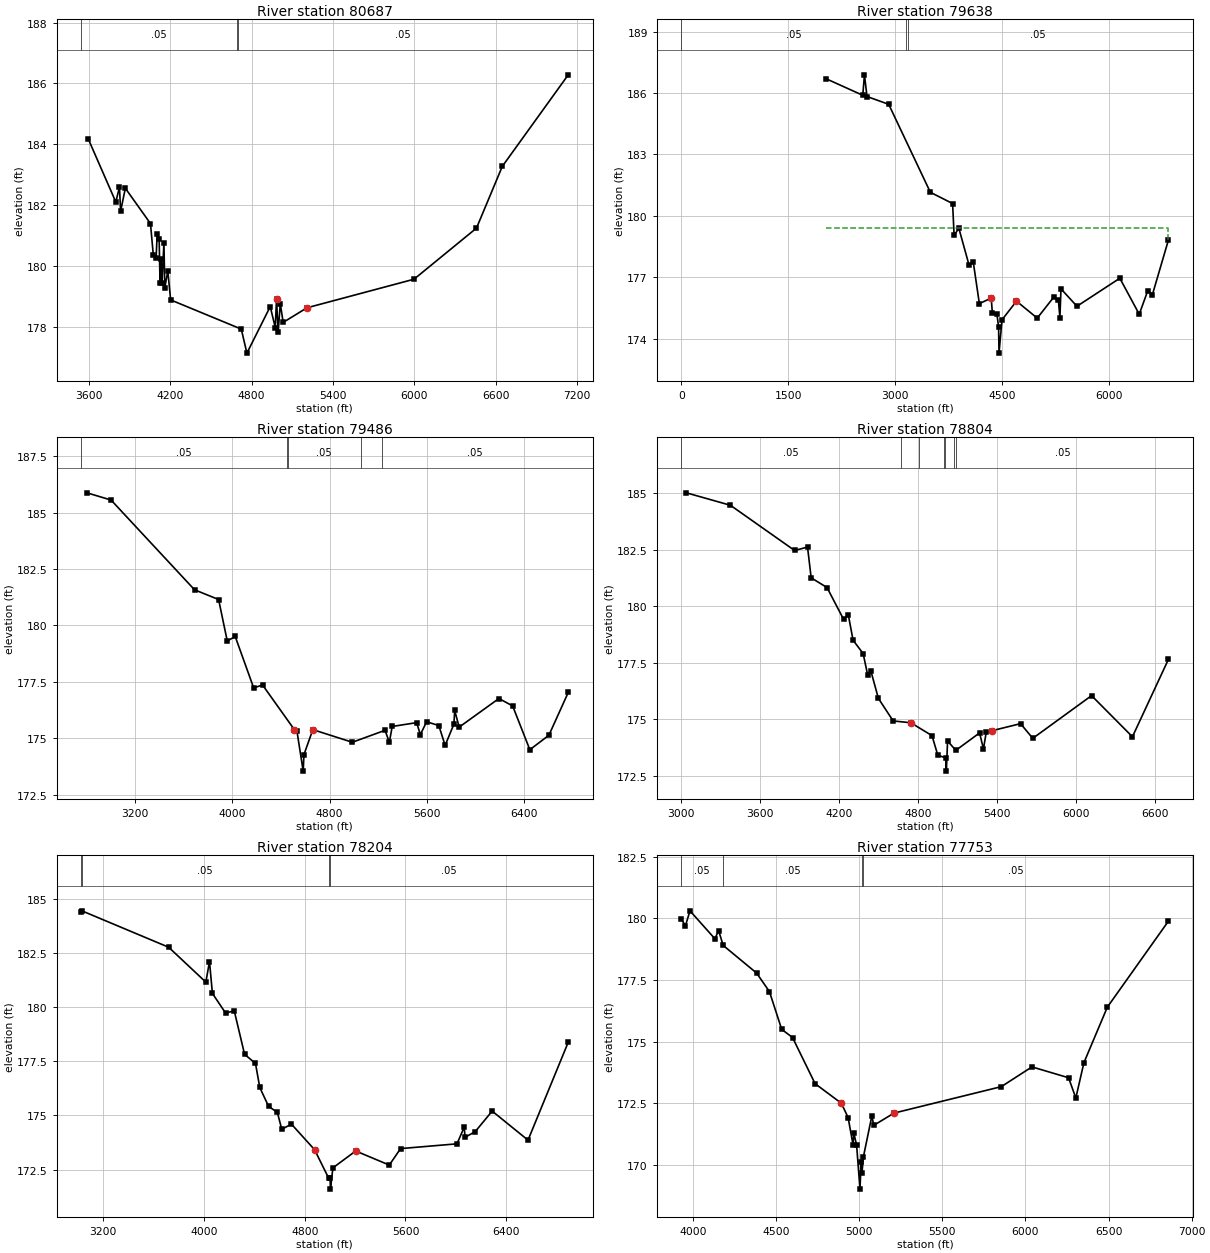
Type RM Length L Ch R = 1 ,80687   ,1049,1049,1049
BEGIN DESCRIPTION:
Mapping XS 6a8414c5
END DESCRIPTION:
XS GIS Cut Line= 5
      2354044.07      13250335.1      2353544.06     13249717.02
      2353169.06      13249432.3      2352912.11     13249001.75
      2351142.04     13249112.81
#Sta/Elev= 30
  3595.3  184.17  3798.3   182.1  3825.5  182.59  3833.5  181.79  3868.7  182.55
  4054.1  181.39  4074.9  180.36  4095.7  180.27  4103.7  181.06  4118.1  180.88
  4124.5  179.45  4132.4  180.22  4138.9  179.42  4153.3  180.76  4159.7  179.28
    4182  179.83  4202.8  178.88    4724  177.92  4765.4  177.13  4937.6  178.66
  4974.6  177.97  4983.9   178.9    4996  177.82  5011.6  178.76    5033  178.14
  5208.1  178.62  5998.1  179.56  6459.1  181.24  6649.5  183.27  7136.1  186.28
#Mann= 3 ,-1 , 0
  3543.5     .05       0    4695     .03       0    4701     .05       0
Bank Sta=4983.9,5208.1
XS Rating Curve= 0 ,0
Exp/Cntr=0.3,0.1

Type RM Length L Ch R = 1 ,79638   ,152,152,152
BEGIN DESCRIPTION:
BAYOU CREEK 109.0
END DESCRIPTION:
XS GIS Cut Line= 3
      2354636.41     13251071.85      2352604.22     13247878.31
      2351989.02     13247061.72
#Sta/Elev= 30
  2031.7   186.7  2547.4  185.89    2571  186.89  2606.6  185.83  2911.4  185.45
  3496.5  181.15  3808.9   180.6    3830  179.05  3896.9  179.39  4040.8  177.58
    4100  177.72  4184.8  175.71  4351.6  175.98  4366.8  175.27  4431.9  175.18
  4454.9  174.58  4460.6  173.29  4503.1  174.92  4706.3  175.83  4997.6     175
  5227.9  176.02  5294.8  175.88  5315.9  175.03  5331.2  176.43  5555.5  175.58
  6157.5  176.95  6430.2  175.19    6551  176.35  6615.5  176.15  6839.4  178.81
#Mann= 3 ,-1 , 0
       0     .05       03154.084     .03       03184.028     .05       0
#XS Ineff= 2 , 0
          1867.2  179.39
Permanent Ineff=
       F       F
Bank Sta=4351.6,4706.3
XS Rating Curve= 0 ,0
Exp/Cntr=0.3,0.1

Type RM Length L Ch R = 1 ,79486   ,682,682,682
BEGIN DESCRIPTION:
BAYOU CREEK 108.0
END DESCRIPTION:
XS GIS Cut Line= 3
      2354331.13     13250344.64      2352673.04     13247700.99
      2352122.05     13247067.07
#Sta/Elev= 30
    2804  185.88  3002.1  185.56  3689.1  181.58    3887  181.15  3958.2  179.31
  4023.7  179.51  4175.7  177.23  4248.8  177.36  4510.4  175.38  4531.6  175.32
  4583.2  173.54  4589.3  174.27  4662.4  175.38  4987.6  174.82  5256.6  175.35
  5292.1  174.82  5315.7  175.52  5516.7  175.69  5547.3  175.16    5599  175.73
  5699.3  175.56  5751.2  174.68  5823.2  175.62  5830.1  176.23  5866.6  175.49
    6194  176.76  6306.9  176.43  6448.4  174.49  6605.1  175.13  6764.5  177.03
#Mann= 5 ,-1 , 0
  2756.8     .05       0    4449     .03       0    4455     .05       0
  5056.5      .1       0  5231.9     .05       0
Bank Sta=4510.4,4662.4
XS Rating Curve= 0 ,0
Exp/Cntr=0.3,0.1

Type RM Length L Ch R = 1 ,78804   ,600,600,600
BEGIN DESCRIPTION:
BAYOU CREEK 106.0
END DESCRIPTION:
XS GIS Cut Line= 3
      2354436.42     13249671.88      2353535.75     13247983.27
      2352092.04     13247003.09
#Sta/Elev= 30
  3043.8  185.02  3378.2  184.47  3865.5  182.47  3963.6  182.62  3991.2  181.26
  4111.6  180.83  4237.7  179.42  4273.5  179.61  4309.3   178.5  4385.8  177.91
  4420.9  176.94  4443.5  177.16  4501.2  175.93  4613.5  174.93  4747.7  174.85
  4908.2  174.28  4952.7  173.41  5011.6   173.3  5017.4  172.71  5026.5  174.04
  5089.5  173.63  5269.5   174.4    5299  173.69    5320  174.43  5364.9   174.5
  5580.5  174.81  5673.3  174.16  6119.5  176.05  6429.8  174.23  6702.6  177.65
#Mann= 7 ,-1 , 0
  3006.1     .05       0  4671.1      .1       0  4806.7     .05       0
  5003.1     .03       0  5009.1     .05       0  5078.3      .1       0
  5093.4     .05       0
Bank Sta=4747.7,5364.9
XS Rating Curve= 0 ,0
Exp/Cntr=0.3,0.1

Type RM Length L Ch R = 1 ,78204   ,451,451,451
BEGIN DESCRIPTION:
BAYOU CREEK 105.0
END DESCRIPTION:
XS GIS Cut Line= 3
      2354636.42     13249321.87      2353836.41     13247521.85
      2352036.37     13246921.84
#Sta/Elev= 30
  3025.3  184.38  3029.9  184.44  3719.3  182.76  4014.7  181.15  4043.5   182.1
  4066.7  180.63  4170.7  179.73  4240.4  179.82  4322.1  177.82  4408.7   177.4
  4442.9  176.29  4512.7  175.42  4582.4  175.14  4617.5  174.36  4694.1   174.6
  4877.9  173.42  4989.6  172.11  5001.2   172.1    5004   171.6  5023.4  172.58
  5204.5  173.36  5471.4  172.71    5561  173.47    6009  173.69  6066.9  174.47
  6072.2  173.99  6153.2  174.25  6288.3   175.2  6572.9  173.86  6892.5  178.38
#Mann= 4 ,-1 , 0
  3025.3     .05       0  3029.9     .05       0  4989.6     .03       0
  5001.2     .05       0
Bank Sta=4877.9,5204.5
XS Rating Curve= 0 ,0
Exp/Cntr=0.3,0.1

Type RM Length L Ch R = 1 ,77753   ,854,854,854
BEGIN DESCRIPTION:
BAYOU CREEK 104.0
END DESCRIPTION:
XS GIS Cut Line= 3
       2354647.4     13247570.52      2354211.18     13247237.49
      2351886.39     13246721.85
#Sta/Elev= 30
  3929.8  179.95  3954.4   179.7  3981.5   180.3  4131.2  179.17  4153.9   179.5
  4181.1   178.9  4382.3  177.78  4459.5  177.03  4533.4   175.5  4598.5  175.17
  4734.3   173.3  4891.9  172.51  4932.9  171.93  4962.5  170.83  4967.6  171.29
  4984.1  170.81  5004.3  169.03  5011.2  170.11  5016.3  169.69    5025  170.34
  5076.3  172.01  5086.5  171.61  5209.4  172.11  5854.7  173.18  6039.1  173.98
  6259.4  173.54    6303  172.72  6351.7  174.15  6492.7   176.4  6859.9  179.88
#Mann= 4 ,-1 , 0
  3929.8     .05       0  4181.1     .05       0  5016.3     .03       0
    5025     .05       0
#XS Ineff= 2 , 0
                         6043.47          173.94
Permanent Ineff=
       F       F
Bank Sta=4891.9,5209.4
XS Rating Curve= 0 ,0
Exp/Cntr=0.3,0.1

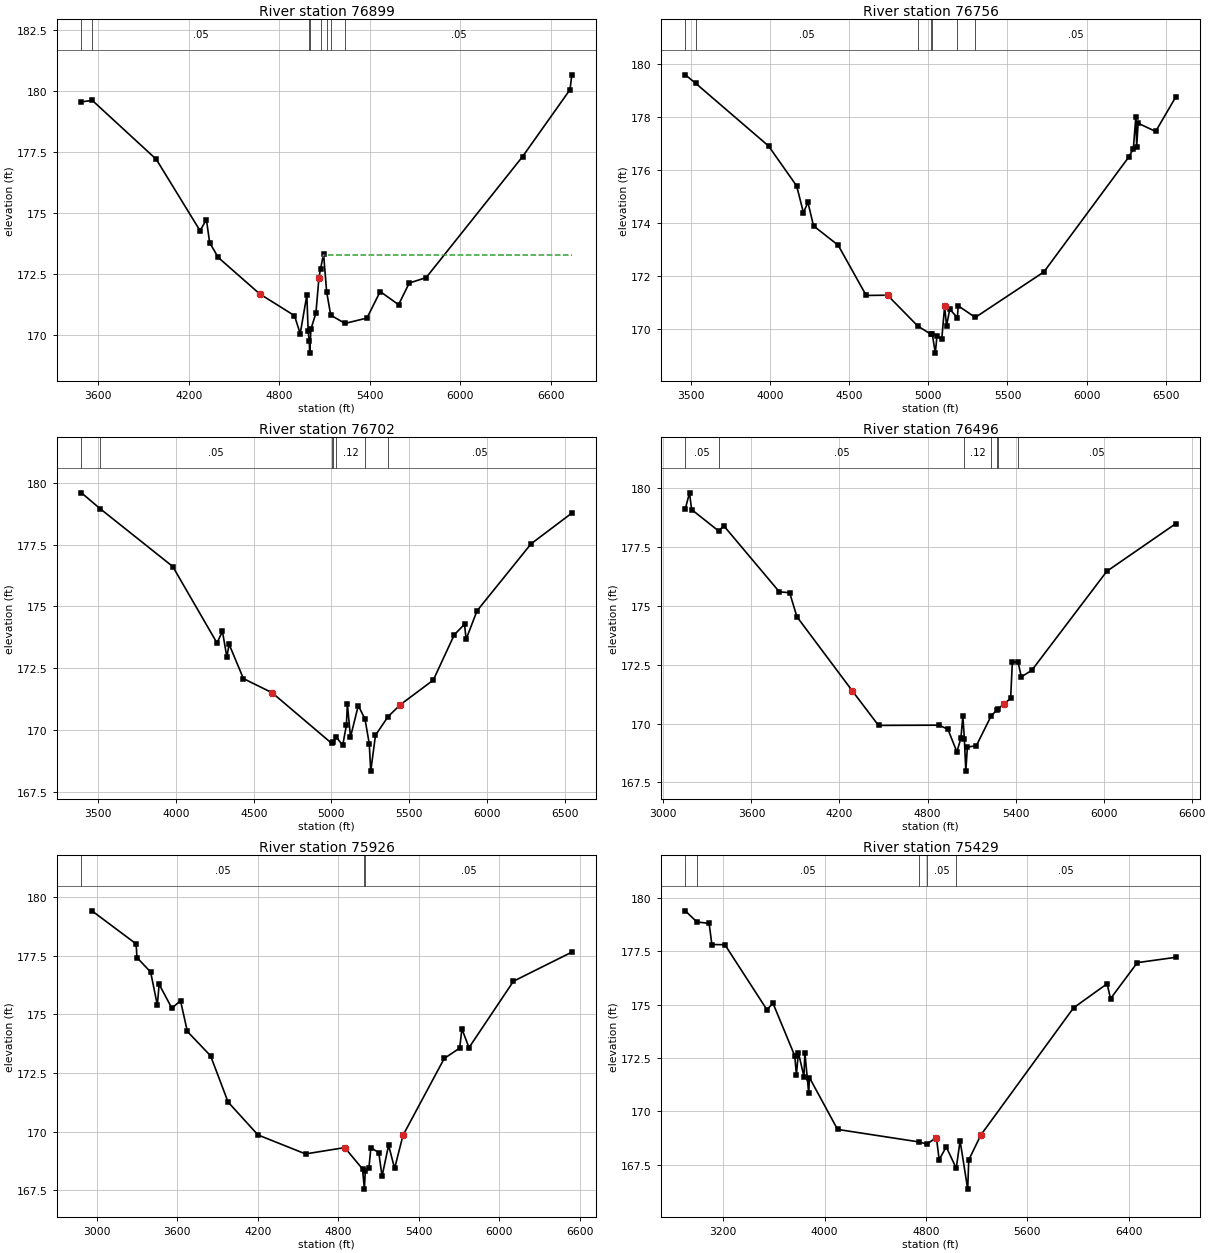
Type RM Length L Ch R = 1 ,76899   ,143,143,143
BEGIN DESCRIPTION:
Mapping XS 51209092
END DESCRIPTION:
XS GIS Cut Line= 4
       2354676.9     13247349.22      2353694.29     13246335.37
      2353583.18     13246300.65      2351885.67     13246591.26
#Sta/Elev= 30
  3488.9  179.56  3560.8  179.62    3985   177.2  4274.9  174.27  4317.4  174.72
  4338.7  173.78  4395.3  173.17    4671  171.67  4900.8  170.78  4939.1  170.04
  4982.9  171.62  4991.5  170.15    4999  169.74  5001.7  169.24  5010.2  170.23
    5043  170.88  5063.3  172.34  5073.5  172.69  5093.8  173.32    5114  171.77
  5141.1   170.8  5235.8  170.46  5381.4  170.68  5469.1  171.77  5590.9  171.23
  5661.9  172.12  5773.5  172.34  6412.7  177.31  6727.2  180.06  6739.4  180.67
#Mann= 8 ,-1 , 0
  3488.9     .05       0  3560.8     .05       0    4999     .03       0
  5001.7     .05       0  5073.5     .12       0    5114     .05       0
  5141.1      .1       0  5235.8     .05       0
#XS Ineff= 2 , 0
                         5088.64          173.29
Permanent Ineff=
       F       F
Bank Sta=4671,5063.3
XS Rating Curve= 0 ,0
Exp/Cntr=0.3,0.1

Type RM Length L Ch R = 1 ,76756   ,54,54,54
BEGIN DESCRIPTION:
Mapping XS f4c1b5c8
END DESCRIPTION:
XS GIS Cut Line= 6
      2354656.07     13247300.62      2353973.17     13246520.87
      2353740.13     13246308.98      2353674.15     13246173.56
      2353602.97     13246173.56      2352092.11     13246363.02
#Sta/Elev= 30
  3465.9   179.6  3531.2  179.28  3991.5  176.91    4169   175.4  4211.7  174.39
  4240.2  174.78  4275.3  173.89  4430.9  173.16  4608.1  171.26  4742.5  171.27
  4932.6  170.11  5014.8   169.8  5024.8  169.82  5044.5  169.08  5054.9  169.74
  5085.1  169.61  5103.2  170.85  5115.3  170.11  5135.5  170.74  5183.7  170.42
  5188.7  170.87  5296.8  170.43  5730.1  172.15  6264.3  176.48  6294.5   176.8
  6310.7  178.02  6315.7  176.88  6324.7  177.77  6435.6  177.46  6562.2  178.76
#Mann= 7 ,-1 , 0
  3465.9     .05       0  3531.2     .05       0  4932.6     .12       0
  5014.8     .07       0  5024.8     .12       0  5183.7      .1       0
  5296.8     .05       0
Bank Sta=4742.5,5103.2
XS Rating Curve= 0 ,0
Exp/Cntr=0.3,0.1

Type RM Length L Ch R = 1 ,76702   ,206,206,206
BEGIN DESCRIPTION:
Mapping XS dd6bde5f
END DESCRIPTION:
XS GIS Cut Line= 4
      2354681.94     13247291.59      2353688.91     13246128.42
      2353550.02     13246135.37      2352070.85     13245985.55
#Sta/Elev= 30
  3391.6  179.59  3511.6  178.95  3979.3  176.61  4263.7  173.52  4298.8  173.99
  4327.3  172.95  4341.6  173.47  4433.8  172.08  4618.3  171.51  5002.3  169.46
  5012.3  169.52  5032.3  169.71  5072.4  169.38  5096.2  170.19  5102.6  171.05
  5122.7  169.72  5172.9  170.99  5216.2  170.44  5243.3  169.45  5253.1  168.34
  5283.5  169.79  5363.9  170.54  5444.3  171.03  5655.4  172.02  5790.3  173.85
  5856.4  174.28  5866.5  173.67  5936.8  174.82  6284.7  177.53  6546.8  178.77
#Mann= 7 ,-1 , 0
  3391.6     .05       0  3511.6     .05       0  5002.3    .035       0
  5012.3     .05       0  5032.3     .12       0  5216.2      .1       0
  5363.9     .05       0
Bank Sta=4618.3,5444.3
XS Rating Curve= 0 ,0
Exp/Cntr=0.3,0.1

Type RM Length L Ch R = 1 ,76496   ,570,570,570
BEGIN DESCRIPTION:
BAYOU CREEK 103.0
END DESCRIPTION:
XS GIS Cut Line= 3
      2354813.05       13247151.      2353948.46     13246062.45
      2352038.08     13245661.64
#Sta/Elev= 30
  3149.3  179.11  3177.9  179.79  3192.3  179.08  3376.5  178.17  3411.7  178.39
  3789.8  175.59  3860.3  175.55    3910  174.53  4288.1  171.38  4465.9  169.92
  4877.4  169.93  4938.7  169.76    5000   168.8  5027.4  169.37  5040.8  170.31
  5051.1  169.35    5061  167.98  5071.5     169  5132.8  169.06    5235  170.34
  5271.8  170.56  5276.9   170.6  5321.7  170.83  5366.5  171.07    5378   172.6
  5416.4  172.62  5439.3  171.98  5510.9  172.26  6021.8  176.46  6491.4  178.48
#Mann= 7 ,-1 , 0
  3149.3     .05       0  3376.5     .05       0  5051.1     .12       0
    5235      .1       0  5271.8    .035       0  5276.9      .1       0
  5416.4     .05       0
Bank Sta=4288.1,5321.7
XS Rating Curve= 0 ,0
Exp/Cntr=0.3,0.1

Type RM Length L Ch R = 1 ,75926   ,497,497,497
BEGIN DESCRIPTION:
Mapping XS ecf09aac
END DESCRIPTION:
XS GIS Cut Line= 4
      2354927.65     13247052.07      2353948.46     13245583.28
      2353266.17     13245390.58      2352177.62     13245229.12
#Sta/Elev= 30
  2964.2  179.41  3293.3     178  3299.3  177.42  3401.4   176.8  3451.2  175.39
  3464.5  176.28  3559.4  175.26  3623.8  175.58  3674.9  174.27  3847.8  173.23
  3978.3  171.26  4200.7  169.86  4555.2  169.05  4847.4  169.32  4979.6  168.41
  4993.5  167.55  5000.4  168.32  5027.7  168.47    5042  169.32  5100.9   169.1
  5125.1   168.1    5174  169.42  5218.6  168.43    5281  169.84  5588.5  173.12
  5703.6  173.56  5719.9  174.38    5773  173.58  6104.1  176.41  6538.9  177.65
#Mann= 3 ,-1 , 0
  2885.8     .05       0  4993.1    .035       0  4999.1     .05       0
Bank Sta=4847.4,5281
XS Rating Curve= 0 ,0
Exp/Cntr=0.3,0.1

Type RM Length L Ch R = 1 ,75429   ,440,440,440
BEGIN DESCRIPTION:
BAYOU CREEK 102.0
END DESCRIPTION:
XS GIS Cut Line= 3
       2355036.4     13246971.83      2354036.41     13245171.85
      2352236.39     13244971.85
#Sta/Elev= 30
  2900.6   179.4  2991.3  178.88  3088.6  178.81  3110.3  177.82  3213.2  177.81
  3543.8  174.77    3593  175.06  3764.3   172.6  3777.2  171.72  3793.2  172.75
  3836.7  171.63  3844.3  172.75  3874.5  170.84  3880.2  171.58  4102.1  169.15
  4748.1  168.56  4806.8  168.46  4882.3  168.77    4904  167.73  4959.7  168.33
  5038.9  167.33  5069.1  168.62  5129.2  166.35  5137.6  167.72  5233.2  168.89
  5964.5  174.85  6229.3  175.98  6256.3  175.28  6467.6  176.97  6770.8  177.22
#Mann= 5 ,-1 , 0
  2900.6     .05       0  2991.3     .05       0  4748.1      .1       0
  4806.8     .05       0  5038.9     .05       0
Bank Sta=4882.3,5233.2
XS Rating Curve= 0 ,0
Exp/Cntr=0.3,0.1