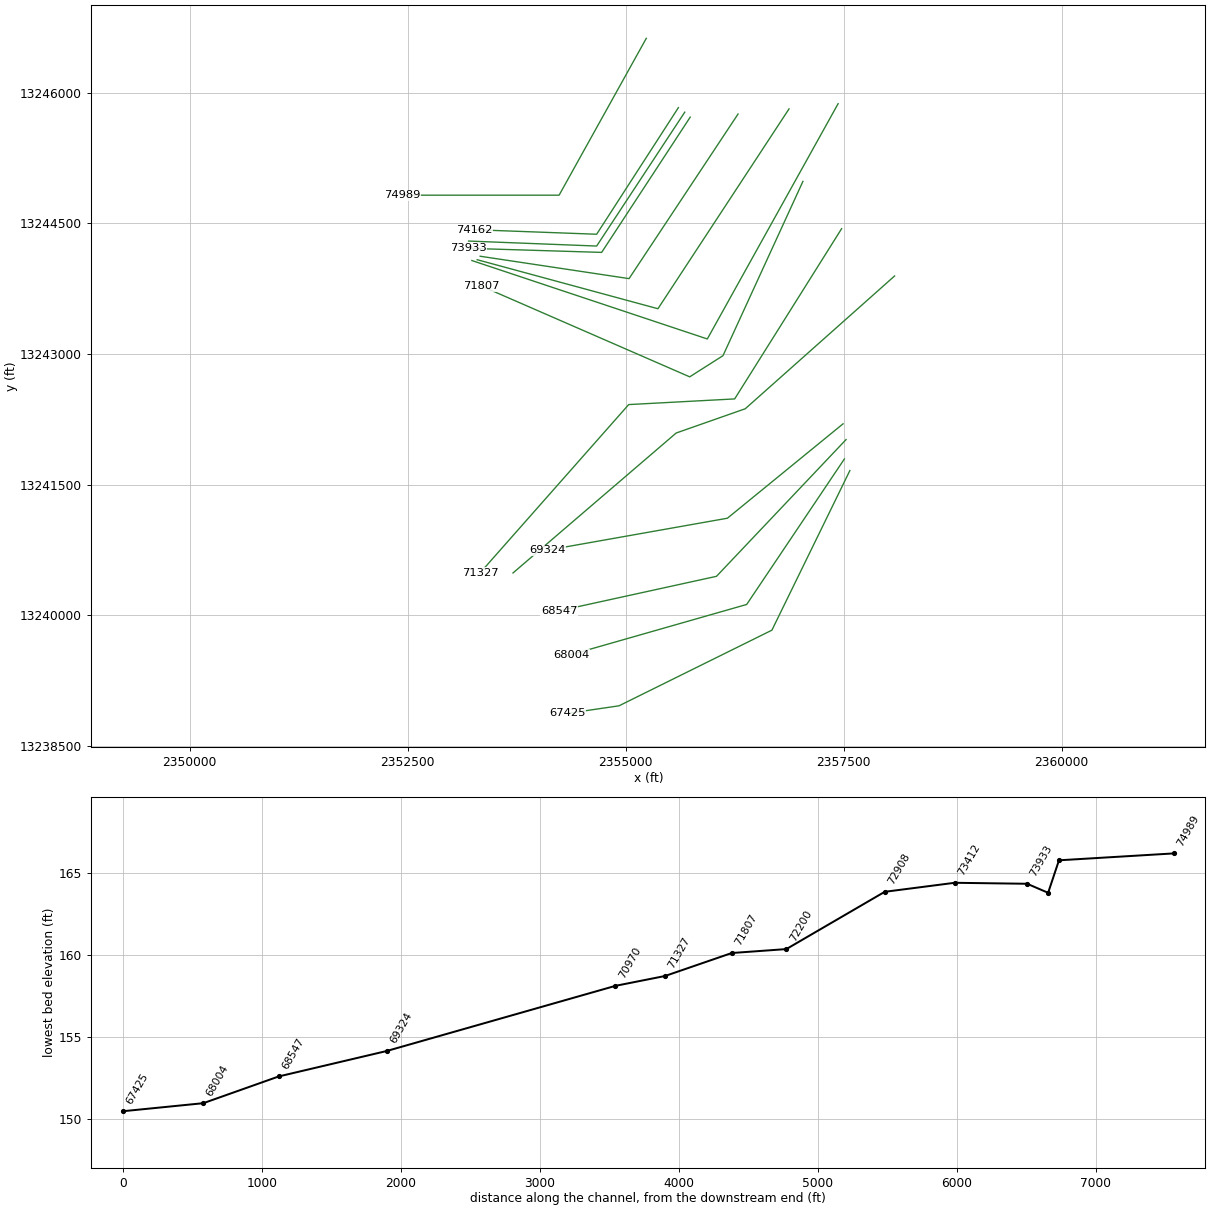
HEC-RAS study BAYOU CREEK.prj: BAYOU CREEK Base Level Engineering

--- BAYOU CREEK.g01 (geometry) --- (continued)

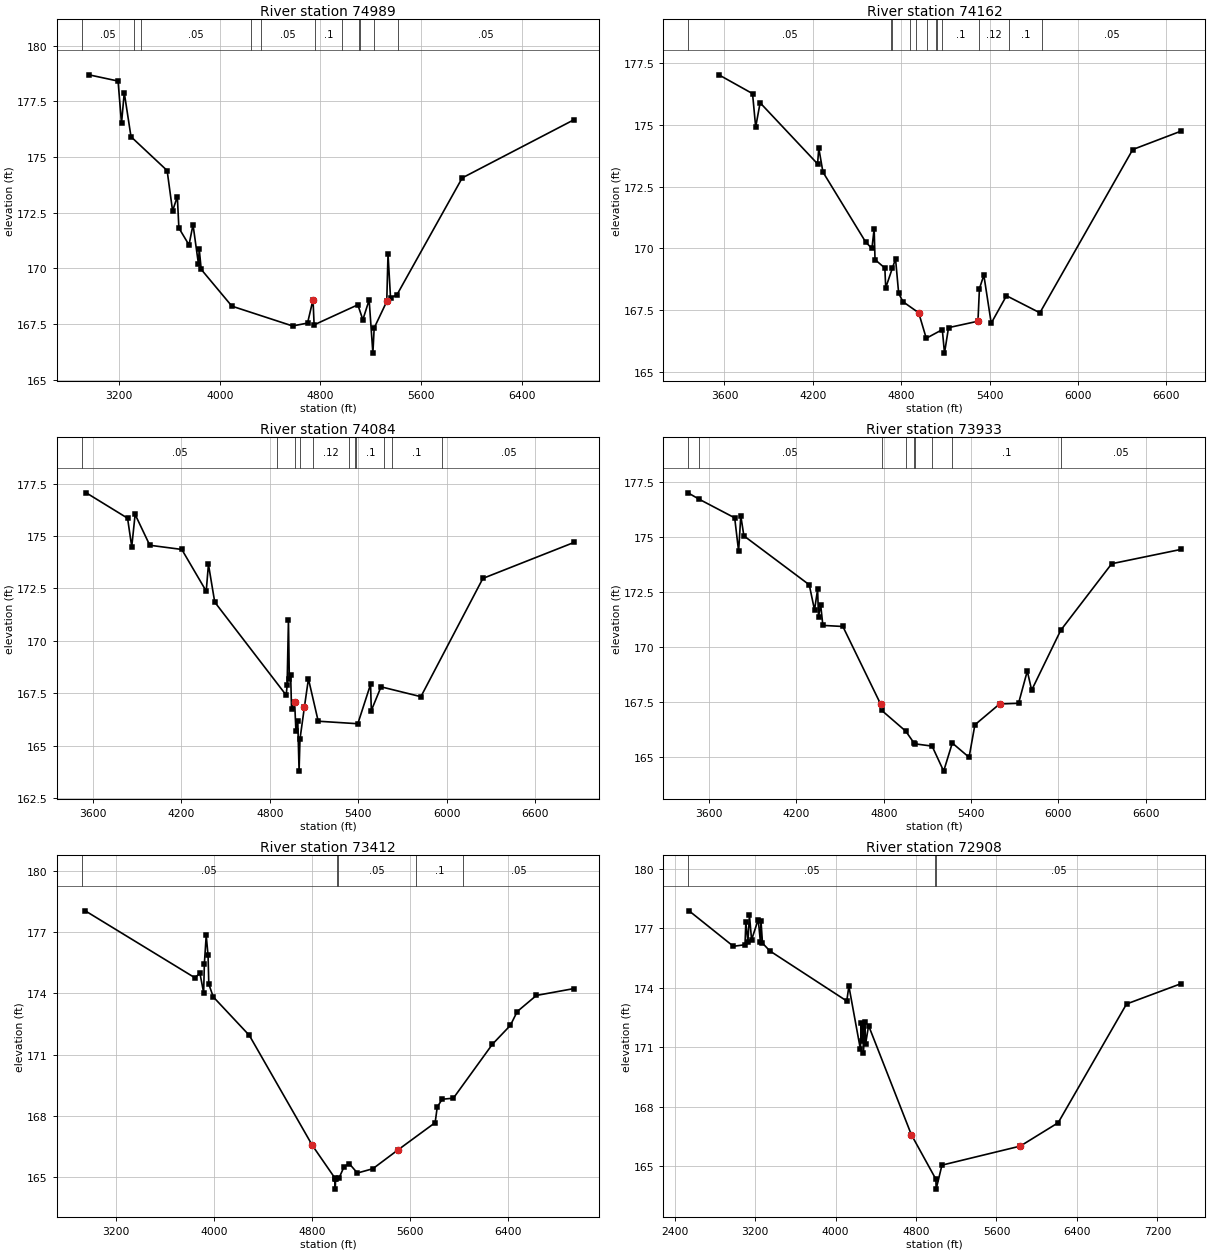
Type RM Length L Ch R = 1 ,74989   ,827,827,827
BEGIN DESCRIPTION:
BAYOU CREEK 101.0
END DESCRIPTION:
XS GIS Cut Line= 3
      2355236.43     13246621.89      2354236.41     13244821.85
      2352436.38     13244821.85
#Sta/Elev= 30
  2959.4  178.69  3190.9  178.41  3218.3  176.51  3240.1  177.89  3293.8  175.91
    3581  174.39  3624.4  172.58  3662.2  173.22  3674.4  171.81  3754.9  171.05
  3786.9  171.96  3830.4  170.18  3836.1  170.87  3852.1  169.95  4095.8   168.3
  4578.5  167.41  4697.5  167.54    4741  168.59  4749.7  167.46  5097.3  168.36
  5137.3  167.69  5187.3  168.58    5217  166.19  5227.3  167.32  5327.3  168.51
  5337.3  170.64  5357.3  168.68  5407.3   168.8  5927.3  174.06  6818.6  176.68
#Mann= 11 ,-1 , 0
  2900.6     .05       0  3314.8      .1       0    3371     .05       0
  4246.7      .1       0  4326.3     .05       0  4756.8      .1       0
  4973.2     .12       0  5106.7     .07       0  5112.7     .12       0
  5226.7      .1       0  5418.1     .05       0
Bank Sta=4741,5327.3
XS Rating Curve= 0 ,0
Exp/Cntr=0.3,0.1

Type RM Length L Ch R = 1 ,74162   ,78,78,78
BEGIN DESCRIPTION:
Mapping XS 15624c15
END DESCRIPTION:
XS GIS Cut Line= 3
      2355604.69     13245826.75      2354667.21     13244373.65
      2353261.84      13244425.7
#Sta/Elev= 30
  3562.2  177.02  3790.7  176.26    3812  174.91  3842.1  175.89  4232.2  173.42
  4240.4  174.06  4268.5  173.09  4558.8  170.26  4601.1     170  4616.3   170.8
  4622.2  169.55  4688.9  169.21  4694.8  168.41  4740.2  169.21  4761.5  169.58
  4782.6  168.19  4811.6  167.85  4918.7   167.4    4970  166.37  5078.9  166.72
  5093.8  165.77  5121.1   166.8    5321  167.06    5331  168.38    5361  168.92
    5411  166.98  5514.6  168.09  5741.3   167.4  6371.7     174  6697.8  174.74
#Mann= 12 ,-1 , 0
  3352.7     .05       0  4728.2      .1       0  4740.2     .05       0
  4857.7      .1       0  4901.4     .05       0  4977.5     .12       0
  5036.9     .07       0  5042.9     .12       0  5074.7      .1       0
  5330.2     .12       0  5530.5      .1       0  5758.4     .05       0
Bank Sta=4918.7,5321
XS Rating Curve= 0 ,0
Exp/Cntr=0.3,0.1

Type RM Length L Ch R = 1 ,74084   ,151,151,151
BEGIN DESCRIPTION:
BAYOU CREEK 100.0
END DESCRIPTION:
XS GIS Cut Line= 3
       2355677.6     13245774.65      2354667.21     13244238.23
       2353198.5     13244295.52
#Sta/Elev= 30
  3556.3  177.06  3836.5  175.85  3864.8  174.49  3887.8  176.03  3987.1  174.56
  4204.1  174.36  4369.7  172.37  4384.8  173.65  4427.4  171.85    4912  167.41
  4918.1  167.88  4927.1  170.99  4933.1  168.17    4942  168.38  4948.2  166.74
  4969.2  167.07  4977.9  165.68  4990.3  166.17  4999.2  163.79  5005.4  165.32
  5035.6  166.86  5062.6  168.19  5128.9  166.17  5397.4  166.05  5483.9  167.93
  5488.9  166.68  5554.8  167.81    5825  167.34  6245.3  172.98    6865   174.7
#Mann= 11 ,-1 , 0
  3524.6     .05       0    4852      .1       0  4972.6     .05       0
  5007.3      .1       0  5093.1     .12       0  5334.3      .1       0
  5381.3    .035       0  5387.3      .1       0  5577.1     .12       0
  5629.5      .1       0    5971     .05       0
Bank Sta=4969.2,5035.6
XS Rating Curve= 0 ,0
Exp/Cntr=0.3,0.1

Type RM Length L Ch R = 1 ,73933   ,521,521,521
BEGIN DESCRIPTION:
Mapping XS d2fb4162
END DESCRIPTION:
XS GIS Cut Line= 3
      2355740.12     13245717.39       2354724.5     13244165.32
      2353193.26     13244212.19
#Sta/Elev= 30
  3454.7  177.02    3528  176.74  3775.4  175.88  3802.4  174.36  3817.5  175.97
  3838.6  175.06    4288  172.83  4324.2  171.68  4345.3  172.62  4351.6  171.37
  4366.3  171.93  4381.4  170.98    4519  170.93  4779.5  167.38  4785.5  167.11
  4951.3  166.16  5008.9  165.61  5017.7  165.58  5132.3  165.48  5211.8  164.34
  5271.1  165.62  5386.4  164.97  5426.4  166.45  5596.5   167.4  5726.5  167.43
  5786.5   168.9  5816.6  168.03  6016.6  170.76  6366.8  173.79  6841.5  174.44
#Mann= 9 ,-1 , 0
  3454.7     .05       0    3528     .05       0  4785.5      .1       0
  4951.3     .05       0  5008.9    .035       0  5017.7     .05       0
  5132.3     .12       0  5271.1      .1       0  6016.6     .05       0
Bank Sta=4779.5,5596.5
XS Rating Curve= 0 ,0
Exp/Cntr=0.3,0.1

Type RM Length L Ch R = 1 ,73412   ,504,504,504
BEGIN DESCRIPTION:
Mapping XS 51ca1d34
END DESCRIPTION:
XS GIS Cut Line= 3
       2356288.8     13245753.22      2355038.82     13243864.36
      2353331.63     13244121.13
#Sta/Elev= 30
  2949.5  178.05  3843.5  174.77  3885.6  174.98  3915.7  174.04  3921.7  175.46
  3936.7  176.84  3951.8  175.86  3957.8  174.46  3993.9  173.83  4288.7  171.94
  4803.3  166.54  4983.7  164.97  4986.8   164.9  4989.6   164.4  4992.8   164.9
  5019.6  164.93    5062   165.5  5104.1  165.65  5170.4  165.19  5296.5   165.4
  5498.8  166.31    5805  167.66  5822.4  168.43  5862.8  168.81  5953.8  168.86
  6272.9  171.51    6419  172.43  6474.9  173.11  6631.4   173.9  6940.9  174.24
#Mann= 5 ,-1 , 0
  2919.3     .05       0  5004.5    .035       0  5010.5     .05       0
  5648.3      .1       0    6036     .05       0
Bank Sta=4803.3,5498.8
XS Rating Curve= 0 ,0
Exp/Cntr=0.3,0.1

Type RM Length L Ch R = 1 ,72908   ,708,708,708
BEGIN DESCRIPTION:
Mapping XS 9346fd2b
END DESCRIPTION:
XS GIS Cut Line= 3
      2356873.57     13245812.31      2355370.07     13243518.87
      2353297.17     13244081.37
#Sta/Elev= 30
  2542.4  177.89  2983.5   176.1    3099  176.18  3107.2  177.31  3128.2  176.34
  3143.3  177.66  3164.4  176.43  3230.5  177.45  3251.9  176.34  3257.8   177.4
  3272.9  176.26  3345.3  175.87    4111  173.34    4132  174.09  4246.9   170.9
  4255.7  172.21  4261.6   171.3  4270.8   172.1  4276.7  170.72  4291.8  172.26
  4297.8  171.16    4328   172.1    4753   166.6  4997.2  164.35  4999.9  163.85
  5057.5  165.06  5836.3  166.02  6213.5   167.2  6893.2  173.19  7432.6  174.21
#Mann= 3 ,-1 , 0
  2532.3     .05       0  4991.2    .035       0  4997.2     .05       0
Bank Sta=4753,5836.3
XS Rating Curve= 0 ,0
Exp/Cntr=0.3,0.1

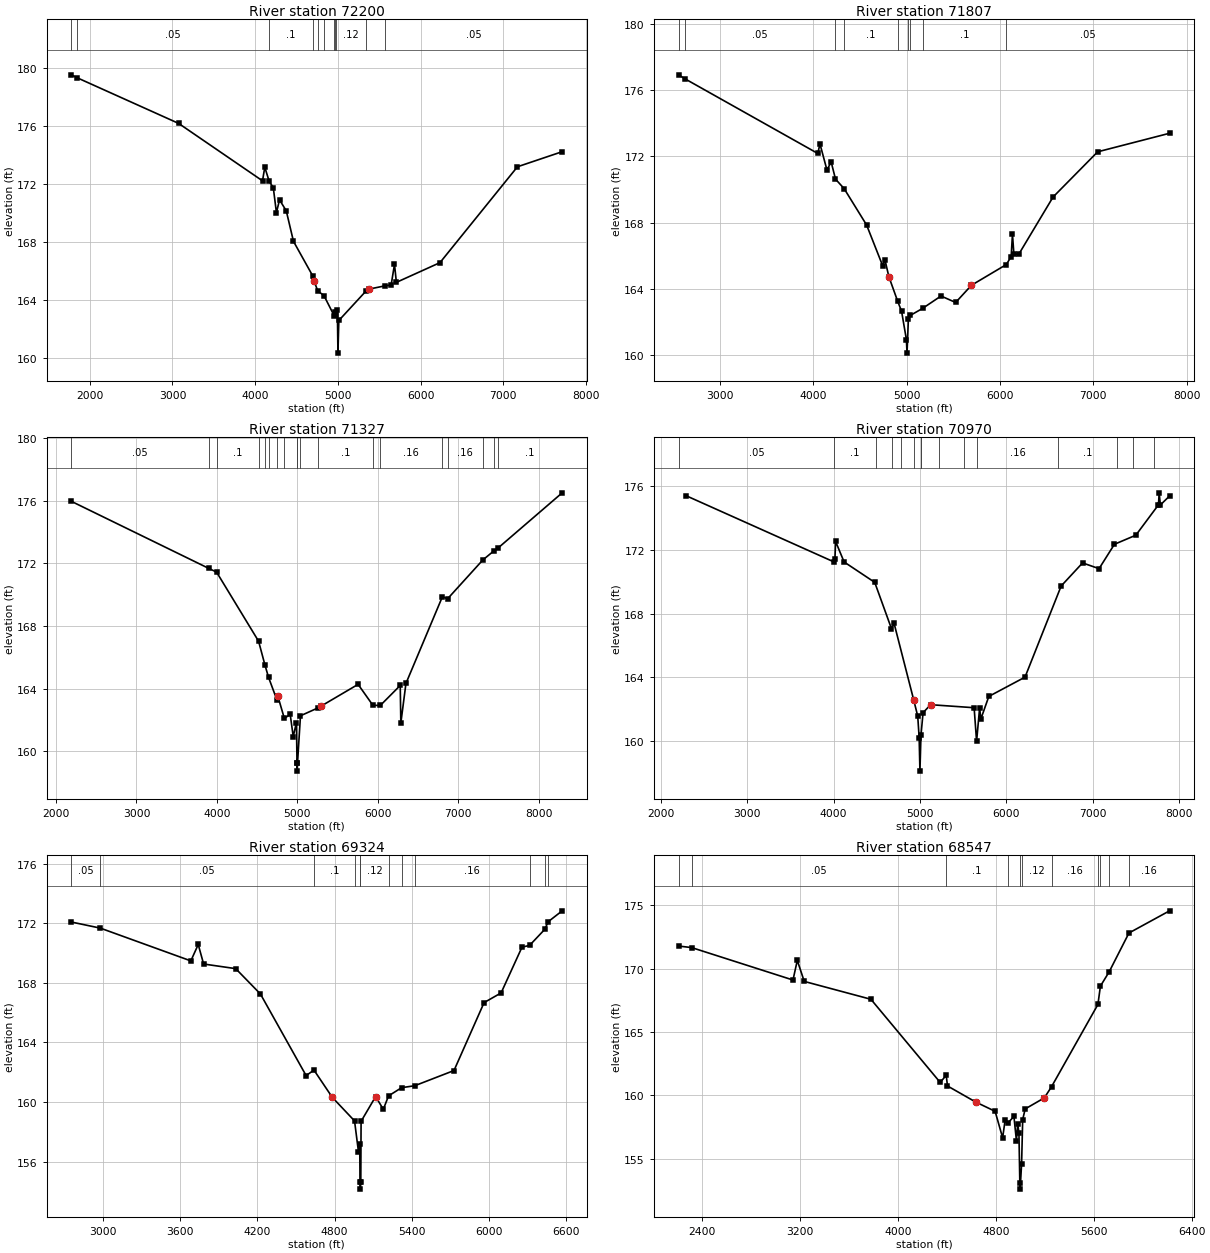
Type RM Length L Ch R = 1 ,72200   ,393,393,393
BEGIN DESCRIPTION:
BAYOU CREEK 99.0
END DESCRIPTION:
XS GIS Cut Line= 3
      2357436.41     13245871.86      2355936.41     13243171.85
      2353236.46     13244071.84
#Sta/Elev= 30
  1776.3  179.55    1851  179.34  3074.7   176.2  4088.6  172.24  4116.1  173.18
  4169.8   172.2    4219  171.77  4256.8  170.05  4294.5  170.93  4375.8  170.17
  4462.7  168.07  4699.1  165.65  4712.1  165.33  4756.3  164.65    4831  164.33
  4956.5  162.92  4961.8  163.19  4979.6     163  4993.4  163.33  5000.4  160.36
  5011.2  162.61    5336  164.62  5380.1  164.78  5569.9     165  5643.6  165.06
  5683.9  166.48  5706.9  165.24  6233.9   166.6  7170.1  173.21    7711  174.25
#Mann= 11 ,-1 , 0
  1776.3     .05       0    1851     .05       0  4169.8      .1       0
  4699.1     .16       0  4756.3      .1       0    4831     .16       0
  4956.5     .07       0  4961.8     .16       0  4979.6     .12       0
    5336      .1       0  5569.9     .05       0
Bank Sta=4712.1,5380.1
XS Rating Curve= 0 ,0
Exp/Cntr=0.3,0.1

Type RM Length L Ch R = 1 ,71807   ,480,480,480
BEGIN DESCRIPTION:
Mapping XS b3d147ab
END DESCRIPTION:
XS GIS Cut Line= 4
      2357032.87     13244980.25       2356116.2     13242980.25
      2355734.25     13242737.19      2353345.38     13243778.85
#Sta/Elev= 30
  2557.8  176.93  2626.1  176.69  4049.1  172.18  4072.1  172.76  4146.6  171.19
  4192.6  171.66  4238.6  170.63  4330.6  170.06  4571.7  167.86  4743.7   165.4
  4767.7  165.77  4810.1  164.74  4904.1  163.26  4946.4  162.65    4998  160.94
  5004.7  160.12  5019.2  162.16  5040.5   162.4  5170.9  162.82  5368.7  163.57
  5525.6  163.18  5694.9  164.22    6068  165.47  6120.3  165.95  6134.1  167.31
  6149.2  166.12  6201.5  166.09  6569.1  169.55  7046.8  172.28  7816.7   173.4
#Mann= 9 ,-1 , 0
  2557.8     .05       0  2626.1     .05       0  4238.6     .16       0
  4330.6      .1       0  4904.1     .16       0  5019.2     .07       0
  5040.5     .16       0  5170.9      .1       0    6068     .05       0
Bank Sta=4810.1,5694.9
XS Rating Curve= 0 ,0
Exp/Cntr=0.3,0.1

Type RM Length L Ch R = 1 ,71327   ,357,357,357
BEGIN DESCRIPTION:
Mapping XS bb4614bf
END DESCRIPTION:
XS GIS Cut Line= 4
      2357476.19     13244437.06      2356250.07     13242483.95
       2355034.8     13242418.85      2353328.43     13240485.45
#Sta/Elev= 30
  2188.9  175.98  3901.1  171.68  3995.4  171.45  4517.4  167.03  4597.5  165.49
  4641.3  164.72  4747.7  163.24  4757.7   163.5  4837.8  162.09  4910.5  162.35
    4948  160.93    4988  161.83  4995.1  159.22  4997.8  158.72  5001.1  159.22
  5038.1  162.26  5258.4  162.77  5298.5  162.89  5754.2  164.27  5938.3  162.93
  6030.3  162.92  6277.9   164.2  6285.5   161.8    6349  164.33  6802.4  169.88
    6866  169.74  7305.2  172.23  7447.5  172.83  7489.3  172.97  8290.7  176.52
#Mann= 19 ,-1 , 0
  2188.9     .05       0  3901.1     .16       0  3995.4      .1       0
  4517.4     .16       0  4597.5      .1       0  4641.3     .16       0
  4747.7      .1       0  4837.8     .16       0  4995.1     .07       0
  5001.1     .16       0  5038.1     .12       0  5258.4      .1       0
  5938.3      .1       0  6030.3     .16       0  6802.4      .1       0
    6866     .16       0  7305.2      .1       0  7447.5     .16       0
  7489.3      .1       0
Bank Sta=4757.7,5298.5
XS Rating Curve= 0 ,0
Exp/Cntr=0.3,0.1

Type RM Length L Ch R = 1 ,70970   ,1646,1646,1646
BEGIN DESCRIPTION:
BAYOU CREEK 98.0
END DESCRIPTION:
XS GIS Cut Line= 4
      2358083.87     13243894.57      2356371.74     13242371.15
       2355579.3     13242092.66      2353707.82     13240486.54
#Sta/Elev= 30
  2290.8  175.41  4000.2  171.26  4014.5  171.42    4022  172.54  4120.7  171.25
  4475.2  169.97  4668.6  167.07  4699.6  167.39    4926   162.6  4973.1  161.57
  4989.6  160.22  4998.6  158.12  5010.8   160.4  5035.1  161.79  5122.7  162.29
  5626.1   162.1  5654.6  159.99  5689.8  162.09    5704  161.39  5796.2  162.81
  6215.3  164.02  6633.6  169.74  6881.6  171.19  7072.6  170.83  7250.3  172.36
  7498.4  172.93  7760.7  174.84  7768.3  175.59  7782.6  174.83  7888.7  175.39
#Mann= 15 ,-1 , 0
  2204.2     .05       0  4004.4      .1       0  4487.3     .16       0
    4674      .1       0    4777     .16       0  4931.5     .12       0
  5007.4     .07       0  5013.4     .12       0  5218.1      .1       0
  5504.2     .12       0  5660.7     .16       0  6602.6      .1       0
    7284     .16       0  7460.7      .1       0  7704.6     .05       0
Bank Sta=4926,5122.7
XS Rating Curve= 0 ,0
Exp/Cntr=0.3,0.1

Type RM Length L Ch R = 1 ,69324   ,777,777,777
BEGIN DESCRIPTION:
BAYOU CREEK 97.0
END DESCRIPTION:
XS GIS Cut Line= 3
      2357493.14     13242198.12      2356166.73     13241114.77
      2354100.81     13240748.14
#Sta/Elev= 30
  2756.1  172.08  2981.7  171.67  3684.6  169.47    3742  170.57  3783.7  169.26
  4032.8  168.95  4224.5  167.25  4579.4  161.77  4640.3  162.14  4782.5  160.31
  4955.2  158.73  4985.7  156.66  4995.6  157.19  4997.7  154.65  5000.4  154.15
  5003.7  154.65    5006   158.7  5118.8  160.36  5178.6  159.51  5219.3  160.41
  5320.8  160.96  5422.4  161.09  5727.1  162.11  5960.7  166.67  6092.8  167.32
  6254.8  170.39  6313.9  170.51    6432  171.59  6458.3   172.1  6566.9  172.83
#Mann= 12 ,-1 , 0
  2756.1     .05       0  2981.7     .05       0  4640.3      .1       0
  4955.2     .12       0  4995.6     .07       0  5000.4     .12       0
  5219.3     .16       0  5320.8      .1       0  5422.4     .16       0
  6313.9      .1       0    6432     .16       0  6458.3      .1       0
Bank Sta=4782.5,5118.8
XS Rating Curve= 0 ,0
Exp/Cntr=0.3,0.1

Type RM Length L Ch R = 1 ,68547   ,543,543,543
BEGIN DESCRIPTION:
Mapping XS a592712a
END DESCRIPTION:
XS GIS Cut Line= 3
      2357527.82     13242017.53      2356041.73     13240448.11
      2354236.18     13240052.28
#Sta/Elev= 30
  2209.6  171.78  2316.3  171.66    3144   169.1  3179.2  170.65  3235.8  168.99
  3780.5  167.58  4346.2  161.02  4395.3  161.58  4405.8  160.74  4634.9  159.48
  4794.8  158.74  4856.2  156.65  4876.7  158.06  4897.2  157.79  4948.4  158.34
  4968.9  156.41  4979.1  157.77  4989.3  157.04  4996.6   153.1  4999.3   152.6
  5011.1   154.6    5020  158.09  5040.5  158.93  5196.6   159.8  5255.5  160.68
  5634.3  167.17  5654.8  168.62  5726.4  169.75  5887.8  172.81  6219.4  174.56
#Mann= 11 ,-1 , 0
  2209.6     .05       0  2316.3     .05       0  4395.3      .1       0
  4897.2     .12       0  4999.3     .07       0  5011.1     .12       0
  5255.5     .16       0  5634.3      .1       0  5654.8     .16       0
  5726.4      .1       0  5887.8     .16       0
Bank Sta=4634.9,5196.6
XS Rating Curve= 0 ,0
Exp/Cntr=0.3,0.1

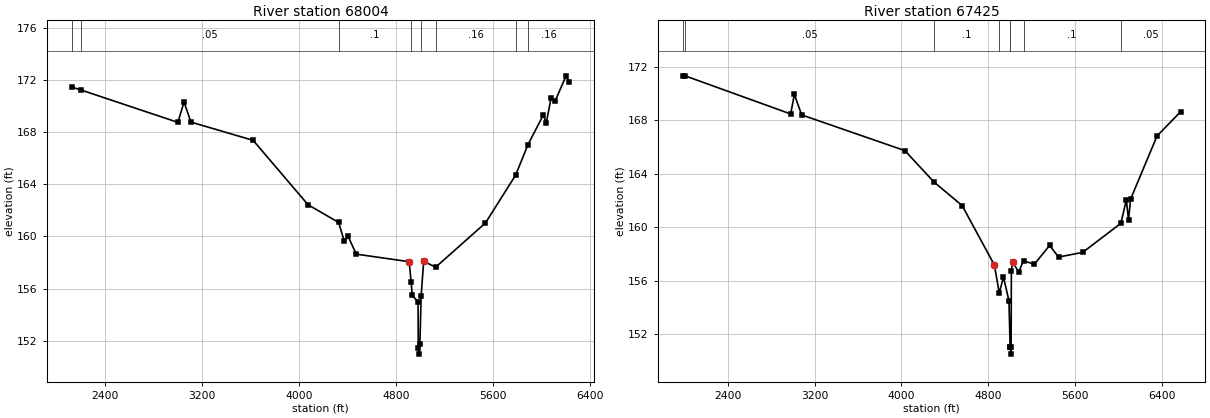
Type RM Length L Ch R = 1 ,68004   ,579,579,579
BEGIN DESCRIPTION:
BAYOU CREEK 96.0
END DESCRIPTION:
XS GIS Cut Line= 3
      2357508.33     13241794.93      2356387.87     13240125.14
      2354372.63     13239548.85
#Sta/Elev= 30
  2122.1  171.46    2201  171.23  2999.3  168.75  3050.3  170.31  3107.3  168.77
  3620.4  167.37  4073.6  162.43  4326.2  161.07  4372.3  159.63  4404.1     160
  4471.7  158.64  4908.4  158.06  4923.6  156.52    4934  155.47  4981.1  154.98
  4983.3  151.47  4986.1  150.97  4996.4  151.72  5006.8  155.46  5027.6  158.09
  5126.7  157.64  5537.2  161.03  5786.9  164.71  5888.2  167.04  6015.7  169.33
  6038.9  168.68  6078.1  170.59  6111.7  170.37  6202.9  172.32    6229  171.82
#Mann= 8 ,-1 , 0
  2122.1     .05       0    2201     .05       0  4326.2      .1       0
  4923.6     .12       0  5006.8     .12       0  5126.7     .16       0
  5786.9      .1       0  5888.2     .16       0
Bank Sta=4908.4,5027.6
XS Rating Curve= 0 ,0
Exp/Cntr=0.3,0.1

Type RM Length L Ch R = 1 ,67425   ,838,838,838
BEGIN DESCRIPTION:
Mapping XS 02c5e654
END DESCRIPTION:
XS GIS Cut Line= 4
      2357571.24     13241661.65      2356677.15     13239830.05
      2354923.67       13238962.      2354333.37     13238875.19
#Sta/Elev= 30
  1983.6   171.3  2004.3  171.35  2978.5  168.49  3012.7  169.96  3079.7  168.42
  4032.3  165.74  4300.1  163.39  4560.5  161.62    4858  157.16  4902.6  155.06
  4941.8  156.26  4992.2  154.48  5003.1  151.03    5006  150.98  5008.8  150.48
    5012  150.98  5014.6  156.75  5025.4   157.4  5081.9  156.64  5126.8  157.48
  5226.2  157.22  5367.9  158.63  5449.4  157.76  5672.6  158.11  6024.8  160.29
  6075.3  162.05  6095.5  160.52  6113.7  162.09  6358.3  166.84    6575  168.65
#Mann= 8 ,-1 , 0
  1983.6     .05       0  2004.3     .05       0  4300.1      .1       0
  4902.6     .12       0  5003.1     .07       0    5006     .12       0
  5126.8      .1       0  6024.8     .05       0
Bank Sta=4858,5025.4
XS Rating Curve= 0 ,0
Exp/Cntr=0.3,0.1