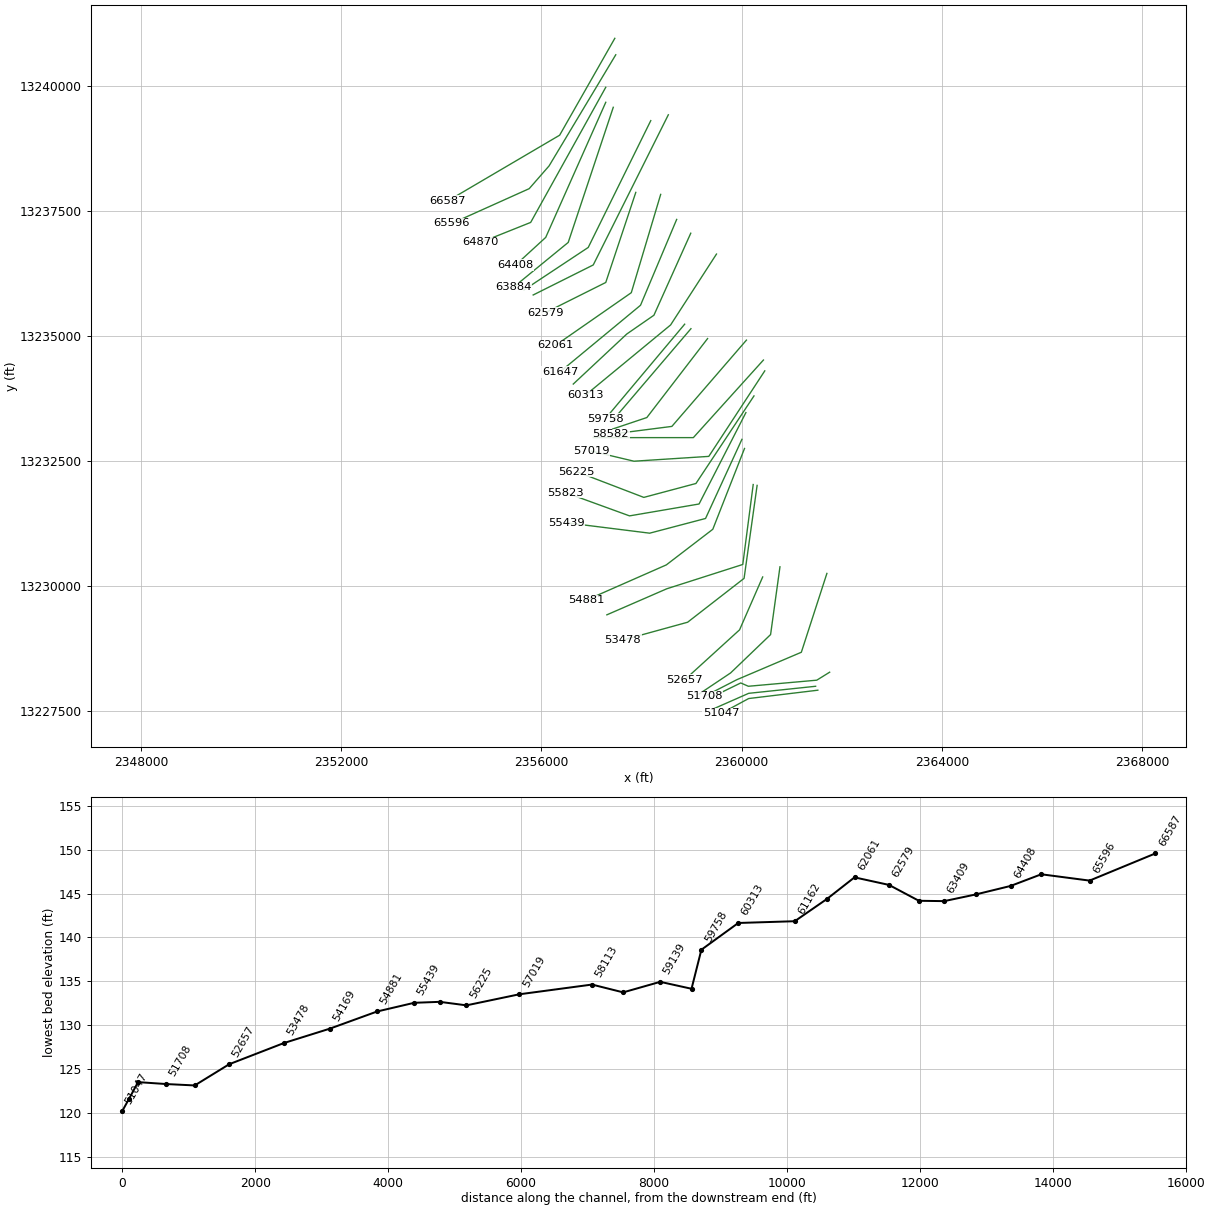
HEC-RAS study BAYOU CREEK.prj: BAYOU CREEK Base Level Engineering

--- BAYOU CREEK.g01 (geometry) --- (continued)

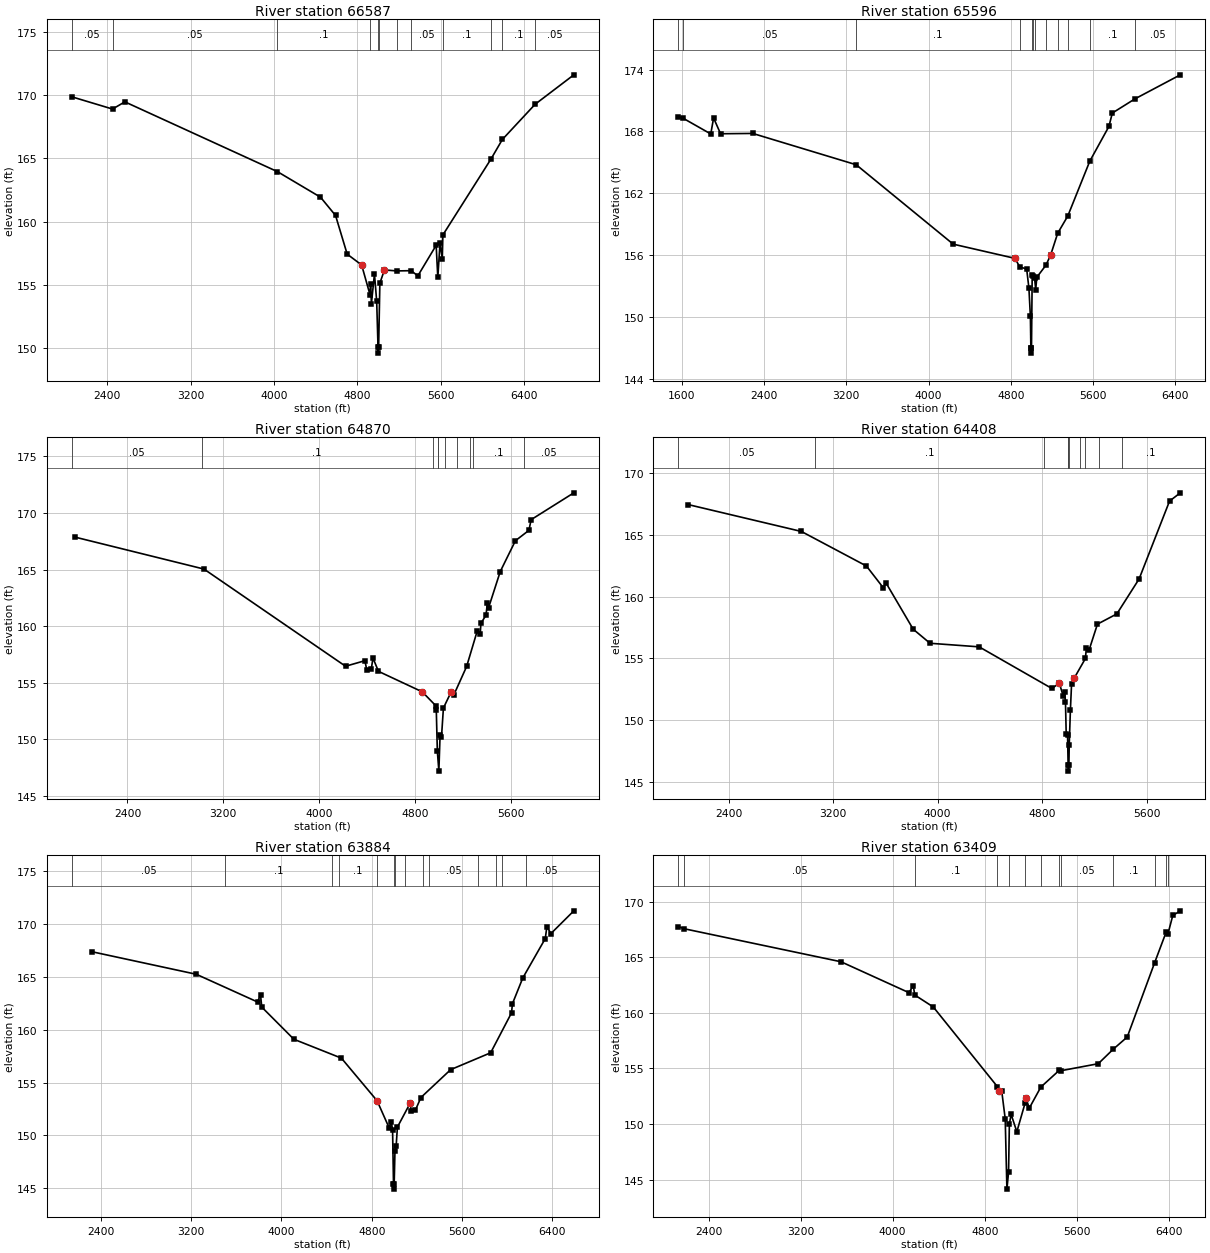
Type RM Length L Ch R = 1 ,66587   ,991,991,991
BEGIN DESCRIPTION:
Mapping XS 3d698dfe
END DESCRIPTION:
XS GIS Cut Line= 3
       2357467.1     13240949.88      2356364.65     13239014.08
      2354133.74     13237703.31
#Sta/Elev= 30
  2060.5  169.88  2451.4  168.91  2569.6  169.48  4033.5  163.95  4445.9  161.93
  4590.4  160.48  4701.8  157.42  4840.5  156.56  4920.5  154.21  4926.3  155.06
  4934.2   153.5  4963.5  155.85  4984.9  153.67  4997.6  150.08  5000.4  149.58
  5003.6  150.08  5015.3  155.12  5059.2  156.17  5176.4  156.09  5315.1  156.11
  5379.5   155.7  5555.3  158.12    5571  155.57  5592.5  158.32  5613.9  157.04
  5619.7  158.94  6082.4  164.97  6190.1   166.5  6504.6  169.29  6875.7  171.62
#Mann= 12 ,-1 , 0
  2060.5     .05       0  2451.4     .05       0  4033.5      .1       0
  4920.5     .12       0  4997.6     .07       0  5003.6     .12       0
  5176.4      .1       0  5315.1     .05       0  5619.7      .1       0
  6082.4     .05       0  6190.1      .1       0  6504.6     .05       0
Bank Sta=4840.5,5059.2
XS Rating Curve= 0 ,0
Exp/Cntr=0.3,0.1

Type RM Length L Ch R = 1 ,65596   ,726,726,726
BEGIN DESCRIPTION:
BAYOU CREEK 95.0
END DESCRIPTION:
XS GIS Cut Line= 4
      2357486.42     13240621.87      2356153.87     13238400.96
      2355757.01     13237946.37      2354214.27     13237252.85
#Sta/Elev= 30
  1564.9  169.42  1611.3  169.29  1881.4  167.76  1908.9  169.31  1976.7  167.78
  2289.6  167.81  3296.4  164.77    4240  157.06  4841.2  155.68  4887.5  154.85
  4954.9  154.65  4976.8  152.79  4991.1  150.04  4995.8  146.98  4998.5  146.48
  5001.8  146.98  5008.8   154.1  5014.2  153.96  5031.7  153.79  5042.9  152.65
  5053.6  153.85  5141.3     155  5187.3  155.98  5256.8  158.12  5354.9  159.79
  5568.8  165.11  5755.3  168.49  5788.2  169.79  6007.5  171.16  6449.8   173.5
#Mann= 12 ,-1 , 0
  1564.9     .05       0  1611.3     .05       0  3296.4      .1       0
  4887.5     .12       0  5008.8     .07       0  5014.2     .12       0
  5031.7      .1       0  5141.3     .05       0  5256.8      .1       0
  5354.9     .05       0  5568.8      .1       0  6007.5     .05       0
Bank Sta=4841.2,5187.3
XS Rating Curve= 0 ,0
Exp/Cntr=0.3,0.1

Type RM Length L Ch R = 1 ,64870   ,462,462,462
BEGIN DESCRIPTION:
BAYOU CREEK 94.0
END DESCRIPTION:
XS GIS Cut Line= 3
      2357286.41     13239971.85      2355786.41     13237271.85
      2354786.43     13236871.86
#Sta/Elev= 30
  1961.8  167.86  3038.6  165.04  4221.1  156.46  4382.8  156.95  4398.8   156.1
  4436.5  156.24  4449.9  157.19  4495.7  156.01  4861.7   154.2  4973.1  152.99
  4978.8   152.6  4987.6  148.97  5000.3   147.2  5010.4  150.38  5022.3  150.22
  5038.3  152.77  5100.9  154.15  5124.5  153.91  5232.2  156.44  5321.7  159.61
    5346  159.35  5351.4  160.25  5393.7  160.96  5405.2  162.01  5415.3  161.62
  5512.9  164.82  5639.5  167.54  5752.5  168.46  5770.7   169.4  6127.5  171.77
#Mann= 10 ,-1 , 0
  1934.8     .05       0  3019.3      .1       0  4949.8     .12       0
  4990.8     .07       0  4996.8     .12       0  5050.2     .05       0
  5154.7      .1       0  5259.2     .05       0  5283.8      .1       0
  5713.7     .05       0
Bank Sta=4861.7,5100.9
XS Rating Curve= 0 ,0
Exp/Cntr=0.3,0.1

Type RM Length L Ch R = 1 ,64408   ,524,524,524
BEGIN DESCRIPTION:
BAYOU CREEK 93.0
END DESCRIPTION:
XS GIS Cut Line= 3
      2357286.39     13239671.81      2356086.41     13236971.85
      2355486.45     13236421.89
#Sta/Elev= 30
  2089.6  167.47  2957.2  165.29  3455.2  162.49  3583.3  160.74  3605.6  161.11
  3813.1  157.37  3942.1  156.23  4318.3  155.94  4874.6  152.57  4932.5  152.99
  4962.1  151.93  4973.1  152.25    4979  151.46  4984.5   148.9    4995  148.78
  4999.2  146.37    5002  145.87  5005.2  146.37  5007.7     148  5016.8  150.84
  5025.5  152.91  5046.7  153.42  5131.8     155  5138.6  155.84  5160.2   155.7
  5223.7  157.78  5372.3  158.61  5542.5  161.44  5775.6  167.75  5858.1  168.42
#Mann= 10 ,-1 , 0
  2014.5     .05       0  3060.4      .1       0  4816.1     .12       0
    4998      .1       0  5001.6     .07       0  5007.6      .1       0
  5087.1     .05       0  5127.7      .1       0  5238.1     .05       0
  5409.7      .1       0
Bank Sta=4932.5,5046.7
XS Rating Curve= 0 ,0
Exp/Cntr=0.3,0.1

Type RM Length L Ch R = 1 ,63884   ,475,475,475
BEGIN DESCRIPTION:
BAYOU CREEK 92.0
END DESCRIPTION:
XS GIS Cut Line= 3
      2357436.42     13239571.89      2356536.41     13236871.85
      2355436.45     13235971.89
#Sta/Elev= 30
  2323.1  167.39  3245.5  165.26  3788.9  162.63  3814.7  163.33  3825.8  162.15
  4110.4   159.1  4531.5  157.31  4847.7  153.27  4953.1  150.73  4974.2  151.26
  4984.7  150.47  4992.8   145.4  4995.6   144.9  4998.8   145.4  5005.8  148.48
  5016.3  148.97  5027.4  150.78  5142.8  153.09  5148.7   152.3  5185.9  152.36
  5235.5  153.58  5498.9  156.22  5853.5  157.82  6038.7  161.61  6046.1  162.46
  6137.7   164.9  6337.3  168.64  6351.6  169.78  6386.8  169.11  6590.4  171.27
#Mann= 14 ,-1 , 0
  2142.8     .05       0  3504.1      .1       0  4449.4     .05       0
  4507.3      .1       0  4850.1     .12       0  4999.5     .07       0
  5005.5     .12       0  5091.6     .05       0  5253.4      .1       0
  5310.7     .05       0  5738.8      .1       0  5900.6     .05       0
  5952.3      .1       0  6168.3     .05       0
Bank Sta=4847.7,5142.8
XS Rating Curve= 0 ,0
Exp/Cntr=0.3,0.1

Type RM Length L Ch R = 1 ,63409   ,380,380,380
BEGIN DESCRIPTION:
BAYOU CREEK 91.0
END DESCRIPTION:
XS GIS Cut Line= 3
      2358185.81     13239305.71      2356936.41     13236771.85
      2355653.04     13235921.61
#Sta/Elev= 30
  2135.8  167.76  2186.4  167.56  3550.5  164.59  4141.4  161.81  4179.2  162.44
  4191.7   161.6  4353.2  160.52  4910.8  153.35  4925.8  153.01  4948.2  152.94
  4978.2  150.47    4993  144.14  5007.3  145.65  5014.3  149.97  5029.4  150.87
  5079.3   149.3  5151.3  151.89  5158.7  152.32  5187.3  151.42    5288  153.32
  5447.5  154.82  5462.5  154.79  5787.1  155.42  5916.8  156.72    6039  157.82
  6277.8  164.52    6377  167.25  6392.1  167.06  6434.8  168.75  6500.4  169.17
#Mann= 13 ,-1 , 0
  2135.8     .05       0  2186.4     .05       0  4191.7      .1       0
  4910.8     .12       0  5007.3     .12       0  5151.3      .1       0
    5288     .05       0  5447.5      .1       0  5462.5     .05       0
  5916.8      .1       0  6277.8     .05       0    6377      .1       0
  6392.1     .05       0
Bank Sta=4925.8,5158.7
XS Rating Curve= 0 ,0
Exp/Cntr=0.3,0.1

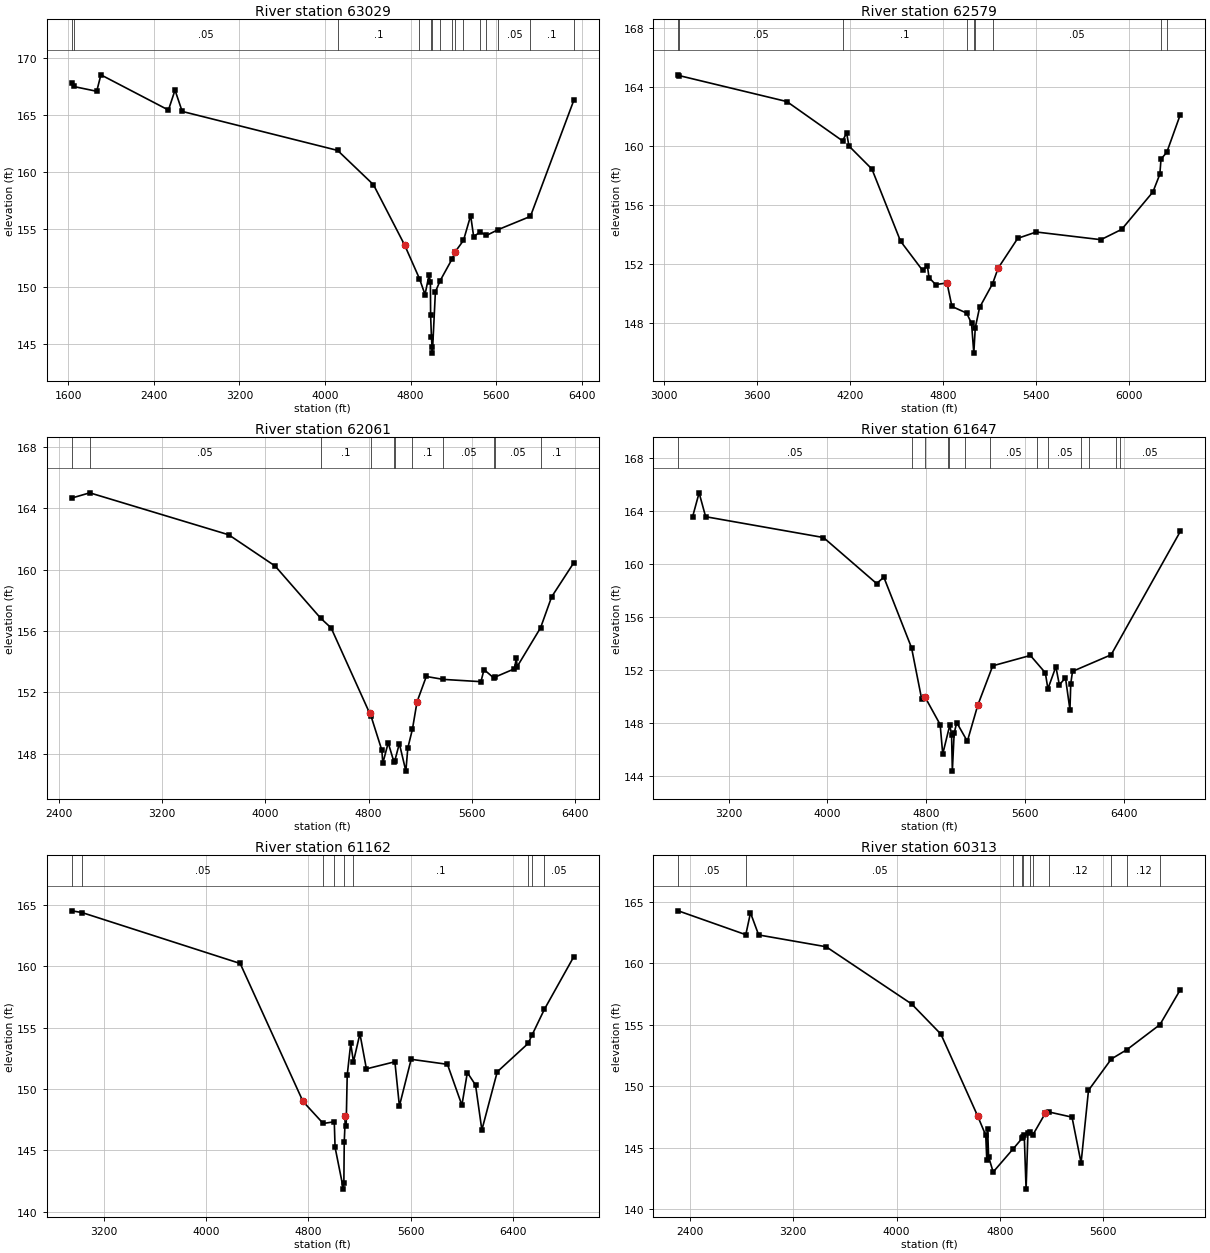
Type RM Length L Ch R = 1 ,63029   ,450,450,450
BEGIN DESCRIPTION:
BAYOU CREEK 90.0
END DESCRIPTION:
XS GIS Cut Line= 3
       2358536.4     13239421.83      2357036.41     13236421.85
      2355836.42     13235821.86
#Sta/Elev= 30
  1631.4  167.77  1648.1   167.5  1864.7  167.08  1903.8  168.52  2535.5  165.44
    2597  167.18  2664.1  165.32  4117.5  161.91  4452.9  158.91  4743.6  153.65
  4883.4  150.69  4935.2   149.3  4972.8  151.02  4985.5  150.42  4987.5  147.49
  4995.2  145.62  5001.3  144.68  5004.1  144.18  5032.3  149.55    5077  150.52
  5188.8  152.42  5218.8  153.06    5295  154.04  5362.1  156.21    5390  154.38
  5451.5  154.77  5509.5  154.47  5621.3  154.99  5921.1  156.14  6327.1   166.3
#Mann= 15 ,-1 , 0
  1631.4     .05       0  1648.1     .05       0  4117.5      .1       0
  4883.4     .12       0  4995.2     .07       0  5001.3     .12       0
    5077     .05       0  5188.8      .1       0  5218.8     .05       0
    5295      .1       0  5451.5     .05       0  5509.5      .1       0
  5621.3     .05       0  5921.1      .1       0  6327.1     .05       0
Bank Sta=4743.6,5218.8
XS Rating Curve= 0 ,0
Exp/Cntr=0.3,0.1

Type RM Length L Ch R = 1 ,62579   ,518,518,518
BEGIN DESCRIPTION:
BAYOU CREEK 89.0
END DESCRIPTION:
XS GIS Cut Line= 3
       2357886.4     13237871.82      2357286.41     13236071.85
      2356086.39     13235471.84
#Sta/Elev= 30
  3089.5  164.83  3094.7  164.78  3790.4  163.02  4149.4  160.36  4175.7  160.89
    4191  160.01  4339.1  158.45  4523.6  153.57  4665.3   151.6    4697  151.89
  4707.5   151.1  4750.2  150.63  4823.4  150.74  4855.1  149.15  4949.9   148.7
  4981.6  148.01  4996.3  145.99  5005.7  147.71  5033.6  149.08  5117.5  150.69
  5153.1  151.74  5279.6  153.76    5399  154.19  5816.2  153.67  5950.4  154.37
  6151.7   156.9  6196.4   158.1    6204  159.13  6241.1  159.58  6328.5  162.14
#Mann= 9 ,-1 , 0
  3089.5     .05       0  3094.7     .05       0  4149.4      .1       0
  4949.9     .12       0  4996.3     .07       0  5005.7     .12       0
  5117.5     .05       0    6204      .1       0  6241.1     .05       0
Bank Sta=4823.4,5153.1
XS Rating Curve= 0 ,0
Exp/Cntr=0.3,0.1

Type RM Length L Ch R = 1 ,62061   ,414,414,414
BEGIN DESCRIPTION:
BAYOU CREEK 88.0
END DESCRIPTION:
XS GIS Cut Line= 3
      2358383.73     13237831.74      2357796.52     13235867.37
      2356286.56     13234817.92
#Sta/Elev= 30
  2500.4  164.68  2639.8  165.02  3716.2  162.28  4075.7  160.24  4427.7  156.84
  4509.4   156.2  4808.3  150.62  4817.1  150.48  4902.4  148.21  4909.6  147.36
  4951.5   148.7    4996  147.45  5002.1  147.51  5037.9  148.65  5088.3  146.85
  5103.4  148.36  5139.2  149.59    5175  151.38  5246.6  153.03  5377.3  152.84
  5669.9  152.69  5693.6  153.48  5771.2  152.92  5779.2  152.99  5929.2  153.53
  5944.1  154.24  5950.2  153.67  6131.8  156.21  6217.6  158.23  6389.5  160.46
#Mann= 11 ,-1 , 0
  2500.4     .05       0  2639.8     .05       0  4427.7      .1       0
  4817.1     .12       0    4996     .07       0  5002.1     .12       0
  5139.2      .1       0  5377.3     .05       0  5771.2      .1       0
  5779.2     .05       0  6131.8      .1       0
Bank Sta=4808.3,5175
XS Rating Curve= 0 ,0
Exp/Cntr=0.3,0.1

Type RM Length L Ch R = 1 ,61647   ,485,485,485
BEGIN DESCRIPTION:
BAYOU CREEK 87.0
END DESCRIPTION:
XS GIS Cut Line= 3
      2358703.18     13237331.76      2357980.97     13235616.51
       2356371.3     13234284.37
#Sta/Elev= 30
  2907.5  163.54  2960.9  165.37  3013.8  163.57    3968     162  4398.6  158.53
  4456.9  159.01  4681.4  153.69  4763.4  149.82  4791.9  149.95  4913.1   147.9
  4933.9  145.68  4991.2  147.86  5005.6  147.11  5011.8  144.39  5026.4  147.24
  5047.2  148.05  5133.2  146.64  5217.8  149.36    5339  152.33  5643.8  153.11
  5764.9   151.8  5785.7  150.59  5850.2  152.26  5878.2   150.9  5928.1  151.42
  5964.2  149.01  5970.7  150.98    5985  151.91  6297.7  153.16    6858  162.46
#Mann= 13 ,-1 , 0
  2791.9     .05       0  4684.7      .1       0  4787.5     .12       0
  4976.4     .07       0  4982.4     .12       0  5116.8      .1       0
  5314.7     .05       0  5697.1      .1       0  5787.9     .05       0
  6055.8      .1       0  6121.5     .05       0  6335.5      .1       0
  6370.9     .05       0
#XS Ineff= 2 , 0
                         5627.84          152.77
Permanent Ineff=
       F       F
Bank Sta=4791.9,5217.8
XS Rating Curve= 0 ,0
Exp/Cntr=0.3,0.1

Type RM Length L Ch R = 1 ,61162   ,849,849,849
BEGIN DESCRIPTION:
Mapping XS 35b8e076
END DESCRIPTION:
XS GIS Cut Line= 4
      2358984.62     13237056.11       2358248.5      13235417.2
      2357706.83      13235042.2      2356637.37     13234042.19
#Sta/Elev= 30
  2952.1  164.53  3031.7  164.39  4266.8  160.24  4756.9     149  4915.1   147.2
  5001.5  147.34  5007.6  145.26  5072.9  141.85  5076.2  142.35  5079.3  145.72
    5088  147.79  5094.1  146.97  5102.4  151.13  5129.9  153.72    5151  152.23
  5201.6  154.52  5252.2  151.65  5474.6  152.23  5509.8  148.62  5601.6  152.43
  5884.9  152.02  5997.8  148.69  6040.3  151.35  6104.3  150.33  6153.6  146.67
  6273.8  151.41  6514.6  153.72  6546.8  154.44  6641.6   156.5  6871.7   160.8
#Mann= 9 ,-1 , 0
  2952.1     .05       0  3031.7     .05       0  4915.1      .1       0
  5001.5      .1       0  5076.2     .16       0    5151      .1       0
  6514.6     .05       0  6546.8      .1       0  6641.6     .05       0
#XS Ineff= 2 , 0
                         5204.55          154.27
Permanent Ineff=
       F       F
Bank Sta=4756.9,5088
XS Rating Curve= 0 ,0
Exp/Cntr=0.3,0.1

Type RM Length L Ch R = 1 ,60313   ,555,555,555
BEGIN DESCRIPTION:
Mapping XS 37de2c33
END DESCRIPTION:
XS GIS Cut Line= 3
      2359498.48      13236639.4      2358581.83     13235222.76
      2356881.57     13233820.91
#Sta/Elev= 30
  2308.1  164.27  2831.7  162.33    2868  164.11  2931.3  162.31  3454.3  161.35
  4116.8   156.7  4343.5  154.25  4627.5  147.62  4691.3  146.02  4699.2  144.04
  4705.7  146.57  4713.5  144.27  4748.7  143.04  4905.1  144.94  4975.4  145.81
  4983.3  145.89  4989.7  146.01  5003.8  141.65  5018.4  146.25  5032.8  146.33
  5053.6  146.01    5154  147.84  5181.3  147.92  5359.8   147.5  5430.1  143.78
  5487.5  149.68  5664.7  152.23  5785.9  152.99  6041.2  155.02  6199.1  157.86
#Mann= 11 ,-1 , 0
  2308.1     .05       0  2831.7     .05       0  4905.1      .1       0
  4975.4     .07       0  4983.3      .1       0  5032.8     .12       0
  5053.6     .16       0  5181.3     .12       0  5664.7      .1       0
  5785.9     .12       0  6041.2      .1       0
Bank Sta=4627.5,5154
XS Rating Curve= 0 ,0
Exp/Cntr=0.3,0.1

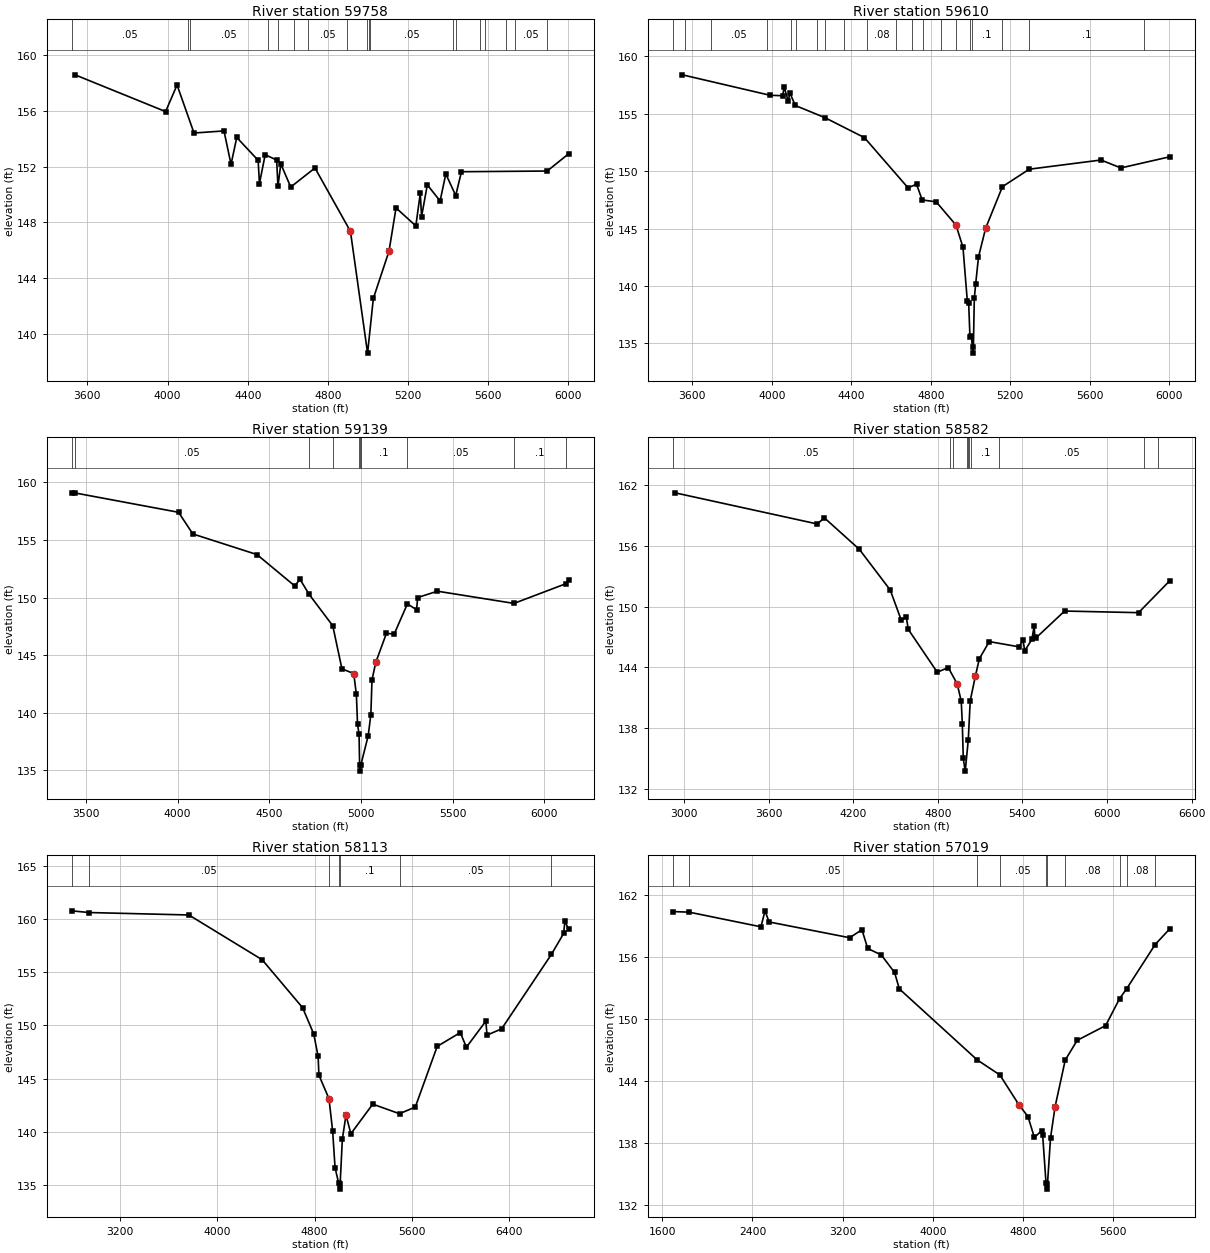
Type RM Length L Ch R = 1 ,59758   ,148,148,148
BEGIN DESCRIPTION:
Mapping XS bf22cd92
END DESCRIPTION:
XS GIS Cut Line= 2
      2358863.06     13235238.36      2357279.51     13233351.12
#Sta/Elev= 30
  3538.2  158.59  3990.2  155.95  4047.4  157.86    4132  154.41  4281.6  154.56
  4316.7  152.16  4345.4  154.09    4452  152.45  4458.5  150.78  4487.2  152.85
  4544.4  152.47  4550.9  150.59  4565.2  152.19  4614.7  150.53  4735.6   151.9
  4912.6  147.35  4998.2   138.6    5027  142.53  5105.1  145.92  5140.2  149.03
  5239.1  147.74  5261.2  150.08  5267.7  148.41  5296.3  150.69  5360.1  149.53
  5388.7  151.47  5438.1  149.92  5466.7  151.63  5894.5  151.68  6001.8  152.92
#Mann= 18 ,-1 , 0
  3520.7     .05       0  4103.8     .08       0  4110.6     .05       0
  4500.5     .08       0  4553.4     .05       0  4632.7     .08       0
    4701     .05       0  4897.1     .08       0  4996.2     .05       0
  5003.1     .04       0  5009.1     .05       0    5426     .08       0
    5439     .05       0  5558.2     .08       0  5586.6     .05       0
  5690.4     .08       0  5734.1     .05       0  5894.5     .08       0
Bank Sta=4912.6,5105.1
XS Rating Curve= 0 ,0
Exp/Cntr=0.3,0.1

Type RM Length L Ch R = 1 ,59610   ,471,471,471
BEGIN DESCRIPTION:
BAYOU CREEK 86.0
END DESCRIPTION:
XS GIS Cut Line= 2
      2358988.39     13235148.28      2357395.48     13233281.92
#Sta/Elev= 30
  3549.7  158.39  3990.9  156.61  4054.5  156.57  4062.2  157.32  4083.1  156.08
  4090.6  156.83  4118.2  155.72  4267.5  154.66  4466.3  152.92  4685.9  148.55
  4728.7  148.86  4757.2  147.49  4827.5  147.33  4927.4   145.3  4962.5  143.37
  4984.5  138.66  4991.1  138.55  4997.7  135.55  5005.4  135.63  5011.7  134.15
  5014.9  134.65  5019.6  138.93  5026.2  140.13  5040.5  142.51  5076.6  145.03
  5161.3  148.65  5296.3  150.17  5657.5  150.97  5757.4  150.28  6003.4  151.25
#Mann= 20 ,-1 , 0
  3500.4     .05       0  3561.8     .05       0    3695     .05       0
  3975.1     .08       0  4094.7     .05       0  4121.3     .08       0
  4227.9     .05       0  4267.5     .08       0  4361.1     .05       0
  4477.8     .08       0  4627.5      .1       0  4706.2     .08       0
  4760.8      .1       0  4852.4     .08       0  4928.7      .1       0
  5000.2     .07       0  5006.2      .1       0  5160.4      .1       0
  5293.6      .1       0    5876     .08       0
Bank Sta=4927.4,5076.6
XS Rating Curve= 0 ,0
Exp/Cntr=0.3,0.1

Type RM Length L Ch R = 1 ,59139   ,557,557,557
BEGIN DESCRIPTION:
Mapping XS 03a69981
END DESCRIPTION:
XS GIS Cut Line= 3
      2359320.86     13234951.24       2358107.3     13233373.08
      2357424.97      13233143.9
#Sta/Elev= 30
  3421.2   159.1  3440.1  159.09  4004.7  157.41  4082.7  155.53  4432.4  153.74
  4638.1  151.02  4667.1  151.59  4716.9  150.28  4845.6  147.56  4895.5  143.82
  4959.8  143.41  4974.3  141.61  4980.6     139  4988.8  138.17  4992.1  135.44
  4994.9  134.94  4998.1  135.44  5038.7  138.01  5053.2  139.84  5059.5  142.87
  5080.3  144.39  5138.3  146.91  5180.2  146.83  5252.5  149.46  5302.4  148.95
  5308.7  150.01  5416.3  150.56  5833.5   149.5  6118.3  151.22  6131.8  151.56
#Mann= 10 ,-1 , 0
  3421.2     .05       0  3440.1     .05       0  4716.9      .1       0
  4845.6     .05       0  4988.8      .1       0  4992.1     .07       0
  4998.1      .1       0  5252.5     .05       0  5833.5      .1       0
  6118.3     .05       0
Bank Sta=4959.8,5080.3
XS Rating Curve= 0 ,0
Exp/Cntr=0.3,0.1

Type RM Length L Ch R = 1 ,58582   ,469,469,469
BEGIN DESCRIPTION:
BAYOU CREEK 85.0
END DESCRIPTION:
XS GIS Cut Line= 3
      2360096.87     13234919.94       2358607.3     13233195.99
      2357388.51     13233039.74
#Sta/Elev= 30
  2937.3  161.26  3945.8  158.18  3995.5  158.79  4243.4  155.68  4462.8  151.65
  4540.7  148.68  4576.9  148.95  4591.1  147.75  4796.3  143.52  4874.2  143.98
  4937.8  142.36  4966.3  140.65    4974  138.41  4980.6  135.01  4994.6  133.74
  5016.3  136.85  5029.9   140.7  5066.1  143.11  5094.6  144.85  5164.9  146.55
  5376.5  146.03  5403.6  146.72  5416.8  145.64  5467.3  146.77  5483.2  148.08
  5488.3  146.99  5497.5  146.93  5699.1  149.57  6223.4  149.41  6444.4  152.56
#Mann= 10 ,-1 , 0
  2919.6     .05       0  4886.5      .1       0    4905     .05       0
    5007     .03       0    5013     .05       0  5021.6     .12       0
  5038.9      .1       0  5235.1     .05       0  6261.4      .1       0
    6360     .05       0
Bank Sta=4937.8,5066.1
XS Rating Curve= 0 ,0
Exp/Cntr=0.3,0.1

Type RM Length L Ch R = 1 ,58113   ,1094,1094,1094
BEGIN DESCRIPTION:
BAYOU CREEK 84.0
END DESCRIPTION:
XS GIS Cut Line= 3
      2360436.43     13234521.88      2359036.41     13232971.85
       2357036.4     13232971.85
#Sta/Elev= 30
  2800.3  160.76  2944.3   160.6  3765.6  160.37  4367.9  156.17  4700.4  151.67
  4792.4   149.2  4828.2  147.09    4835  145.33  4917.7  143.12  4947.7   140.1
  4967.7  136.64  4997.7  135.17  5004.7  135.13  5007.4  134.63  5027.7  139.33
  5057.7  141.58  5097.7  139.83  5277.7  142.61  5497.7  141.71  5627.7  142.34
  5807.7  148.03  5997.7  149.33  6047.7  147.95  6207.7   150.4  6217.7  149.09
  6337.7  149.68  6747.7  156.68  6847.7  158.64  6857.7  159.79    6889  159.02
#Mann= 7 ,-1 , 0
  2800.3     .05       0  2944.3     .05       0  4917.7      .1       0
  4997.7     .07       0  5004.7      .1       0  5497.7     .05       0
  6747.7      .1       0
Bank Sta=4917.7,5057.7
XS Rating Curve= 0 ,0
Exp/Cntr=0.3,0.1

Type RM Length L Ch R = 1 ,57019   ,794,794,794
BEGIN DESCRIPTION:
BAYOU CREEK 83.0
END DESCRIPTION:
XS GIS Cut Line= 4
      2360463.21     13234305.39      2359345.14     13232597.04
       2357850.4     13232500.66       2357004.9     13232701.19
#Sta/Elev= 30
  1691.3  160.44  1838.6  160.38  2474.9  158.96  2511.1  160.51  2547.3  159.43
  3261.9   157.9  3370.5  158.68  3421.7  156.86  3542.3  156.23    3660  154.53
  3702.1  152.94  4391.8  146.06  4593.9  144.59  4762.6   141.7  4842.7  140.56
  4899.7  138.53    4963  139.18    4973  138.77  5003.1  134.09  5010.1  134.02
  5012.8  133.52  5043.1  138.51  5083.2  141.51  5173.4  146.04  5279.6  147.95
  5531.6  149.38    5655  151.99  5717.2  152.94  5970.6  157.24  6099.8  158.76
#Mann= 10 ,-1 , 0
  1691.3     .05       0  1838.6     .05       0  4391.8      .1       0
  4593.9     .05       0  5003.1     .07       0  5010.1      .1       0
  5173.4     .08       0    5655      .1       0  5717.2     .08       0
  5970.6     .05       0
Bank Sta=4762.6,5083.2
XS Rating Curve= 0 ,0
Exp/Cntr=0.3,0.1

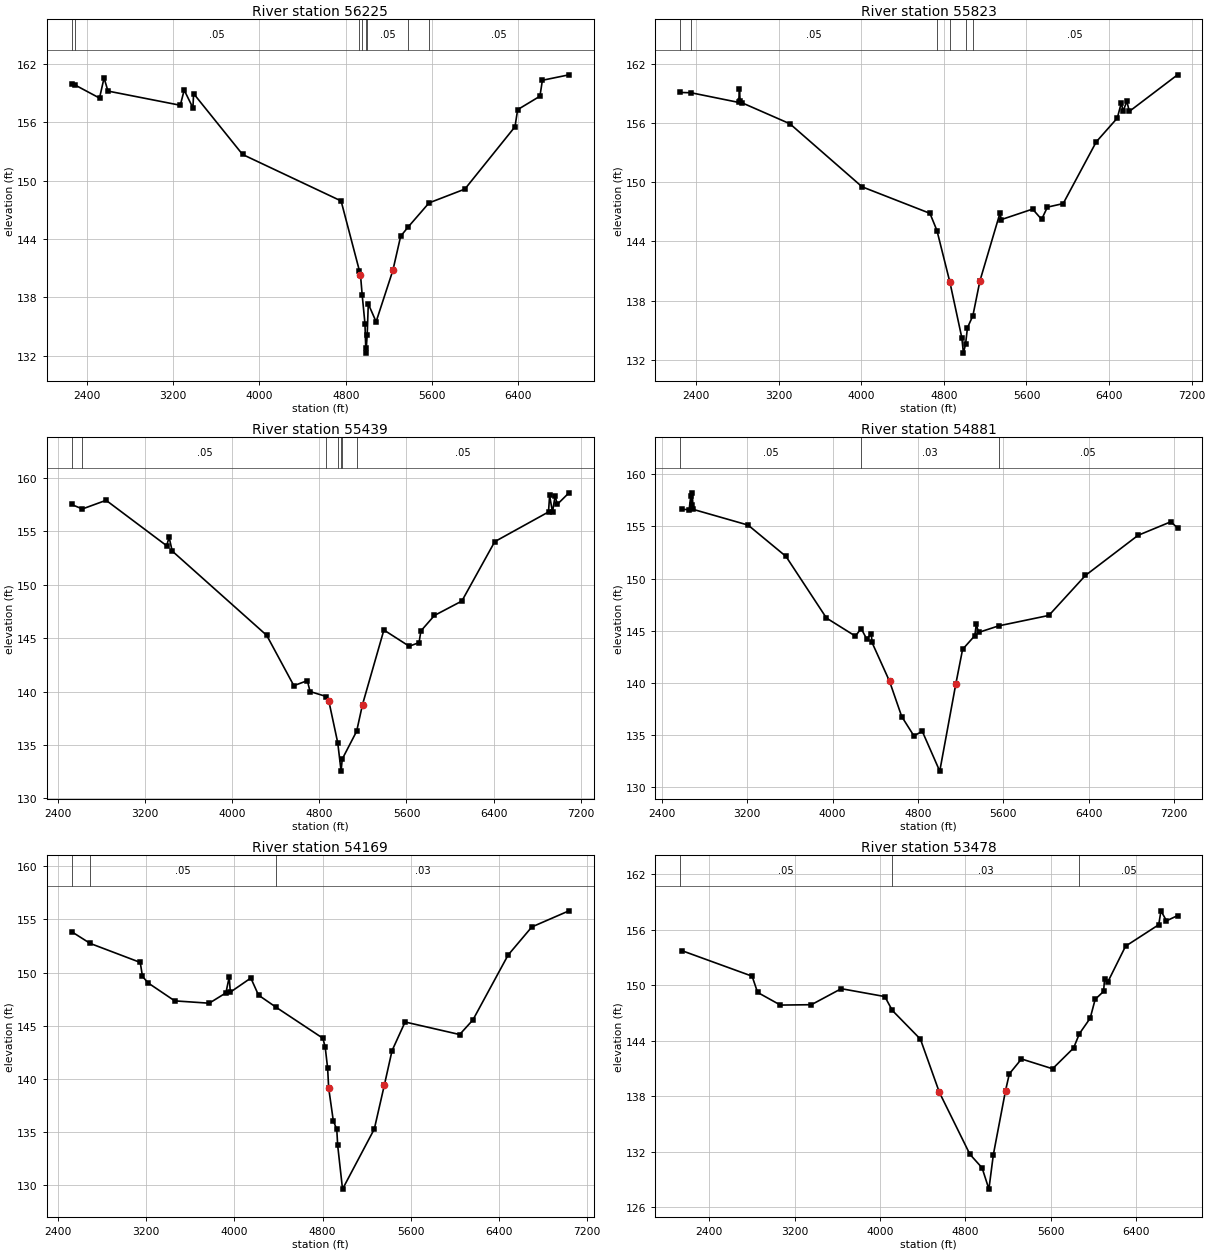
Type RM Length L Ch R = 1 ,56225   ,402,402,402
BEGIN DESCRIPTION:
Mapping XS c25342e1
END DESCRIPTION:
XS GIS Cut Line= 4
      2360247.93     13233805.38       2359088.2     13232055.37
      2358046.53     13231777.59      2356706.24     13232291.48
#Sta/Elev= 30
  2257.4   159.9  2285.3  159.86  2516.9  158.49    2559  160.56  2595.1  159.21
  3265.9  157.75    3302  159.31  3383.2  157.48  3389.2  158.95  3843.5  152.69
  4757.1  147.91  4926.5  140.75  4936.9   140.3  4952.5  138.26  4978.3   135.3
  4987.2  132.26  4990.4  132.76    4999   134.1  5009.3  137.32  5081.8  135.49
    5237  140.76  5309.4  144.28  5378.1  145.22  5572.8  147.71  5904.8  149.13
  6369.6  155.54  6394.3   157.3    6601  158.68  6623.8  160.32  6870.3  160.88
#Mann= 8 ,-1 , 0
  2257.4     .05       0  2285.3     .05       0  4926.5     .07       0
  4952.5     .05       0  4990.4     .03       0    4999     .05       0
  5378.1     .08       0  5572.8     .05       0
Bank Sta=4936.9,5237
XS Rating Curve= 0 ,0
Exp/Cntr=0.3,0.1

Type RM Length L Ch R = 1 ,55823   ,384,384,384
BEGIN DESCRIPTION:
BAYOU CREEK 82.0
END DESCRIPTION:
XS GIS Cut Line= 4
      2360086.39     13233471.83       2359150.7     13231645.65
      2357761.34     13231408.24      2356486.45     13231871.84
#Sta/Elev= 30
  2244.6  159.12  2351.3  159.09    2812  158.11  2820.2  159.47  2825.8   158.3
  2842.4  158.08  3308.6  155.94  4007.8  149.54  4664.8  146.85  4732.7   145.1
    4858  139.86  4973.2  134.24  4989.2  132.66  5009.7  133.57  5028.2  135.24
  5080.7  136.46  5148.5  139.98  5344.5  146.92  5354.6  146.21    5659  147.28
  5746.5  146.24  5802.4  147.48  5955.3  147.84  6275.9  154.11  6479.4  156.52
  6518.6  158.08  6535.2  157.21  6571.8  158.22  6596.4   157.2  7062.6  160.91
#Mann= 6 ,-1 , 0
  2244.6     .05       0  2351.3     .05       0  4732.7      .1       0
    4858     .07       0  5009.7     .07       0  5080.7     .05       0
Bank Sta=4858,5148.5
XS Rating Curve= 0 ,0
Exp/Cntr=0.3,0.1

Type RM Length L Ch R = 1 ,55439   ,558,558,558
BEGIN DESCRIPTION:
BAYOU CREEK 81.0
END DESCRIPTION:
XS GIS Cut Line= 4
      2360006.59     13232937.29      2359280.21     13231356.34
      2358163.73     13231062.54       2356501.2     13231270.45
#Sta/Elev= 30
  2523.1  157.51  2622.6  157.09  2840.5   157.9  3396.6  153.65  3419.5  154.43
    3448  153.15    4316  145.26  4565.4  140.55  4689.5  141.02  4714.1     140
    4865  139.53  4885.9  139.15  4968.7   135.2  4999.4  132.55    5010  133.68
  5142.2  136.28  5196.1  138.78  5392.6  145.76    5625  144.24  5715.7  144.58
  5732.5  145.67  5856.8  147.12  6108.8  148.47  6411.1  154.03  6904.9  156.81
    6915  158.35  6941.6  156.79  6965.4  158.32  6985.6  157.52  7092.9   158.6
#Mann= 7 ,-1 , 0
  2523.1     .05       0  2622.6     .05       0    4865      .1       0
  4968.7     .07       0  4999.4     .07       0    5010     .07       0
  5142.2     .05       0
Bank Sta=4885.9,5196.1
XS Rating Curve= 0 ,0
Exp/Cntr=0.3,0.1

Type RM Length L Ch R = 1 ,54881   ,712,712,712
BEGIN DESCRIPTION:
Mapping XS d68b1fea
END DESCRIPTION:
XS GIS Cut Line= 4
      2360058.69     13232755.04        2359425.     13231140.44
      2358496.19     13230428.63        2356899.     13229725.52
#Sta/Elev= 30
  2584.7  156.63  2654.2   156.6  2668.7  157.86  2678.6  157.01    2684  158.21
  2690.2  156.63  3207.2  155.12  3562.4  152.12    3942  146.22  4213.1  144.49
  4267.3  145.21  4318.4  144.24    4363  144.68  4369.3  143.88  4533.4  140.17
  4647.7  136.79  4761.9  134.94  4840.8  135.37  5004.6  131.56  5154.5  139.87
  5218.8  143.22  5333.1  144.53  5347.6  145.62  5368.4  144.84  5557.3  145.47
    6028  146.47  6371.1   150.3  6864.4  154.14  7172.5  155.44  7234.5  154.84
#Mann= 3 ,-1 , 0
    2569     .05       0  4267.3     .03       0  5557.3     .05       0
Bank Sta=4533.4,5154.5
XS Rating Curve= 0 ,0
Exp/Cntr=0.3,0.1

Type RM Length L Ch R = 1 ,54169   ,691,691,691
BEGIN DESCRIPTION:
Mapping XS 848f163b
END DESCRIPTION:
XS GIS Cut Line= 4
       2360232.3     13232034.54      2360023.96     13230437.31
      2358504.87      13229951.2      2357308.67     13229431.12
#Sta/Elev= 30
  2523.7  153.85  2692.8  152.74  3146.6  150.95  3166.8  149.63  3219.3  149.01
  3459.2  147.33  3771.9  147.11  3923.1  148.08  3953.4  149.57  3963.5  148.15
  4149.3  149.48  4218.9  147.87  4379.6  146.72  4802.5  143.81  4823.5  142.98
  4845.6  140.99    4855  139.13    4897  136.04  4928.5  135.23  4936.8  133.71
  4980.7   129.6  5268.8  135.26    5359  139.36  5429.6  142.64  5547.9  145.34
  6042.6  144.16  6162.5  145.53  6482.2  151.65  6696.8  154.29  7033.8  155.81
#Mann= 3 ,-1 , 0
  2523.7     .05       0  2692.8     .05       0  4379.6     .03       0
Bank Sta=4855,5359
XS Rating Curve= 0 ,0
Exp/Cntr=0.3,0.1

Type RM Length L Ch R = 1 ,53478   ,821,821,821
BEGIN DESCRIPTION:
BAYOU CREEK 80.0
END DESCRIPTION:
XS GIS Cut Line= 4
      2360310.42      13232017.2        2360050.     13230159.54
       2358921.9     13229283.19      2357628.09     13228926.89
#Sta/Elev= 30
  2144.3  153.71    2801  150.96  2852.3  149.21  3066.4  147.84  3356.9  147.88
  3637.2  149.61  4045.5  148.76  4116.1  147.26  4379.4  144.16  4557.7   138.4
  4843.7  131.72  4957.8  130.26  5021.8  127.96  5063.6  131.69  5177.7   138.6
  5213.3  140.41  5327.3  142.02  5618.9  140.96    5816   143.2  5870.5  144.75
  5971.6  146.42  6018.4  148.46  6097.6  149.32  6106.4  150.67  6137.5  150.35
  6303.5   154.2  6614.7  156.52  6635.4  158.02  6687.3  156.94  6790.6   157.5
#Mann= 3 ,-1 , 0
  2125.4     .05       0  4116.1     .03       0  5870.5     .05       0
Bank Sta=4557.7,5177.7
XS Rating Curve= 0 ,0
Exp/Cntr=0.3,0.1

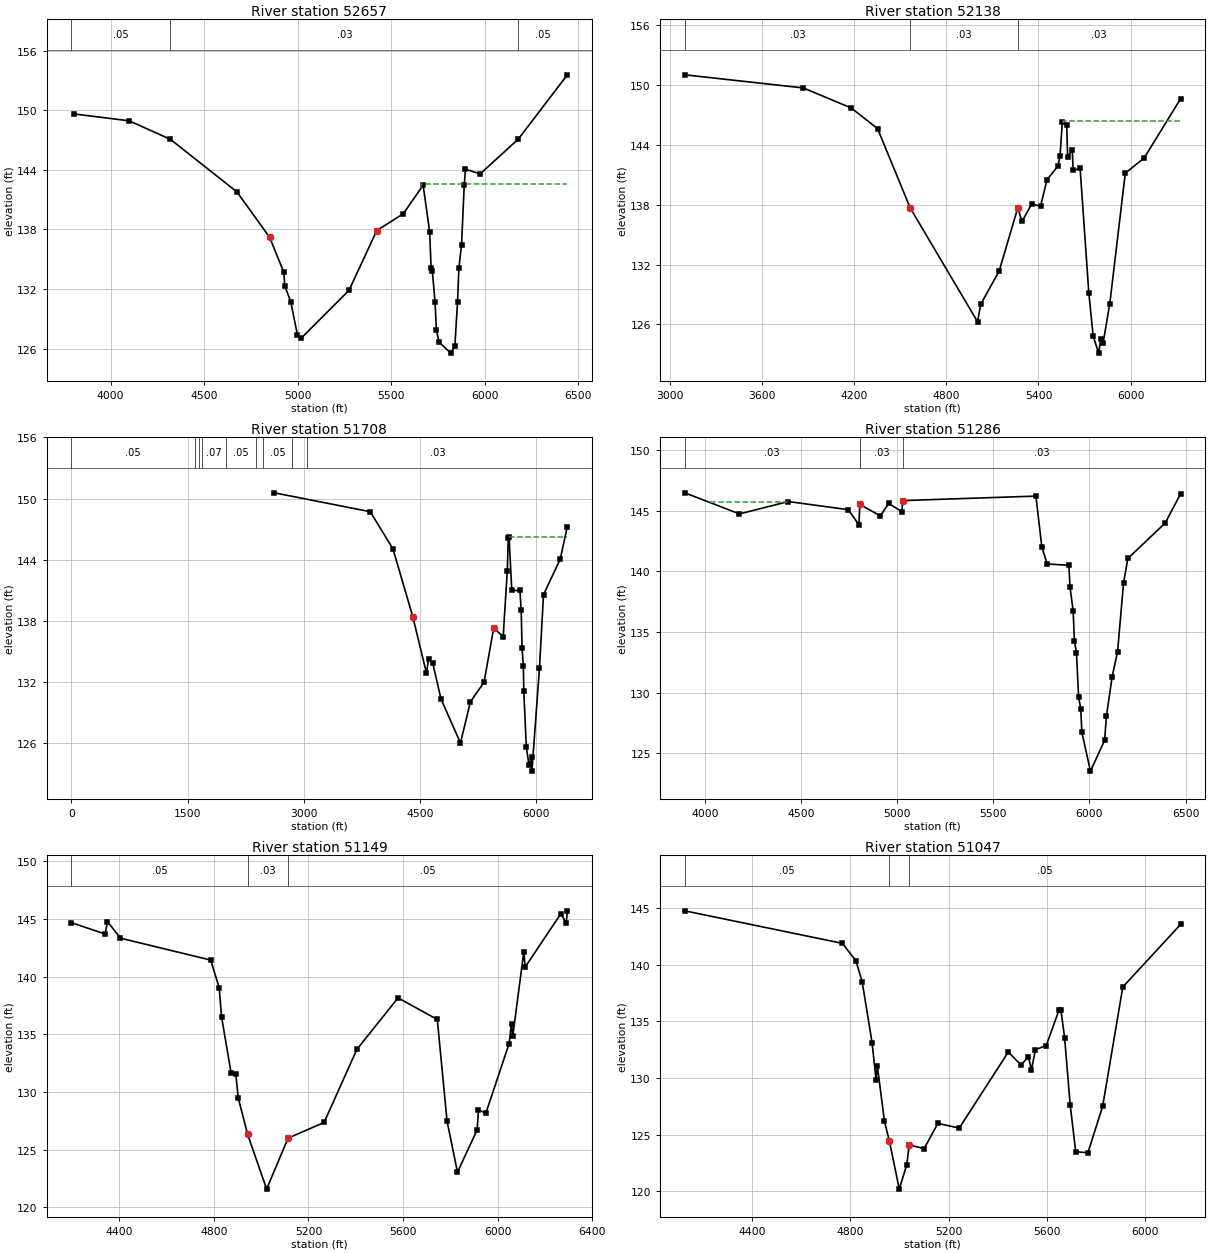
Type RM Length L Ch R = 1 ,52657   ,519,519,519
BEGIN DESCRIPTION:
BAYOU CREEK 79.0
END DESCRIPTION:
XS GIS Cut Line= 3
      2360421.86     13230187.99      2359959.97     13229131.41
      2358862.93     13228132.52
#Sta/Elev= 30
  3805.7  149.63  4099.6  148.94  4319.9  147.08    4676  141.78  4850.7  137.21
  4926.3   133.7  4931.8  132.31  4963.7  130.73  4999.2  127.39  5020.2  127.07
  5274.9  131.87  5423.5  137.89  5565.4  139.58  5671.5  142.46  5706.6  137.73
  5714.1   134.1  5720.8   133.8    5735  130.73  5742.5  127.88  5756.6  126.65
  5819.9  125.55  5841.1  126.26  5855.3  130.66  5862.7  134.13  5876.9  136.47
  5891.1  142.43  5897.9  144.07  5976.2  143.59    6181  147.11  6442.5  153.57
#Mann= 3 ,-1 , 0
  3791.1     .05       0  4319.9     .03       0    6181     .05       0
#XS Ineff= 2 , 0
                         5659.66          142.57
Permanent Ineff=
       F       F
Bank Sta=4850.7,5423.5
XS Rating Curve= 0 ,0
Exp/Cntr=0.3,0.1

Type RM Length L Ch R = 1 ,52138   ,430,430,430
BEGIN DESCRIPTION:
BAYOU CREEK 79.0
END DESCRIPTION:
XS GIS Cut Line= 4
      2360767.01      13230390.4      2360579.52     13229036.27
      2359780.98     13228270.13       2359154.5     13227850.89
#Sta/Elev= 30
  3097.8  151.01  3868.6   149.7  4181.6  147.69  4353.2  145.61  4564.6  137.69
  5003.3  126.28  5024.4  128.02  5144.8  131.38  5264.9  137.66  5293.2  136.32
  5356.8  138.09  5413.4  137.83  5455.8  140.51  5526.6  141.86  5540.7   142.9
  5554.9  146.24  5583.9  146.01  5589.9  142.77  5619.9   143.5  5625.9  141.44
    5671  141.65    5728  129.13  5755.9  124.86  5791.7  123.13  5806.1  124.59
  5821.1  124.17  5864.2  128.09  5965.2  141.16  6088.3  142.68  6325.3  148.62
#Mann= 3 , 0 , 0
  3097.8     .03       0  4564.6     .03       0  5264.9     .03       0
#XS Ineff= 2 , 0
                          5562.2          146.37
Permanent Ineff=
       F       F
Bank Sta=4564.6,5264.9
XS Rating Curve= 0 ,0
Exp/Cntr=0.3,0.1

Type RM Length L Ch R = 1 ,51708   ,422,422,422
XS GIS Cut Line= 4
      2361704.51     13230258.46      2361194.13     13228683.29
      2359903.59     13228134.28      2359257.71     13227801.57
#Sta/Elev= 30
  2622.8  150.56  3860.5  148.71  4153.7  145.08  4410.3  138.44  4586.6  132.91
  4615.7  134.29  4668.4  133.88  4774.6  130.37  5026.5  126.05  5155.6  130.09
  5331.9  132.01  5455.6   137.3  5578.8  136.48  5631.9  142.93    5644  146.09
  5654.8  146.21  5689.8  140.99    5795  140.99  5811.4  139.05  5822.8  135.33
  5839.4  133.57  5845.1   131.1  5878.1  125.63  5912.6  123.86  5944.6  124.67
    5950  123.29  6047.6   133.4  6099.7  140.58  6315.8  144.06  6407.6  147.26
#Mann= 9 ,-1 , 0
       0     .05       01592.823     .07       01652.554    .033       0
1682.467     .07       01991.819     .05       02390.983      .1       0
2480.794     .05       02850.021      .1       03049.603     .03       0
#XS Ineff= 2 , 0
                         5654.56          146.21
Permanent Ineff=
       F       F
Bank Sta=4410.3,5455.6
XS Rating Curve= 0 ,0
Exp/Cntr=0.3,0.1

Type RM Length L Ch R = 1 ,51286   ,137,137,137
XS GIS Cut Line= 5
      2361759.72     13228285.02      2361502.73     13228125.29
      2360135.49     13228003.69      2359983.45     13228070.04
      2359321.18     13227746.47
#Sta/Elev= 30
  3895.9  146.49  4180.5  144.75  4434.4  145.77  4745.6   145.1  4801.3  143.86
  4806.3  145.53  4912.9  144.59  4956.5  145.61  5024.6  144.94  5029.6  145.85
  5721.7  146.22  5752.3  142.04  5780.4  140.62    5893   140.5  5899.2  138.69
  5915.5  136.71  5921.5  134.28  5932.5   133.3  5943.7   129.6  5954.9  128.67
  5960.5  126.72  6005.3  123.51  6078.7  126.05  6088.4  128.05  6118.2  131.32
  6146.3  133.37  6177.4  139.05  6199.7  141.07    6394     144  6474.1  146.41
#Mann= 3 , 0 , 0
  3895.9     .03       0  4806.3     .03       0  5029.6     .03       0
#XS Ineff= 2 ,-1
 4030.93  4435.1  145.76 5593.29 6482.84145.4363
Permanent Ineff=
       F       F
Bank Sta=4806.3,5029.6
XS Rating Curve= 0 ,0
Exp/Cntr=0.3,0.1

Type RM Length L Ch R = 1 ,51149   ,102,102,102
XS GIS Cut Line= 3
      2361479.35     13228003.48      2360142.02     13227862.66
      2359452.23     13227558.51
#Sta/Elev= 30
  4196.9  144.69  4339.3  143.71  4349.4  144.79  4404.1  143.35  4786.1  141.45
    4822  139.06    4832  136.55  4872.2   131.7  4892.4  131.59  4902.4  129.52
  4942.6  126.33  5022.8  121.59  5113.6  126.01  5266.1  127.37  5405.2  133.72
  5579.1  138.17  5745.2   136.3  5786.4   127.5  5830.5  123.06  5913.9  126.73
  5919.4  128.46  5950.7  128.18  6049.1  134.21  6059.3  135.94  6064.8  134.89
  6111.4  142.18  6116.9  140.84  6267.8  145.46  6291.1  144.67  6295.5  145.72
#Mann= 3 , 0 , 0
  4196.9     .05       0  4942.6     .03       0  5113.6     .05       0
#XS Ineff= 2 , 0
                         5681.82          137.01
Permanent Ineff=
       F       F
Bank Sta=4942.6,5113.6
XS Rating Curve= 0 ,0
Exp/Cntr=0.3,0.1

Type RM Length L Ch R = 1 ,51047   ,885,885,885
XS GIS Cut Line= 3
      2361523.97     13227925.16      2360142.02     13227758.49
      2359592.44     13227462.05
#Sta/Elev= 30
    4127  144.75  4767.9  141.88    4823  140.34  4848.4   138.5  4888.7  133.12
  4905.1  129.82  4910.1  131.07  4939.1  126.17  4959.2  124.43  4999.3  120.19
  5029.7  122.33  5039.8   124.1  5100.3  123.76  5156.2  125.99  5243.3  125.58
  5442.7  132.29  5494.5  131.14  5524.2  131.86  5536.9  130.74  5553.1   132.5
  5596.9  132.86  5648.8  135.99  5656.9  135.96  5671.6  133.57  5694.3  127.63
  5716.9  123.49  5766.4   123.4  5826.4   127.5  5908.3  138.03  6143.4  143.55
#Mann= 3 , 0 , 0
    4127     .05       0  4959.2     .03       0  5039.8     .05       0
#XS Ineff= 2 , 0
                         5650.57          135.96
Permanent Ineff=
       F       F
Bank Sta=4959.2,5039.8
XS Rating Curve= 0 ,0
Exp/Cntr=0.3,0.1