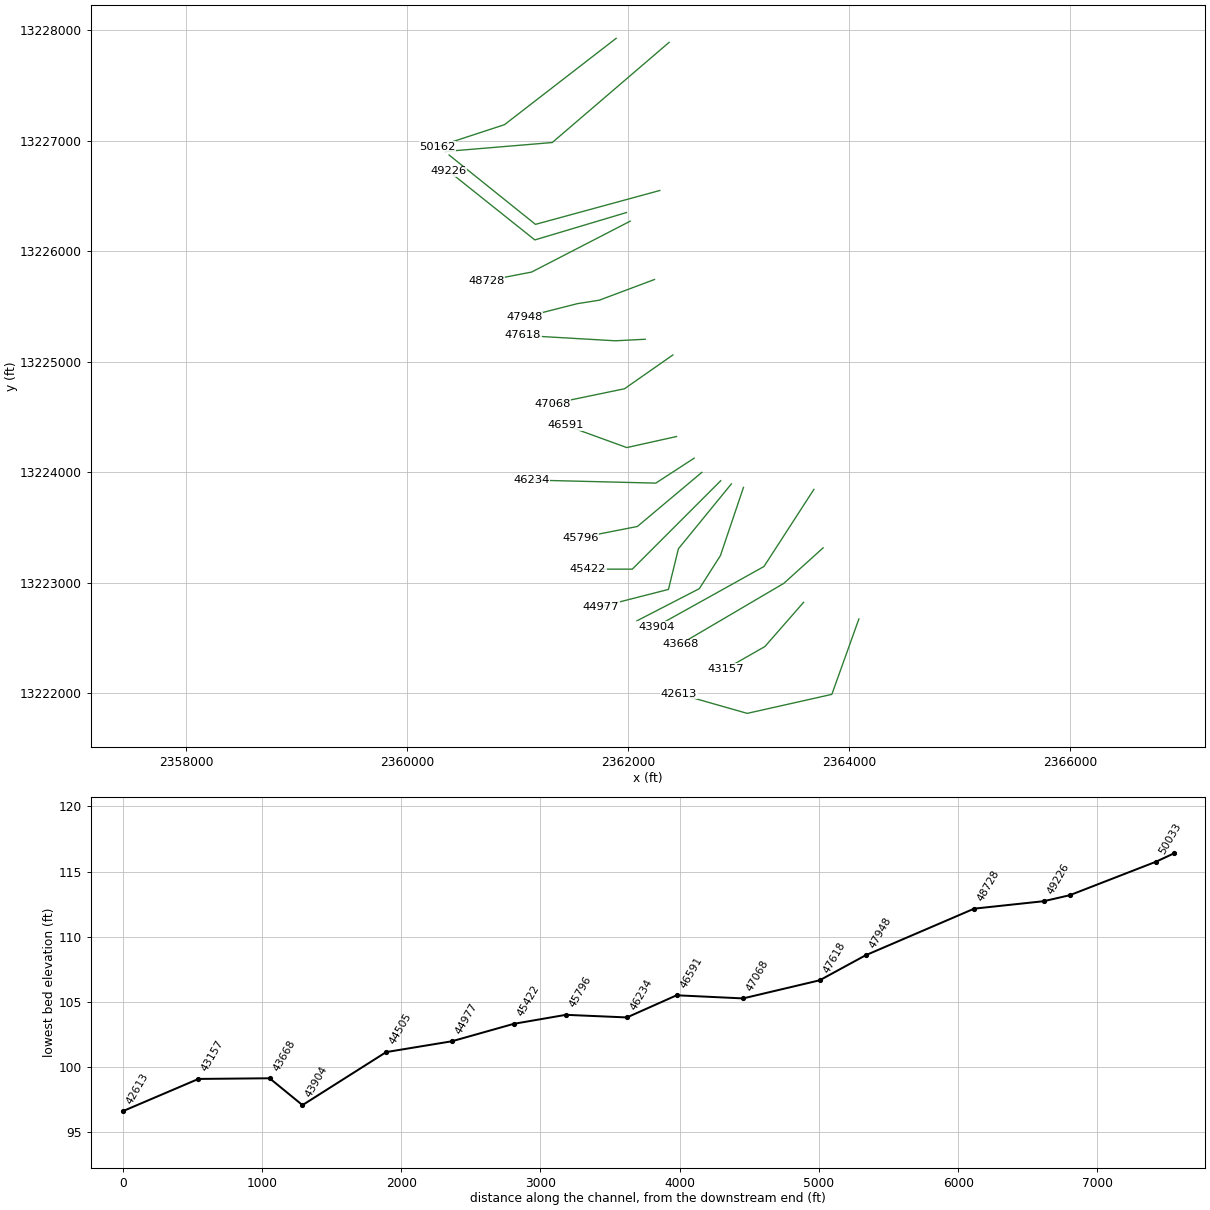
HEC-RAS study BAYOU CREEK.prj: BAYOU CREEK Base Level Engineering

--- BAYOU CREEK.g01 (geometry) --- (continued)

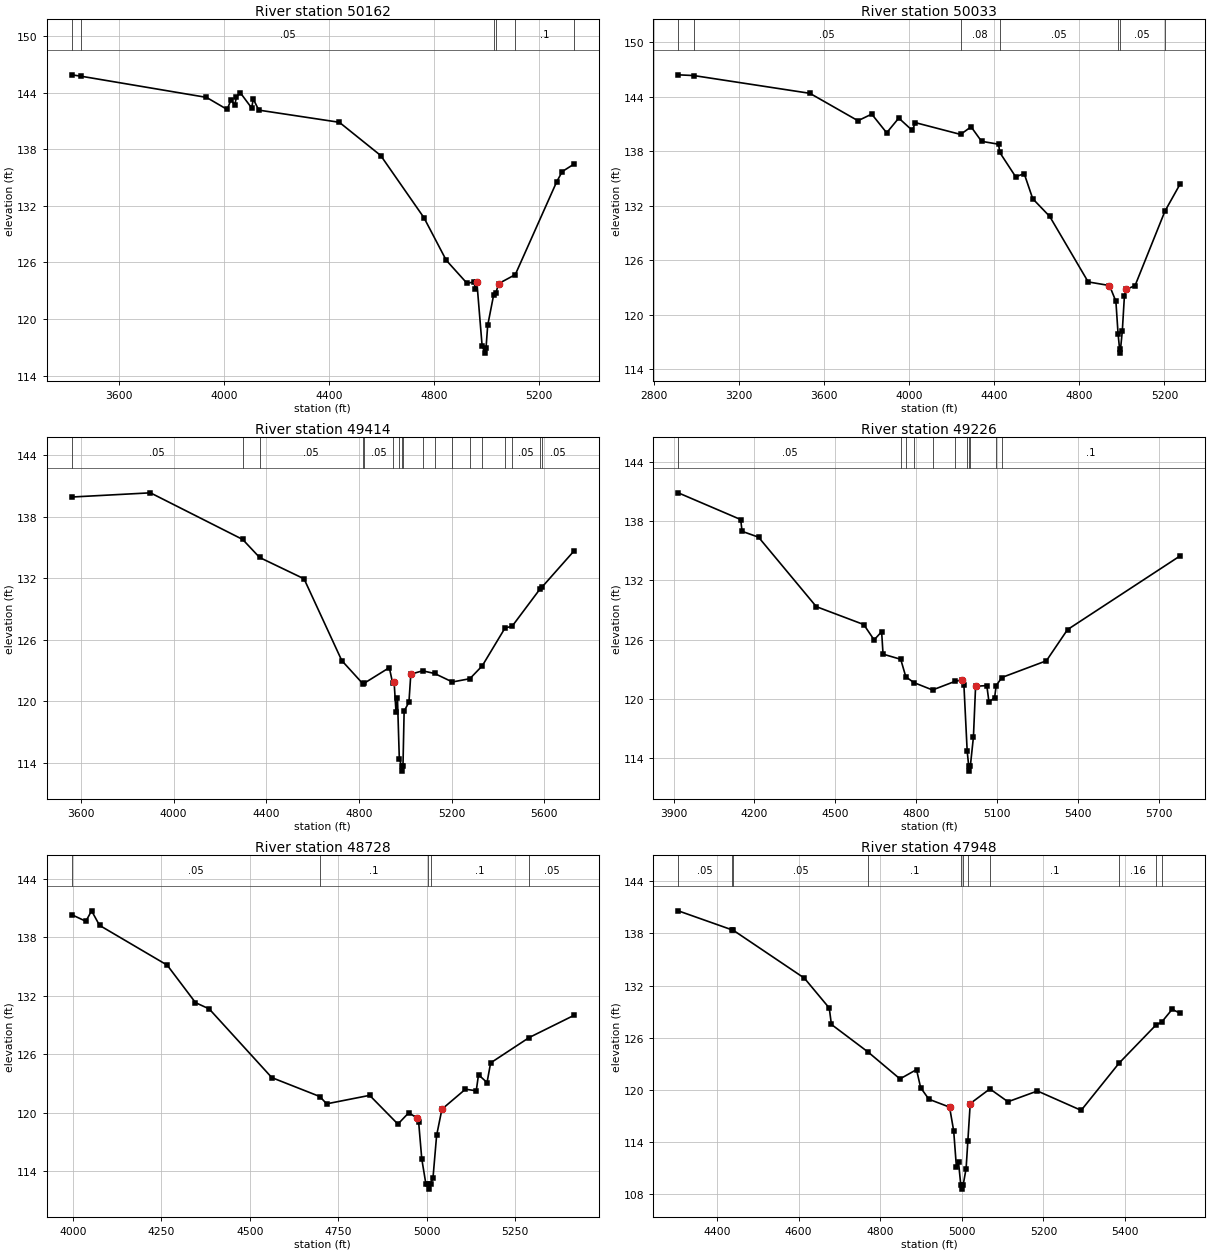
Type RM Length L Ch R = 1 ,50162   ,129,129,129
BEGIN DESCRIPTION:
BAYOU CREEK 75.0
END DESCRIPTION:
XS GIS Cut Line= 3
      2361890.29     13227924.63      2360879.87     13227143.37
      2360275.69     13226945.45
#Sta/Elev= 30
  3420.1  145.88  3456.1  145.73  3933.4  143.49  4012.2  142.21  4026.7  143.23
  4041.1  142.67  4047.5  143.54    4062  143.99  4105.4  142.37  4111.8  143.31
  4132.6  142.14  4439.6  140.85  4597.2  137.33    4762  130.74  4846.9  126.23
  4926.4  123.78  4952.1  123.94  4958.3  123.22  4963.6  123.92  4983.7  117.12
  4995.1  116.39  4998.4  116.89  5004.8  119.32  5027.2  122.51  5036.3   122.8
  5046.8  123.76    5110  124.71  5267.8  134.55  5288.9  135.63  5333.1  136.41
#Mann= 6 ,-1 , 0
  3420.1     .05       0  3456.1     .05       0  5027.2     .03       0
  5036.3     .05       0    5110      .1       0  5333.1     .05       0
Bank Sta=4963.6,5046.8
XS Rating Curve= 0 ,0
Exp/Cntr=0.3,0.1

Type RM Length L Ch R = 1 ,50033   ,619,619,619
BEGIN DESCRIPTION:
BAYOU CREEK 74.0
END DESCRIPTION:
XS GIS Cut Line= 3
      2362369.47     13227888.18      2361312.16     13226981.91
      2360345.71     13226900.96
#Sta/Elev= 30
  2912.5  146.43  2985.5  146.35  3532.1  144.39  3758.2  141.37  3822.9   142.1
  3893.2  140.04  3950.2  141.66  4013.9   140.3  4028.2  141.16  4241.1  139.86
  4290.5   140.7  4339.6   139.1  4419.9  138.78  4425.2  137.88  4500.2  135.19
  4540.3  135.54  4580.5  132.77  4660.4  130.82  4841.4   123.6  4941.7   123.2
  4971.8  121.46  4981.9  117.91  4988.9  116.25  4991.7  115.75  5001.9  118.16
    5012   122.1  5020.8  122.77  5062.1   123.2  5202.6   131.4  5274.9  134.43
#Mann= 7 ,-1 , 0
  2912.5     .05       0  2985.5     .05       0  4241.1     .08       0
  4425.2     .05       0  4981.9     .03       0  4988.9     .05       0
  5202.6      .1       0
Bank Sta=4941.7,5020.8
XS Rating Curve= 0 ,0
Exp/Cntr=0.3,0.1

Type RM Length L Ch R = 1 ,49414   ,188,188,188
BEGIN DESCRIPTION:
BAYOU CREEK 73.0
END DESCRIPTION:
XS GIS Cut Line= 3
      2362285.39     13226548.02      2361160.39      13226241.4
      2360378.94     13226868.82
#Sta/Elev= 30
    3560  139.93  3899.6  140.34  4298.1  135.79  4371.2  134.03    4563  131.95
    4726  123.97    4817  121.71  4822.3  121.75  4931.3  123.28  4945.9  121.75
  4952.1  121.86  4960.1  118.97  4966.5  120.28  4974.5  114.39  4984.3  113.68
  4987.1  113.18  4990.3  113.68  4995.3  119.04  5016.1  119.91  5024.1  122.64
  5074.8  122.97  5126.8  122.71  5203.7  121.88  5279.1   122.2  5332.5  123.45
  5431.3  127.16  5461.4  127.31  5583.6     131  5590.3  131.13  5728.2  134.65
#Mann= 18 ,-1 , 0
    3560     .05       0  4298.1      .1       0  4371.2     .05       0
    4817     .08       0  4822.3     .05       0  4945.9     .08       0
  4974.5     .05       0  4984.3     .04       0  4990.3     .05       0
  5074.8     .08       0  5126.8      .1       0  5203.7     .08       0
  5279.1      .1       0  5332.5     .05       0  5431.3      .1       0
  5461.4     .05       0  5583.6      .1       0  5590.3     .05       0
Bank Sta=4952.1,5024.1
XS Rating Curve= 0 ,0
Exp/Cntr=0.3,0.1

Type RM Length L Ch R = 1 ,49226   ,498,498,498
BEGIN DESCRIPTION:
BAYOU CREEK 72.0
END DESCRIPTION:
XS GIS Cut Line= 3
      2361983.64      13226348.5      2361154.63     13226100.62
      2360375.41     13226722.45
#Sta/Elev= 30
  3917.4  140.84    4149  138.14  4154.2  136.95  4215.2  136.36  4429.5  129.34
  4605.5  127.53  4643.9  125.98  4671.8  126.81    4677  124.54  4742.6  124.02
  4761.5  122.25  4791.1  121.67  4860.5  120.92  4943.9  121.79  4970.6  121.94
    4977   121.4  4989.1  114.74  4994.8  113.22  4997.6  112.72  5000.8  113.22
  5012.3  116.18  5020.3   121.3  5061.9  121.36  5069.9  119.72  5090.7  120.13
  5096.7  121.36  5117.6  122.18  5282.9  123.87  5361.3  127.02  5779.6  134.48
#Mann= 11 ,-1 , 0
  3917.4     .05       0  4742.6     .08       0  4761.5      .1       0
  4791.1     .08       0  4860.5      .1       0  4943.9     .08       0
  4989.1      .1       0  4994.8     .07       0  5000.8      .1       0
  5096.7     .08       0  5117.6      .1       0
Bank Sta=4970.6,5020.3
XS Rating Curve= 0 ,0
Exp/Cntr=0.3,0.1

Type RM Length L Ch R = 1 ,48728   ,780,780,780
BEGIN DESCRIPTION:
BAYOU CREEK 71.0
END DESCRIPTION:
XS GIS Cut Line= 3
      2362017.54     13226270.39      2361125.63     13225810.05
      2360716.63     13225730.86
#Sta/Elev= 30
  3996.3   140.3  4036.1  139.63  4052.4   140.7  4074.8  139.21  4266.2  135.13
  4346.3  131.28    4385  130.64  4562.2  123.59  4697.9  121.65  4717.3   120.9
    4839  121.77  4918.9  118.82  4949.7  119.99  4971.9  119.47  4977.5  119.06
  4986.4  115.25    4998  112.69  5005.1  112.65  5007.8  112.15  5011.1  112.65
  5018.2  113.32  5028.4  117.66  5043.4  120.35  5109.9   122.4  5140.5  122.24
  5146.9  123.89    5171  123.08  5181.2   125.1  5290.2   127.7  5416.6  129.97
#Mann= 5 ,-1 , 0
  3996.3     .05       0  4697.9      .1       0  5005.1     .07       0
  5011.1      .1       0  5290.2     .05       0
Bank Sta=4971.9,5043.4
XS Rating Curve= 0 ,0
Exp/Cntr=0.3,0.1

Type RM Length L Ch R = 1 ,47948   ,330,330,330
BEGIN DESCRIPTION:
Mapping XS 084fd843
END DESCRIPTION:
XS GIS Cut Line= 4
      2362237.12     13225742.59       2361737.5     13225555.23
      2361539.59     13225523.98      2361058.34     13225401.72
#Sta/Elev= 30
  4304.9  140.61  4435.5  138.44  4438.6  138.41    4614  132.86    4675  129.42
  4680.3  127.53  4770.8  124.33  4848.4  121.26  4888.9  122.33    4899  120.25
  4919.2  118.92  4969.9  118.01    4980  115.27  4986.7  111.09  4991.8  111.69
  4997.3  109.07    5000  108.57  5003.3  109.07  5010.4  110.93  5014.7  114.12
  5020.5  118.42  5068.7  120.11    5113  118.63  5185.2  119.87  5292.4  117.64
  5385.4  123.08  5475.6  127.46  5489.7   127.8  5515.4  129.27  5535.4  128.81
#Mann= 11 ,-1 , 0
  4304.9     .05       0  4435.5      .1       0  4438.6     .05       0
  4770.8      .1       0  4997.3     .07       0  5003.3      .1       0
  5014.7     .16       0  5068.7      .1       0  5385.4     .16       0
  5475.6      .1       0  5489.7     .16       0
Bank Sta=4969.9,5020.5
XS Rating Curve= 0 ,0
Exp/Cntr=0.3,0.1

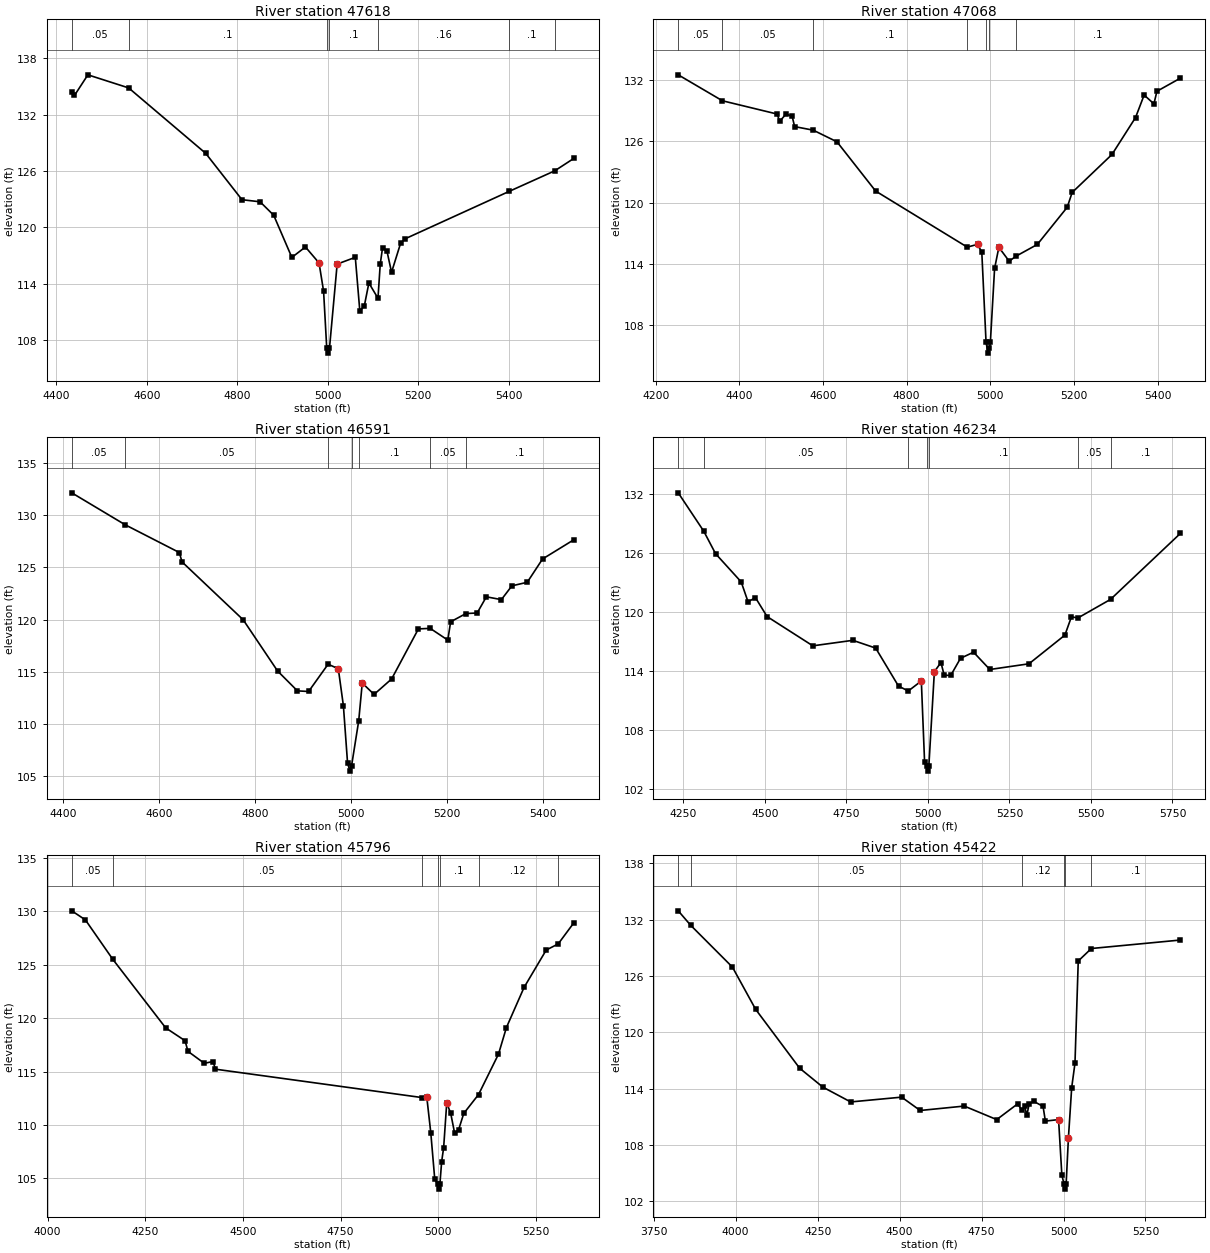
Type RM Length L Ch R = 1 ,47618   ,550,550,550
BEGIN DESCRIPTION:
BAYOU CREEK 70.0
END DESCRIPTION:
XS GIS Cut Line= 3
      2362153.26     13225201.93      2361882.47     13225188.04
      2361045.63     13225236.66
#Sta/Elev= 30
  4434.4  134.43  4440.4  134.03    4470  136.22  4560.1  134.83  4730.3  127.88
  4810.5  122.95  4850.5  122.73  4880.6   121.3  4920.7  116.82  4950.7  117.93
  4980.8  116.23  4990.8  113.24  4997.8  107.15  5000.5  106.65  5003.8  107.15
  5020.8  116.11  5060.9  116.83  5070.9  111.12  5080.9  111.69  5090.9   114.1
    5111  112.48    5116  116.11  5121.1  117.84    5131  117.46    5141  115.24
  5161.1  118.34  5171.1   118.8  5401.5  123.85  5501.6  126.02  5543.8  127.34
#Mann= 7 ,-1 , 0
  4434.4     .05       0  4560.1      .1       0  4997.8     .07       0
  5003.8      .1       0    5111     .16       0  5401.5      .1       0
  5501.6     .16       0
Bank Sta=4980.8,5020.8
XS Rating Curve= 0 ,0
Exp/Cntr=0.3,0.1

Type RM Length L Ch R = 1 ,47068   ,477,477,477
BEGIN DESCRIPTION:
Mapping XS 5f63e91e
END DESCRIPTION:
XS GIS Cut Line= 3
      2362403.27     13225059.55       2361965.8     13224754.02
        2361313.     13224618.59
#Sta/Elev= 30
  4253.9  132.51  4359.5  129.97  4490.3  128.67  4496.4  127.95  4511.3  128.66
  4526.1  128.46  4532.2  127.44  4576.7  127.09  4633.4  125.95  4725.8  121.13
  4944.8  115.64  4969.4  115.91  4979.6  115.16  4989.8  106.31  4994.7  105.26
    4998  105.76  5000.1  106.31  5010.2  113.55  5020.4  115.62  5045.1  114.26
  5061.3  114.75  5112.3   115.9  5183.8  119.54  5195.6  120.99  5290.8  124.71
  5347.2  128.33  5367.7  130.53  5391.1  129.67  5398.3   130.9  5454.2  132.18
#Mann= 7 ,-1 , 0
  4253.9     .05       0  4359.5     .05       0  4576.7      .1       0
  4944.8     .16       0  4989.8     .07       0    4998     .16       0
  5061.3      .1       0
Bank Sta=4969.4,5020.4
XS Rating Curve= 0 ,0
Exp/Cntr=0.3,0.1

Type RM Length L Ch R = 1 ,46591   ,357,357,357
BEGIN DESCRIPTION:
BAYOU CREEK 69.0
END DESCRIPTION:
XS GIS Cut Line= 3
      2362436.43     13224321.86      2361986.41     13224221.85
      2361436.44     13224421.84
#Sta/Elev= 30
  4418.6  132.13    4530  129.07  4642.6  126.42  4648.4  125.52  4775.8  119.98
  4847.5  115.08  4888.8  113.18  4912.1  113.12  4952.7  115.73    4974   115.3
  4984.6  111.76  4993.3  106.26  4998.4   105.5  5001.6     106  5016.5  110.31
  5023.9  113.93  5048.5  112.84  5085.1  114.32  5140.9  119.11  5165.5  119.16
  5202.1  118.04  5208.1  119.79    5240  120.58  5263.3  120.63  5282.5  122.18
  5313.8  121.91  5335.7  123.23  5367.7  123.57  5399.6   125.8  5464.8  127.64
#Mann= 7 ,-1 , 0
  4418.6     .05       0    4530     .05       0  4952.7      .1       0
  5001.6     .07       0  5016.5      .1       0  5165.5     .05       0
    5240      .1       0
Bank Sta=4974,5023.9
XS Rating Curve= 0 ,0
Exp/Cntr=0.3,0.1

Type RM Length L Ch R = 1 ,46234   ,438,438,438
BEGIN DESCRIPTION:
BAYOU CREEK 68.0
END DESCRIPTION:
XS GIS Cut Line= 3
      2362596.15     13224125.97      2362248.93     13223900.28
      2361123.89     13223928.06
#Sta/Elev= 30
  4234.5  132.14  4312.8  128.23    4349  125.94  4427.5  123.07  4448.6  121.04
  4471.2  121.47  4506.9  119.54  4647.2  116.56  4769.9  117.12  4839.9  116.33
  4909.9  112.46  4939.9  111.96  4979.9  112.98  4989.9   104.7  4996.9   104.3
  4999.7   103.8  5002.9   104.3  5019.9  113.93    5040  114.86    5050  113.57
    5070  113.54    5100  115.29    5140  115.91    5190  114.15    5310  114.73
  5420.1  117.65  5440.1  119.51  5460.1   119.4  5560.1  121.29    5774     128
#Mann= 7 ,-1 , 0
  4234.5     .05       0  4312.8     .05       0  4939.9      .1       0
  4996.9     .07       0  5002.9      .1       0  5460.1     .05       0
  5560.1      .1       0
Bank Sta=4979.9,5019.9
XS Rating Curve= 0 ,0
Exp/Cntr=0.3,0.1

Type RM Length L Ch R = 1 ,45796   ,374,374,374
BEGIN DESCRIPTION:
Mapping XS 23a1bdb3
END DESCRIPTION:
XS GIS Cut Line= 3
      2362665.59      13223997.5      2362082.27     13223507.92
      2361568.39     13223407.23
#Sta/Elev= 30
  4061.7  130.06  4096.6  129.21  4166.9  125.51  4302.1   119.1  4351.6   117.9
  4359.2   116.9    4401  115.78  4423.1  115.95  4429.6  115.23    4957  112.58
  4970.5  112.61  4980.7  109.28  4990.9  104.91  4998.1   104.5  5000.9     104
  5004.1   104.5  5008.5  106.57  5013.6  107.88  5021.5  112.06  5031.7   111.1
  5041.9  109.21  5052.1  109.58  5065.1  111.09    5103  112.86    5154  116.64
  5174.3  119.13  5219.5  122.89  5276.2  126.39  5306.8  126.96  5346.9  128.94
#Mann= 7 ,-1 , 0
  4061.7     .05       0  4166.9     .05       0    4957      .1       0
  4998.1     .07       0  5004.1      .1       0    5103     .12       0
  5306.8      .1       0
Bank Sta=4970.5,5021.5
XS Rating Curve= 0 ,0
Exp/Cntr=0.3,0.1

Type RM Length L Ch R = 1 ,45422   ,445,445,445
BEGIN DESCRIPTION:
BAYOU CREEK 67.0
END DESCRIPTION:
XS GIS Cut Line= 3
      2362836.42     13223921.86      2362036.41     13223121.85
      2361636.39     13223121.85
#Sta/Elev= 30
  3824.8  132.93  3862.8  131.39  3990.1  126.94  4060.8  122.45  4195.1  116.18
  4265.8  114.17  4350.7  112.59  4506.2   113.1  4562.8  111.68  4697.2  112.15
  4796.2  110.71  4859.8  112.38  4873.9  111.69    4881  112.17  4888.1  111.17
  4895.2  112.39  4909.3  112.65  4937.6  112.11  4944.6  110.55  4984.9  110.71
  4994.9   104.8  5001.9  103.81  5004.6  103.31  5007.9  103.81  5014.9  108.75
  5024.9  114.12  5034.9  116.71  5044.9  127.59  5084.9  128.92  5356.2  129.82
#Mann= 6 ,-1 , 0
  3824.8     .05       0  3862.8     .05       0  4873.9     .12       0
  5001.9     .07       0  5004.6     .12       0  5084.9      .1       0
Bank Sta=4984.9,5014.9
XS Rating Curve= 0 ,0
Exp/Cntr=0.3,0.1

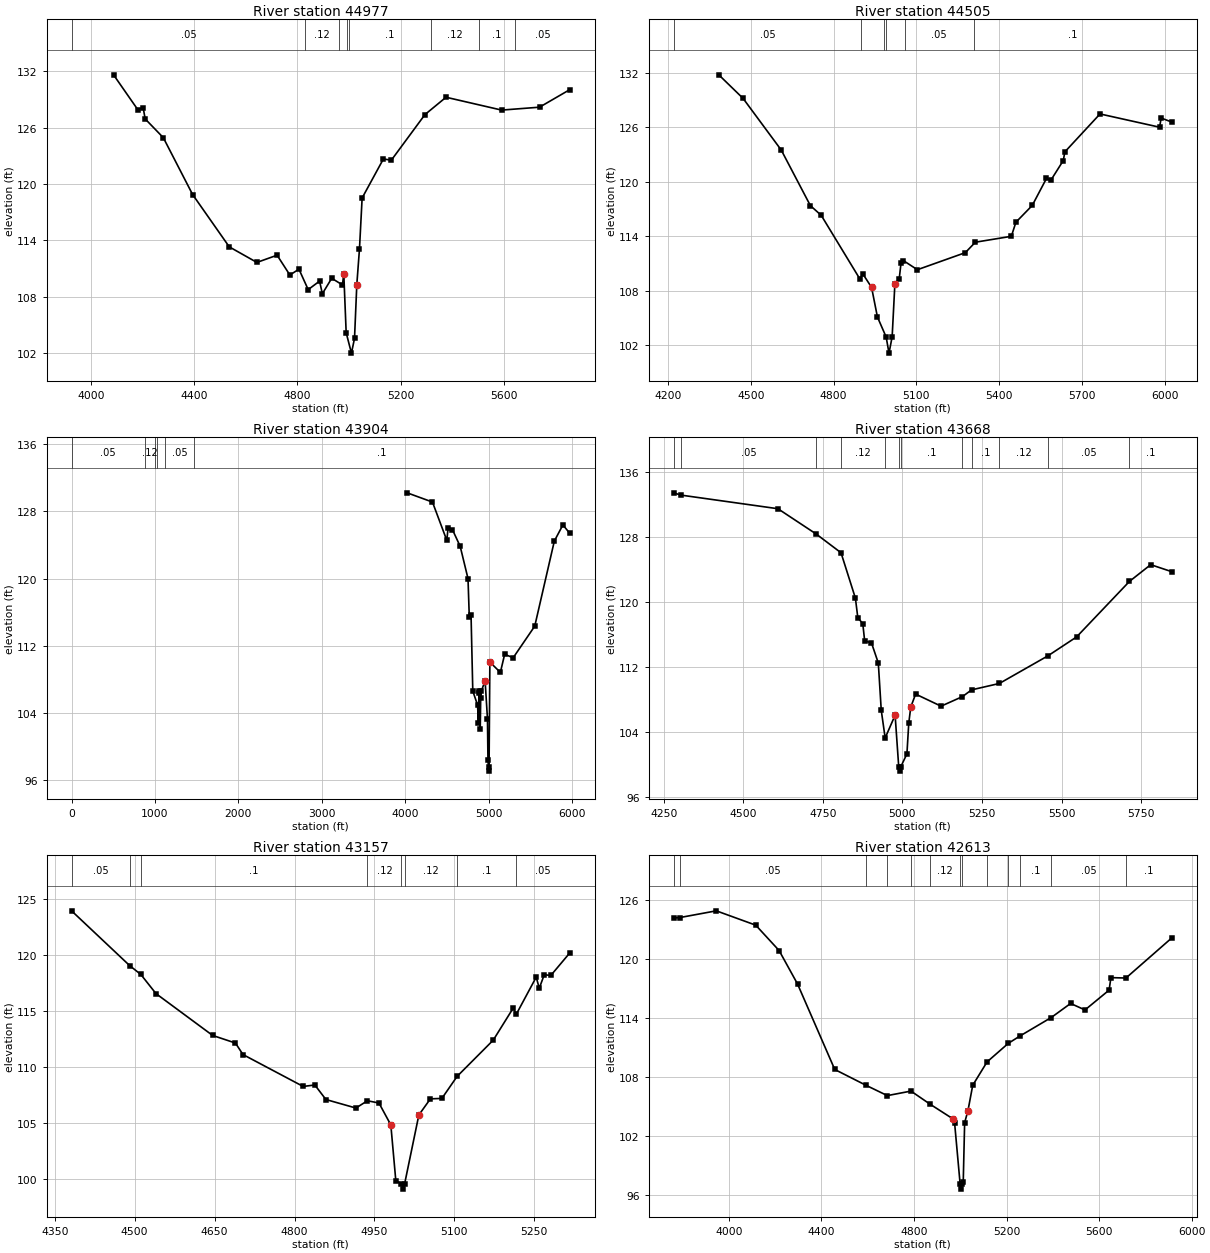
Type RM Length L Ch R = 1 ,44977   ,472,472,472
BEGIN DESCRIPTION:
Mapping XS 267e7cbc
END DESCRIPTION:
XS GIS Cut Line= 4
      2362932.96     13223893.34      2362453.79     13223306.53
      2362363.52     13222938.48      2361752.53     13222782.26
#Sta/Elev= 30
  4087.3  131.64  4181.1  127.93  4201.9  128.15  4209.8  126.94  4280.1  124.94
  4393.6  118.88  4535.7   113.3  4642.7  111.64    4721  112.41  4770.5   110.3
  4805.7  110.92  4841.5  108.74  4885.7  109.65  4896.3   108.3  4932.7  109.95
  4974.3  109.24  4979.4  110.43  4988.7  104.14  5009.1  101.97    5021  103.54
  5029.9  109.28  5040.2  113.07  5050.5  118.51  5132.9  122.67  5163.7  122.54
  5293.9   127.4  5375.6  129.25  5591.1  127.88  5737.9  128.19  5854.5  130.05
#Mann= 8 ,-1 , 0
  3924.6     .05       0  4830.7     .12       0  4961.3      .1       0
  4992.9     .07       0  4998.9      .1       0    5318     .12       0
  5502.1      .1       0  5644.5     .05       0
Bank Sta=4979.4,5029.9
XS Rating Curve= 0 ,0
Exp/Cntr=0.3,0.1

Type RM Length L Ch R = 1 ,44505   ,601,601,601
BEGIN DESCRIPTION:
Mapping XS 5a4fbf3a
END DESCRIPTION:
XS GIS Cut Line= 4
      2363042.33      13223861.2        2362834.      13223244.9
      2362643.03     13222945.42       2362078.8     13222654.63
#Sta/Elev= 30
  4384.3   131.8  4472.4   129.2  4610.6  123.51  4716.1  117.39  4755.4  116.32
  4895.6   109.3  4906.1  109.87  4937.8  108.38  4958.9  105.13  4990.6  102.91
  5000.9  101.14  5012.3  102.94  5022.2  108.77  5037.9  109.32  5044.4  111.06
  5053.1  111.33  5103.7  110.33  5277.4  112.21  5313.7  113.36  5444.1  114.01
  5460.6  115.56  5519.8  117.41  5571.4  120.39  5587.3  120.19  5632.3  122.36
  5637.9  123.31  5765.3  127.49    5981  126.03  5986.9  127.04  6024.8   126.6
#Mann= 6 ,-1 , 0
  4220.6     .05       0  4899.7     .12       0  4984.5     .07       0
  4990.5     .12       0  5057.9     .05       0  5307.6      .1       0
Bank Sta=4937.8,5022.2
XS Rating Curve= 0 ,0
Exp/Cntr=0.3,0.1

Type RM Length L Ch R = 1 ,43904   ,236,236,236
BEGIN DESCRIPTION:
BAYOU CREEK 66.0
END DESCRIPTION:
XS GIS Cut Line= 3
      2363679.54     13223843.88      2363227.88     13223145.86
      2362252.56     13222602.63
#Sta/Elev= 30
  4022.9  130.22  4326.5  129.12  4498.7  124.55  4513.9  126.07  4565.3  125.85
    4659  123.84  4752.6     120  4767.8  115.47  4788.9  115.72    4810  106.61
  4867.1  104.95  4877.4  102.82  4883.1  106.35  4888.8  106.59  4899.1  102.03
  4904.8  105.77  4911.7  106.57  4957.5  107.85    4986  103.28  4991.8   98.36
  5001.7   97.07    5005   97.57  5014.7  110.06  5140.6  108.83  5191.8  110.98
  5294.6  110.58  5552.7  114.34  5787.4  124.47  5890.2   126.4  5970.7  125.42
#Mann= 6 ,-1 , 0
       0     .05       0877.8257     .12       0996.7975     .07       0
 1026.54     .12       01125.684     .05       01472.685      .1       0
Bank Sta=4957.5,5014.7
XS Rating Curve= 0 ,0
Exp/Cntr=0.3,0.1

Type RM Length L Ch R = 1 ,43668   ,511,511,511
BEGIN DESCRIPTION:
Mapping XS ee002d5b
END DESCRIPTION:
XS GIS Cut Line= 3
      2363762.85     13223314.37      2363406.92     13222993.17
      2362471.04      13222442.9
#Sta/Elev= 30
    4281  133.45  4303.9  133.17  4608.8  131.49  4729.1  128.37  4807.1  126.06
  4852.3  120.46  4859.9  118.05  4875.5  117.32  4881.4  115.19  4902.8  114.95
  4924.3  112.46  4933.5  106.65  4945.8  103.22  4977.1  106.03  4988.5   99.63
  4991.3   99.13  4994.5   99.63  5014.2  101.26    5020  105.06  5026.3  107.03
  5041.5  108.63  5121.5  107.14  5188.7  108.32  5217.3  109.15  5304.7  109.94
  5457.4  113.35  5547.4  115.68  5713.3  122.52  5780.3  124.59  5846.1  123.73
#Mann= 12 ,-1 , 0
    4281     .05       0  4303.9     .05       0  4729.1      .1       0
  4807.1     .12       0  4945.8      .1       0  4988.5     .07       0
  4994.5      .1       0  5188.7     .05       0  5217.3      .1       0
  5304.7     .12       0  5457.4     .05       0  5713.3      .1       0
Bank Sta=4977.1,5026.3
XS Rating Curve= 0 ,0
Exp/Cntr=0.3,0.1

Type RM Length L Ch R = 1 ,43157   ,544,544,544
BEGIN DESCRIPTION:
BAYOU CREEK 65.0
END DESCRIPTION:
XS GIS Cut Line= 3
       2363586.4     13222821.84      2363236.41     13222421.85
      2362886.41     13222221.86
#Sta/Elev= 30
  4381.6  123.96  4490.7  119.06  4511.6  118.27    4540  116.56  4646.3  112.82
  4689.1  112.14  4703.3  111.11  4816.2  108.26  4838.1  108.39  4858.9  107.09
  4915.2  106.33  4936.8  106.98  4958.4  106.78  4980.7  104.82  4990.1   99.81
  5000.7   99.58  5003.5   99.08  5006.7   99.58  5033.3  105.71  5054.9  107.15
  5076.5  107.19  5105.1  109.16  5172.9   112.4  5210.4  115.27  5216.1  114.71
  5253.5  118.03  5259.3  117.04  5268.6  118.25  5280.9  118.18  5316.2  120.18
#Mann= 8 ,-1 , 0
  4381.6     .05       0  4490.7     .05       0  4511.6      .1       0
  4936.8     .12       0  5000.7     .07       0  5006.7     .12       0
  5105.1      .1       0  5216.1     .05       0
Bank Sta=4980.7,5033.3
XS Rating Curve= 0 ,0
Exp/Cntr=0.3,0.1

Type RM Length L Ch R = 1 ,42613   ,560,560,560
BEGIN DESCRIPTION:
BAYOU CREEK 64.0
END DESCRIPTION:
XS GIS Cut Line= 4
      2364086.61     13222671.13      2363841.82     13221988.83
      2363076.19     13221816.95      2362457.74     13221993.05
#Sta/Elev= 30
  3760.9  124.21  3786.7  124.24  3945.4  124.93    4116  123.47  4216.8  120.89
  4296.6  117.48  4457.4  108.78  4592.5  107.17  4684.7  106.12  4786.8  106.58
  4869.2  105.25  4970.4  103.72  4975.5  103.31  4999.4    97.1  5002.2    96.6
  5005.4    97.1  5012.7    97.3  5018.8  103.37  5033.2  104.59  5053.7  107.17
  5115.7  109.55  5207.5  111.44  5258.7   112.2  5393.2  114.07  5476.8   115.5
    5539  114.84  5643.2  116.86    5651  118.13    5716  118.09  5913.5  122.16
#Mann= 13 ,-1 , 0
  3760.9     .05       0  3786.7     .05       0  4592.5      .1       0
  4684.7     .12       0  4786.8      .1       0  4869.2     .12       0
  4999.4     .07       0  5005.4     .12       0  5115.7      .1       0
  5207.5     .05       0  5258.7      .1       0  5393.2     .05       0
    5716      .1       0
Bank Sta=4970.4,5033.2
XS Rating Curve= 0 ,0
Exp/Cntr=0.3,0.1