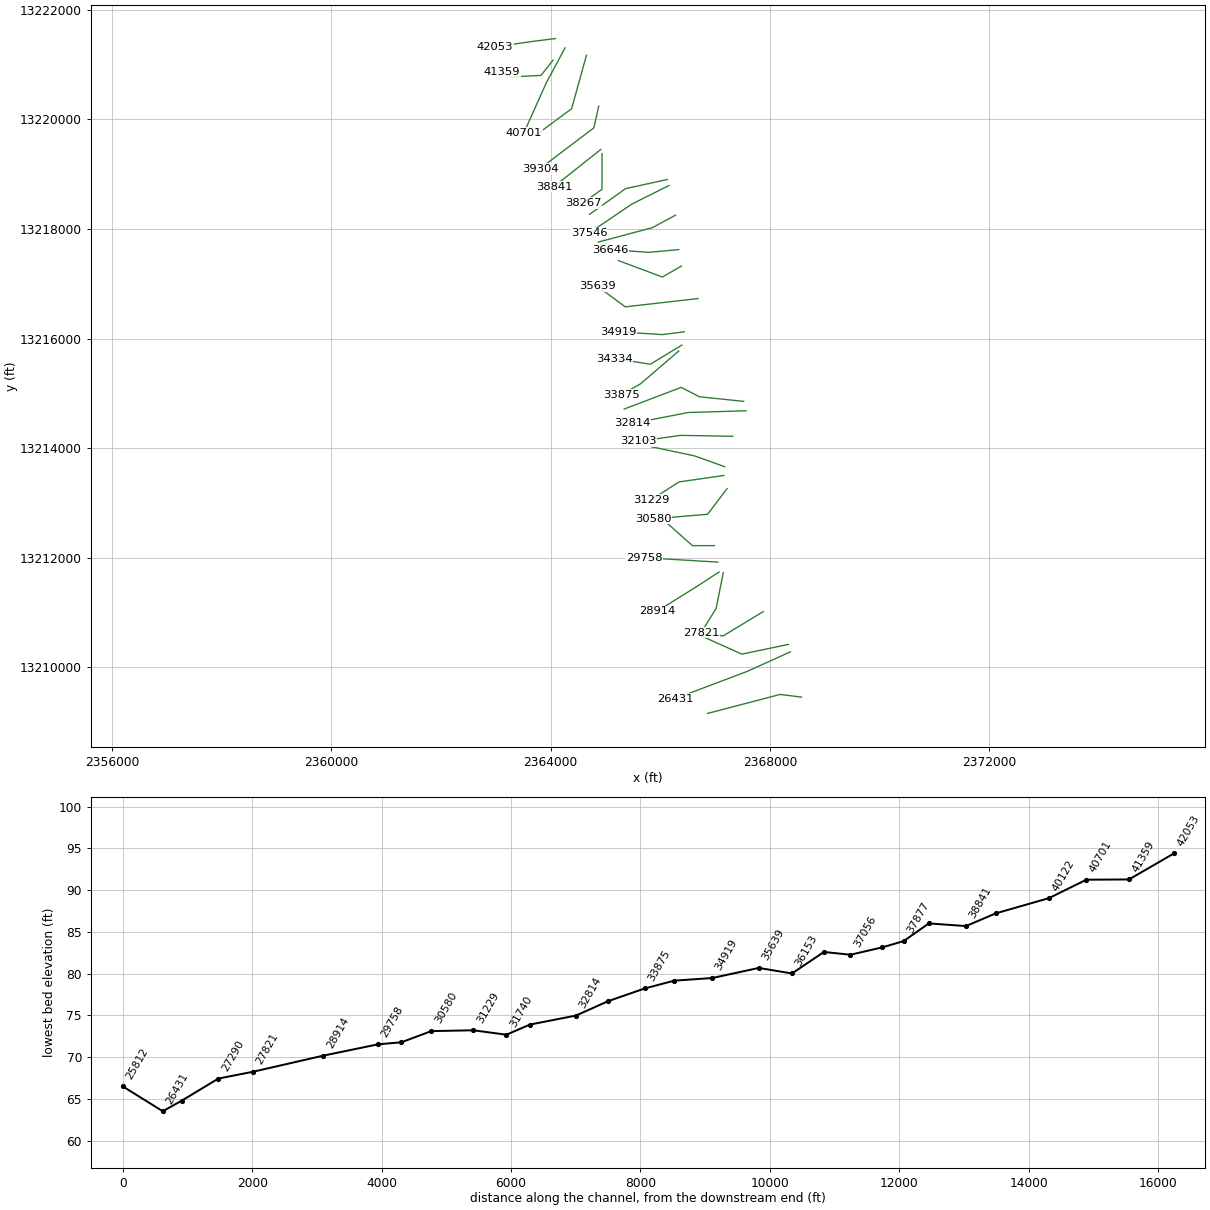
HEC-RAS study BAYOU CREEK.prj: BAYOU CREEK Base Level Engineering

--- BAYOU CREEK.g01 (geometry) --- (continued)

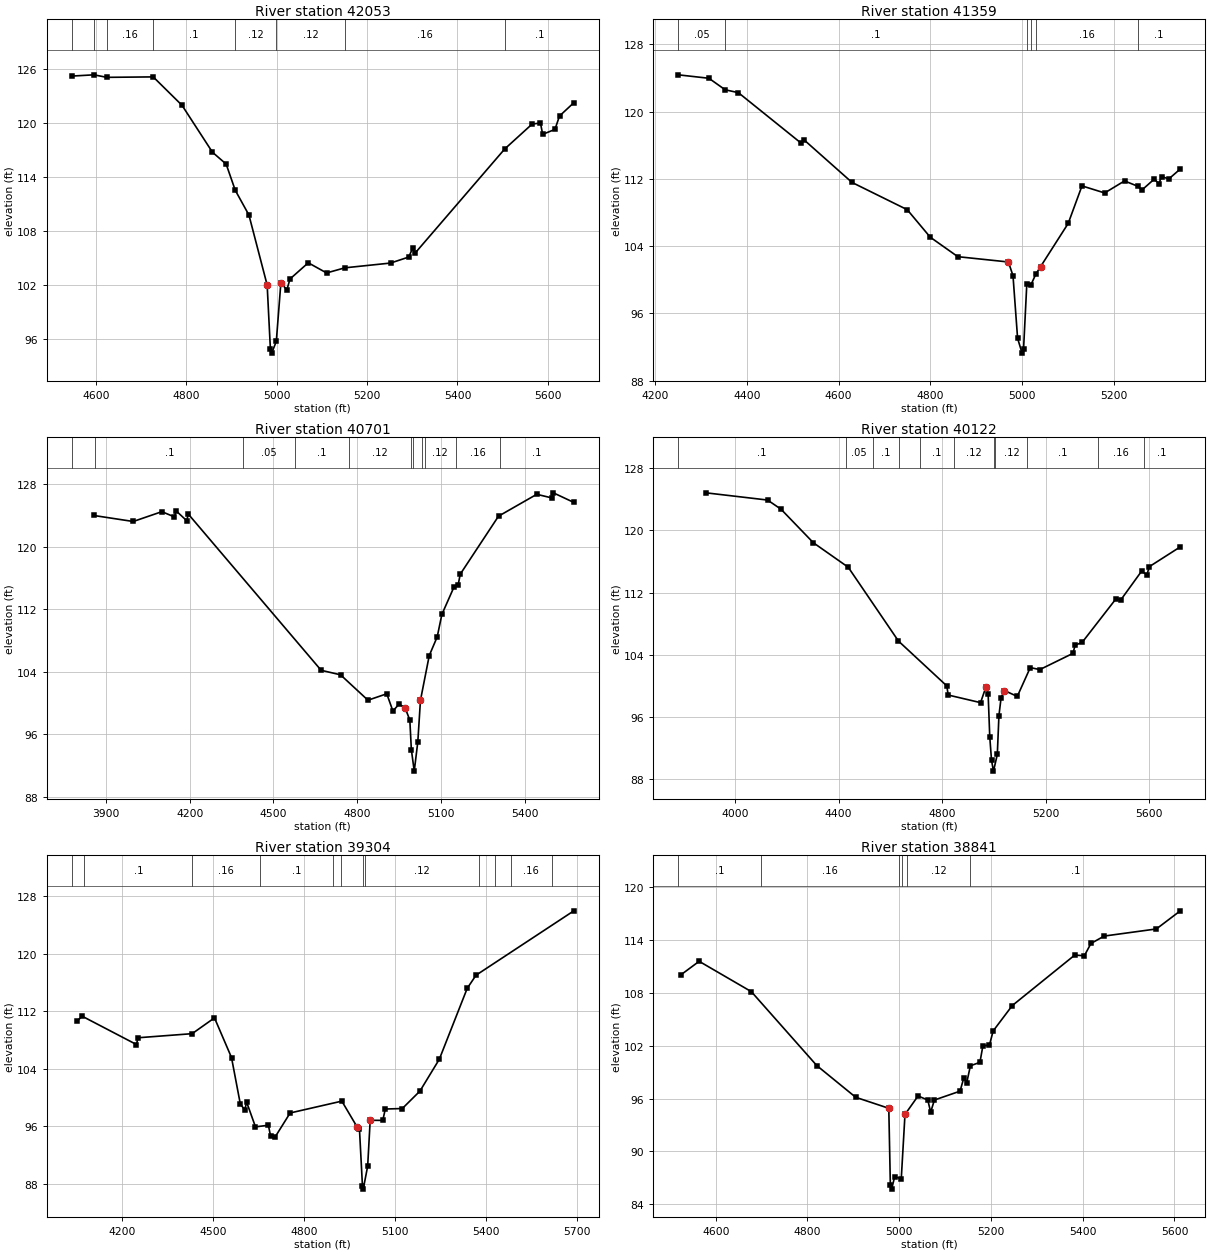
Type RM Length L Ch R = 1 ,42053   ,694,694,694
BEGIN DESCRIPTION:
BAYOU CREEK 63.0
END DESCRIPTION:
XS GIS Cut Line= 3
      2364086.45     13221471.86      2363686.41     13221421.85
      2362986.37     13221321.85
#Sta/Elev= 30
  4547.1  125.21  4596.2  125.35  4624.6  125.07  4727.2  125.12  4790.9  121.96
  4858.2  116.74  4888.5  115.42  4908.6  112.51  4938.9  109.75  4979.2  101.96
  4986.3   94.89  4989.1   94.39  4999.4   95.69  5009.5   102.2  5022.8  101.43
  5029.7  102.64  5070.1  104.44  5110.6  103.31    5151  103.88    5252  104.41
  5292.4  105.08  5300.6  106.04  5305.7  105.48  5504.5   117.1  5565.1  119.87
  5583.5  119.99  5588.5  118.73  5615.6  119.28  5625.7  120.77  5657.4  122.25
#Mann= 8 ,-1 , 0
  4547.1     .05       0  4596.2      .1       0  4624.6     .16       0
  4727.2      .1       0  4908.6     .12       0  4999.4     .12       0
    5151     .16       0  5504.5      .1       0
Bank Sta=4979.2,5009.5
XS Rating Curve= 0 ,0
Exp/Cntr=0.3,0.1

Type RM Length L Ch R = 1 ,41359   ,658,658,658
BEGIN DESCRIPTION:
BAYOU CREEK 62.0
END DESCRIPTION:
XS GIS Cut Line= 4
      2364042.05     13221076.95      2363822.65      13220799.8
      2363268.36     13220770.93      2363108.01     13220862.56
#Sta/Elev= 30
  4250.9  124.38  4317.7  123.97  4353.1   122.6  4381.8  122.26  4518.1  116.27
  4524.5  116.66  4629.3  111.58  4749.5  108.34  4799.6  105.07  4859.7  102.75
  4969.8  102.12  4979.8  100.49  4989.8   93.04  4999.6   91.28  5002.8   91.78
  5009.9   99.55  5018.5   99.36  5029.9  100.72  5039.9  101.57    5100  106.71
    5130  111.17  5179.4  110.33  5222.6  111.76  5252.3  111.11  5260.1  110.66
  5287.4  111.98  5297.5  111.43  5303.2  112.28  5319.1     112  5344.1  113.18
#Mann= 6 ,-1 , 0
  4250.9     .05       0  4353.1      .1       0  5009.9     .07       0
  5018.5      .1       0  5029.9     .16       0  5252.3      .1       0
Bank Sta=4969.8,5039.9
XS Rating Curve= 0 ,0
Exp/Cntr=0.3,0.1

Type RM Length L Ch R = 1 ,40701   ,579,579,579
BEGIN DESCRIPTION:
BAYOU CREEK 61.0
END DESCRIPTION:
XS GIS Cut Line= 3
       2364261.9     13221301.64      2363923.34     13220671.41
      2363512.29     13219755.64
#Sta/Elev= 30
  3856.7  123.98  3997.8  123.21  4100.5  124.47  4145.5  123.79  4151.2  124.58
  4189.4  123.31    4195  124.16  4670.8  104.16  4740.3  103.58  4838.5  100.33
  4905.9  101.15  4927.9   98.94  4949.8   99.83  4971.7   99.34  4988.5   97.78
  4993.9   94.01  5004.3   91.25  5017.1   95.02  5026.5  100.31    5058  106.04
  5086.6  108.45  5103.2  111.31  5147.1  114.86  5161.6  115.11    5169  116.46
  5306.1  123.89    5443  126.69    5497  126.23  5502.5  126.88  5575.9  125.65
#Mann= 11 ,-1 , 0
  3777.7     .16       0  3862.6      .1       0  4392.3     .05       0
  4577.1      .1       0    4772     .12       0  4993.8     .07       0
  4999.8     .12       0    5033      .1       0  5041.8     .12       0
  5153.9     .16       0  5312.6      .1       0
Bank Sta=4971.7,5026.5
XS Rating Curve= 0 ,0
Exp/Cntr=0.3,0.1

Type RM Length L Ch R = 1 ,40122   ,818,818,818
BEGIN DESCRIPTION:
BAYOU CREEK 60.0
END DESCRIPTION:
XS GIS Cut Line= 3
      2364652.52     13221166.24      2364381.67     13220192.24
      2363721.49      13219703.6
#Sta/Elev= 30
  3887.9  124.84    4126  123.91  4177.9  122.73  4302.7  118.42  4437.4  115.27
  4631.5  105.77  4818.3     100  4823.5   98.83  4948.6   97.85  4969.5   99.88
  4977.9   98.95  4984.1   93.48  4990.9   90.44  4998.5   89.04  5013.3   91.18
  5019.6   96.19    5028   98.51  5040.6   99.41  5090.5   98.65  5140.6  102.36
  5177.5   102.1  5305.5  104.19  5313.9  105.24    5341   105.6  5470.4  111.15
  5491.3  111.11  5570.6  114.76  5591.5   114.3  5599.9  115.33  5720.2  117.89
#Mann= 11 ,-1 , 0
  3780.8      .1       0    4428     .05       0  4531.3      .1       0
  4634.7     .12       0  4714.4      .1       0  4845.9     .12       0
    5000     .07       0    5006     .12       0  5129.4      .1       0
  5400.8     .16       0  5579.7      .1       0
Bank Sta=4969.5,5040.6
XS Rating Curve= 0 ,0
Exp/Cntr=0.3,0.1

Type RM Length L Ch R = 1 ,39304   ,463,463,463
BEGIN DESCRIPTION:
Mapping XS 9f7edd60
END DESCRIPTION:
XS GIS Cut Line= 3
      2364876.46     13220239.09      2364787.92     13219843.28
      2363803.53     13219098.48
#Sta/Elev= 30
  4050.4  110.64  4067.8  111.29  4246.5  107.36  4251.6   108.3  4430.4  108.87
  4504.1  111.07  4560.3  105.55  4589.4   99.08    4604   98.27  4610.3   99.33
  4639.4    95.9    4682   96.12  4689.3   94.63  4703.9   94.46  4753.8   97.83
  4924.5   99.48  4974.4   95.92  4982.7    95.6  4992.5   87.73  4995.2   87.23
  5009.8   90.43  5018.1   96.81  5059.7    96.8    5068   98.38  5124.2   98.45
  5182.4  100.88  5246.3  105.31  5338.5  115.19  5367.6  117.01  5690.4  125.97
#Mann= 12 ,-1 , 0
    4033     .05       0  4074.1      .1       0  4430.9     .16       0
  4655.8      .1       0  4894.3     .16       0  4920.7     .12       0
  4994.4     .07       0  5000.4     .12       0  5378.4     .16       0
  5431.7      .1       0  5481.3     .16       0  5617.1      .1       0
Bank Sta=4974.4,5018.1
XS Rating Curve= 0 ,0
Exp/Cntr=0.3,0.1

Type RM Length L Ch R = 1 ,38841   ,574,574,574
BEGIN DESCRIPTION:
BAYOU CREEK 59.0
END DESCRIPTION:
XS GIS Cut Line= 2
      2364912.95     13219447.47       2364059.7     13218771.11
#Sta/Elev= 30
    4524  110.06  4563.9   111.6  4677.7  108.15  4820.3   99.75  4905.2   96.14
  4977.3   94.89  4980.7    86.2  4983.5    85.7  4990.1   87.11  5004.5   86.88
  5012.6   94.19  5041.1   96.29  5062.3   95.83  5068.6   94.45  5076.7   95.83
  5132.7   96.84  5140.8   98.35  5147.2    97.8  5155.2   99.72    5176  100.12
  5182.4  101.98  5196.8   102.1  5204.9  103.69  5246.5  106.57  5382.7  112.31
  5403.6  112.23    5418  113.63  5446.8  114.47  5560.6  115.28  5612.8  117.34
#Mann= 6 ,-1 , 0
  4518.3      .1       0  4697.9     .16       0  5000.6     .07       0
  5006.6     .16       0  5016.2     .12       0  5154.8      .1       0
Bank Sta=4977.3,5012.6
XS Rating Curve= 0 ,0
Exp/Cntr=0.3,0.1

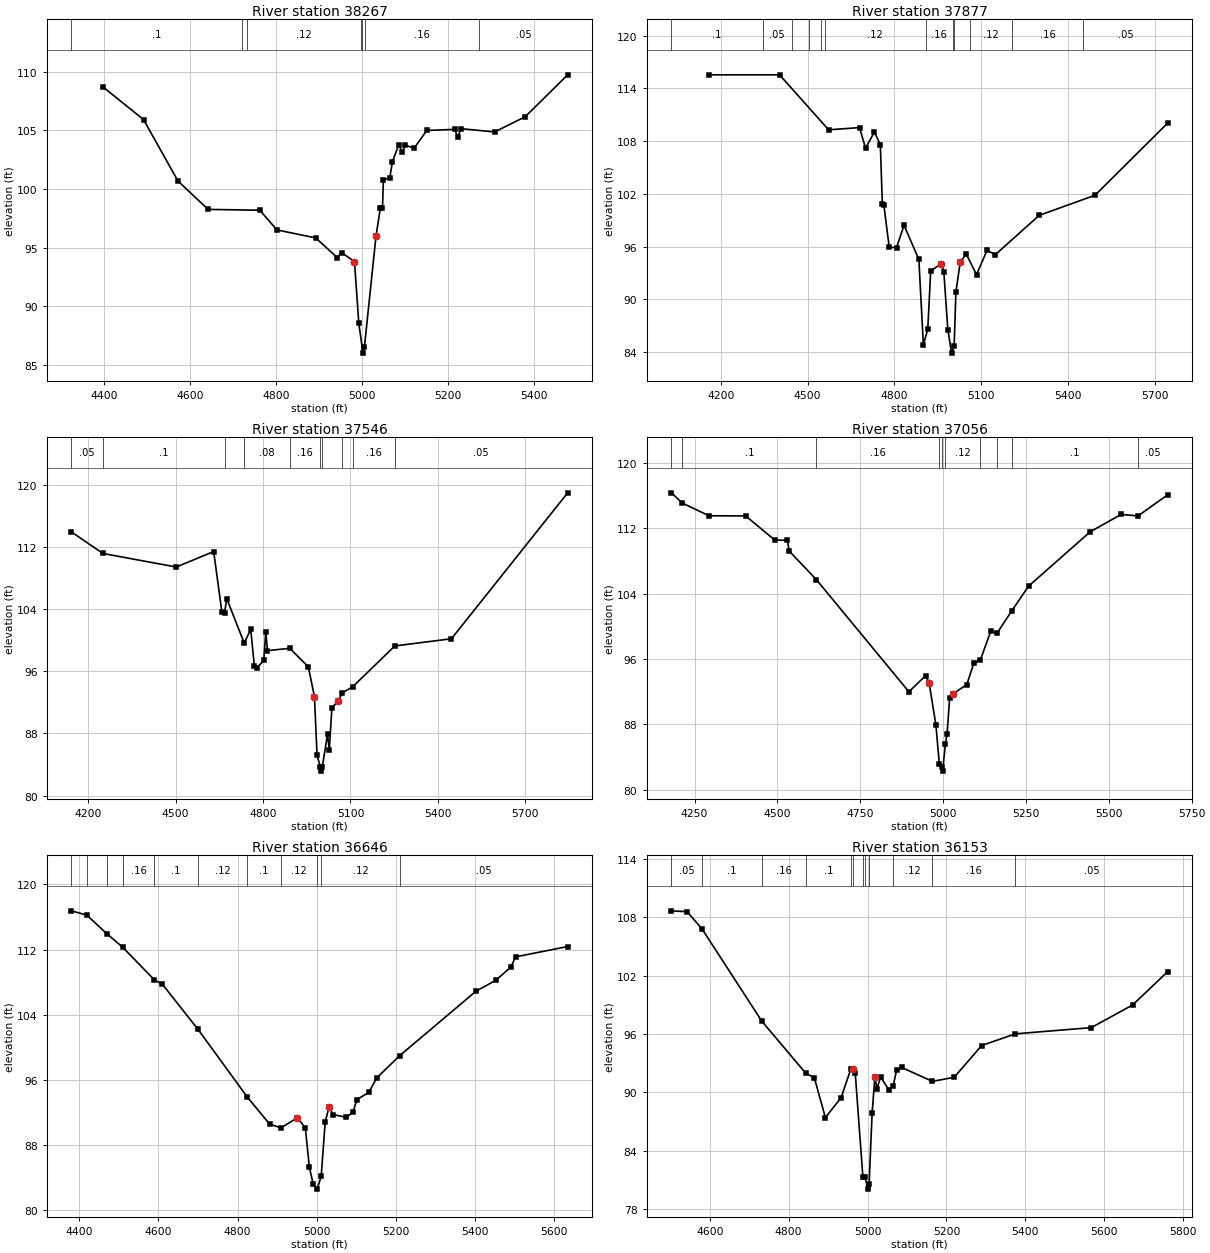
Type RM Length L Ch R = 1 ,38267   ,390,390,390
BEGIN DESCRIPTION:
BAYOU CREEK 58.0
END DESCRIPTION:
XS GIS Cut Line= 3
      2364936.41     13219371.81      2364936.41     13218721.85
      2364586.39     13218471.84
#Sta/Elev= 30
  4397.3  108.73  4492.3  105.93  4572.3  100.69  4642.3   98.27  4762.3    98.2
  4802.3   96.52  4892.3   95.84  4942.3   94.16  4952.3   94.59  4982.3   93.82
  4992.3   88.58    5002   86.02  5005.3   86.52  5032.3      96  5042.3   98.37
  5047.3   98.37  5049.5  100.79  5064.3  100.95  5070.4  102.34  5085.2  103.78
  5093.8  103.14  5099.9  103.75  5120.8  103.49  5150.3     105  5215.4  105.09
  5221.6  104.43    5230  105.15  5307.6  104.87  5378.9  106.17  5477.4  109.74
#Mann= 7 ,-1 , 0
    4325      .1       0  4721.7     .16       0  4732.8     .12       0
  4997.4     .16       0  5000.3     .07       0  5006.3     .16       0
  5271.9     .05       0
Bank Sta=4982.3,5032.3
XS Rating Curve= 0 ,0
Exp/Cntr=0.3,0.1

Type RM Length L Ch R = 1 ,37877   ,331,331,331
BEGIN DESCRIPTION:
Mapping XS c2f3b900
END DESCRIPTION:
XS GIS Cut Line= 3
      2366126.47     13218900.57      2365366.05     13218733.91
      2364709.83     13218265.18
#Sta/Elev= 30
  4158.9  115.54  4403.3  115.54  4572.8  109.29  4679.7  109.54  4700.2   107.2
  4730.9  109.03  4751.4   107.6  4758.3   100.9  4763.4  100.78  4782.1   95.93
  4807.3    95.9  4833.3   98.44  4884.5   94.55    4900   84.84  4915.2   86.61
  4925.4   93.24  4962.1   94.07  4970.7   93.17  4984.5   86.58  4997.5    83.9
  5006.3   84.66  5012.5   90.84  5027.2   94.23  5048.1   95.17  5083.7   92.82
  5119.7   95.58  5148.9    95.1    5300   99.56    5493  101.85  5743.8  110.05
#Mann= 12 ,-1 , 0
  4029.9      .1       0  4344.7     .05       0  4445.5     .16       0
    4505     .05       0  4545.3     .16       0  4560.3     .12       0
  4907.6     .16       0  5001.1     .07       0  5007.1     .16       0
  5061.9     .12       0    5206     .16       0  5452.5     .05       0
Bank Sta=4962.1,5027.2
XS Rating Curve= 0 ,0
Exp/Cntr=0.3,0.1

Type RM Length L Ch R = 1 ,37546   ,490,490,490
BEGIN DESCRIPTION:
BAYOU CREEK 57.0
END DESCRIPTION:
XS GIS Cut Line= 3
      2366157.68     13218791.18      2365483.02     13218453.06
      2364697.77     13217921.66
#Sta/Elev= 30
  4142.5   113.9  4250.7  111.13    4502  109.39  4630.5  111.38  4658.5  103.65
  4668.2  103.53  4675.2  105.34  4735.3   99.62  4757.7  101.37  4770.2   96.63
    4780   96.47  4802.4   97.38  4809.3  101.09  4814.9   98.64  4891.7   98.94
  4955.4   96.55  4976.3   92.72  4985.3   85.17  4997.1   83.65  4999.9   83.15
  5003.1   83.65  5021.2   87.87  5027.3   85.89  5036.2   91.29  5057.2   92.15
  5072.1   93.22  5108.1   94.01  5251.9   99.24  5446.6  100.17  5845.3  118.93
#Mann= 10 ,-1 , 0
  4142.5     .05       0  4250.7      .1       0  4668.2     .05       0
  4735.3     .08       0  4891.7     .16       0  4997.1     .07       0
  5003.1     .16       0  5072.1     .12       0  5108.1     .16       0
  5251.9     .05       0
Bank Sta=4976.3,5057.2
XS Rating Curve= 0 ,0
Exp/Cntr=0.3,0.1

Type RM Length L Ch R = 1 ,37056   ,410,410,410
BEGIN DESCRIPTION:
BAYOU CREEK 56.0
END DESCRIPTION:
XS GIS Cut Line= 3
      2366277.46     13218249.51      2365855.63     13218021.85
      2364871.99     13217760.14
#Sta/Elev= 30
  4180.3  116.36  4212.9  115.11  4293.6  113.55  4404.3  113.53  4491.8  110.58
  4529.9  110.54  4535.6  109.23  4617.5  105.73  4896.8   91.99  4947.2   93.96
  4957.6   93.12  4978.3   87.92  4988.6   83.13    4996   82.77  4998.7   82.27
  5006.9   85.65  5012.1   86.87  5019.7    91.2    5030   91.75  5071.4   92.86
  5092.4   95.47  5112.8   95.91  5143.8   99.43  5162.3   99.14  5207.6  101.93
  5257.7  104.92  5443.9  111.59  5537.1  113.71  5588.3  113.53  5677.5  116.12
#Mann= 10 ,-1 , 0
  4180.3     .05       0  4212.9      .1       0  4617.5     .16       0
  4988.6     .07       0    4996     .16       0  5006.9     .12       0
  5112.8      .1       0  5162.3     .05       0  5207.6      .1       0
  5588.3     .05       0
Bank Sta=4957.6,5030
XS Rating Curve= 0 ,0
Exp/Cntr=0.3,0.1

Type RM Length L Ch R = 1 ,36646   ,493,493,493
BEGIN DESCRIPTION:
BAYOU CREEK 55.0
END DESCRIPTION:
XS GIS Cut Line= 3
       2366336.4     13217621.85      2365786.41     13217571.85
      2365086.45     13217621.85
#Sta/Elev= 30
  4380.1  116.75  4418.9  116.22  4469.1  113.96  4509.3  112.29  4589.6  108.28
  4609.7  107.75  4700.1  102.19  4823.8   93.94  4880.8   90.58  4909.4   90.12
  4951.1   91.35  4971.1   90.12  4981.2   85.33  4991.2   83.17    5001    82.6
  5011.2   84.18  5021.3   90.84  5031.3   92.72  5041.3   91.75  5074.6   91.41
  5091.5   92.04  5101.5   93.59  5131.6   94.47  5151.6   96.25  5209.9   98.99
  5402.2  106.88  5452.4  108.22  5490.6  109.85  5502.5   111.1  5634.1  112.37
#Mann= 11 ,-1 , 0
  4380.1     .05       0  4418.9     .16       0  4469.1      .1       0
  4509.3     .16       0  4589.6      .1       0  4700.1     .12       0
  4823.8      .1       0  4909.4     .12       0    5001     .07       0
  5011.2     .12       0  5209.9     .05       0
Bank Sta=4951.1,5031.3
XS Rating Curve= 0 ,0
Exp/Cntr=0.3,0.1

Type RM Length L Ch R = 1 ,36153   ,514,514,514
BEGIN DESCRIPTION:
BAYOU CREEK 54.0
END DESCRIPTION:
XS GIS Cut Line= 3
      2366386.44     13217321.87      2366036.41     13217121.85
      2365236.45     13217421.84
#Sta/Elev= 30
  4503.1  108.67  4542.7  108.58  4580.1  106.84    4732   97.32  4843.6   91.95
  4865.2   91.49  4893.2   87.39  4933.1   89.45  4958.1   92.44  4963.4   92.35
  4968.9   91.95  4988.3   81.26  4993.7   81.28  5000.7   80.03    5004   80.53
  5011.6   87.82  5018.6   91.57  5023.9   90.34    5033   91.57  5054.4   90.25
    5065   90.69  5073.8   92.27  5086.4   92.55  5164.5   91.12  5219.7   91.54
  5289.3   94.81  5374.8   96.01    5567   96.65  5671.8   98.98  5760.6  102.41
#Mann= 12 ,-1 , 0
  4503.1     .05       0  4580.1      .1       0    4732     .16       0
  4843.6      .1       0  4958.1     .16       0  4963.4     .12       0
  4988.3     .07       0  4993.7     .12       0    5004     .16       0
    5065     .12       0  5164.5     .16       0  5374.8     .05       0
Bank Sta=4963.4,5018.6
XS Rating Curve= 0 ,0
Exp/Cntr=0.3,0.1

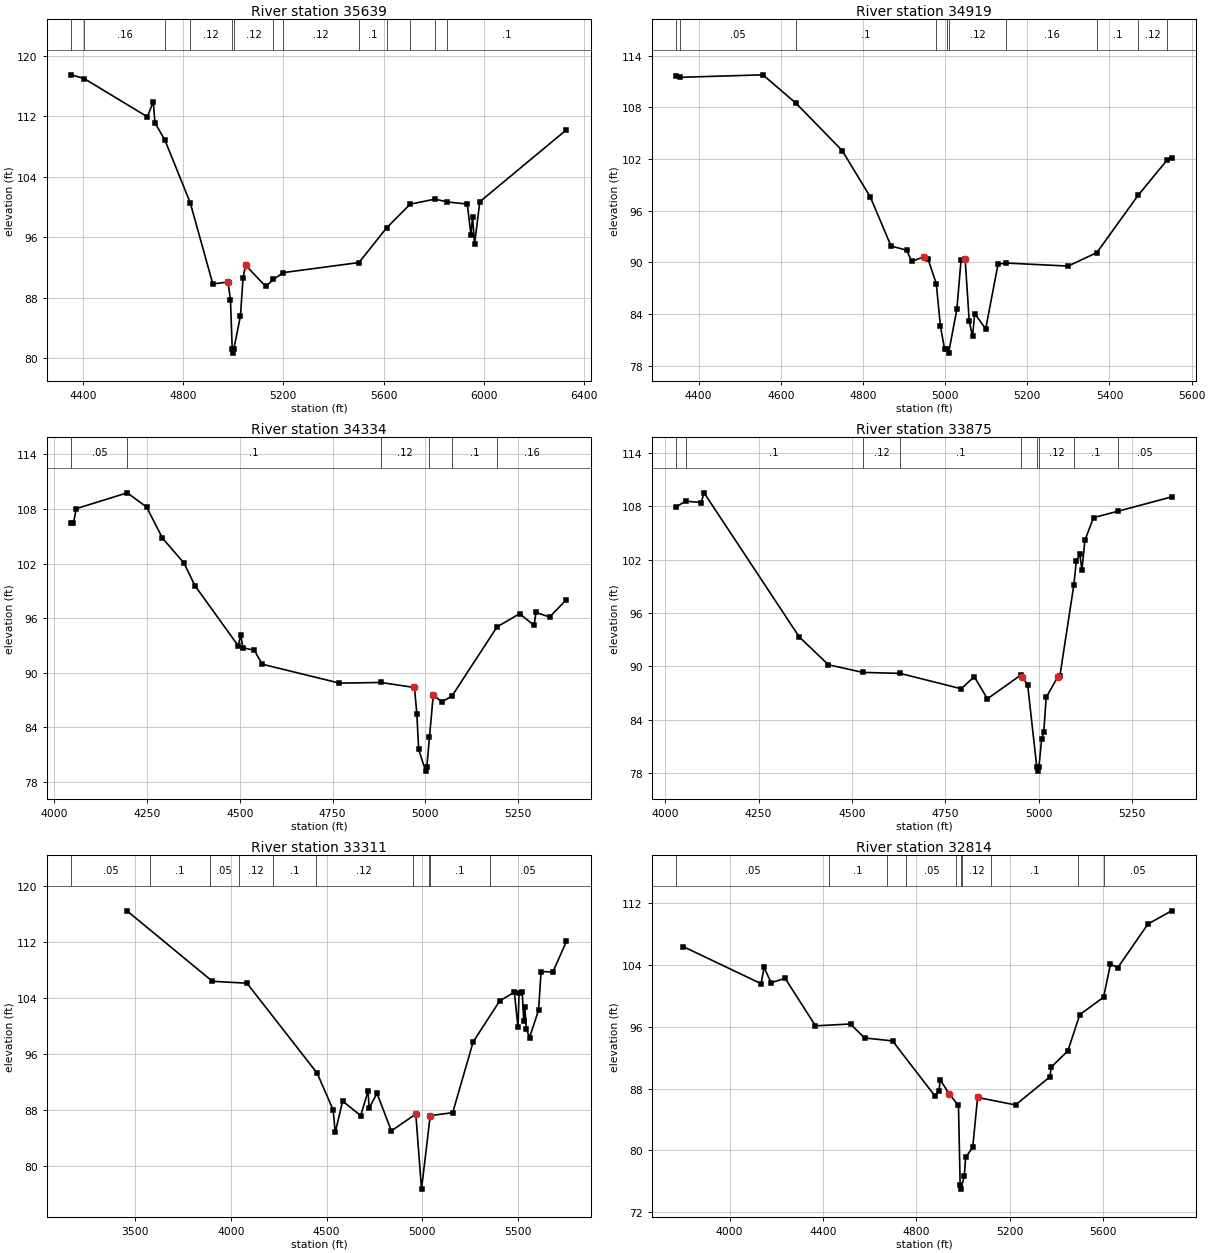
Type RM Length L Ch R = 1 ,35639   ,720,720,720
BEGIN DESCRIPTION:
BAYOU CREEK 53.0
END DESCRIPTION:
XS GIS Cut Line= 3
      2366688.94      13216728.7      2365360.84     13216577.66
      2364845.22     13216957.86
#Sta/Elev= 30
  4353.4   117.5    4405  116.99  4656.6  111.95  4680.6  113.96  4686.8  111.18
    4727  108.85  4827.7  100.61  4918.2   89.84  4978.6   90.09  4988.7   87.76
  4995.8   81.19  4998.5   80.69  5001.8   81.19  5028.7   85.64    5039   90.66
  5049.1   92.32  5129.6   89.51  5159.8   90.43    5200   91.34    5502   92.67
  5612.7   97.27  5706.4  100.39  5805.8  101.06  5855.5  100.68  5934.6  100.41
  5949.3   96.32  5955.5   98.74  5963.9   95.17  5984.8  100.72  6330.7  110.23
#Mann= 13 ,-1 , 0
  4353.4     .05       0    4405     .16       0    4727      .1       0
  4827.7     .12       0  4995.8     .07       0  5001.8     .12       0
  5159.8     .16       0    5200     .12       0    5502      .1       0
  5612.7     .05       0  5706.4      .1       0  5805.8     .05       0
  5855.5      .1       0
Bank Sta=4978.6,5049.1
XS Rating Curve= 0 ,0
Exp/Cntr=0.3,0.1

Type RM Length L Ch R = 1 ,34919   ,585,585,585
BEGIN DESCRIPTION:
BAYOU CREEK 52.0
END DESCRIPTION:
XS GIS Cut Line= 3
      2366436.41     13216121.85      2366036.41     13216071.85
      2365236.38     13216121.86
#Sta/Elev= 30
  4346.3  111.67  4355.1  111.48  4556.6  111.77  4637.2  108.47  4749.4  102.99
  4818.2   97.58  4868.3   91.91  4906.6   91.42  4918.4   90.12  4948.5   90.66
  4958.5   90.38  4978.5   87.54  4988.6    82.6  4998.6   79.98  5005.6   79.98
  5008.4   79.48  5028.6   84.55  5038.7   90.23  5048.7   90.45  5058.7   83.18
  5066.9   81.41  5071.9   84.07  5098.8    82.3  5128.8   89.81  5148.9   89.93
  5299.2   89.58  5369.3   91.14  5469.5   97.78  5539.6  101.85    5551  102.13
#Mann= 10 ,-1 , 0
  4346.3     .05       0  4355.1     .05       0  4637.2      .1       0
  4978.5     .12       0  5005.6     .07       0  5008.4     .12       0
  5148.9     .16       0  5369.3      .1       0  5469.5     .12       0
  5539.6      .1       0
Bank Sta=4948.5,5048.7
XS Rating Curve= 0 ,0
Exp/Cntr=0.3,0.1

Type RM Length L Ch R = 1 ,34334   ,459,459,459
BEGIN DESCRIPTION:
BAYOU CREEK 51.0
END DESCRIPTION:
XS GIS Cut Line= 3
      2366392.09     13215879.74      2365819.17     13215530.78
      2365162.91     13215634.95
#Sta/Elev= 30
  4045.7  106.46  4051.2  106.46  4058.8  108.04  4196.3  109.78  4248.6  108.21
  4291.2   104.8  4349.3  102.06  4378.7   99.58  4495.8   92.95  4502.3   94.19
  4508.2   92.74  4539.1   92.46  4560.4   90.93  4768.6   88.85    4880   88.92
  4971.1   88.37  4977.4    85.5  4982.4   81.55  5001.2   79.17  5004.5   79.67
  5011.6   82.94  5021.8   87.56  5044.7   86.78  5072.4   87.44  5193.9   95.04
  5254.6   96.48  5293.8   95.21  5298.8   96.63  5335.6   96.12    5381   98.03
#Mann= 6 ,-1 , 0
  4045.7     .05       0  4196.3      .1       0    4880     .12       0
  5011.6     .12       0  5072.4      .1       0  5193.9     .16       0
Bank Sta=4971.1,5021.8
XS Rating Curve= 0 ,0
Exp/Cntr=0.3,0.1

Type RM Length L Ch R = 1 ,33875   ,564,564,564
BEGIN DESCRIPTION:
BAYOU CREEK 50.0
END DESCRIPTION:
XS GIS Cut Line= 3
      2366336.42     13215771.86      2365636.41     13215171.85
      2365286.39     13214971.84
#Sta/Elev= 30
  4030.4  107.97  4054.8  108.58  4096.5  108.43  4104.2  109.52  4358.8   93.33
    4437   90.19  4529.2   89.33  4628.8   89.22  4792.4   87.49  4827.5   88.85
  4862.6   86.36  4952.4   89.04  4954.5   88.86  4970.3   87.96  4994.7   78.73
  4997.4   78.23  5000.7   78.73  5007.8   81.83  5013.5   82.64    5020   86.51
  5050.9   88.83  5056.7   88.93  5094.1   99.19  5100.6  101.81    5110  102.63
  5115.7  100.84  5123.6  104.18  5146.7  106.73  5212.2  107.45  5355.5  109.06
#Mann= 9 ,-1 , 0
  4030.4     .05       0  4054.8      .1       0  4529.2     .12       0
  4628.8      .1       0  4952.4     .12       0  4994.7     .07       0
  5000.7     .12       0  5094.1      .1       0  5212.2     .05       0
Bank Sta=4954.5,5050.9
XS Rating Curve= 0 ,0
Exp/Cntr=0.3,0.1

Type RM Length L Ch R = 1 ,33311   ,497,497,497
BEGIN DESCRIPTION:
BAYOU CREEK 49.0
END DESCRIPTION:
XS GIS Cut Line= 4
      2367522.32      13214853.7      2366715.01     13214937.03
      2366381.67     13215108.91      2365341.39      13214713.6
#Sta/Elev= 30
  3455.9  116.43  3902.9  106.37  4083.8   106.1  4451.3   93.25  4534.4   88.03
  4545.7    84.8  4584.3   89.27  4678.9    87.2  4717.5   90.73  4722.8   88.28
  4764.4   90.38  4839.3   85.02  4967.2   87.43  4997.1   76.71  5042.6    87.2
  5160.3   87.62  5267.2   97.72  5406.3  103.58  5482.7  104.81  5502.1   99.79
  5507.4  104.75    5524  104.82  5532.2  100.66  5537.6  102.73  5545.4   99.58
  5562.3   98.35  5609.6  102.26  5622.6  107.76  5684.4  107.71  5755.4  112.07
#Mann= 10 ,-1 , 0
  3165.3     .05       0  3574.9      .1       0  3889.9     .05       0
  4039.9     .12       0  4222.1      .1       0  4445.4     .12       0
  4950.1     .07       0  5035.1     .12       0  5041.6      .1       0
  5353.1     .05       0
#XS Ineff= 2 , 0
         4284.09   95.91
Permanent Ineff=
       F       F
Bank Sta=4967.2,5042.6
XS Rating Curve= 0 ,0
Exp/Cntr=0.3,0.1

Type RM Length L Ch R = 1 ,32814   ,711,711,711
BEGIN DESCRIPTION:
BAYOU CREEK 48.0
END DESCRIPTION:
XS GIS Cut Line= 3
      2367563.94     13214681.82      2366511.88     13214650.57
       2365491.9     13214452.82
#Sta/Elev= 30
  3801.5  106.39    4135  101.59  4147.9  103.69  4177.9  101.71  4237.9  102.29
    4368   96.13    4518   96.37  4578.1   94.56  4698.1   94.18  4878.6   87.09
  4896.9   87.67    4902   89.17  4939.8   87.35  4980.5   85.82  4987.7   75.49
  4990.4   74.99  5005.4   76.64  5011.1    79.1  5041.6   80.41  5062.3   86.86
    5225   85.89  5372.7   89.54  5377.8   90.79  5449.1   92.89    5500   97.58
  5601.9   99.83  5631.4  104.11    5663  103.67  5791.7   109.3    5893  111.02
#Mann= 10 ,-1 , 0
  3772.7     .05       0  4425.8      .1       0    4676     .12       0
  4757.1     .05       0  4971.3     .12       0  4990.8     .07       0
  4996.8     .12       0  5120.9      .1       0  5490.9     .16       0
  5603.9     .05       0
Bank Sta=4939.8,5062.3
XS Rating Curve= 0 ,0
Exp/Cntr=0.3,0.1

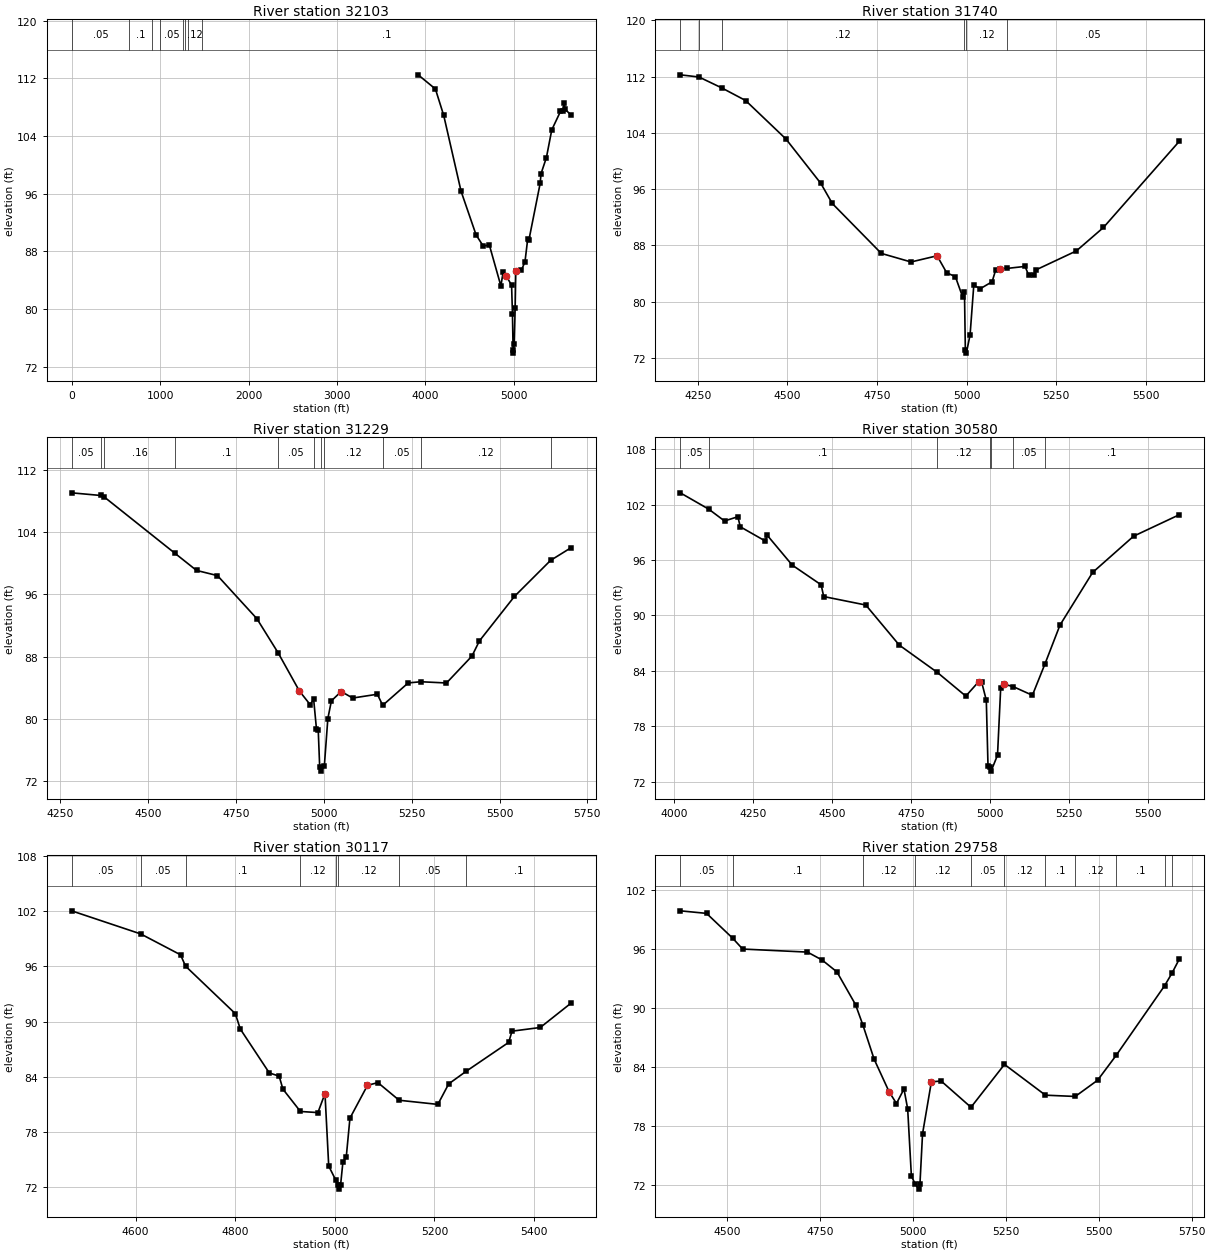
Type RM Length L Ch R = 1 ,32103   ,363,363,363
BEGIN DESCRIPTION:
BAYOU CREEK 47.0
END DESCRIPTION:
XS GIS Cut Line= 3
      2367322.68     13214216.89      2366371.17     13214233.28
      2365605.37     13214126.18
#Sta/Elev= 30
  3917.7  112.48  4112.7  110.52  4206.8  106.85  4402.7   96.35  4572.8   90.29
  4652.8   88.76  4722.8   88.88  4852.8   83.23  4878.8   85.16  4913.2    84.6
  4973.8   83.34  4983.9   79.36    4991   74.41  4993.8   73.91  5004.1   75.24
  5014.2   80.12  5021.6   85.32  5084.9    85.4  5125.3   86.57  5155.6   89.66
  5169.6   89.58  5296.9   97.43    5307   98.79  5367.6  101.01  5428.2  104.85
  5526.8  107.41  5559.5  107.44  5569.5  108.53  5579.6  107.69  5642.6  106.96
#Mann= 8 ,-1 , 0
       0     .05       0653.6032      .1       0911.0833     .12       0
1000.084     .05       01256.902     .12       01286.535     .07       0
1316.168     .12       0 1474.21      .1       0
Bank Sta=4913.2,5021.6
XS Rating Curve= 0 ,0
Exp/Cntr=0.3,0.1

Type RM Length L Ch R = 1 ,31740   ,511,511,511
BEGIN DESCRIPTION:
BAYOU CREEK 46.0
END DESCRIPTION:
XS GIS Cut Line= 3
      2367176.85     13213661.32      2366624.73     13213859.25
      2365836.58     13214025.91
#Sta/Elev= 30
    4201  112.24  4253.2  111.93  4316.4  110.39  4383.2  108.59  4495.6  103.13
  4593.1   96.81    4625   93.96  4761.7   86.87  4844.6   85.65  4917.3   86.53
    4944   84.12  4968.4   83.56  4988.6   80.67  4993.7   81.37  4996.1    73.2
  4998.9    72.7  5009.3   75.28  5019.6   82.31  5038.3   81.87  5070.7   82.84
  5080.9   84.54  5093.2    84.7  5111.5   84.73  5162.7   85.02  5172.9   83.75
  5187.5   83.78  5193.3   84.53  5305.7   87.22  5381.3   90.55  5593.1  102.81
#Mann= 6 ,-1 , 0
    4201     .05       0  4253.2      .1       0  4316.4     .12       0
  4993.7     .07       0  4998.9     .12       0  5111.5     .05       0
Bank Sta=4917.3,5093.2
XS Rating Curve= 0 ,0
Exp/Cntr=0.3,0.1

Type RM Length L Ch R = 1 ,31229   ,649,649,649
BEGIN DESCRIPTION:
BAYOU CREEK 45.0
END DESCRIPTION:
XS GIS Cut Line= 3
      2367159.49     13213501.62      2366340.01     13213383.56
      2365842.32     13213062.14
#Sta/Elev= 30
  4282.3   109.1  4364.7  108.76    4375  108.57  4577.1  101.28  4637.7    99.1
  4697.4   98.43  4809.5   92.88  4870.1   88.47  4930.7   83.54    4961   81.81
  4971.1   82.48  4979.1   78.67  4984.1   78.56  4988.3   73.73  4991.1   73.23
  5001.4   73.83  5011.5   80.01  5021.6   82.29  5049.5   83.49  5082.2   82.65
  5152.4   83.14  5167.6   81.71  5240.2    84.6  5276.5   84.75  5349.1   84.59
  5421.6   88.06  5442.8   90.01  5542.4   95.74  5645.3  100.39  5702.7     102
#Mann= 11 ,-1 , 0
  4282.3     .05       0  4364.7     .05       0    4375     .16       0
  4577.1      .1       0  4870.1     .05       0  4971.1     .12       0
  4991.1     .07       0  5001.4     .12       0  5167.6     .05       0
  5276.5     .12       0  5645.3      .1       0
Bank Sta=4930.7,5049.5
XS Rating Curve= 0 ,0
Exp/Cntr=0.3,0.1

Type RM Length L Ch R = 1 ,30580   ,463,463,463
BEGIN DESCRIPTION:
BAYOU CREEK 44.0
END DESCRIPTION:
XS GIS Cut Line= 3
      2367218.47     13213262.03      2366863.16     13212794.23
      2365873.99     13212709.91
#Sta/Elev= 30
  4018.6  103.29  4108.7  101.52  4158.7  100.24  4200.9   100.7  4208.6   99.61
  4287.6   98.07  4293.9   98.69  4372.9   95.46  4464.6   93.32  4472.7   92.05
    4606   91.13  4711.9   86.79  4832.3   83.83  4922.6   81.26  4962.8    82.8
  4972.8   82.78  4987.5   80.81  4992.9   73.69  4999.9   73.63  5002.7   73.13
    5023   74.86    5033    82.1  5043.1   82.56  5073.2   82.28  5133.4   81.35
  5173.5   84.77  5220.7   88.95  5324.1   94.66  5453.8   98.59  5598.8  100.92
#Mann= 7 ,-1 , 0
  4018.6     .05       0  4108.7      .1       0  4832.3     .12       0
  4999.9     .07       0  5002.7     .12       0  5073.2     .05       0
  5173.5      .1       0
Bank Sta=4962.8,5043.1
XS Rating Curve= 0 ,0
Exp/Cntr=0.3,0.1

Type RM Length L Ch R = 1 ,30117   ,359,359,359
BEGIN DESCRIPTION:
BAYOU CREEK 43.0
END DESCRIPTION:
XS GIS Cut Line= 3
      2366986.45     13212221.85      2366586.41     13212221.85
      2366136.42     13212621.84
#Sta/Elev= 30
  4471.5  102.04  4610.2   99.53  4690.2   97.26  4700.2   96.03  4800.2   90.86
  4810.2   89.19  4868.4   84.42  4888.2   84.07  4895.7   82.66  4930.9   80.23
    4966   80.11  4980.2   82.18  4987.7    74.3  5001.9   72.76  5005.6   72.29
  5008.4   71.79  5011.6   72.29  5016.2   74.74  5022.9   75.28  5030.3    79.5
  5065.5   83.07  5086.4   83.37  5129.1   81.45  5206.8      81  5228.6   83.23
  5263.7    84.6    5349   87.74  5355.7   88.96  5412.5   89.36  5473.6   91.98
#Mann= 8 ,-1 , 0
  4471.5     .05       0  4610.2     .05       0  4700.2      .1       0
  4930.9     .12       0  5001.9     .07       0  5005.6     .12       0
  5129.1     .05       0  5263.7      .1       0
Bank Sta=4980.2,5065.5
XS Rating Curve= 0 ,0
Exp/Cntr=0.3,0.1

Type RM Length L Ch R = 1 ,29758   ,844,844,844
BEGIN DESCRIPTION:
BAYOU CREEK 42.0
END DESCRIPTION:
XS GIS Cut Line= 2
      2367048.31     13211921.76      2365708.09     13212001.61
#Sta/Elev= 30
  4374.5   99.87  4445.2   99.61  4515.3   97.09  4542.3   95.98  4716.6   95.67
  4755.8   94.87  4795.8   93.66  4845.9   90.33    4866   88.22    4896   84.77
  4936.1   81.47  4956.1   80.26  4976.2   81.74  4986.2   79.72  4996.2   72.88
  5006.2   72.09    5016   71.55  5019.2   72.05  5026.2   77.18    5050   82.47
  5076.3   82.55  5156.5   79.88  5246.6   84.24  5356.8   81.11    5437   80.98
  5497.1   82.63  5547.2   85.17  5677.4   92.25  5697.4   93.54  5717.1   94.98
#Mann= 11 ,-1 , 0
  4374.5     .05       0  4515.3      .1       0    4866     .12       0
  5006.2     .12       0  5156.5     .05       0  5246.6     .12       0
  5356.8      .1       0    5437     .12       0  5547.2      .1       0
  5677.4     .12       0  5697.4      .1       0
Bank Sta=4936.1,5050
XS Rating Curve= 0 ,0
Exp/Cntr=0.3,0.1

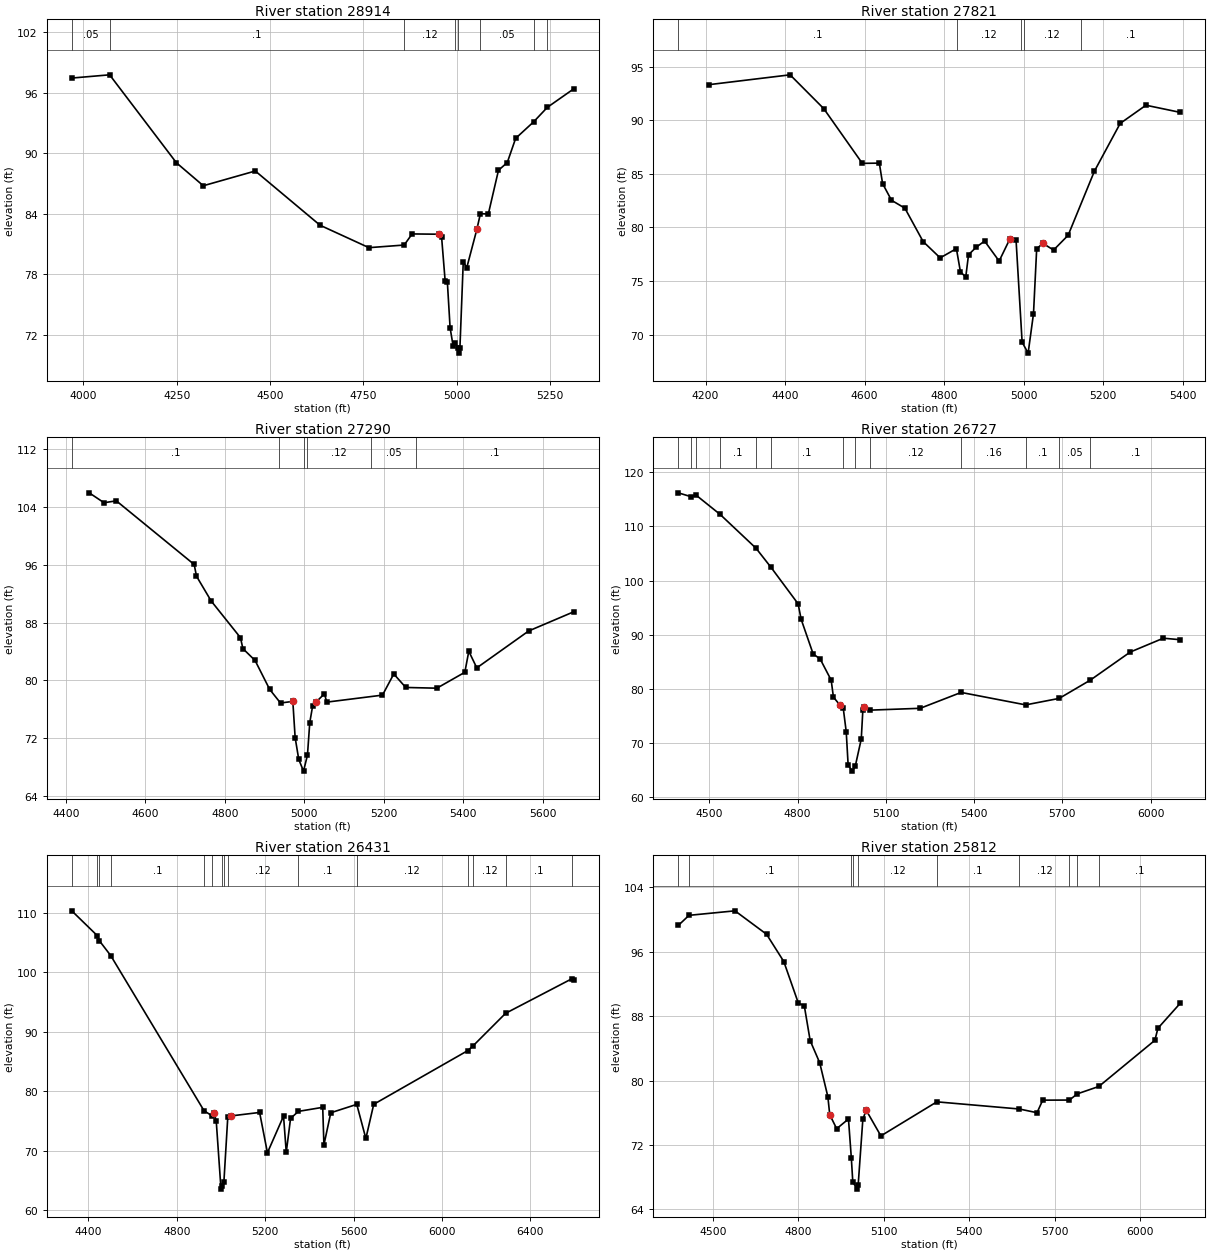
Type RM Length L Ch R = 1 ,28914   ,1093,1093,1093
BEGIN DESCRIPTION:
BAYOU CREEK 41.0
END DESCRIPTION:
XS GIS Cut Line= 3
      2367072.66     13211741.21      2366683.76     13211487.73
      2365936.39     13211021.84
#Sta/Elev= 30
  3968.6   97.43    4070   97.75    4249   89.04    4321   86.77  4460.2   88.23
  4633.7   82.86  4764.6   80.64    4859    80.9  4880.3      82  4953.4   81.97
  4959.3   81.67  4968.8   77.32  4974.7   77.23    4982   72.72    4990   70.93
  4995.9   71.23  5002.3    70.7  5005.1    70.2  5008.3    70.7  5017.3   79.25
  5026.6   78.65  5053.7   82.45  5063.2   84.01  5084.4   83.97  5111.6    88.3
  5135.2   89.07  5157.6   91.46  5205.9    93.1  5242.5   94.53  5313.5   96.37
#Mann= 8 ,-1 , 0
  3968.6     .05       0    4070      .1       0    4859     .12       0
  4995.9     .07       0  5002.3     .12       0  5063.2     .05       0
  5205.9      .1       0  5242.5     .05       0
Bank Sta=4953.4,5053.7
XS Rating Curve= 0 ,0
Exp/Cntr=0.3,0.1

Type RM Length L Ch R = 1 ,27821   ,531,531,531
BEGIN DESCRIPTION:
BAYOU CREEK 40.0
END DESCRIPTION:
XS GIS Cut Line= 3
      2367149.04     13211727.32      2367018.83     13211076.27
      2366742.76     13210633.52
#Sta/Elev= 30
  4208.2   93.34  4412.6   94.26  4497.3    91.1  4594.2   85.99    4637   86.01
  4645.2    84.1  4667.6   82.54  4701.3    81.8  4747.2   78.68    4790   77.16
  4830.8   78.02  4840.9   75.87  4854.3   75.36  4861.3   77.45  4880.5   78.15
  4901.7   78.73  4938.3   76.86  4965.7   78.96  4980.8   78.84  4996.1   69.28
  5011.2   68.26  5024.7   71.95  5032.7      78  5048.1   78.52  5075.2   77.89
  5111.8   79.27  5177.9   85.26  5242.7   89.72  5307.5   91.42  5393.9   90.75
#Mann= 5 ,-1 , 0
  4131.3      .1       0  4831.9     .12       0  4993.6     .07       0
  4999.6     .12       0  5144.7      .1       0
Bank Sta=4965.7,5048.1
XS Rating Curve= 0 ,0
Exp/Cntr=0.3,0.1

Type RM Length L Ch R = 1 ,27290   ,563,563,563
BEGIN DESCRIPTION:
BAYOU CREEK 39.0
END DESCRIPTION:
XS GIS Cut Line= 3
      2367878.19     13211018.97      2367149.04     13210576.27
       2366784.5     13210607.51
#Sta/Elev= 30
  4459.1  105.97  4496.3   104.6  4527.3  104.86  4723.1   96.05  4728.9   94.43
  4765.8      91  4839.4   85.93  4845.7    84.4  4876.2   82.77    4913   78.76
  4940.2   76.88  4971.2    77.1    4977    72.1  4986.1   69.07  4998.1   67.45
    5008   69.67  5013.8   74.17  5021.2   76.53  5029.3   76.99  5050.7   78.16
  5056.5      77  5196.7   77.97  5225.1    80.9  5255.2   79.03  5333.5   78.93
  5403.8   81.13  5413.8   84.04  5433.9   81.74  5564.4   86.85    5678   89.51
#Mann= 6 ,-1 , 0
  4415.2      .1       0  4936.6     .12       0  4999.7     .07       0
  5005.7     .12       0  5168.9     .05       0    5280      .1       0
Bank Sta=4971.2,5029.3
XS Rating Curve= 0 ,0
Exp/Cntr=0.3,0.1

Type RM Length L Ch R = 1 ,26727   ,296,296,296
BEGIN DESCRIPTION:
BAYOU CREEK 38.0
END DESCRIPTION:
XS GIS Cut Line= 3
       2368336.5     13210420.01      2367487.58     13210242.93
      2366722.36      13210586.5
#Sta/Elev= 30
  4394.6   116.2  4436.9  115.51  4454.6   115.8    4537  112.21  4658.9  105.97
    4710  102.43    4802    95.7  4812.2   92.86    4853   86.46  4876.9   85.52
  4914.3   81.61  4921.9   78.49    4945   76.94  4955.2   76.49  4965.4   72.09
  4971.9   65.97  4985.6   64.82    4996    65.7  5016.5   70.75  5021.9   76.08
    5027   76.66  5047.1   76.08  5216.9   76.42  5355.8   79.35  5575.3   77.05
  5689.1   78.25  5794.8   81.62  5930.3    86.8  6042.9   89.36  6100.6   89.08
#Mann= 13 ,-1 , 0
  4394.6     .05       0  4436.9      .1       0  4454.6     .16       0
    4537      .1       0  4658.9     .16       0    4710      .1       0
  4955.2     .05       0    4996     .05       0  5047.1     .12       0
  5355.8     .16       0  5575.3      .1       0  5689.1     .05       0
  5794.8      .1       0
Bank Sta=4945,5027
XS Rating Curve= 0 ,0
Exp/Cntr=0.3,0.1

Type RM Length L Ch R = 1 ,26431   ,619,619,619
BEGIN DESCRIPTION:
BAYOU CREEK 37.0
END DESCRIPTION:
XS GIS Cut Line= 3
      2368372.98      13210284.6      2367591.74     13209930.43
      2366268.84     13209430.44
#Sta/Elev= 30
  4324.8  110.36  4440.4  106.18  4449.2  105.35  4500.9  102.84  4923.5   76.72
  4961.5   75.83  4967.4   76.43  4978.4   75.07  5000.1   63.54  5003.3   64.04
  5013.2   64.75  5030.8   75.67  5044.2   75.85  5174.8   76.44  5210.2   69.66
  5283.1   75.83  5295.4   69.74  5314.9   75.44  5350.4   76.62  5460.4    77.3
  5465.8   70.98  5496.9   76.39  5614.5    77.8  5655.6   72.06  5691.2   77.81
  6117.1   86.85    6142   87.69    6288   93.12  6587.3   98.92  6596.8    98.8
#Mann= 15 ,-1 , 0
  4324.8     .05       0  4440.4      .1       0  4449.2     .16       0
  4500.9      .1       0  4923.5     .05       0  4961.5      .1       0
  5003.3     .07       0  5013.2      .1       0  5030.8     .12       0
  5350.4      .1       0  5614.5     .12       0  6117.1      .1       0
    6142     .12       0    6288      .1       0  6587.3     .05       0
Bank Sta=4967.4,5044.2
XS Rating Curve= 0 ,0
Exp/Cntr=0.3,0.1

Type RM Length L Ch R = 1 ,25812   ,415,415,415
BEGIN DESCRIPTION:
BAYOU CREEK 36.0
END DESCRIPTION:
XS GIS Cut Line= 3
      2368575.26       13209459.      2368186.32     13209507.62
      2366861.33     13209160.76
#Sta/Elev= 30
  4378.6   99.26  4416.4  100.52  4577.7  101.08  4688.5   98.17    4749   94.78
  4800.1   89.61  4820.8   89.31  4841.5   84.96    4875   82.21  4903.5   78.01
  4910.2   75.76  4934.5   74.02  4975.9   75.23  4985.9   70.39  4991.1    67.4
  5006.6   66.52  5009.9   67.02  5026.3   75.18  5037.9   76.33  5089.6   73.13
    5286   77.36  5575.4   76.47  5637.4   76.01  5657.5   77.57  5751.1   77.58
  5778.7   78.35  5854.4   79.27  6050.9      85  6061.7    86.5  6140.2   89.61
#Mann= 10 ,-1 , 0
  4378.6     .05       0  4416.4      .1       0  4985.9     .07       0
  4991.1      .1       0  5009.9     .12       0    5286      .1       0
  5575.4     .12       0  5751.1      .1       0  5778.7     .05       0
  5854.4      .1       0
Bank Sta=4910.2,5037.9
XS Rating Curve= 0 ,0
Exp/Cntr=0.3,0.1