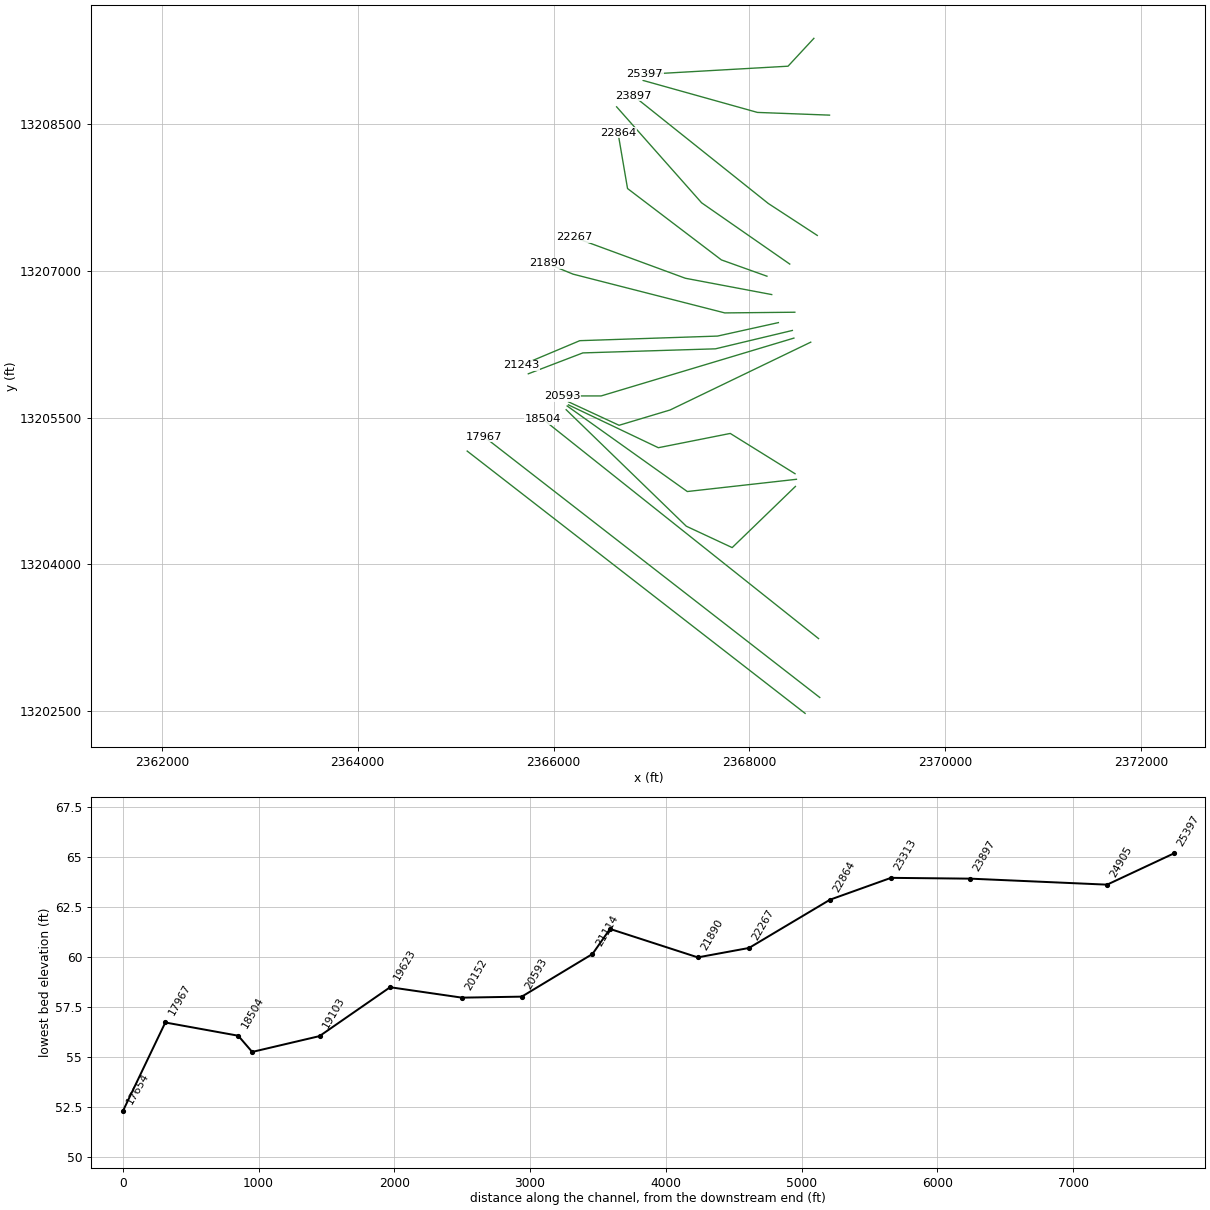
HEC-RAS study BAYOU CREEK.prj: BAYOU CREEK Base Level Engineering

--- BAYOU CREEK.g01 (geometry) --- (continued)

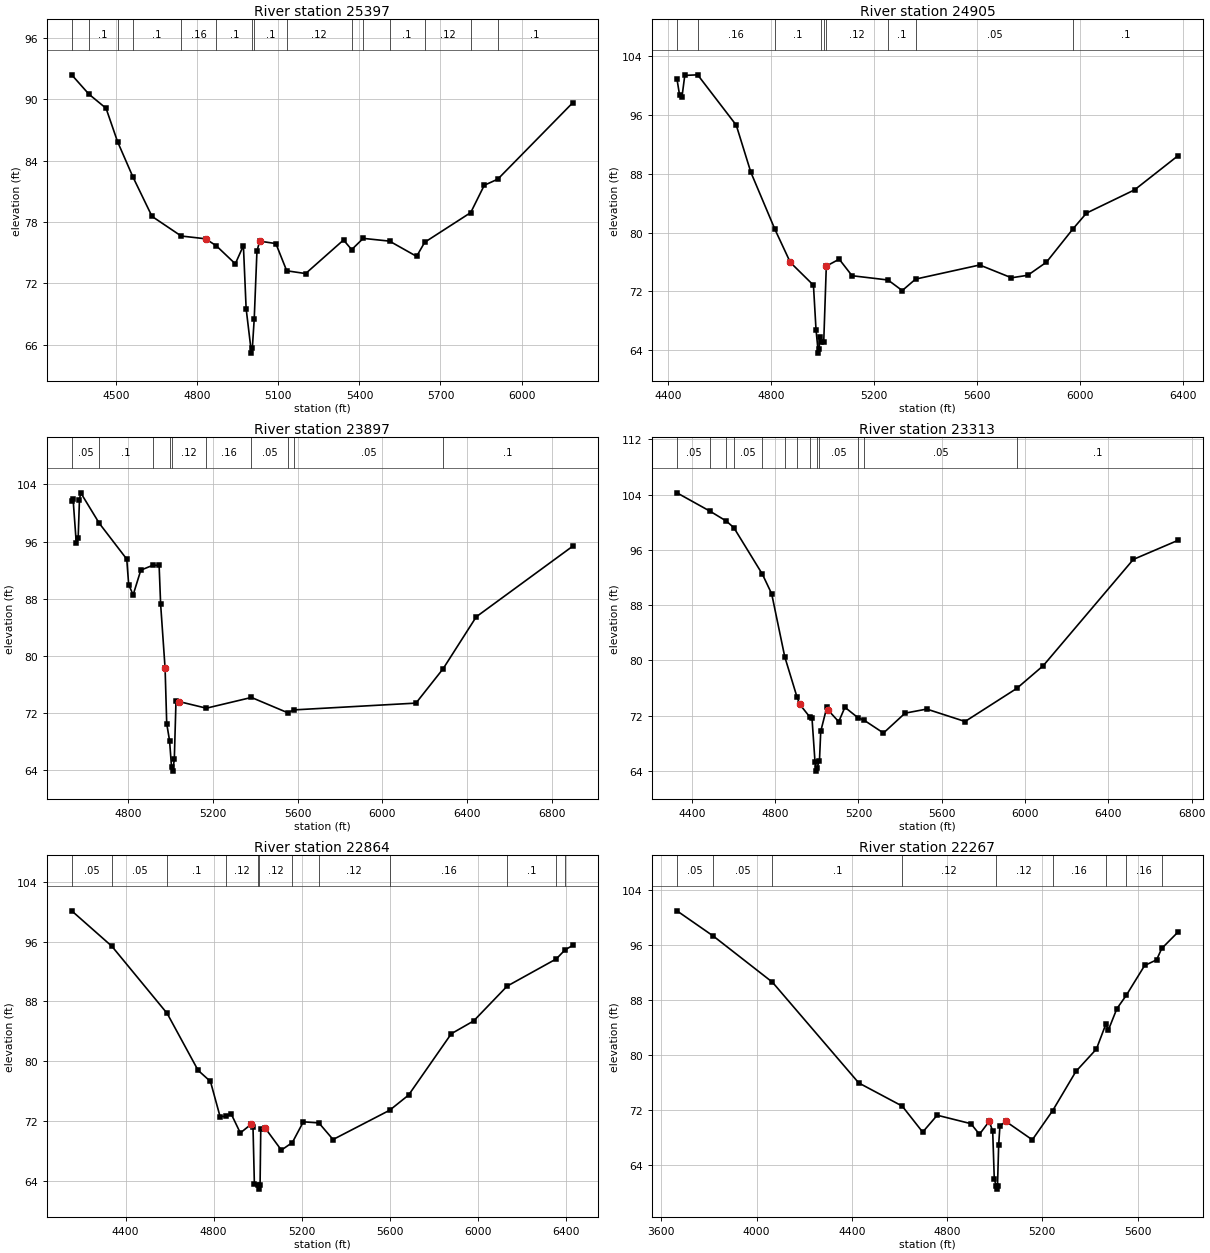
Type RM Length L Ch R = 1 ,25397   ,492,492,492
BEGIN DESCRIPTION:
BAYOU CREEK 35.0
END DESCRIPTION:
XS GIS Cut Line= 3
      2368658.55     13209375.67      2368394.66     13209090.95
      2366931.03     13209007.71
#Sta/Elev= 30
    4335   92.38  4398.6   90.49  4462.1   89.11  4504.6   85.85  4561.3   82.41
  4632.2   78.54  4740.2   76.62  4830.3   76.35  4870.4   75.66  4940.5    73.9
  4970.5   75.68  4980.6   69.52  5000.3   65.17  5003.6   65.67  5010.6   68.54
  5020.6   75.13  5030.6   76.12  5090.7   75.88  5130.8   73.22  5200.9   72.95
  5341.1   76.23  5371.2   75.29    5414   76.39  5511.4   76.12  5611.6   74.63
  5641.6   76.01  5811.9   78.91    5862   81.58  5912.1   82.18  6189.2   89.64
#Mann= 15 ,-1 , 0
    4335     .05       0  4398.6      .1       0  4504.6     .16       0
  4561.3      .1       0  4740.2     .16       0  4870.4      .1       0
  5003.6     .07       0  5010.6      .1       0  5130.8     .12       0
  5371.2      .1       0    5414     .12       0  5511.4      .1       0
  5641.6     .12       0  5811.9     .05       0  5912.1      .1       0
Bank Sta=4830.3,5030.6
XS Rating Curve= 0 ,0
Exp/Cntr=0.3,0.1

Type RM Length L Ch R = 1 ,24905   ,1008,1008,1008
BEGIN DESCRIPTION:
BAYOU CREEK 34.0
END DESCRIPTION:
XS GIS Cut Line= 3
      2368818.24     13208590.95      2368082.16     13208618.73
      2366915.46     13208945.12
#Sta/Elev= 30
  4433.6  100.93  4444.1   98.66  4453.4   98.51  4464.1  101.39  4514.2  101.47
  4664.3   94.62  4721.1   88.21  4814.4   80.47  4874.4   75.96  4964.5   72.85
  4974.5   66.79  4983.5   63.61  4986.8   64.11  4988.8   65.87    4992   65.08
  5004.5   65.16  5014.5   75.45  5064.6   76.39  5114.6   74.14  5254.4   73.56
  5309.8   72.12  5361.7   73.68  5610.9    75.6  5734.5   73.86  5797.9    74.2
  5870.5   75.98  5974.4   80.54  6026.3   82.66  6213.2   85.82  6381.7   90.45
#Mann= 9 ,-1 , 0
  4433.6     .05       0  4514.2     .16       0  4814.4      .1       0
    4992     .07       0  5004.5      .1       0  5014.5     .12       0
  5254.4      .1       0  5361.7     .05       0  5974.4      .1       0
Bank Sta=4874.4,5014.5
XS Rating Curve= 0 ,0
Exp/Cntr=0.3,0.1

Type RM Length L Ch R = 1 ,23897   ,584,584,584
BEGIN DESCRIPTION:
BAYOU CREEK 33.0
END DESCRIPTION:
XS GIS Cut Line= 3
      2368693.26     13207361.79      2368193.27     13207688.17
      2366812.32     13208791.54
#Sta/Elev= 30
    4533  101.63  4539.6  101.89  4554.5   95.83  4563.5   96.56  4569.6  101.88
  4575.6  102.82  4663.1   98.56  4792.8   93.55  4801.9   89.99    4823   88.55
  4859.2   92.01  4916.5    92.7  4945.6   92.67  4952.7   87.26  4973.8   78.28
  4981.5   70.55  4994.9   68.17  5004.1   64.52  5009.8   63.91  5017.3   65.56
  5025.2   73.68  5040.3   73.63  5168.6   72.71  5381.5   74.21  5552.8   72.07
  5581.7   72.47    6158   73.42  6286.1   78.22  6442.8   85.49  6897.7   95.35
#Mann= 10 ,-1 , 0
    4533     .05       0  4663.1      .1       0  4916.5     .12       0
  4994.9     .07       0  5004.1     .12       0  5168.6     .16       0
  5381.5     .05       0  5552.8     .16       0  5581.7     .05       0
  6286.1      .1       0
Bank Sta=4973.8,5040.3
XS Rating Curve= 0 ,0
Exp/Cntr=0.3,0.1

Type RM Length L Ch R = 1 ,23313   ,449,449,449
BEGIN DESCRIPTION:
BAYOU CREEK 32.0
END DESCRIPTION:
XS GIS Cut Line= 3
       2368412.1     13207069.23      2367512.32     13207694.96
      2366644.27     13208675.85
#Sta/Elev= 30
  4328.1  104.27    4488  101.59  4565.7  100.17  4601.5   99.22  4738.5   92.48
  4783.1   89.64  4845.9   80.52  4905.3   74.63  4918.1   73.62  4968.1   71.72
  4976.8   71.61  4991.2   65.27  4997.5   63.95  5000.8   64.45  5012.6   65.45
  5018.7   69.71  5048.4   73.26  5054.5   72.78  5105.1   71.11  5134.8    73.2
  5198.2   71.67  5227.3   71.32    5320   69.47  5423.8   72.35  5527.9   72.94
  5711.9   71.14  5960.4   75.94  6087.5   79.23  6519.9   94.62  6733.9   97.38
#Mann= 13 ,-1 , 0
  4328.1     .05       0    4488     .05       0  4565.7      .1       0
  4601.5     .05       0  4738.5      .1       0  4845.9     .05       0
  4905.3      .1       0  4968.1     .05       0  5000.8     .04       0
  5012.6     .05       0  5198.2     .12       0  5227.3     .05       0
  5960.4      .1       0
Bank Sta=4918.1,5054.5
XS Rating Curve= 0 ,0
Exp/Cntr=0.3,0.1

Type RM Length L Ch R = 1 ,22864   ,597,597,597
BEGIN DESCRIPTION:
BAYOU CREEK 31.0
END DESCRIPTION:
XS GIS Cut Line= 4
       2368179.4     13206945.11       2367714.1     13207111.78
      2366755.77     13207840.95      2366658.55     13208410.36
#Sta/Elev= 30
  4155.6  100.11    4338   95.37  4589.2   86.38  4729.8   78.76    4786   77.27
  4829.6   72.58  4858.7    72.6  4879.5   72.97  4921.7   70.38    4972   71.57
  4979.3   71.19  4985.6   63.53  5000.1   63.47  5008.1   62.86  5011.4   63.36
  5014.6   70.91  5035.5      71  5108.2   68.08  5158.1    69.1    5208   71.87
  5278.7   71.72  5343.1    69.5  5600.3   73.42  5686.2   75.45  5880.3   83.66
  5981.8   85.37    6134   90.03  6357.1   93.67  6397.7    94.9  6431.7   95.47
#Mann= 12 ,-1 , 0
  4155.6     .05       0    4338     .05       0  4589.2      .1       0
  4858.7     .12       0  5000.1     .07       0  5008.1     .12       0
  5158.1      .1       0  5278.7     .12       0  5600.3     .16       0
    6134      .1       0  6357.1     .16       0  6397.7      .1       0
Bank Sta=4972,5035.5
XS Rating Curve= 0 ,0
Exp/Cntr=0.3,0.1

Type RM Length L Ch R = 1 ,22267   ,377,377,377
BEGIN DESCRIPTION:
BAYOU CREEK 30.0
END DESCRIPTION:
XS GIS Cut Line= 3
      2368227.99     13206757.61      2367346.04     13206924.28
      2366214.06     13207340.96
#Sta/Elev= 30
  3665.5  100.97  3818.4   97.29  4066.5   90.58  4429.1   75.91  4611.6   72.54
  4697.6   68.75  4758.5   71.21  4900.2   69.98    4936   68.43  4976.9   70.32
  4991.6    68.9  4998.2   61.97  5005.8   60.95  5008.6   60.45  5011.8   60.95
  5016.7    66.9    5022   69.65  5047.1    70.3    5158   67.63  5243.3   71.87
  5341.1   77.59  5427.1   80.84    5467   84.49  5477.4   83.61  5513.2   86.73
  5552.3   88.65  5629.7   93.01  5679.9   93.83  5701.5   95.49  5769.3   97.86
#Mann= 9 ,-1 , 0
  3665.5     .05       0  3818.4     .05       0  4066.5      .1       0
  4611.6     .12       0  5005.8     .12       0  5243.3     .16       0
    5467      .1       0  5552.3     .16       0  5701.5      .1       0
Bank Sta=4976.9,5047.1
XS Rating Curve= 0 ,0
Exp/Cntr=0.3,0.1

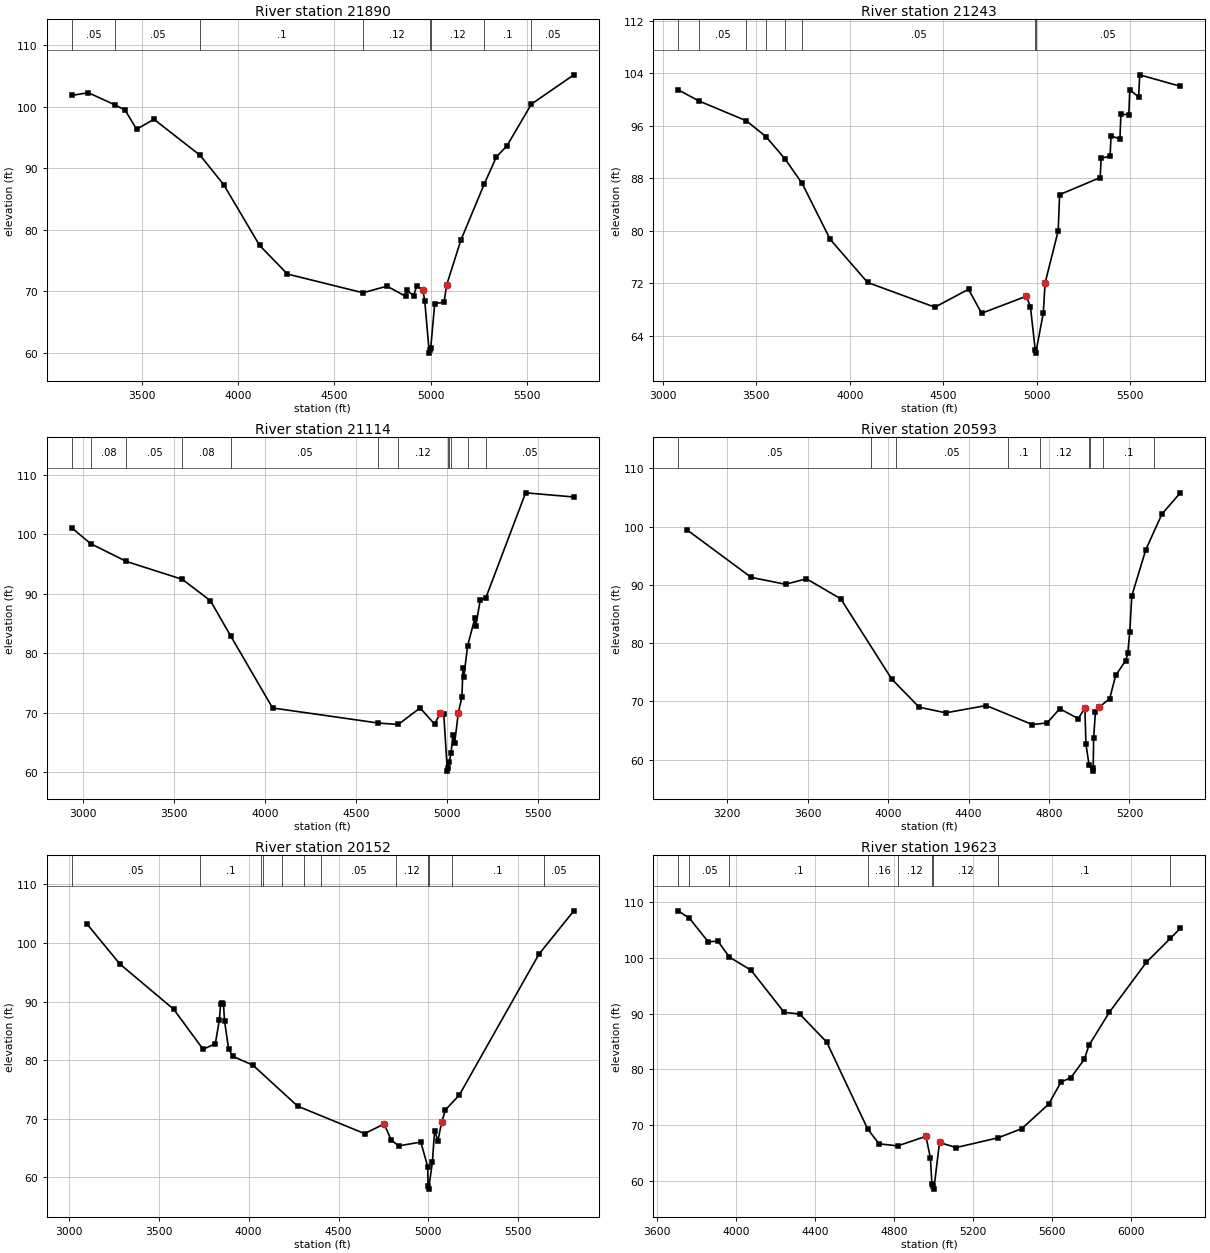
Type RM Length L Ch R = 1 ,21890   ,647,647,647
BEGIN DESCRIPTION:
BAYOU CREEK 29.0
END DESCRIPTION:
XS GIS Cut Line= 4
      2368464.07     13206577.06      2367748.82     13206570.12
      2366200.21     13206965.95      2365931.06     13207076.37
#Sta/Elev= 30
  3137.2  101.84  3223.6  102.27  3363.6  100.26  3413.6   99.45  3473.6   96.34
  3563.6   97.96  3803.6   92.09  3925.9   87.31  4111.7   77.47  4256.2   72.82
  4648.4   69.78  4772.2   70.86  4869.7    69.2  4875.4   70.16  4910.5   69.33
  4927.1   70.87    4958   70.24  4968.3    68.5  4991.9   59.98  4995.2   60.48
  4999.3   60.78    5020   68.01  5068.7   68.27  5081.9   71.05  5155.5   78.31
    5278   87.52  5339.9   91.84  5395.3   93.67  5521.5  100.42  5741.8  105.18
#Mann= 8 ,-1 , 0
  3137.2     .05       0  3363.6     .05       0  3803.6      .1       0
  4648.4     .12       0  4995.2     .07       0  4999.3     .12       0
    5278      .1       0  5521.5     .05       0
Bank Sta=4958,5081.9
XS Rating Curve= 0 ,0
Exp/Cntr=0.3,0.1

Type RM Length L Ch R = 1 ,21243   ,129,129,129
BEGIN DESCRIPTION:
BAYOU CREEK 28.0
END DESCRIPTION:
XS GIS Cut Line= 4
      2368296.15      13206470.9      2367674.51     13206333.34
      2366268.26     13206286.47      2365674.55     13206036.48
#Sta/Elev= 30
  3081.7  101.47  3192.8   99.78  3445.6   96.77  3551.2   94.36  3653.6   90.95
  3745.2   87.22  3895.3   78.71  4095.4   72.16  4455.6   68.39  4635.7   71.12
  4705.7   67.47  4945.8   70.06  4967.3   68.43  4992.9    61.9  4995.6    61.4
  5035.9   67.47  5045.9    72.1  5115.9   80.02  5123.2   85.52  5340.5   88.12
  5345.9   91.11  5393.4   91.33  5398.8   94.46  5446.3   94.01  5451.7   97.78
  5493.8   97.68  5499.2  101.49  5546.7  100.37  5552.1  103.76  5769.6  102.02
#Mann= 8 ,-1 , 0
  3081.7     .05       0  3192.8     .05       0  3445.6     .08       0
  3551.2     .05       0  3653.6     .08       0  3745.2     .05       0
  4992.9     .04       0  4995.6     .05       0
Bank Sta=4945.8,5045.9
XS Rating Curve= 0 ,0
Exp/Cntr=0.3,0.1

Type RM Length L Ch R = 1 ,21114   ,521,521,521
BEGIN DESCRIPTION:
Mapping XS 8d302372
END DESCRIPTION:
XS GIS Cut Line= 4
      2368438.89     13206390.85      2367653.68     13206203.13
      2366299.51     13206161.47      2365742.45     13205948.01
#Sta/Elev= 30
  2936.5   101.1  3040.5   98.44  3237.1   95.44  3544.3   92.43  3698.5   88.83
  3809.8    82.9  4039.9   70.78  4620.2   68.25  4730.3      68  4850.3   70.79
  4930.4   68.05  4960.4   69.88  4980.4   69.76  5000.1   60.15  5003.4   60.65
  5010.4   61.73  5020.4   63.15  5030.4   66.19  5040.4    64.9  5060.4   69.97
  5080.4   72.67  5085.7   77.46  5090.7   76.01  5111.3   81.22  5151.1   85.86
  5156.5   84.58  5181.1   89.02  5211.2   89.29  5430.1     107  5695.2   106.3
#Mann= 12 ,-1 , 0
  2936.5     .05       0  3040.5     .08       0  3237.1     .05       0
  3544.3     .08       0  3809.8     .05       0  4620.2      .1       0
  4730.3     .12       0  5003.4     .07       0  5010.4     .12       0
  5020.4      .1       0  5111.3     .12       0  5211.2     .05       0
Bank Sta=4960.4,5060.4
XS Rating Curve= 0 ,0
Exp/Cntr=0.3,0.1

Type RM Length L Ch R = 1 ,20593   ,441,441,441
BEGIN DESCRIPTION:
BAYOU CREEK 27.0
END DESCRIPTION:
XS GIS Cut Line= 3
      2368454.52     13206312.73      2366486.41     13205721.85
      2366086.41     13205721.85
#Sta/Elev= 30
  2998.1   99.48  3318.9   91.28  3489.4    90.1  3593.7   91.04  3764.2    87.6
    4018   73.81  4153.9      69  4286.1   68.03  4487.8   69.28  4717.5   66.01
  4790.6    66.3  4853.2   68.73  4945.3   67.04  4978.4   68.85  4983.6   62.65
  4999.4   59.04  5016.4   58.02  5019.7   58.52  5021.9    63.7  5030.7   68.11
  5049.5   69.01  5101.7   70.46  5131.7   74.47  5181.7   77.01  5191.7   78.26
  5201.7   81.97  5211.7   88.11  5281.7   96.07  5361.7  102.17    5453   105.8
#Mann= 9 ,-1 , 0
  2955.9     .05       0  3915.8      .1       0  4037.3     .05       0
  4597.6      .1       0  4754.9     .12       0  4997.3     .07       0
  5003.3     .12       0  5070.2      .1       0  5323.2     .05       0
Bank Sta=4978.4,5049.5
XS Rating Curve= 0 ,0
Exp/Cntr=0.3,0.1

Type RM Length L Ch R = 1 ,20152   ,529,529,529
BEGIN DESCRIPTION:
Mapping XS 473ce4c6
END DESCRIPTION:
XS GIS Cut Line= 4
      2368626.41     13206271.07      2367190.14     13205578.13
       2366669.3     13205421.88      2366152.56     13205661.62
#Sta/Elev= 30
  3101.2  103.22  3283.2   96.42  3582.7   88.69  3746.5   81.85  3814.4   82.81
    3837   86.89  3843.6   89.62    3854   89.81  3859.6   89.54  3865.9   86.62
  3888.1   81.98  3910.3   80.66  4023.4   79.15  4272.1   72.15    4645   67.45
  4754.2    69.1  4792.5   66.38  4834.1   65.35  4957.8   66.01  4996.1   61.81
  4998.3   58.47    5001   57.97  5022.1   62.55  5034.3   67.85  5053.4   66.27
  5074.3    69.5  5095.1   71.51  5171.8   74.03  5615.2    98.1  5809.3   105.5
#Mann= 12 ,-1 , 0
  3015.6     .05       0  3730.9      .1       0  4070.6     .12       0
    4081      .1       0    4187     .05       0  4307.3      .1       0
  4401.9     .05       0  4819.6     .12       0  4998.6     .07       0
  5004.6     .12       0  5129.8      .1       0  5645.7     .05       0
Bank Sta=4754.2,5074.3
XS Rating Curve= 0 ,0
Exp/Cntr=0.3,0.1

Type RM Length L Ch R = 1 ,19623   ,520,520,520
BEGIN DESCRIPTION:
Mapping XS 7470d99e
END DESCRIPTION:
XS GIS Cut Line= 4
      2368466.16      13204927.1      2367804.72     13205338.55
      2367070.35     13205192.72      2366152.54     13205630.38
#Sta/Elev= 30
  3707.4  108.45  3764.4  107.11  3858.7  102.91  3908.7  102.99  3966.5  100.15
  4076.3   97.79    4244   90.23    4323   89.92    4460   84.87  4666.8   69.33
  4724.5   66.63  4819.8   66.25  4962.5   67.97  4985.4   64.09  4993.1   59.34
  5000.3   58.99    5003   58.49  5031.5   66.87  5115.4   65.95  5329.1   67.71
  5448.5   69.35  5584.3   73.73  5646.8   77.68  5697.7   78.52  5765.8   81.81
  5788.5   84.28  5891.6   90.21    6080   99.21  6201.8  103.51  6251.9  105.29
#Mann= 9 ,-1 , 0
  3707.4     .05       0  3764.4     .05       0  3966.5      .1       0
  4666.8     .16       0  4819.8     .12       0  4993.1     .07       0
  5000.3     .12       0  5329.1      .1       0  6201.8     .05       0
Bank Sta=4962.5,5031.5
XS Rating Curve= 0 ,0
Exp/Cntr=0.3,0.1

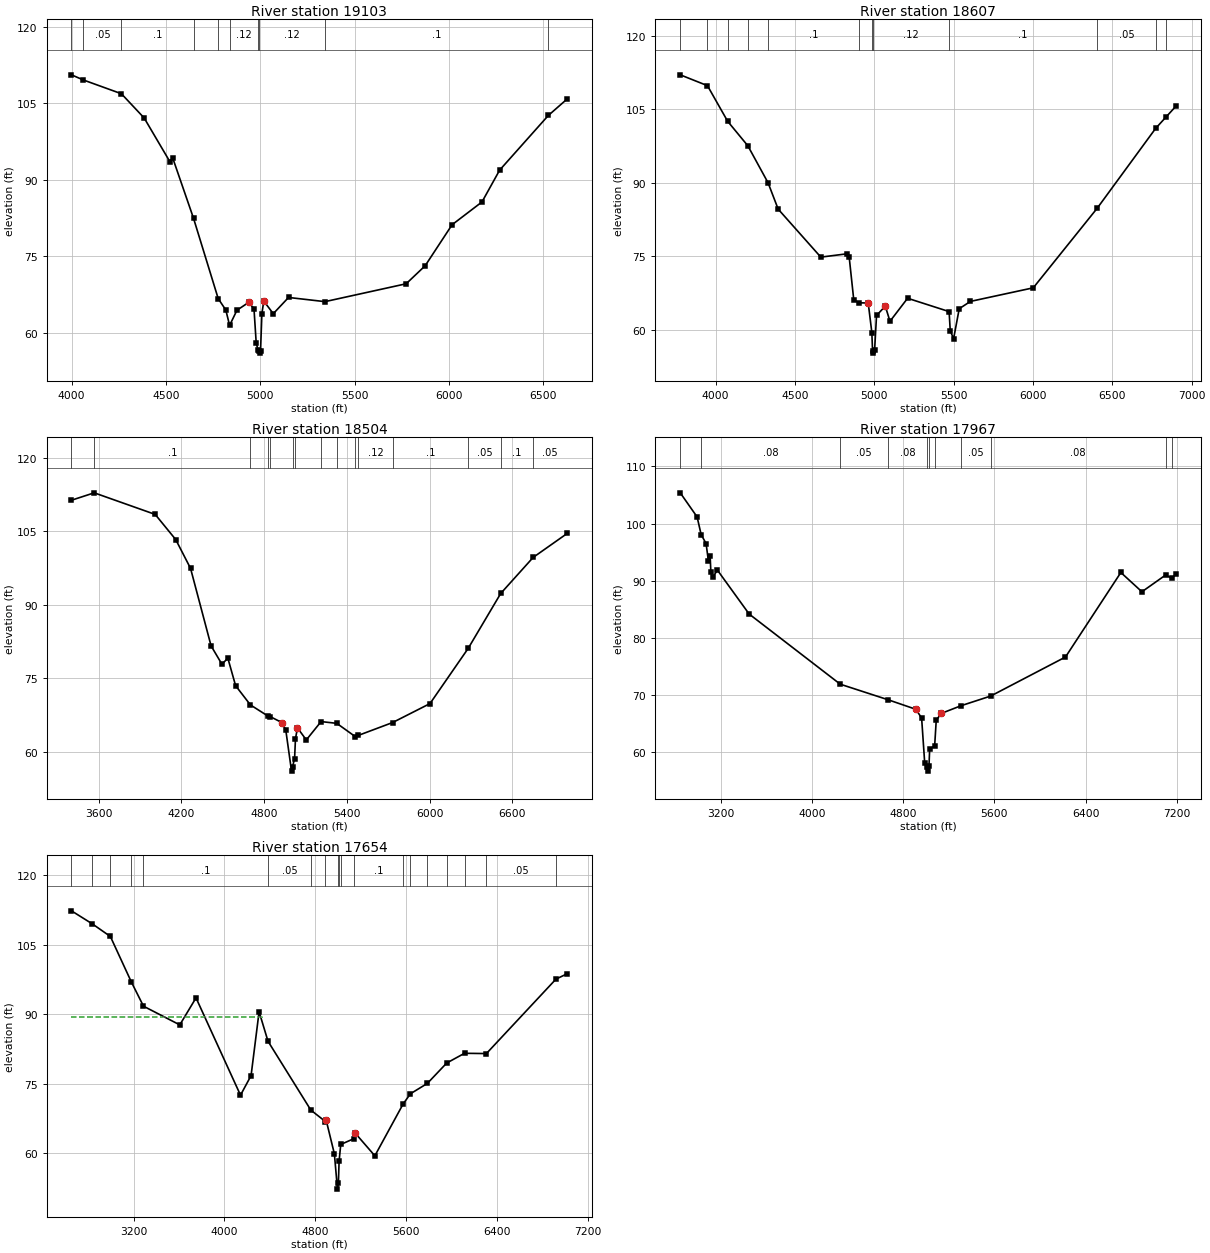
Type RM Length L Ch R = 1 ,19103   ,496,496,496
BEGIN DESCRIPTION:
Mapping XS 5216ed63
END DESCRIPTION:
XS GIS Cut Line= 3
      2368480.57     13204870.02      2367365.97     13204745.02
      2366139.38     13205619.17
#Sta/Elev= 30
  3999.4  110.54  4062.6  109.53  4263.9  106.84  4384.7  102.09  4520.9   93.54
  4535.6    94.3  4646.3   82.45  4777.1   66.72  4817.4   64.49  4837.5   61.48
  4876.4   64.45  4938.1   65.97  4966.6   64.78  4978.4   58.07  4988.4    56.6
  4995.5   56.55  4998.2   56.05  5001.5   56.55  5008.5   63.76  5018.6   66.25
  5068.9   63.77  5149.8   66.95  5342.8   66.13  5773.1   69.63  5873.9   73.16
  6016.5   81.19  6174.9   85.65  6268.5   91.88  6526.7  102.59  6627.2  105.84
#Mann= 10 ,-1 , 0
  3999.4     .05       0  4062.6     .05       0  4263.9      .1       0
  4646.3     .12       0  4777.1      .1       0  4837.5     .12       0
  4988.4     .07       0  4995.5     .12       0  5342.8      .1       0
  6526.7     .05       0
Bank Sta=4938.1,5018.6
XS Rating Curve= 0 ,0
Exp/Cntr=0.3,0.1

Type RM Length L Ch R = 1 ,18607   ,103,103,103
BEGIN DESCRIPTION:
BAYOU CREEK 26.0
END DESCRIPTION:
XS GIS Cut Line= 4
      2368470.16     13204797.12       2367824.3      13204172.1
      2367355.55     13204390.85      2366128.97     13205580.97
#Sta/Elev= 30
    3777  112.02  3948.5  109.81  4075.9  102.54  4203.2   97.54  4330.5      90
  4394.1   84.63  4662.9   74.84  4826.5   75.51  4841.9    74.8  4870.6   66.12
  4903.7   65.52  4961.7   65.49  4984.5   59.46    4989   55.76  4991.8   55.26
  5001.9   55.83  5014.1   62.94  5069.3   64.85  5098.8   61.75  5209.9   66.45
  5471.5   63.73  5478.7   59.81  5499.8    58.2  5535.3   64.32    5606   65.81
  6001.9   68.58    6405   84.82  6772.8  101.08  6836.4  103.34  6902.1  105.66
#Mann= 12 ,-1 , 0
    3777     .05       0  3948.5     .05       0  4075.9      .1       0
  4203.2     .05       0  4330.5      .1       0  4903.7     .12       0
  4984.5     .07       0    4989     .12       0  5471.5      .1       0
    6405     .05       0  6772.8      .1       0  6836.4     .05       0
Bank Sta=4961.7,5069.3
XS Rating Curve= 0 ,0
Exp/Cntr=0.3,0.1

Type RM Length L Ch R = 1 ,18504   ,537,537,537
BEGIN DESCRIPTION:
BAYOU CREEK 25.0
END DESCRIPTION:
XS GIS Cut Line= 2
      2368706.16     13203242.54      2365893.78     13205482.02
#Sta/Elev= 30
  3403.9  111.29  3568.9   112.8    4011   108.4  4159.9  103.27  4267.2   97.41
  4416.2    81.6  4494.6   77.87  4537.9   79.09  4593.9   73.49  4701.3   69.57
  4829.4   67.28  4843.8    67.2  4928.7   65.98  4957.5    64.5  4999.5   56.07
  5007.2      57  5021.6   58.63    5028   62.66  5042.4   64.89  5106.5   62.43
  5213.8   66.17  5327.5   65.81    5462    63.1  5484.4   63.36  5732.7   65.98
  6003.4   69.84  6280.4    81.1  6515.9   92.28  6751.1   99.63    6999  104.54
#Mann= 15 ,-1 , 0
  3403.9     .05       0  3568.9      .1       0  4701.3     .12       0
  4829.4     .05       0  4843.8     .12       0  5007.2     .07       0
  5021.6     .12       0  5213.8      .1       0  5327.5     .12       0
    5462      .1       0  5484.4     .12       0  5732.7      .1       0
  6280.4     .05       0  6515.9      .1       0  6751.1     .05       0
Bank Sta=4928.7,5042.4
XS Rating Curve= 0 ,0
Exp/Cntr=0.3,0.1

Type RM Length L Ch R = 1 ,17967   ,313,313,313
BEGIN DESCRIPTION:
Mapping XS e15a9df4
END DESCRIPTION:
XS GIS Cut Line= 2
       2368718.7     13202640.57      2365288.14     13205307.25
#Sta/Elev= 30
    2847  105.36  2994.8  101.15  3030.1   98.07  3073.5   96.49  3094.4   93.37
  3108.8    94.4  3115.2   91.56  3129.7   90.58  3173.1   91.84  3450.9   84.18
  4249.1   71.92  4669.9   69.19  4912.4   67.53  4962.2      66  4989.4   58.07
    5012   57.52  5018.1   56.73  5026.5   57.58  5032.8   60.64  5076.2   61.09
  5090.1   65.58    5132    66.8  5310.6   68.18  5567.6   69.85  6222.8   76.67
  6707.9   91.44  6892.5   88.07  7099.7   90.99  7155.8   90.44  7192.1   91.19
#Mann= 11 ,-1 , 0
    2847     .05       0  3030.1     .08       0  4249.1     .05       0
  4669.9     .08       0    5012     .08       0  5026.5     .05       0
  5076.2     .08       0  5310.6     .05       0  5567.6     .08       0
  7099.7      .1       0  7155.8     .08       0
Bank Sta=4912.4,5132
XS Rating Curve= 0 ,0
Exp/Cntr=0.3,0.1

Type RM Length L Ch R = 1 ,17654   ,649,649,649
BEGIN DESCRIPTION:
BAYOU CREEK 24.0
END DESCRIPTION:
XS GIS Cut Line= 2
      2368568.98     13202478.23      2365118.47     13205158.35
#Sta/Elev= 30
  2652.6  112.35  2837.8  109.51  2995.3  106.82  3179.9   97.02  3287.3   91.77
  3607.1   87.74  3750.1   93.57    4142   72.57  4235.2    76.8  4305.8   90.58
  4384.5    84.2  4761.9   69.35  4890.5   66.88  4896.8   67.18  4969.2   59.91
  4996.4    52.3  5004.5   53.59  5010.8   58.33  5025.3   61.94  5139.4   63.17
  5153.8   64.35  5325.8   59.49  5574.7   70.66  5638.9   72.87  5788.3   75.11
    5959   79.51  6115.9   81.61  6308.7   81.55  6921.3   97.61  7021.7   98.79
#Mann= 19 ,-1 , 0
  2652.6     .05       0  2837.8     .05       0  2995.3      .1       0
  3179.9      .1       0  3287.3      .1       0  4384.5     .05       0
  4761.9      .1       0  4890.5     .12       0  5004.5     .07       0
  5010.8     .12       0  5025.3     .12       0  5139.4      .1       0
  5574.7     .16       0  5638.9      .1       0  5788.3      .1       0
    5959      .1       0  6115.9      .1       0  6308.7     .05       0
  6921.3     .05       0
#XS Ineff= 2 , 0
         4328.41    89.4
Permanent Ineff=
       F       F
Bank Sta=4896.8,5153.8
XS Rating Curve= 0 ,0
Exp/Cntr=0.3,0.1