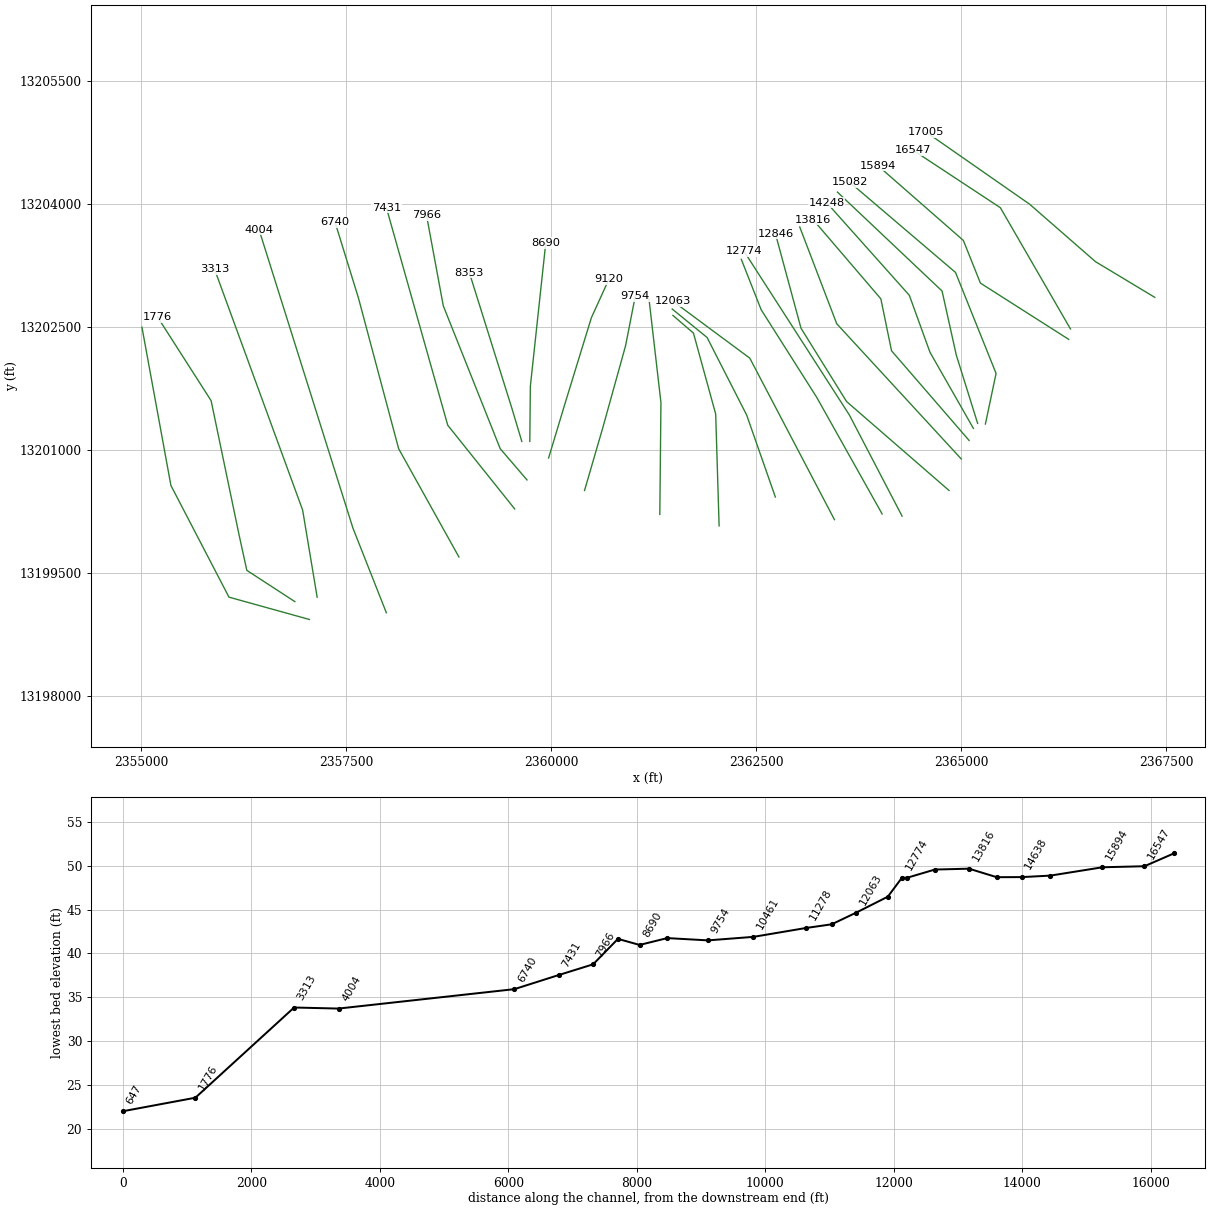
HEC-RAS study BAYOU CREEK.prj: BAYOU CREEK Base Level Engineering

--- BAYOU CREEK.g01 (geometry) --- (continued)

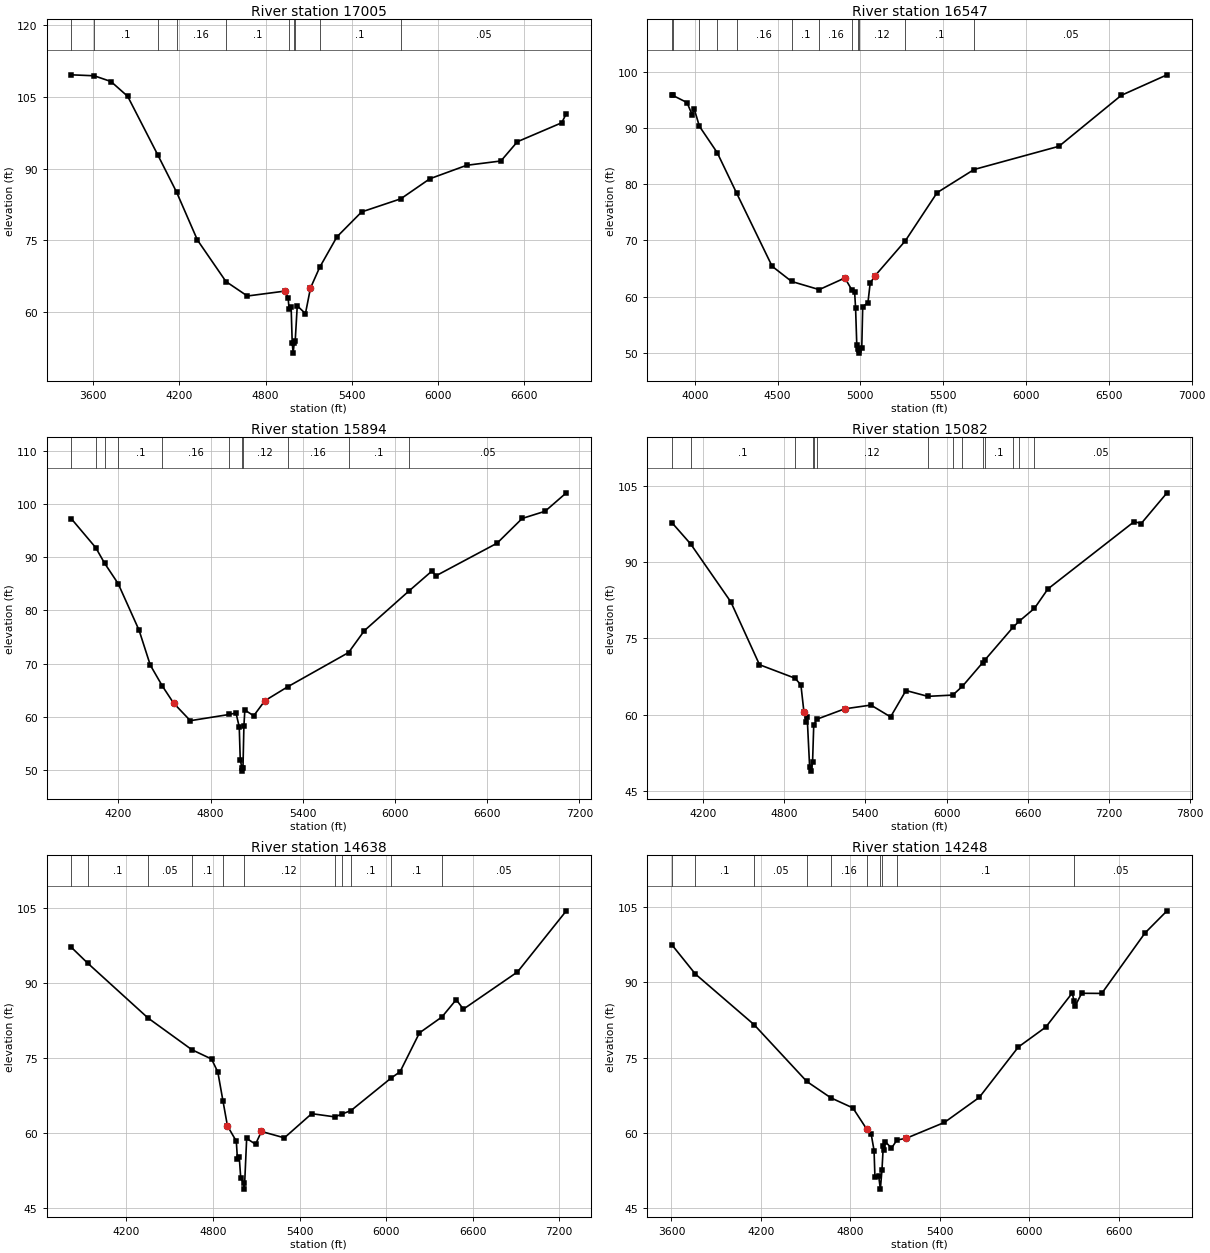
Type RM Length L Ch R = 1 ,17005   ,458,458,458
BEGIN DESCRIPTION:
BAYOU CREEK 23.0
END DESCRIPTION:
XS GIS Cut Line= 4
      2367364.55     13202857.58      2366641.63     13203292.62
      2365837.76     13203993.93       2364578.1     13204871.45
#Sta/Elev= 30
  3448.3  109.67    3607  109.47  3723.5  108.27    3840  105.17  4051.5   92.79
  4180.1   85.14  4325.8   75.07  4524.2   66.39  4673.3   63.36  4935.3   64.39
  4957.1   62.95  4963.8   60.71    4978   61.09  4985.6   53.58    4992    51.4
  4999.9   53.57  5006.5   54.01  5020.7   61.31  5077.7   59.67  5112.8   65.03
  5176.4   69.34    5297   75.75  5468.6   80.96  5741.4   83.71  5943.9   87.91
  6200.4   90.73  6438.6   91.63  6553.2   95.66  6861.9   99.63    6894  101.55
#Mann= 10 ,-1 , 0
  3448.3     .05       0    3607      .1       0  4051.5     .05       0
  4180.1     .16       0  4524.2      .1       0  4963.8     .12       0
  4999.9     .07       0  5006.5     .12       0  5176.4      .1       0
  5741.4     .05       0
Bank Sta=4935.3,5112.8
XS Rating Curve= 0 ,0
Exp/Cntr=0.3,0.1

Type RM Length L Ch R = 1 ,16547   ,653,653,653
BEGIN DESCRIPTION:
BAYOU CREEK 22.0
END DESCRIPTION:
XS GIS Cut Line= 3
      2366336.42     13202471.83      2365480.87     13203951.33
      2364413.15     13204654.46
#Sta/Elev= 30
  3863.7   95.76  3867.4   95.76  3953.6   94.48    3985   92.28  3996.6   93.41
  4028.2   90.28  4135.9   85.58  4253.6   78.35  4467.4   65.38  4585.1   62.68
  4751.6   61.23  4906.6    63.3  4949.7   61.12  4965.5   60.75  4971.2   57.97
  4978.5    51.4    4987   50.63  4989.8   50.44  4992.5   49.94  5008.5   50.86
  5014.3   58.21  5045.8    58.9  5059.3   62.38  5088.9    63.7  5271.2   69.89
  5463.5   78.47  5686.5   82.58  6199.2   86.71    6575   95.76  6851.2   99.41
#Mann= 12 ,-1 , 0
  3863.7     .05       0  3867.4     .05       0  4028.2     .05       0
  4135.9      .1       0  4253.6     .16       0  4585.1      .1       0
  4751.6     .16       0  4949.7     .12       0    4987     .07       0
  4989.8     .12       0  5271.2      .1       0  5686.5     .05       0
Bank Sta=4906.6,5088.9
XS Rating Curve= 0 ,0
Exp/Cntr=0.3,0.1

Type RM Length L Ch R = 1 ,15894   ,812,812,812
BEGIN DESCRIPTION:
Mapping XS c892ce83
END DESCRIPTION:
XS GIS Cut Line= 4
      2366314.21     13202345.42      2365237.81     13203031.19
      2365029.48     13203552.02      2363988.77     13204462.64
#Sta/Elev= 30
  3894.3   97.19  4052.7   91.77  4110.2   88.85  4198.3   85.03  4334.6   76.27
  4407.3   69.74  4486.1   65.79  4558.9    62.6  4668.1   59.29  4921.7   60.46
  4965.2   60.74  4986.3   58.12  4992.8      52  5004.5   50.32  5007.2   49.82
  5010.5   50.32  5016.6   58.24  5022.7   61.29  5080.3   60.21  5153.1   63.04
  5300.7   65.64  5697.5   72.08  5800.3   76.19  6090.9   83.65  6238.9   87.36
  6267.4   86.51  6664.1   92.62  6827.4   97.26  6976.4   98.61  7114.4  102.07
#Mann= 11 ,-1 , 0
  3894.3     .05       0  4052.7      .1       0  4110.2     .05       0
  4198.3      .1       0  4486.1     .16       0  4921.7     .12       0
  5004.5     .07       0  5010.5     .12       0  5300.7     .16       0
  5697.5      .1       0  6090.9     .05       0
Bank Sta=4558.9,5153.1
XS Rating Curve= 0 ,0
Exp/Cntr=0.3,0.1

Type RM Length L Ch R = 1 ,15082   ,444,444,444
BEGIN DESCRIPTION:
BAYOU CREEK 21.0
END DESCRIPTION:
XS GIS Cut Line= 4
      2365298.57     13201312.41      2365428.64     13201929.63
      2364933.99      13203161.4      2363642.83     13204261.92
#Sta/Elev= 30
  3972.6   97.77    4110    93.6  4406.4    82.2  4617.9   69.83  4880.6   67.17
  4923.7   65.85  4945.9   60.56  4964.8   58.47  4970.1   59.46  4988.3   49.61
  4999.5   48.87  5009.9   50.72  5018.5   57.97  5042.2    59.1    5247   61.14
  5440.9   61.88  5585.9   59.55  5699.6   64.75  5860.7    63.6    6045   63.85
  6116.4   65.58  6265.8   70.23    6280   70.69  6491.9   77.26  6534.8   78.38
  6648.5   80.94  6747.8   84.76  7385.7   98.03  7436.3   97.63  7627.3  103.69
#Mann= 14 ,-1 , 0
  3972.6     .05       0    4110      .1       0  4880.6     .16       0
  5009.9     .07       0  5018.5     .16       0  5042.2     .12       0
  5860.7      .1       0    6045     .16       0  6116.4      .1       0
  6265.8     .16       0    6280      .1       0  6491.9     .16       0
  6534.8      .1       0  6648.5     .05       0
Bank Sta=4945.9,5247
XS Rating Curve= 0 ,0
Exp/Cntr=0.3,0.1

Type RM Length L Ch R = 1 ,14638   ,390,390,390
BEGIN DESCRIPTION:
BAYOU CREEK 20.0
END DESCRIPTION:
XS GIS Cut Line= 4
      2365203.82     13201320.24       2364943.4     13202153.58
      2364769.78     13202934.83      2363493.72     13204141.45
#Sta/Elev= 30
  3818.9   97.11  3930.6   93.98  4349.7   82.97  4653.5   76.62    4790   74.75
  4833.5   72.15  4869.5    66.3  4900.2   61.36  4961.7   58.29  4969.2   54.79
  4982.2   55.05  4992.4   50.88  5012.8   49.95  5017.7    48.7  5033.4   58.85
  5094.9   57.69  5135.8   60.25  5294.5   58.97  5484.1   63.81  5643.9   63.17
  5693.2   63.72  5756.7   64.44  6032.6    70.9  6096.5   72.21  6230.8   79.99
  6386.6   83.18  6485.7   86.64  6535.1   84.74  6910.1   92.19  7248.5  104.43
#Mann= 11 ,-1 , 0
  3818.9     .05       0  3930.6      .1       0  4349.7     .05       0
  4653.5      .1       0  4869.5     .12       0  5012.8     .12       0
  5643.9     .16       0  5693.2     .12       0  5756.7      .1       0
  6032.6      .1       0  6386.6     .05       0
Bank Sta=4900.2,5135.8
XS Rating Curve= 0 ,0
Exp/Cntr=0.3,0.1

Type RM Length L Ch R = 1 ,14248   ,432,432,432
BEGIN DESCRIPTION:
BAYOU CREEK 19.0
END DESCRIPTION:
XS GIS Cut Line= 4
      2365151.73     13201259.49      2364622.21     13202188.31
      2364370.48     13202882.75      2363363.55      13204011.2
#Sta/Elev= 30
  3604.2   97.47  3760.1   91.69  4153.7   81.58  4507.8   70.21  4669.1   66.94
    4817   64.92  4908.9   60.72  4939.5   59.73    4959   56.41  4964.8    51.2
  4990.1   51.27  5001.3   48.69  5012.2   52.58  5020.7   57.22  5026.1   56.52
  5033.5    58.2    5076   56.88  5112.6   58.51  5173.9   58.84  5430.9   62.02
  5664.7   67.02  5926.8   77.09  6111.2   81.08  6288.4   87.89  6300.8   86.28
  6309.3   85.36  6351.9   87.84  6486.5   87.81  6776.7   99.89  6924.4  104.32
#Mann= 10 ,-1 , 0
  3604.2     .05       0  3760.1      .1       0  4153.7     .05       0
  4507.8      .1       0  4669.1     .16       0  4908.9     .12       0
  5001.3     .07       0  5012.2     .12       0  5112.6      .1       0
  6300.8     .05       0
Bank Sta=4908.9,5173.9
XS Rating Curve= 0 ,0
Exp/Cntr=0.3,0.1

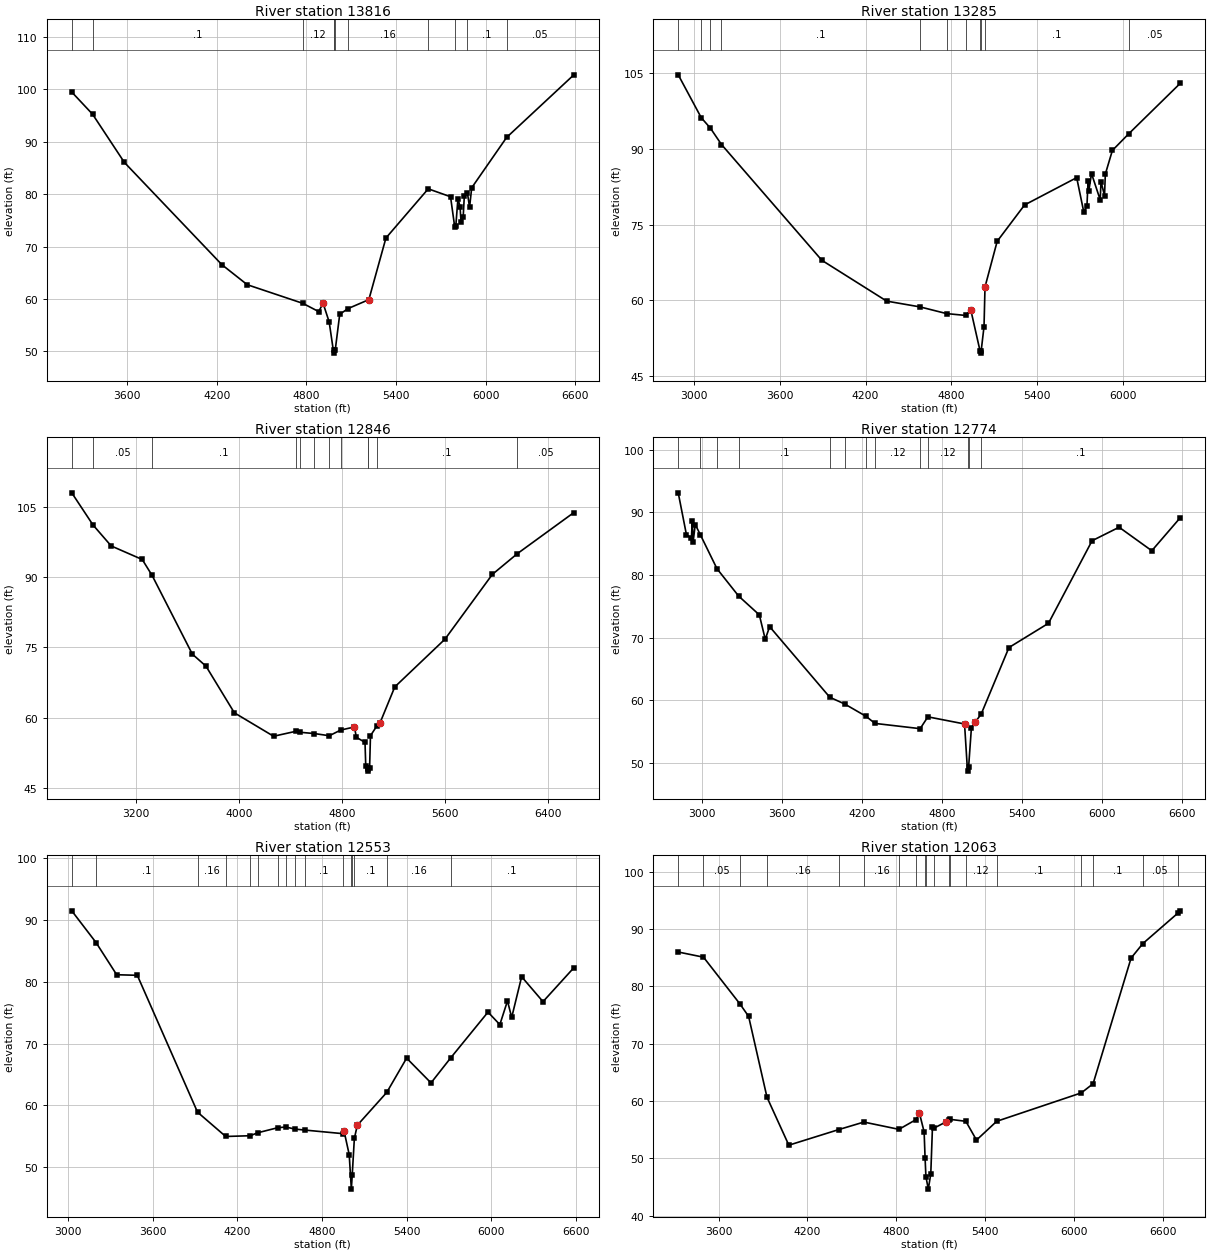
Type RM Length L Ch R = 1 ,13816   ,531,531,531
BEGIN DESCRIPTION:
Mapping XS cf132123
END DESCRIPTION:
XS GIS Cut Line= 4
      2365099.68     13201111.88      2364153.46     13202205.67
      2364023.26     13202839.35      2363199.02      13203802.4
#Sta/Elev= 30
    3230   99.49  3369.2   95.26  3581.9   86.07  4234.5   66.55  4404.5   62.72
  4776.9   59.16  4882.7   57.59  4912.3   59.17  4953.1    55.6  4983.5   49.66
  4987.6   50.18    4994   50.33  5023.6   57.07  5079.1   58.16  5218.6   59.87
  5332.9   71.63  5616.1   81.02  5765.4   79.51  5793.8   73.66  5800.6   73.88
  5814.8   79.13  5829.1   77.64  5835.7   74.67  5849.9   75.56  5857.6   79.63
  5878.5   80.21  5892.8    77.5    5907   81.22  6140.8   90.83  6590.8  102.78
#Mann= 11 ,-1 , 0
    3230     .05       0  3369.2      .1       0  4776.9     .12       0
  4983.5     .07       0  4987.6     .12       0    4994      .1       0
  5079.1     .16       0  5616.1      .1       0  5793.8     .16       0
  5878.5      .1       0  6140.8     .05       0
Bank Sta=4912.3,5218.6
XS Rating Curve= 0 ,0
Exp/Cntr=0.3,0.1

Type RM Length L Ch R = 1 ,13285   ,439,439,439
BEGIN DESCRIPTION:
BAYOU CREEK 18.0
END DESCRIPTION:
XS GIS Cut Line= 3
      2365004.18      13200886.2      2363485.06     13202535.53
      2363033.68     13203716.06
#Sta/Elev= 30
  2892.2  104.67  3053.1   96.17  3116.6   94.12  3194.3   90.87  3895.2   67.94
  4347.8   59.86  4581.4   58.71  4765.7   57.39  4900.1   57.02  4935.3   58.11
  4999.4   50.06  5003.1   50.06  5005.9   49.56  5027.6   54.81  5034.5   62.67
  5119.6   71.71  5310.8    78.9  5674.8   84.31  5724.3    77.5  5746.2   78.65
  5754.3   83.62  5759.7   81.75  5778.3   85.12  5839.1    79.9  5844.5   83.53
  5869.2   80.76  5874.7      85    5924    89.7  6038.8   93.01  6398.4     103
#Mann= 11 ,-1 , 0
  2892.2     .05       0  3053.1      .1       0  3116.6     .05       0
  3194.3      .1       0  4581.4      .1       0  4765.7     .16       0
  4900.1     .12       0  4999.4     .07       0  5003.1     .12       0
  5034.5      .1       0  6038.8     .05       0
Bank Sta=4935.3,5034.5
XS Rating Curve= 0 ,0
Exp/Cntr=0.3,0.1

Type RM Length L Ch R = 1 ,12846   ,72,72,72
BEGIN DESCRIPTION:
BAYOU CREEK 17.0
END DESCRIPTION:
XS GIS Cut Line= 4
      2364854.84     13200501.69      2363604.85     13201586.74
       2363049.3     13202480.84      2362737.28     13203633.58
#Sta/Elev= 30
  2700.4  107.97  2865.3  101.12  3006.8   96.64    3248   93.75  3324.8   90.35
  3637.3   73.57  3743.7   70.99    3964   61.05  4268.8   56.05  4439.8   57.09
  4470.5   56.91  4586.2   56.62  4701.9   56.16  4790.5   57.37  4897.3   58.03
  4912.1   55.84  4979.4   54.73  4985.3   49.68  5000.6   49.23  5003.5   49.11
  5006.3   48.61  5015.1    49.3  5021.9   56.17  5073.9   58.34  5095.1   58.83
  5210.8   66.57    5601   76.76    5969   90.57  6163.1   94.99  6602.5  103.76
#Mann= 12 ,-1 , 0
  2700.4     .05       0  2865.3     .05       0  3324.8      .1       0
  4439.8     .12       0  4470.5      .1       0  4586.2      .1       0
  4701.9     .16       0  4790.5     .12       0  5000.6     .07       0
  5003.5     .12       0  5073.9      .1       0  6163.1     .05       0
Bank Sta=4897.3,5095.1
XS Rating Curve= 0 ,0
Exp/Cntr=0.3,0.1

Type RM Length L Ch R = 1 ,12774   ,221,221,221
BEGIN DESCRIPTION:
Mapping XS 7e0a8154
END DESCRIPTION:
XS GIS Cut Line= 3
      2364281.94     13200189.17      2363639.58     13201421.81
      2362354.87     13203418.31
#Sta/Elev= 30
  2823.5   93.14  2884.8   86.46  2922.4   85.88    2929   88.71  2934.6   85.22
  2951.1   88.07  2989.7   86.42  3114.1      81  3276.9   76.62  3431.6   73.62
  3475.8   69.72  3508.7   71.74  3959.8   60.45  4071.9   59.37  4231.7    57.4
  4298.4   56.27  4637.2   55.43  4695.1   57.32    4970   56.18  4992.2   48.64
  5000.3   49.24  5021.5   55.59  5051.8   56.54  5094.1   57.73  5302.8    68.4
  5599.2   72.28  5926.1   85.48  6128.8   87.64  6373.8   83.88  6587.6   89.17
#Mann= 13 ,-1 , 0
  2823.5     .05       0  2989.7      .1       0  3114.1     .16       0
  3276.9      .1       0  3959.8     .16       0  4071.9      .1       0
  4231.7     .16       0  4298.4     .12       0  4637.2      .1       0
  4695.1     .12       0  4992.2     .07       0  5000.3     .12       0
  5094.1      .1       0
Bank Sta=4970,5051.8
XS Rating Curve= 0 ,0
Exp/Cntr=0.3,0.1

Type RM Length L Ch R = 1 ,12553   ,490,490,490
BEGIN DESCRIPTION:
BAYOU CREEK 16.0
END DESCRIPTION:
XS GIS Cut Line= 4
      2364038.88     13200215.22      2363240.27     13201638.83
      2362563.19     13202706.53      2362321.02     13203321.03
#Sta/Elev= 30
  3027.4   91.45  3199.5   86.32  3345.6   81.12  3491.7   81.03  3918.4   58.91
    4118   54.98  4291.5    55.1  4345.1   55.58  4485.5   56.39  4542.8   56.51
  4609.8   56.17  4681.1   56.01  4950.7   55.43  4956.6   55.84    4993   52.05
  5008.1   46.47  5014.2   48.68  5029.5   54.67  5050.7    56.8  5259.3   62.11
  5399.7   67.64  5572.6   63.64  5711.2   67.66  5976.3   75.08  6060.2   73.06
  6114.3   76.89  6144.1   74.22  6214.6    80.8    6366   76.77  6584.5   82.25
#Mann= 16 ,-1 , 0
  3027.4     .05       0  3199.5      .1       0  3918.4     .16       0
    4118      .1       0  4291.5     .16       0  4345.1      .1       0
  4485.5     .16       0  4542.8      .1       0  4609.8     .16       0
  4681.1      .1       0  4950.7     .12       0  5008.1     .07       0
  5014.2     .12       0  5029.5      .1       0  5259.3     .16       0
  5711.2      .1       0
Bank Sta=4956.6,5050.7
XS Rating Curve= 0 ,0
Exp/Cntr=0.3,0.1

Type RM Length L Ch R = 1 ,12063   ,384,384,384
BEGIN DESCRIPTION:
Mapping XS d6374813
END DESCRIPTION:
XS GIS Cut Line= 3
      2363457.28     13200145.78       2362424.3     13202116.26
       2361486.8      13202810.7
#Sta/Elev= 30
  3327.7   85.99  3498.3   85.09  3743.9   76.96  3803.1   74.77  3927.3   60.67
  4074.8   52.32  4410.8   55.03  4581.6   56.35  4818.6   55.08  4934.6   56.79
  4956.6   57.95  4988.7   54.63  4995.1    50.1  5000.8   46.83  5016.9   44.66
  5033.6   47.31  5045.1   55.52  5055.6    55.3  5135.4   56.36    5158   56.76
  5165.9   56.82  5270.6   56.48  5342.4   53.21  5478.7   56.48  6050.7   61.44
    6130   63.03  6386.7   84.94    6466   87.46  6701.9   92.75  6719.2   93.17
#Mann= 19 ,-1 , 0
  3327.7     .05       0  3498.3     .05       0  3743.9      .1       0
  3927.3     .16       0  4410.8      .1       0  4581.6     .16       0
  4818.6      .1       0  4934.6     .12       0  4995.1     .07       0
  5000.8     .12       0  5055.6     .16       0    5158     .12       0
  5165.9     .16       0  5270.6     .12       0  5478.7      .1       0
  6050.7     .16       0    6130      .1       0    6466     .05       0
  6701.9     .08       0
Bank Sta=4956.6,5135.4
XS Rating Curve= 0 ,0
Exp/Cntr=0.3,0.1

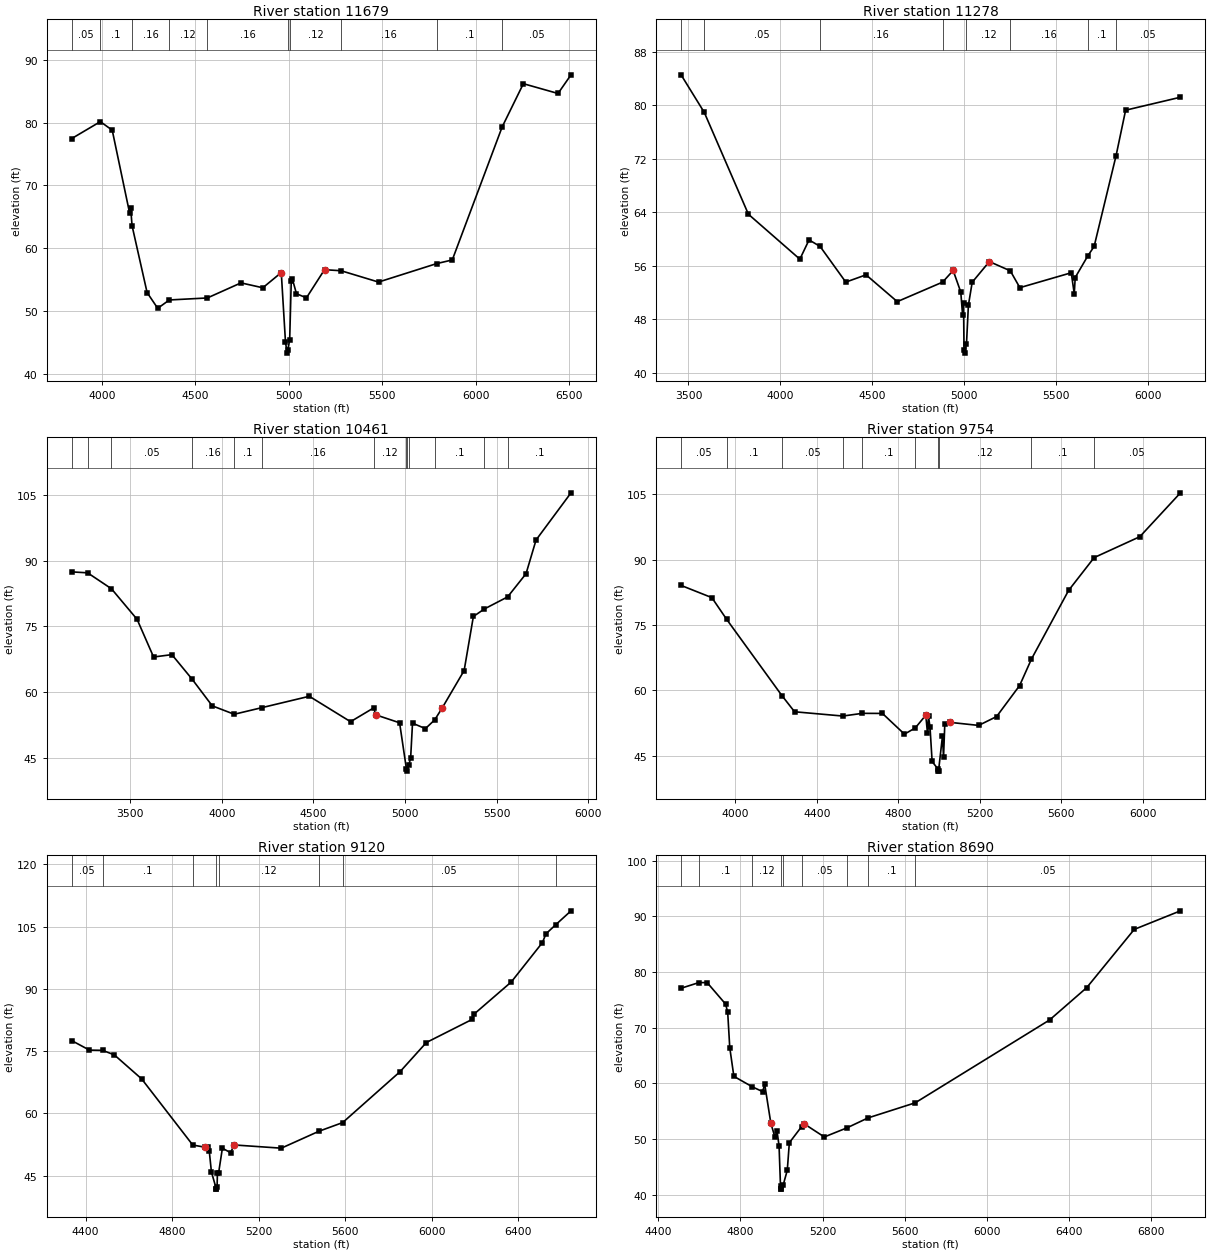
Type RM Length L Ch R = 1 ,11679   ,401,401,401
BEGIN DESCRIPTION:
BAYOU CREEK 15.0
END DESCRIPTION:
XS GIS Cut Line= 4
      2362736.39      13200421.9      2362386.41     13201421.85
      2361903.46     13202367.99       2361478.1     13202715.23
#Sta/Elev= 30
  3838.7   77.46  3992.3   80.16  4055.8    78.8  4149.2   65.55  4154.5   66.38
  4161.8   63.61  4242.3   52.96  4299.1   50.45  4361.1   51.78  4564.4    52.1
  4744.5    54.5  4861.1   53.72  4959.9   56.14  4982.3   45.15  4990.8   43.32
  4994.1   43.82  5004.8    45.4  5013.3   54.82  5018.9   55.16  5041.2   52.77
  5094.6   52.12  5191.1    56.6    5280   56.43    5480   54.63  5791.2   57.57
  5874.5   58.15  6141.3   79.32  6254.7    86.2    6440   84.64  6509.5   87.61
#Mann= 10 ,-1 , 0
  3838.7     .05       0  3992.3      .1       0  4161.8     .16       0
  4361.1     .12       0  4564.4     .16       0  4994.1     .07       0
  5004.8     .12       0    5280     .16       0  5791.2      .1       0
  6141.3     .05       0
Bank Sta=4959.9,5191.1
XS Rating Curve= 0 ,0
Exp/Cntr=0.3,0.1

Type RM Length L Ch R = 1 ,11278   ,817,817,817
BEGIN DESCRIPTION:
BAYOU CREEK 14.0
END DESCRIPTION:
XS GIS Cut Line= 4
      2362050.31     13200070.46      2362008.58     13201433.75
      2361737.31     13202421.44      2361486.94     13202637.04
#Sta/Elev= 30
  3459.7   84.52  3586.2   78.89  3826.3   63.67  4106.4   56.95  4156.4   59.83
  4216.5   58.86  4356.4   53.52  4466.6   54.61  4636.6    50.6  4883.7   53.52
  4940.9   55.26  4982.4   52.03  4992.2   48.62  4997.4    50.4  5000.1    43.4
  5002.9    42.9  5013.5   44.26  5023.9   50.06  5044.6    53.5    5138   56.59
    5252   55.21    5304   52.69  5583.9   54.92  5600.2   51.78  5605.4   54.21
  5674.2   57.45  5708.3   58.85  5827.5   72.39  5879.8   79.23  6178.3   81.17
#Mann= 8 ,-1 , 0
  3459.7     .05       0  3586.2     .05       0  4216.5     .16       0
  4883.7     .12       0  5013.5     .12       0    5252     .16       0
  5674.2      .1       0  5827.5     .05       0
Bank Sta=4940.9,5138
XS Rating Curve= 0 ,0
Exp/Cntr=0.3,0.1

Type RM Length L Ch R = 1 ,10461   ,707,707,707
BEGIN DESCRIPTION:
Mapping XS 088e2f8f
END DESCRIPTION:
XS GIS Cut Line= 4
      2361326.93     13200209.54      2361340.84     13201572.86
      2361194.77     13202838.78      2361132.41     13202901.14
#Sta/Elev= 30
  3180.5   87.44  3267.8   87.22  3397.8   83.58  3537.8   76.59  3627.8   67.98
  3727.8   68.52  3837.9   62.92  3947.9   56.82  4067.9   54.89  4217.9   56.39
  4477.9      59    4703   53.19  4829.8   56.36  4839.8   54.77  4970.7   52.94
    5008   42.39  5010.7   41.89    5021   43.24  5031.1   44.97  5041.2   52.85
  5111.6   51.61    5162   53.59  5202.2   56.26    5323   64.88  5373.4   77.24
  5433.8   78.97  5560.4   81.72  5660.9   87.02  5715.6   94.73  5906.4  105.51
#Mann= 13 ,-1 , 0
  3180.5     .05       0  3267.8      .1       0  3397.8     .05       0
  3837.9     .16       0  4067.9      .1       0  4217.9     .16       0
  4829.8     .12       0    5008      .1       0  5010.7     .07       0
    5021      .1       0    5162      .1       0  5433.8     .05       0
  5560.4      .1       0
Bank Sta=4839.8,5202.2
XS Rating Curve= 0 ,0
Exp/Cntr=0.3,0.1

Type RM Length L Ch R = 1 ,9754    ,634,634,634
BEGIN DESCRIPTION:
Mapping XS 210ff350
END DESCRIPTION:
XS GIS Cut Line= 4
       2360408.8     13200501.74      2360631.37     13201266.81
      2360909.59     13202268.42      2361027.66     13202872.67
#Sta/Elev= 30
  3732.9   84.07    3884   81.27  3956.7   76.29  4227.7   58.83  4290.2    55.1
  4527.1   54.12  4623.1   54.74  4721.6   54.72  4829.6   49.97  4882.6   51.38
  4934.5   54.31  4942.7   50.25  4947.9   54.04  4955.3   51.52  4965.6    43.7
  4993.8   41.99  4996.5   41.49    4997   41.49  5016.4   49.53  5021.6    44.7
  5027.9   52.36  5055.8   52.66    5194   51.97  5282.1      54  5395.2   61.11
  5453.4   67.19  5635.8   82.93  5761.2   90.45  5985.4   95.24  6184.9   105.3
#Mann= 10 ,-1 , 0
  3732.9     .05       0  3956.7      .1       0  4227.7     .05       0
  4527.1     .16       0  4623.1      .1       0  4882.6     .12       0
  4993.8     .07       0    4997     .12       0  5453.4      .1       0
  5761.2     .05       0
Bank Sta=4934.5,5055.8
XS Rating Curve= 0 ,0
Exp/Cntr=0.3,0.1

Type RM Length L Ch R = 1 ,9120    ,430,430,430
BEGIN DESCRIPTION:
Mapping XS 4874b057
END DESCRIPTION:
XS GIS Cut Line= 4
      2359970.58     13200898.13      2360165.34     13201545.03
      2360492.26     13202609.24       2360707.8     13203082.05
#Sta/Elev= 30
  4335.3   77.56  4417.5   75.26  4478.2    75.2  4532.4   74.12  4658.9   68.32
  4895.2   52.38  4950.1   51.87  4966.4   51.92  4971.7   50.84  4981.5   45.89
  5004.4   41.75  5004.9   41.75  5007.7   42.25  5009.2   45.58  5014.5   45.58
  5032.2   51.62  5070.2   50.52    5086    52.4  5304.5   51.62  5478.5    55.7
  5588.2   57.79  5854.1   70.09  5975.2   77.09  6187.5   82.68  6195.3   83.92
  6367.6   91.68  6511.4  101.16  6528.2   103.3  6572.1  105.43  6643.8  108.83
#Mann= 8 ,-1 , 0
  4335.3     .05       0  4478.2      .1       0  4895.2     .12       0
  5004.9     .07       0  5014.5     .12       0  5478.5      .1       0
  5588.2     .05       0  6572.1      .1       0
Bank Sta=4950.1,5086
XS Rating Curve= 0 ,0
Exp/Cntr=0.3,0.1

Type RM Length L Ch R = 1 ,8690    ,337,337,337
BEGIN DESCRIPTION:
BAYOU CREEK 10.0
END DESCRIPTION:
XS GIS Cut Line= 3
      2359741.05     13201099.84      2359748.01     13201774.57
      2359935.81     13203520.43
#Sta/Elev= 30
  4511.5   77.09  4598.5   78.11  4638.5    78.1  4728.5   74.23  4738.5   72.73
  4748.5    66.4  4768.5   61.25  4858.5   59.36  4908.5    58.5  4918.5   59.84
  4948.5   52.81  4968.5    50.3  4978.5   51.41  4988.5   48.74  4995.5   41.47
  4998.3   40.97  4998.8   40.97  5008.5    41.7  5028.5   44.37  5038.5   49.31
  5098.6   52.23  5108.6   52.76  5208.7   50.35  5319.1   51.99  5421.1   53.77
  5651.2   56.49    6305   71.38    6486    77.2  6717.3   87.67  6942.2   91.01
#Mann= 9 ,-1 , 0
  4511.5     .05       0  4598.5      .1       0  4858.5     .12       0
  4998.8     .07       0  5008.5     .12       0  5098.6     .05       0
  5319.1     .12       0  5421.1      .1       0  5651.2     .05       0
Bank Sta=4948.5,5108.6
XS Rating Curve= 0 ,0
Exp/Cntr=0.3,0.1

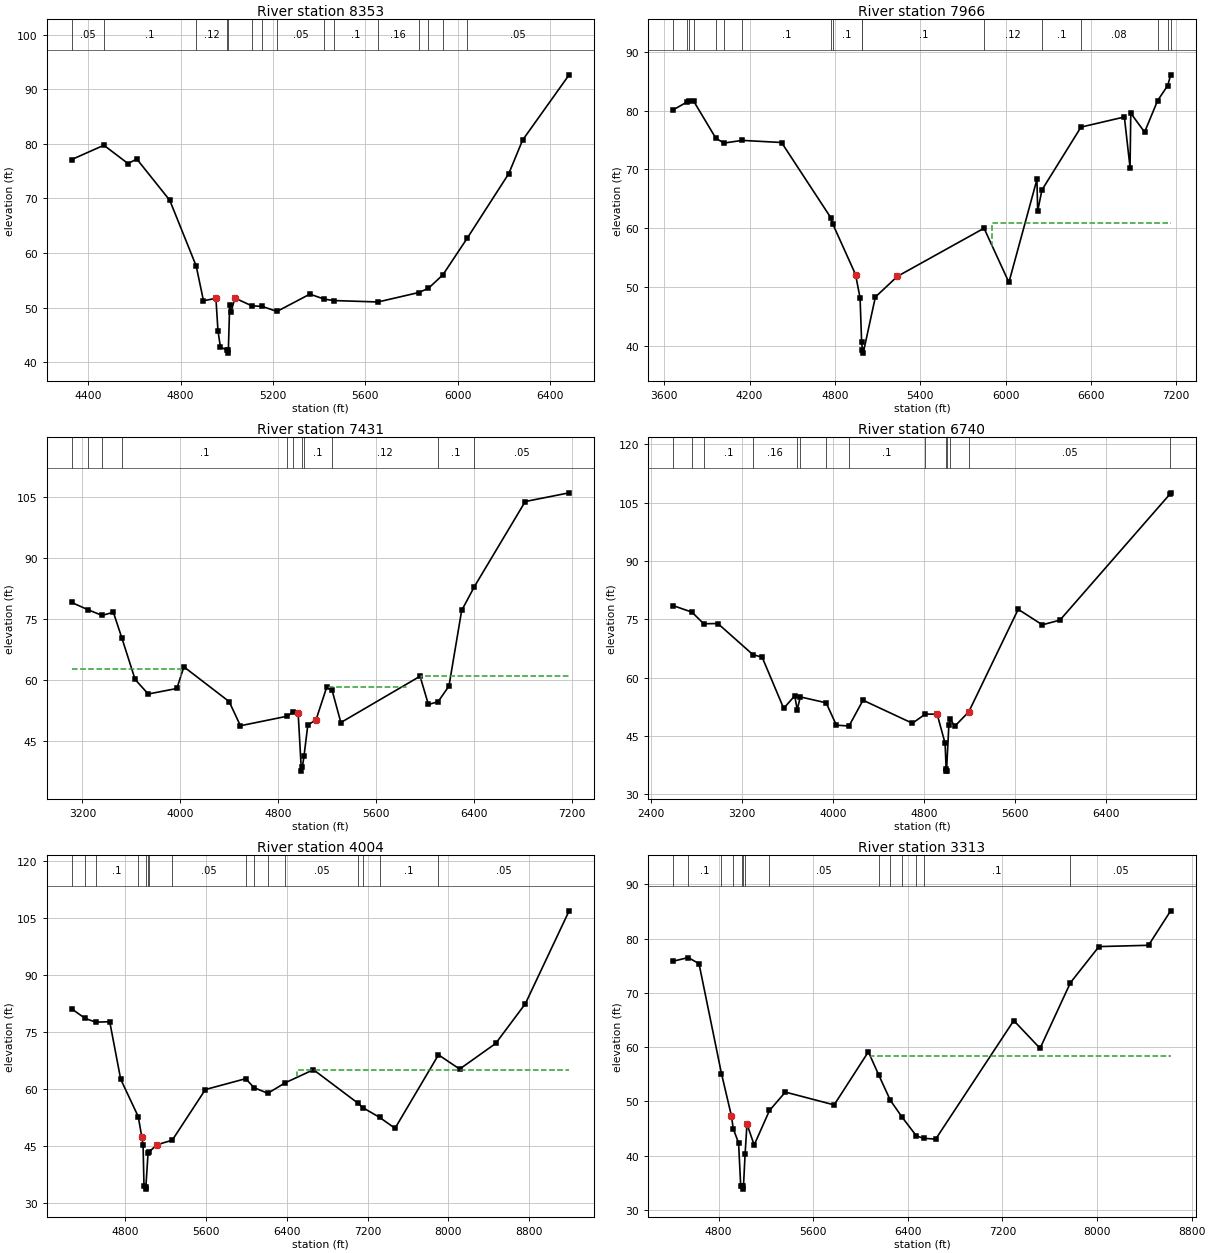
Type RM Length L Ch R = 1 ,8353    ,387,387,387
BEGIN DESCRIPTION:
Mapping XS 6ba8a440
END DESCRIPTION:
XS GIS Cut Line= 3
      2359643.67     13201099.89      2359518.47     13201517.21
      2359003.77     13203158.71
#Sta/Elev= 30
  4327.3   77.11  4467.4   79.74  4571.8   76.39  4610.1   77.21  4752.8   69.66
  4867.4   57.62  4898.9   51.26  4952.9   51.69  4961.7   45.75  4972.2   42.82
  5000.7   42.16  5003.4   41.66  5006.7   42.16  5012.5   50.47  5017.8   49.11
  5035.1   51.75  5108.5   50.32  5152.7   50.22  5217.6    49.3    5360   52.47
  5422.9   51.54  5464.8   51.29  5654.9   51.03  5831.6   52.76  5873.5   53.53
  5936.4   56.01  6041.2   62.68    6222   74.56  6281.6   80.68  6483.3   92.64
#Mann= 15 ,-1 , 0
  4327.3     .05       0  4467.4      .1       0  4867.4     .12       0
  5000.7     .07       0  5003.4     .12       0  5108.5     .05       0
  5152.7     .12       0  5217.6     .05       0  5422.9     .16       0
  5464.8      .1       0  5654.9     .16       0  5831.6     .05       0
  5873.5     .16       0  5936.4      .1       0  6041.2     .05       0
Bank Sta=4952.9,5035.1
XS Rating Curve= 0 ,0
Exp/Cntr=0.3,0.1

Type RM Length L Ch R = 1 ,7966    ,535,535,535
BEGIN DESCRIPTION:
BAYOU CREEK 9.0
END DESCRIPTION:
XS GIS Cut Line= 4
      2359706.89     13200630.28      2359380.12     13201011.51
      2358685.73      13202754.3      2358481.51     13203857.11
#Sta/Elev= 30
  3661.8   80.13  3758.2   81.44  3772.5   81.59  3807.6   81.57  3963.5   75.27
  4020.6   74.49  4147.9   74.94  4424.8   74.58  4772.5   61.74  4783.5    60.8
  4945.2   52.13    4977   48.13  4987.8   40.68  4993.8   39.33  4998.9   38.76
  5084.6    48.3  5239.2   51.81  5848.9      60  6023.8   50.79  6220.9   68.29
    6226    62.9  6256.1   66.51  6530.7    77.2  6835.8   78.92  6875.8   70.32
  6880.9   79.56  6978.2   76.35  7069.7   81.71  7140.9   84.27  7161.5   86.09
#Mann= 17 ,-1 , 0
  3661.8     .05       0  3758.2     .08       0  3772.5     .05       0
  3807.6     .08       0  3963.5     .05       0  4020.6     .08       0
  4147.9      .1       0  4772.5     .16       0  4783.5      .1       0
  4987.8     .07       0  4993.8      .1       0  5848.9     .12       0
  6256.1      .1       0  6530.7     .08       0  7069.7     .05       0
  7140.9     .08       0  7161.5     .05       0
#XS Ineff= 2 , 0
                         5908.16           60.91
Permanent Ineff=
       F       F
Bank Sta=4945.2,5239.2
XS Rating Curve= 0 ,0
Exp/Cntr=0.3,0.1

Type RM Length L Ch R = 1 ,7431    ,691,691,691
BEGIN DESCRIPTION:
Mapping XS bfc25046
END DESCRIPTION:
XS GIS Cut Line= 3
      2359557.13     13200276.26      2358740.19     13201297.43
      2357991.44     13203952.12
#Sta/Elev= 30
  3111.4   79.06  3246.6   77.26  3360.2   75.87  3453.1   76.64  3523.5   70.22
  3630.8    60.1    3738   56.52  3971.7   57.88  4029.4   63.21  4399.1   54.66
  4491.3   48.71  4875.7   51.07    4924    52.2  4963.2   51.73  4989.7   37.54
  4997.2   38.46  5010.8   41.23  5041.9   48.86  5109.6   50.21  5197.8   58.33
  5239.4   57.55  5312.1    49.5  5959.2   60.89  6027.3   53.95  6105.7    54.6
  6195.3   58.46  6299.2   77.08  6403.7   82.98  6818.7   103.9  7177.4  106.04
#Mann= 11 ,-1 , 0
  3111.4     .05       0  3246.6      .1       0  3360.2     .05       0
  3523.5      .1       0  4875.7     .12       0    4924      .1       0
  4997.2     .07       0  5010.8      .1       0  5239.4     .12       0
  6105.7      .1       0  6403.7     .05       0
#XS Ineff= 3 ,-1
  3111.4 4002.84    62.8 5218.75 5855.11   58.34 5968.75  7177.4   60.84
Permanent Ineff=
       F       F       F
Bank Sta=4963.2,5109.6
XS Rating Curve= 0 ,0
Exp/Cntr=0.3,0.1

Type RM Length L Ch R = 1 ,6740    ,2736,2736,2736
BEGIN DESCRIPTION:
Mapping XS 8096666f
END DESCRIPTION:
XS GIS Cut Line= 4
      2358876.36     13199690.78      2358141.11     13201011.51
      2357650.95     13202849.61      2357365.59     13203773.62
#Sta/Elev= 30
  2590.8   78.49  2757.5    76.8  2860.4   73.82    2985   73.88  3293.7   65.88
  3374.9   65.23  3564.7   52.07  3661.9   55.31  3683.6   51.71  3711.1   55.01
  3938.6    53.5  4028.4   47.75  4139.6   47.53  4263.2   54.16  4697.8   48.24
  4811.7    50.6  4915.8   50.57  4985.6    43.1    4995   36.43  4997.7   35.93
  4998.2   35.93  5018.7   47.69  5030.9   49.29    5071   47.47  5194.6   51.19
  5629.3   77.54    5842   73.55  5997.3   74.77  6964.7  107.14  6971.8  107.49
#Mann= 14 ,-1 , 0
  2590.8     .05       0  2757.5     .05       0  2860.4      .1       0
  3293.7     .16       0  3683.6      .1       0  3711.1     .16       0
  3938.6     .12       0  4139.6      .1       0  4811.7     .12       0
    4995     .07       0  4998.2     .12       0  5030.9      .1       0
  5194.6     .05       0  6964.7      .1       0
Bank Sta=4915.8,5194.6
XS Rating Curve= 0 ,0
Exp/Cntr=0.3,0.1

Type RM Length L Ch R = 1 ,4004    ,691,691,691
BEGIN DESCRIPTION:
Mapping XS e9a101ab
END DESCRIPTION:
XS GIS Cut Line= 3
      2357991.34     13199010.03      2357582.87     13200044.81
      2356439.16     13203680.17
#Sta/Elev= 30
  4271.4   81.17  4406.4   78.62  4511.4   77.64  4649.3   77.76  4757.5   62.64
  4931.5   52.79  4966.8   47.37  4979.3   45.29  4988.3   34.42  5003.5   33.72
  5006.7   34.22  5028.1   43.13  5036.5   43.48  5117.3    45.4  5267.8   46.59
  5595.7   59.92    5994   62.77  6077.9    60.4  6213.2   58.93  6385.6   61.69
    6665   65.13  7105.3   56.33  7151.4   55.19  7318.6   52.61  7472.2   49.72
    7902   69.05  8111.6    65.3  8468.1   72.04  8761.6   82.49  9194.9  106.93
#Mann= 16 ,-1 , 0
  4271.4     .05       0  4406.4     .05       0  4511.4      .1       0
  4931.5     .05       0  5006.7     .04       0  5028.1     .05       0
  5036.5      .1       0  5267.8     .05       0    5994      .1       0
  6077.9     .05       0  6213.2      .1       0  6385.6     .05       0
  7105.3      .1       0  7151.4     .12       0  7318.6      .1       0
    7902     .05       0
#XS Ineff= 2 , 0
                         6502.27           64.93
Permanent Ineff=
       F       F
Bank Sta=4966.8,5117.3
XS Rating Curve= 0 ,0
Exp/Cntr=0.3,0.1

Type RM Length L Ch R = 1 ,3313    ,1537,1537,1537
BEGIN DESCRIPTION:
BAYOU CREEK 3.0
END DESCRIPTION:
XS GIS Cut Line= 3
      2357147.18      13199200.6      2356970.17     13200262.65
      2355894.85     13203202.77
#Sta/Elev= 30
  4415.2   75.84  4543.2    76.5  4634.4   75.39  4824.6   55.11  4908.2   47.36
  4924.3   44.94    4969   42.35    4987   34.47  4999.4    34.4  5006.5   34.34
  5009.3   33.84    5024   40.27    5040   45.84  5100.8   41.97  5230.3   48.33
  5364.4   51.72  5777.1   49.36  6066.4   59.14  6152.7   54.94  6252.4    50.2
  6353.5   47.04  6472.5   43.65  6533.6    43.2  6635.7   43.06  7295.9    64.9
  7518.3   59.78    7775   71.88    8016   78.53  8435.2   78.77  8622.5   85.12
#Mann= 14 ,-1 , 0
  4415.2     .05       0  4543.2      .1       0  4824.6     .08       0
  4924.3     .12       0  4999.4     .07       0  5006.5     .12       0
    5024      .1       0  5230.3     .05       0  6152.7      .1       0
  6252.4     .05       0  6353.5      .1       0  6472.5     .12       0
  6533.6      .1       0    7775     .05       0
#XS Ineff= 2 , 0
                         6088.07           58.46
Permanent Ineff=
       F       F
Bank Sta=4908.2,5040
XS Rating Curve= 0 ,0
Exp/Cntr=0.3,0.1

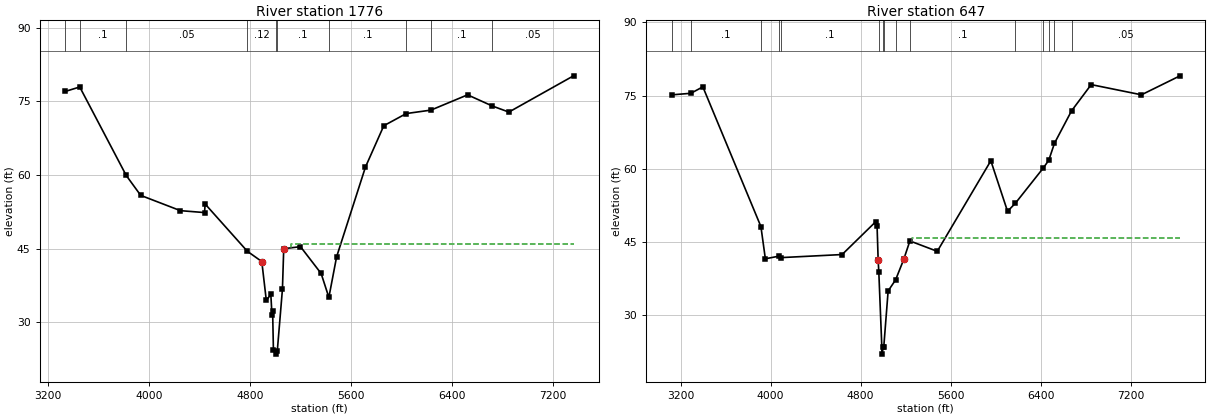
Type RM Length L Ch R = 1 ,1776    ,1129,1129,1129
BEGIN DESCRIPTION:
BAYOU CREEK 2.0
END DESCRIPTION:
XS GIS Cut Line= 5
      2356874.85     13199146.19       2356289.4     13199527.41
      2356194.09     13199963.11       2355853.7     13201596.98
      2355200.14     13202618.17
#Sta/Elev= 30
  3337.4   77.04  3452.5   77.95  3820.8   59.93  3935.4   55.88  4249.9   52.77
  4440.7   52.38  4445.8   54.12  4779.9    44.5  4894.4   42.41  4930.1    34.5
  4965.9   35.71    4975   31.54  4980.2   32.33  4986.4   24.46  5006.6   23.56
    5017   24.16  5057.9   36.78  5068.1   45.02  5200.9   45.44  5364.3   39.98
  5425.6   35.11  5486.9   43.37  5715.6   61.66  5860.7   70.06  6038.5   72.54
  6233.9   73.24  6524.3   76.35  6720.7   74.07  6851.3   72.84  7363.4   80.22
#Mann= 10 ,-1 , 0
  3337.4     .05       0  3452.5      .1       0  3820.8     .05       0
  4779.9     .12       0  5006.6     .07       0    5017      .1       0
  5425.6      .1       0  6038.5     .05       0  6233.9      .1       0
  6720.7     .05       0
#XS Ineff= 2 , 0
                         5127.84           45.93
Permanent Ineff=
       F       F
Bank Sta=4894.4,5068.1
XS Rating Curve= 0 ,0
Exp/Cntr=0.3,0.1

Type RM Length L Ch R = 1 ,647     ,0,0,0
BEGIN DESCRIPTION:
BAYOU CREEK 1.0
END DESCRIPTION:
XS GIS Cut Line= 4
      2357051.84     13198928.34      2356071.55     13199200.64
      2355363.54      13200562.2      2355009.88     13202493.74
#Sta/Elev= 30
  3121.4   75.16  3291.7   75.48  3398.4    76.8  3914.2   48.16  3953.6   41.56
    4072   42.09  4090.9    41.8  4635.5   42.43  4933.7   49.15  4946.1   48.19
  4955.8   41.22  4961.5   38.87  4990.9   22.02    5000   23.46  5005.7   23.55
  5044.3   34.97  5110.6   37.24  5182.8   41.43  5237.6   45.22  5480.8   43.09
  5956.7   61.65  6105.2   51.29  6174.5   52.94  6420.3    60.1  6471.1   61.74
    6522   65.24  6673.4   71.87  6848.2   77.26  7294.6   75.17  7637.1   79.06
#Mann= 15 ,-1 , 0
  3121.4     .05       0  3291.7      .1       0  3914.2     .05       0
    4072     .12       0  4090.9      .1       0  4961.5     .12       0
    5000     .07       0  5005.7     .12       0  5110.6     .12       0
  5237.6      .1       0  6174.5     .05       0  6420.3      .1       0
  6471.1     .05       0    6522      .1       0  6673.4     .05       0
#XS Ineff= 2 , 0
                         5255.68           45.83
Permanent Ineff=
       F       F
Bank Sta=4955.8,5182.8
XS Rating Curve= 0 ,0
Exp/Cntr=0.3,0.1
Stream Node=BAYOU CREEK     ,Reach-1         , 0 , 0 ,Upstream end
Stream Node=BAYOU CREEK     ,Reach-1         , 0 , 1 ,Downstream end

Chan Stop Cuts=-1
Use User Specified Reach Order=0
Composite Channel Slope=5