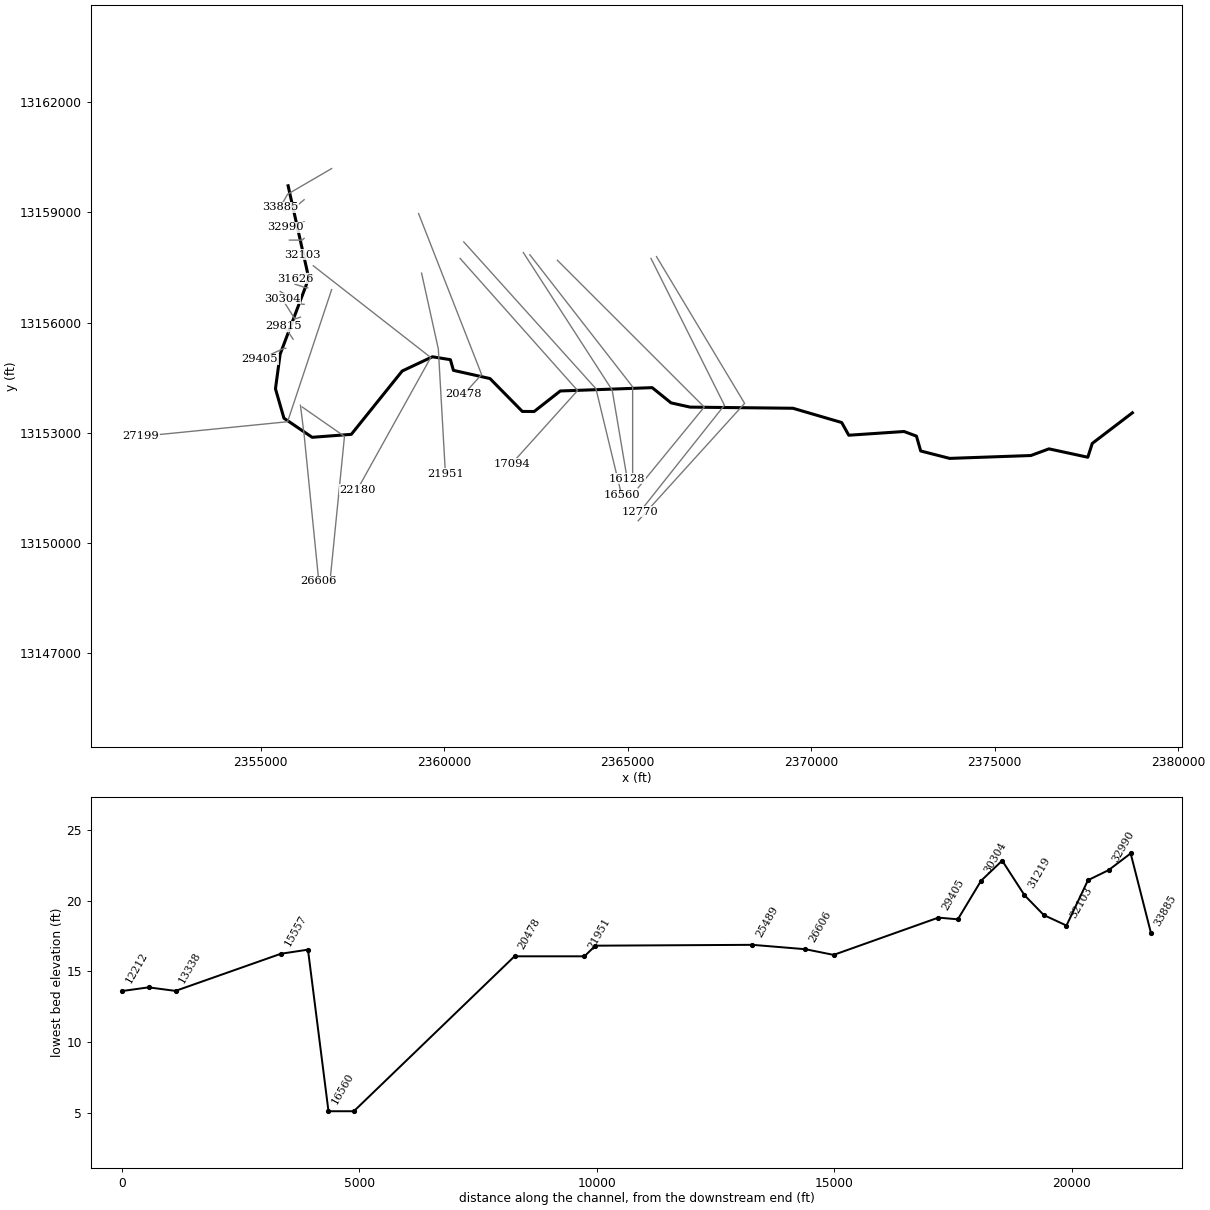
--- CAYAMON CREEK.prj (project) ---

Proj Title=CAYAMON CREEK Base Level Engineering
Current Plan=p01
Default Exp/Contr=0.3,0.1
English Units
Geom File=g01
Flow File=f01
Plan File=p01
Y Axis Title=Elevation
X Axis Title(PF)=Main Channel Distance
X Axis Title(XS)=Station
BEGIN DESCRIPTION:
CAYAMON CREEK
END DESCRIPTION:
DSS Export Rating Curves= 0
DSS Export Rating Curve Sorted= 0
DSS Export Volume Flow Curves= 0
DXF OffsetX= 0
DXF OffsetY= 0
DXF ScaleX= 1
DXF ScaleY= 10

--- CAYAMON CREEK.p01 (plan) ---

Plan Title=Multiple Run
Short Identifier=Multiple
Geom File=g01
Flow File=f01
Subcritical Flow
K Sum by GR= 0
Std Step Tol= 0.01
Critical Tol= 0.01
Num of Std Step Trials= 20
Max Error Tol= 0.3
Flow Tol Ratio= 0.001
Split Flow NTrial= 30
Split Flow Tol= 0.02
Split Flow Ratio= 0.02
Log Output Level= 0
Friction Slope Method= 1
Unsteady Friction Slope Method= 2
Unsteady Bridges Friction Slope Method= 1
Parabolic Critical Depth
Global Vel Dist=  1 , 1 , 1
Global Log Level= 0
CheckData=True
Encroach Param= -1, 0, 0, 0
BEGIN DESCRIPTION:
Multiple Run
END DESCRIPTION:

--- CAYAMON CREEK.f01 (steady flow) ---

Flow Title=Multiple
Program Version=4.10
Number of Profiles= 7
Profile Names=10-year,25-year,50-year,1pct_min,100-year,1pct_plu,500-year
River Rch & RM=CAYAMON CREEK,Reach-1         ,33885
     102     125     141     117     158     214     199
River Rch & RM=CAYAMON CREEK,Reach-1         ,29405
    1016    1459    1837    1690    2285    3091    3573
River Rch & RM=CAYAMON CREEK,Reach-1         ,27199
    1016    1459    1837    1690    2285    3091    3573
River Rch & RM=CAYAMON CREEK,Reach-1         ,25489
    1126    1617    2037    1872    2532    3424    3953
River Rch & RM=CAYAMON CREEK,Reach-1         ,21951
    1604    2286    2862    2609    3529    4772    5419
River Rch & RM=CAYAMON CREEK,Reach-1         ,20478
    1604    2286    2862    2609    3529    4772    5419
River Rch & RM=CAYAMON CREEK,Reach-1         ,17094
    1721    2457    3081    2813    3805    5145    5858
River Rch & RM=CAYAMON CREEK,Reach-1         ,11671
    1727    2462    3083    2811    3802    5142    5838
River Rch & RM=CAYAMON CREEK,Reach-1         ,7768
    2034    2911    3655    3341    4518    6110    6969
River Rch & RM=CAYAMON CREEK,Reach-1         ,6108
    2034    2911    3655    3341    4518    6110    6969
River Rch & RM=CAYAMON CREEK,Reach-1         ,1732
    2034    2911    3655    3341    4518    6110    6969
Boundary for River Rch & Prof#=CAYAMON CREEK,Reach-1         , 1
Up Type= 0
Dn Type= 3
Dn Slope=0.0014
Boundary for River Rch & Prof#=CAYAMON CREEK,Reach-1         , 2
Up Type= 0
Dn Type= 3
Dn Slope=0.0014
Boundary for River Rch & Prof#=CAYAMON CREEK,Reach-1         , 3
Up Type= 0
Dn Type= 3
Dn Slope=0.0014
Boundary for River Rch & Prof#=CAYAMON CREEK,Reach-1         , 4
Up Type= 0
Dn Type= 3
Dn Slope=0.0014
Boundary for River Rch & Prof#=CAYAMON CREEK,Reach-1         , 5
Up Type= 0
Dn Type= 3
Dn Slope=0.0014
Boundary for River Rch & Prof#=CAYAMON CREEK,Reach-1         , 6
Up Type= 0
Dn Type= 3
Dn Slope=0.0014
Boundary for River Rch & Prof#=CAYAMON CREEK,Reach-1         , 7
Up Type= 0
Dn Type= 3
Dn Slope=0.0014
DSS Import GetInterval= 0
DSS Import GetPeak= 0
DSS Import FillOption= 0

--- CAYAMON CREEK.g01 (geometry) ---

Geom Title=Existing Conditions
Program Version=4.10

River Reach=CAYAMON CREEK   ,Reach-1
Reach XY= 30
      2355751.88      13159727.1      2356315.24     13157207.78
      2355534.69     13155137.03       2355407.7     13154193.78
      2355638.46     13153392.88      2356406.69     13152872.05
      2357473.73     13152952.79      2358859.89     13154679.12
      2359682.81     13155066.28      2360172.84     13154987.76
      2360255.26     13154696.86      2361251.36     13154473.33
      2362132.23     13153577.33      2362454.77     13153575.03
      2363166.38     13154134.52      2365669.68     13154225.53
      2366183.79     13153810.82      2366703.54     13153694.72
      2369503.09     13153663.68      2370832.52     13153274.97
      2371025.22     13152928.62      2372531.73     13153030.18
      2372868.67     13152904.61      2372984.99     13152499.23
      2373773.84     13152297.41      2375986.76     13152375.73
       2376477.6     13152557.16      2377536.83     13152328.74
      2377658.46       13152706.      2378750.88     13153539.78

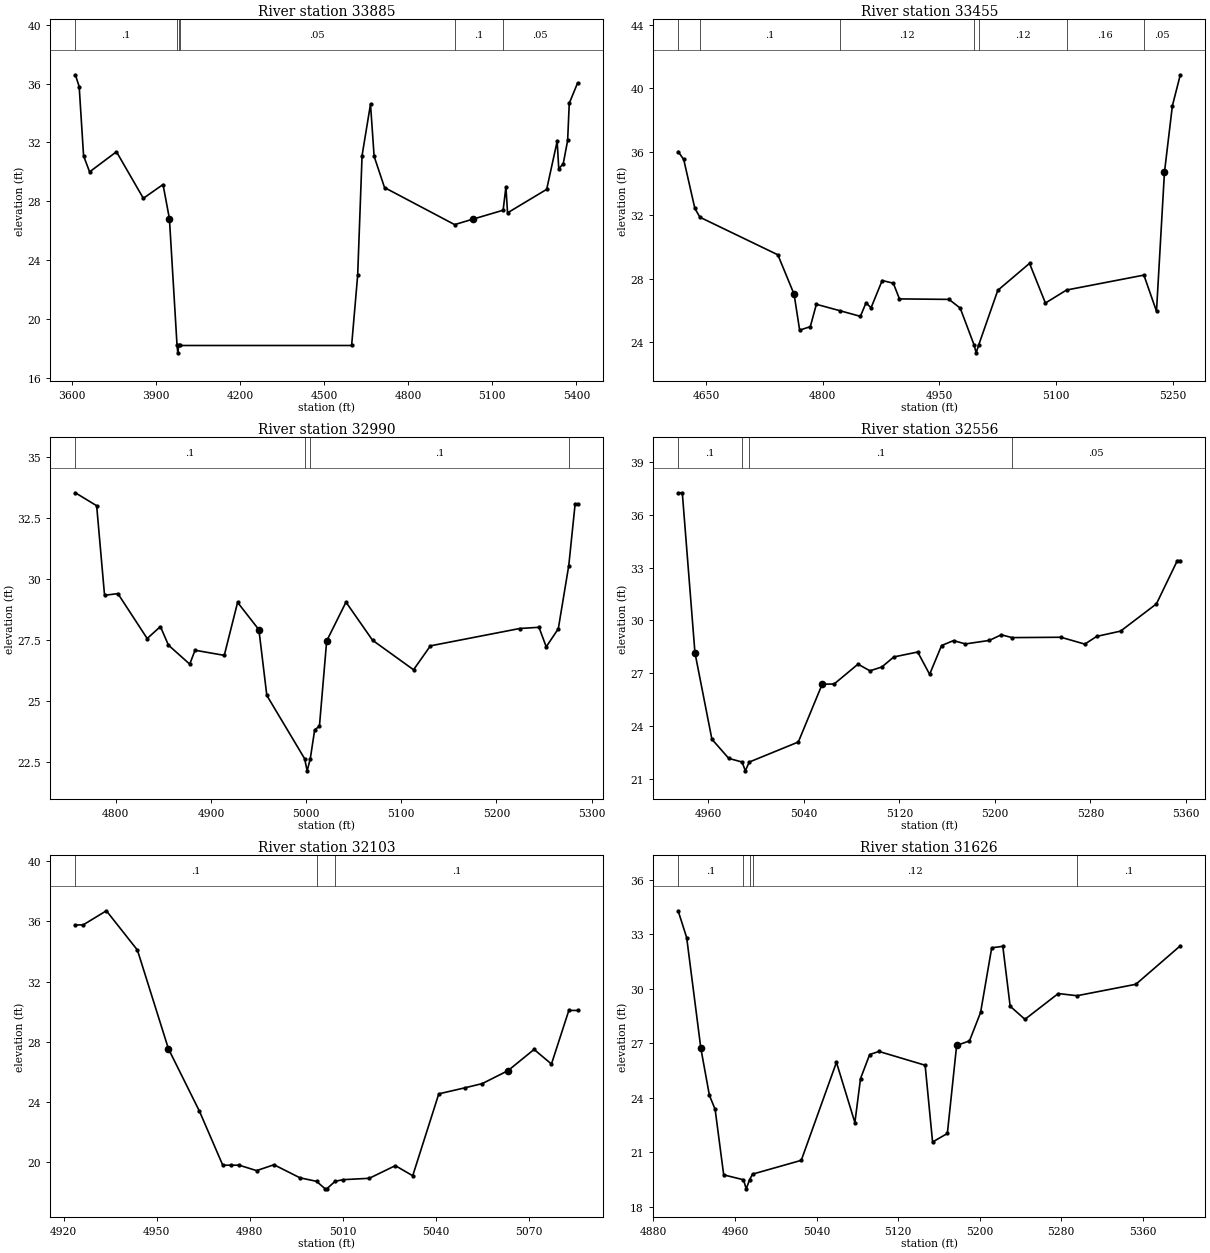
Type RM Length L Ch R = 1 ,33885   ,430,430,430
BEGIN DESCRIPTION:
CAYAMON CREEK 38.0
END DESCRIPTION:
XS GIS Cut Line= 3
      2356937.75     13160196.87      2355737.72     13159496.85
      2355537.72     13159146.85
#Sta/Elev= 30
  3611.8   36.61  3625.5   35.81  3641.2   31.09  3662.7      30  3758.6   31.37
  3854.5    28.2  3924.8   29.14  3947.6   26.81  3974.8   18.18  3977.5   17.68
  3980.8   18.18    3984   18.18  4597.9   18.18  4619.5   22.96  4635.2   31.11
  4665.3   34.61  4678.2   31.06  4715.4   28.93  4965.6   26.41  5030.6   26.78
  5138.7   27.39  5148.6   28.98  5154.4   27.21  5294.1   28.81  5331.5   32.08
  5337.2   30.22  5353.1   30.54  5368.9   32.14  5374.7   34.67  5404.2   36.04
#Mann= 6 ,-1 , 0
  3611.8      .1       0  3974.8     .07       0  3980.8      .1       0
    3984     .05       0  4965.6      .1       0  5138.7     .05       0
Bank Sta=3947.6,5030.6
XS Rating Curve= 0 ,0
Exp/Cntr=0.3,0.1

Type RM Length L Ch R = 1 ,33455   ,465,465,465
BEGIN DESCRIPTION:
CAYAMON CREEK 37.0
END DESCRIPTION:
XS GIS Cut Line= 3
      2356187.74     13159346.87      2355887.72     13159096.85
      2355637.72     13159046.85
#Sta/Elev= 30
  4614.2   36.02  4621.4   35.52  4635.7   32.44  4642.2   31.88  4742.4   29.51
  4763.3   27.02  4770.4   24.76  4784.1   24.98  4791.9   26.39  4822.6   25.98
  4848.5   25.63  4855.7   26.48  4862.2   26.17  4876.5   27.89  4890.8   27.72
  4898.7   26.73  4962.4    26.7  4976.8   26.15  4994.6   23.83  4997.3   23.33
  5000.6   23.83  5025.1   27.27  5065.9   28.97  5086.3   26.47  5113.5   27.29
  5212.9   28.23  5229.1   25.95  5239.3    34.7  5249.5    38.9  5259.7   40.86
#Mann= 7 ,-1 , 0
  4614.2     .05       0  4642.2      .1       0  4822.6     .12       0
  4994.6     .07       0  5000.6     .12       0  5113.5     .16       0
  5212.9     .05       0
Bank Sta=4763.3,5239.3
XS Rating Curve= 0 ,0
Exp/Cntr=0.3,0.1

Type RM Length L Ch R = 1 ,32990   ,434,434,434
BEGIN DESCRIPTION:
CAYAMON CREEK 36.0
END DESCRIPTION:
XS GIS Cut Line= 3
      2356187.71     13158746.85      2355987.72     13158646.85
      2355687.76     13158596.86
#Sta/Elev= 30
  4757.5   33.54  4779.9   33.01  4788.2   29.34  4802.2   29.41    4833   27.57
  4846.9   28.06  4855.3    27.3  4877.7   26.52  4883.3   27.09    4914   26.88
    4928   29.05  4950.4   27.93  4958.7   25.24  4998.4   22.65  5001.1   22.15
  5004.4   22.65    5009   23.83    5014   23.98  5021.6   27.47  5041.9   29.06
  5069.8    27.5  5112.9   26.29  5130.6   27.27  5224.4   27.98  5244.7   28.03
  5252.3   27.23    5265   27.97    5276   30.56  5282.7   33.09  5285.2   33.09
#Mann= 4 ,-1 , 0
  4757.5      .1       0  4998.4     .07       0  5004.4      .1       0
    5276     .05       0
Bank Sta=4950.4,5021.6
XS Rating Curve= 0 ,0
Exp/Cntr=0.3,0.1

Type RM Length L Ch R = 1 ,32556   ,453,453,453
BEGIN DESCRIPTION:
CAYAMON CREEK 35.0
END DESCRIPTION:
XS GIS Cut Line= 3
      2356187.72     13158296.85      2356137.72     13158246.85
      2355787.73     13158246.85
#Sta/Elev= 30
  4934.6   37.26  4938.1   37.26  4948.7   28.16  4962.9   23.24    4977   22.15
  4988.2   21.94  4990.9   21.44  4994.2   21.94  5035.3   23.08  5055.3   26.37
  5065.3   26.38  5085.3   27.51  5095.3   27.13  5105.3   27.35  5115.3   27.92
  5135.3    28.2  5145.3   26.93  5155.3   28.57  5165.3   28.85  5175.3   28.66
  5195.3   28.86  5205.3   29.18  5214.4   29.02  5255.3   29.04  5275.3   28.65
  5285.3   29.09  5305.3   29.39  5335.3   30.94  5352.8    33.4  5355.3    33.4
#Mann= 4 ,-1 , 0
  4934.6      .1       0  4988.2     .07       0  4994.2      .1       0
  5214.4     .05       0
Bank Sta=4948.7,5055.3
XS Rating Curve= 0 ,0
Exp/Cntr=0.3,0.1

Type RM Length L Ch R = 1 ,32103   ,477,477,477
BEGIN DESCRIPTION:
CAYAMON CREEK 34.0
END DESCRIPTION:
XS GIS Cut Line= 3
      2356287.72     13157796.85      2356237.72     13157796.85
      2356137.72     13157846.85
#Sta/Elev= 28
  4923.8   35.77  4926.3   35.77  4933.8   36.71  4943.8    34.1  4953.8   27.54
  4963.8   23.39  4971.3   19.81  4973.8   19.81  4976.6   19.81  4982.2   19.45
  4987.8   19.84  4996.2   18.97  5001.5   18.74  5004.3   18.24  5004.8   18.24
  5007.5   18.74  5010.1   18.85  5018.5   18.94  5026.9   19.78  5032.5   19.11
  5040.9   24.55  5049.3   24.95  5054.9   25.23  5063.2   26.09  5071.6    27.5
  5077.2   26.53  5082.8   30.09  5085.6   30.09
#Mann= 3 ,-1 , 0
  4923.8      .1       0  5001.5     .07       0  5007.5      .1       0
Bank Sta=4953.8,5063.2
XS Rating Curve= 0 ,0
Exp/Cntr=0.3,0.1

Type RM Length L Ch R = 1 ,31626   ,407,407,407
BEGIN DESCRIPTION:
CAYAMON CREEK 33.0
END DESCRIPTION:
XS GIS Cut Line= 3
       2356387.7     13157296.87      2356287.72     13157346.85
      2355937.69     13157196.84
#Sta/Elev= 30
  4904.2    34.3  4912.6   32.82  4926.5   26.72  4934.9   24.13  4940.5   23.36
  4948.9   19.75  4968.3   19.48    4971   18.98  4974.3   19.48  4977.2   19.79
    5025   20.55  5059.5   25.95  5077.6   22.63  5083.1   25.05  5092.1   26.38
  5101.2   26.55  5146.5   25.79  5153.8   21.56  5168.3   22.03  5177.4   26.88
    5190   27.13  5200.9    28.7  5211.8   32.26  5222.7   32.34  5229.9   29.04
  5244.4   28.32  5277.1   29.74  5295.5   29.62  5353.2   30.25  5396.8   32.37
#Mann= 5 ,-1 , 0
  4904.2      .1       0  4968.3     .07       0  4974.3      .1       0
  4977.2     .12       0  5295.5      .1       0
Bank Sta=4926.5,5177.4
XS Rating Curve= 0 ,0
Exp/Cntr=0.3,0.1

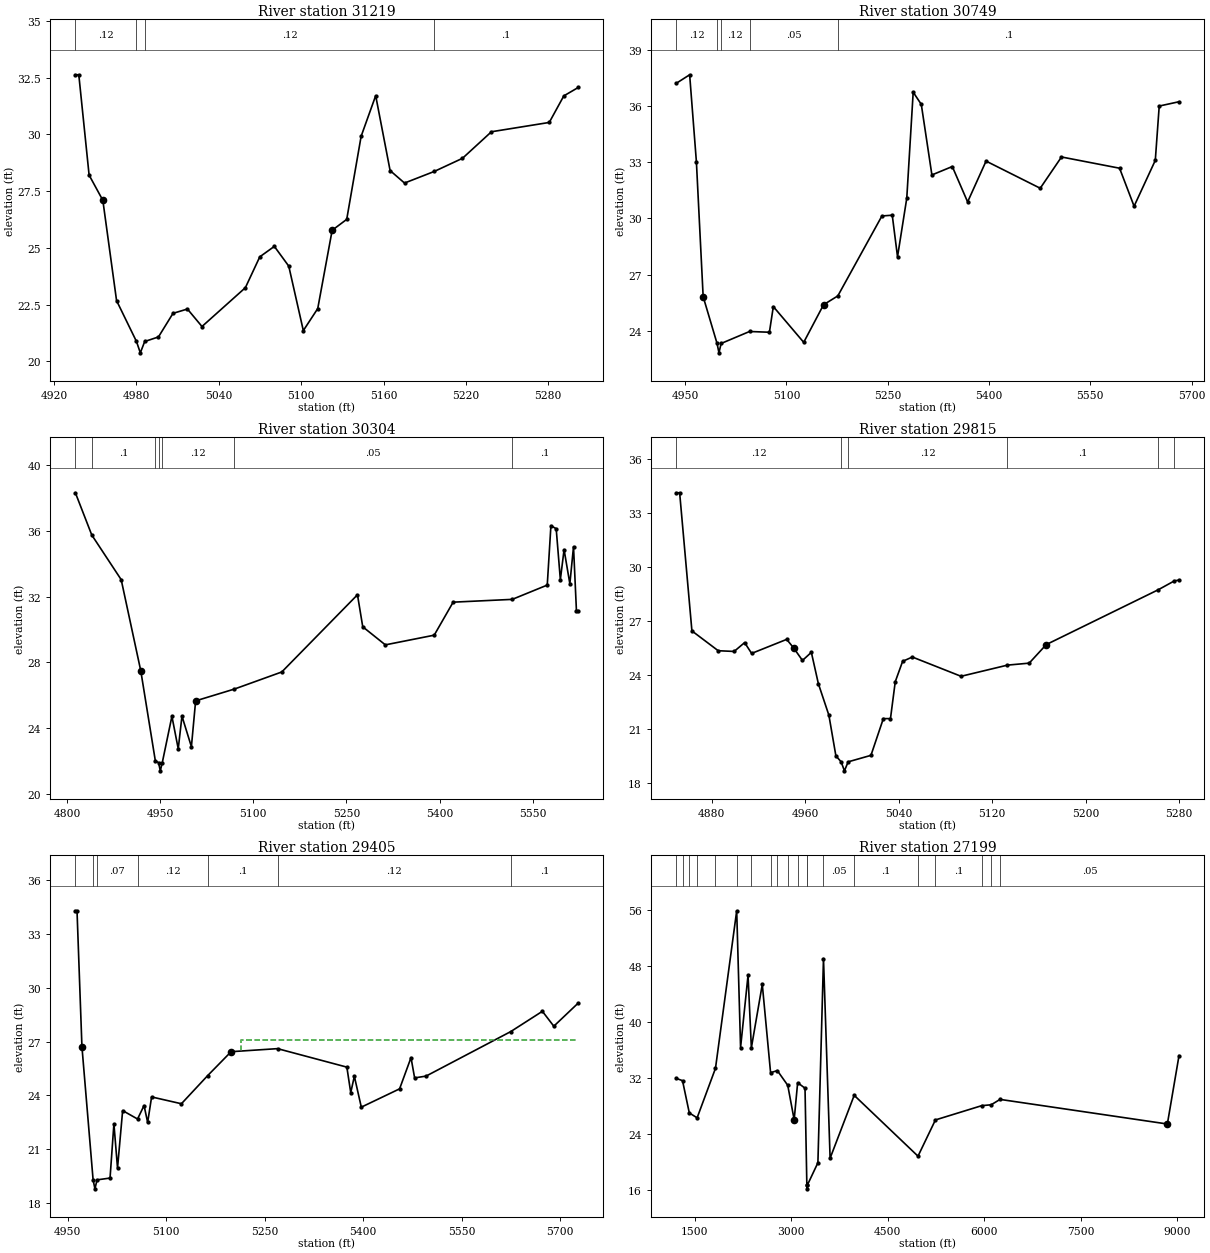
Type RM Length L Ch R = 1 ,31219   ,470,470,470
BEGIN DESCRIPTION:
CAYAMON CREEK 32.0
END DESCRIPTION:
XS GIS Cut Line= 3
      2356287.72     13156946.85      2356237.72     13156946.85
      2355937.75     13157046.85
#Sta/Elev= 30
  4935.6   32.63  4938.1   32.63  4945.6   28.21  4955.6    27.1  4965.6   22.68
  4980.1   20.88  4982.9   20.38  4986.1   20.88  4996.1   21.08  5006.7   22.12
  5017.2   22.31  5027.8   21.54  5059.4   23.25  5069.9   24.61  5080.5   25.07
    5091    24.2  5101.6   21.36  5112.1   22.33  5122.6   25.78  5133.2   26.26
  5143.7   29.92  5154.3   31.71  5164.8   28.41  5175.3   27.86  5196.9   28.37
  5217.5   28.95  5238.6   30.12  5280.7   30.53  5291.3    31.7  5301.8   32.07
#Mann= 4 ,-1 , 0
  4935.6     .12       0  4980.1     .07       0  4986.1     .12       0
  5196.9      .1       0
Bank Sta=4955.6,5122.6
XS Rating Curve= 0 ,0
Exp/Cntr=0.3,0.1

Type RM Length L Ch R = 1 ,30749   ,445,445,445
BEGIN DESCRIPTION:
CAYAMON CREEK 31.0
END DESCRIPTION:
XS GIS Cut Line= 3
      2356187.72     13156496.85      2356137.72     13156496.85
      2355537.74     13156846.84
#Sta/Elev= 30
  4936.7   37.21  4956.7   37.67  4966.7   33.02  4976.7   25.82  4997.3   23.32
  5000.1   22.82  5003.3   23.32  5045.4   23.96  5074.8   23.92  5080.6   25.29
  5125.6   23.38    5155   25.39  5176.1   25.86  5241.4   30.13  5256.7   30.17
  5264.5   27.95  5278.2   31.08  5287.7   36.74  5299.7   36.09  5315.4   32.32
  5345.6   32.77  5368.3   30.88  5395.6   33.06  5475.8   31.61  5507.3   33.28
  5593.3   32.68  5614.8   30.65  5646.2    33.1    5652      36  5681.3   36.23
#Mann= 5 ,-1 , 0
  4936.7     .12       0  4997.3     .07       0  5003.3     .12       0
  5045.4     .05       0  5176.1      .1       0
Bank Sta=4976.7,5155
XS Rating Curve= 0 ,0
Exp/Cntr=0.3,0.1

Type RM Length L Ch R = 1 ,30304   ,489,489,489
BEGIN DESCRIPTION:
CAYAMON CREEK 30.0
END DESCRIPTION:
XS GIS Cut Line= 3
      2356087.72     13156146.85      2355937.72     13156096.85
      2355587.74     13156646.83
#Sta/Elev= 30
  4813.3   38.33  4839.7   35.76  4887.1   33.04  4918.7   27.48  4942.1   22.01
  4947.3    21.9  4950.1    21.4  4953.3    21.9  4968.8   24.72    4979   22.74
    4985   24.73  5000.2   22.87    5007   25.66  5069.5   26.38  5145.8   27.42
  5267.7   32.12  5276.2   30.17  5312.6   29.07  5391.3   29.66  5421.8   31.67
    5517   31.84  5573.4   32.71  5579.3   36.33  5587.8   36.14  5594.5   33.04
  5600.5   34.87  5609.8   32.79  5615.7   35.05  5620.4   31.15  5623.3   31.15
#Mann= 7 ,-1 , 0
  4813.3     .05       0  4839.7      .1       0  4942.1     .12       0
  4947.3     .07       0  4953.3     .12       0  5069.5     .05       0
    5517      .1       0
Bank Sta=4918.7,5007
XS Rating Curve= 0 ,0
Exp/Cntr=0.3,0.1

Type RM Length L Ch R = 1 ,29815   ,410,410,410
BEGIN DESCRIPTION:
CAYAMON CREEK 29.0
END DESCRIPTION:
XS GIS Cut Line= 3
      2355887.71     13155546.87      2355787.72     13155696.85
      2355637.69     13155896.89
#Sta/Elev= 30
  4849.5   34.12  4852.5   34.12    4863   26.45  4885.5   25.35  4899.1   25.31
  4908.1    25.8  4914.1    25.2  4944.1   25.98  4950.1    25.5  4957.6   24.81
  4965.2   25.26  4971.2   23.52  4980.2   21.77  4986.2   19.51  4990.7   19.18
  4993.5   18.68  4996.7   19.18  5016.2   19.54  5026.8   21.58  5032.9   21.58
    5037   23.63  5043.3   24.76  5051.6      25  5093.3   23.93    5133   24.55
  5151.6   24.66  5166.2   25.69  5262.2   28.74  5275.9   29.23  5279.8   29.27
#Mann= 6 ,-1 , 0
  4849.5     .12       0  4990.7     .07       0  4996.7     .12       0
    5133      .1       0  5262.2     .12       0  5275.9      .1       0
Bank Sta=4950.1,5166.2
XS Rating Curve= 0 ,0
Exp/Cntr=0.3,0.1

Type RM Length L Ch R = 1 ,29405   ,2206,2206,2206
BEGIN DESCRIPTION:
CAYAMON CREEK 28.0
END DESCRIPTION:
XS GIS Cut Line= 3
      2355687.73     13155296.85      2355637.72     13155296.85
      2354987.72     13154996.85
#Sta/Elev= 30
  4961.5   34.29    4964   34.29  4971.5   26.72  4988.5    19.3  4991.3    18.8
  4994.5    19.3  5014.3    19.4  5020.2   22.42  5025.7   19.96  5033.5   23.16
  5056.2   22.69  5066.1   23.44  5071.6    22.5  5077.6   23.92    5123   23.54
  5162.8    25.1  5198.7   26.44  5269.4   26.61    5375   25.58  5380.9   24.16
  5386.4   25.07    5397   23.35  5455.3   24.37  5472.7   26.11  5478.2   24.98
  5495.6   25.08  5624.6   27.56  5672.8   28.69  5690.2   27.86  5727.4   29.15
#Mann= 7 ,-1 , 0
  4961.5     .07       0  4988.5     .07       0  4994.5     .07       0
  5056.2     .12       0  5162.8      .1       0  5269.4     .12       0
  5624.6      .1       0
#XS Ineff= 2 , 0
                         5213.64            27.1
Permanent Ineff=
       F       F
Bank Sta=4971.5,5198.7
XS Rating Curve= 0 ,0
Exp/Cntr=0.3,0.1

Type RM Length L Ch R = 1 ,27199   ,593,593,593
BEGIN DESCRIPTION:
CAYAMON CREEK 27.0
END DESCRIPTION:
XS GIS Cut Line= 3
      2356937.71     13156896.81      2355737.72     13153296.85
      2351737.76     13152896.86
#Sta/Elev= 30
  1212.2   31.94  1311.4    31.6  1416.7      27  1538.3    26.3  1823.7   33.37
  2153.3   55.84  2213.5   36.33  2329.5   46.64  2381.2   36.29  2550.9   45.33
  2679.8   32.74  2784.7   33.04  2946.6   30.94  3046.3   26.03  3100.4   31.31
  3214.9   30.53  3243.6   16.67  3246.3   16.17  3249.6   16.67  3415.2   19.89
    3502   49.02  3604.9   20.54  3979.3   29.51  4970.7   20.83  5241.4      26
  5962.2   28.04  6107.3   28.16  6245.6   28.93  8845.9   25.42  9026.8   35.17
#Mann= 20 ,-1 , 0
  1212.2      .1       0  1311.4     .16       0  1416.7      .1       0
  1538.3      .1       0  1823.7     .05       0  2153.3      .1       0
  2381.2     .15       0  2679.8     .05       0  2784.7      .1       0
  2946.6     .05       0  3100.4      .1       0  3243.6     .07       0
  3249.6     .05       0    3502     .05       0  3979.3      .1       0
  4970.7     .12       0  5241.4      .1       0  5962.2     .05       0
  6107.3      .1       0  6245.6     .05       0
Bank Sta=3046.3,8845.9
XS Rating Curve= 0 ,0
Exp/Cntr=0.3,0.1

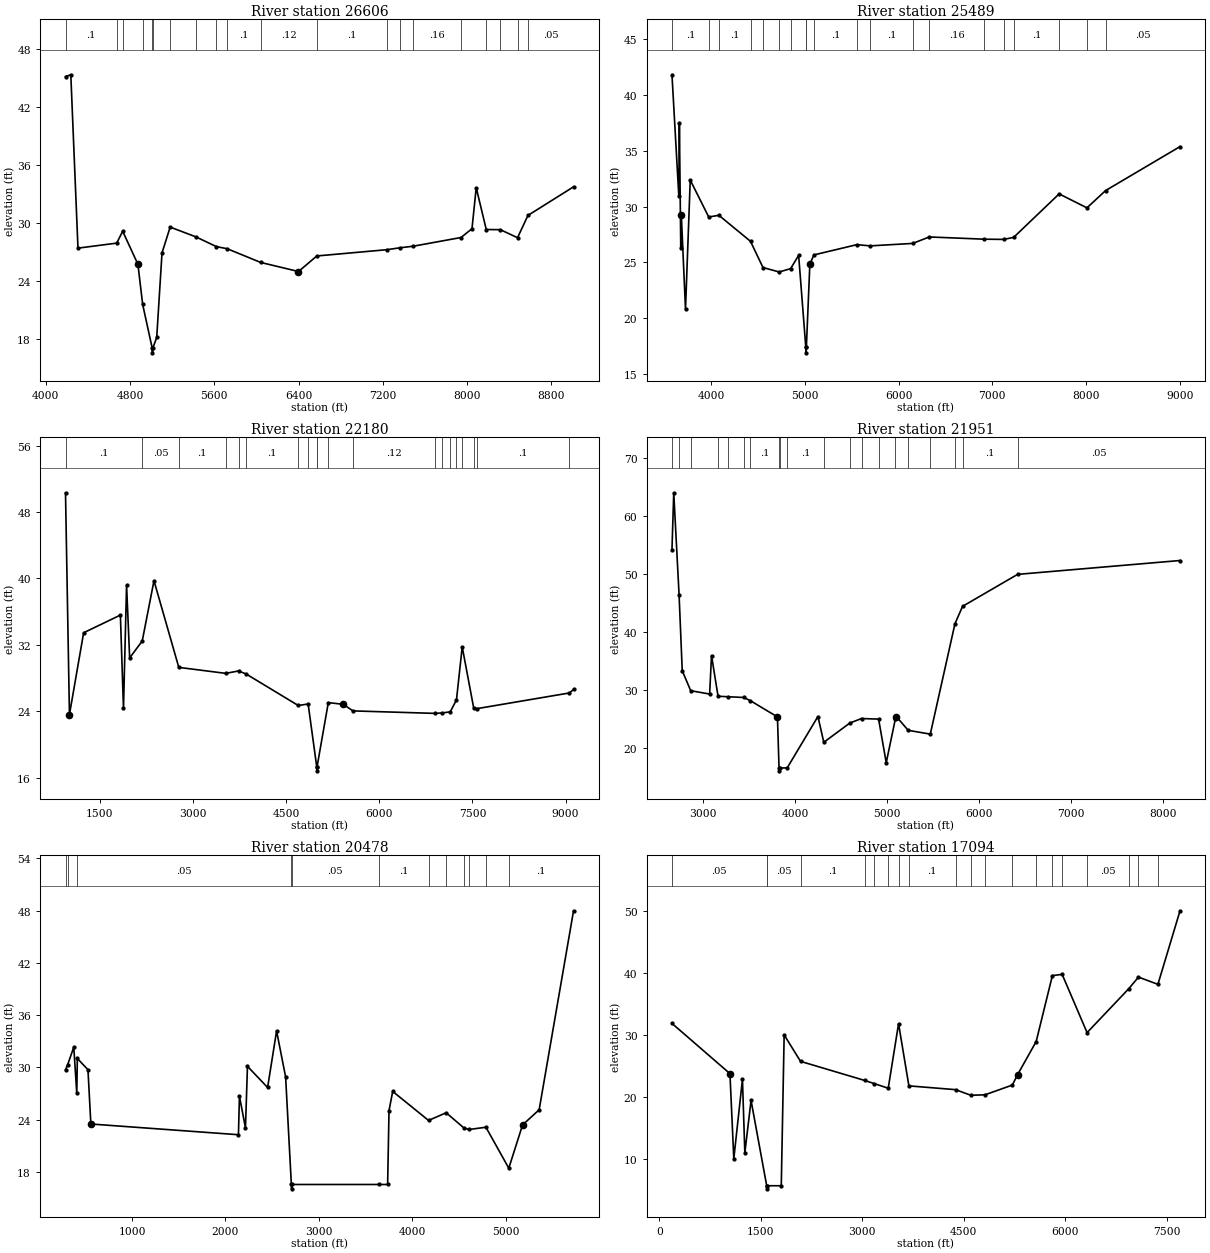
Type RM Length L Ch R = 1 ,26606   ,1117,1117,1117
BEGIN DESCRIPTION:
CAYAMON CREEK 26.0
END DESCRIPTION:
XS GIS Cut Line= 3
      2356087.72     13153746.87      2356187.72     13152946.85
      2356587.72     13148946.84
#Sta/Elev= 30
  4186.6   45.18    4237   45.36    4305   27.41    4673   27.93  4729.8   29.16
  4874.4   25.74  4919.6   21.58  5009.9   17.07  5012.7   16.57  5015.9   17.07
  5053.1   18.16  5103.4   26.92  5180.9   29.59  5424.8   28.58  5619.7   27.57
  5722.1   27.35  6040.7   25.93  6399.8   24.99  6574.1    26.6  7239.7   27.25
  7365.8   27.45  7490.1   27.61  7943.3   28.51    8048   29.42  8088.2   33.67
  8183.5   29.34  8318.1   29.32  8480.7   28.49  8579.8    30.8  9012.8   33.76
#Mann= 20 ,-1 , 0
  4186.6      .1       0    4673     .16       0  4729.8      .1       0
  4919.6     .05       0  5009.9    .033       0  5015.9     .05       0
  5180.9     .16       0  5424.8      .1       0  5619.7     .16       0
  5722.1      .1       0  6040.7     .12       0  6574.1      .1       0
  7239.7     .16       0  7365.8      .1       0  7490.1     .16       0
  7943.3     .05       0  8183.5      .1       0  8318.1     .12       0
  8480.7      .1       0  8579.8     .05       0
Bank Sta=4874.4,6399.8
XS Rating Curve= 0 ,0
Exp/Cntr=0.3,0.1

Type RM Length L Ch R = 1 ,25489   ,3309,3309,3309
BEGIN DESCRIPTION:
CAYAMON CREEK 25.0
END DESCRIPTION:
XS GIS Cut Line= 3
      2356137.75     13153696.84      2357287.72     13152896.85
      2356887.72     13148896.86
#Sta/Elev= 30
  3581.6   41.81  3654.5   30.96  3660.6   37.51  3675.4   26.31  3681.5   29.22
    3726   20.78  3776.5   32.37  3973.7   29.06  4082.2   29.21  4419.5   26.88
  4552.4   24.53  4725.5   24.13  4847.7   24.43  4933.2   25.62  5009.6   17.38
  5012.4   16.88  5015.6   17.38  5052.8   24.84  5096.3   25.66  5554.9   26.58
  5696.3   26.47  6150.2   26.69  6327.2   27.27  6913.2   27.07  7120.1   27.05
    7227   27.23  7712.7   31.13  8009.3   29.88  8208.6   31.43  9002.4   35.37
#Mann= 20 ,-1 , 0
  3581.6      .1       0  3973.7     .16       0  4082.2      .1       0
  4419.5     .16       0  4552.4     .16       0  4725.5      .1       0
  4847.7     .12       0  5009.6    .033       0  5015.6     .05       0
  5096.3      .1       0  5554.9     .16       0  5696.3      .1       0
  6150.2     .16       0  6327.2     .16       0  6913.2      .1       0
  7120.1     .16       0    7227      .1       0  7712.7     .16       0
  8009.3     .05       0  8208.6     .05       0
Bank Sta=3681.5,5052.8
XS Rating Curve= 0 ,0
Exp/Cntr=0.3,0.1

Type RM Length L Ch R = 1 ,22180   ,229,229,229
BEGIN DESCRIPTION:
CAYAMON CREEK 24.0
END DESCRIPTION:
XS GIS Cut Line= 3
      2356437.75     13157546.83      2359637.72     13155046.85
      2357637.72     13151446.86
#Sta/Elev= 30
   949.1   50.31  1012.5    23.6  1240.9   33.45  1832.7   35.58  1882.4   24.34
  1932.2   39.18  1981.9   30.42  2184.4   32.46  2373.5   39.72    2773   29.28
  3529.1   28.56  3734.7   28.85  3856.1   28.49    4696   24.69  4855.4   24.87
  4993.3   17.32    4996   16.82  4999.3   17.32    5180   25.04  5421.7   24.83
  5576.4   24.04  6897.2   23.74  7013.4   23.79  7143.7   23.93  7243.3   25.37
  7335.7   31.75  7521.6   24.35  7572.5   24.31  9061.6    26.2  9128.1   26.62
#Mann= 20 ,-1 , 0
   949.1      .1       0  2184.4     .05       0    2773      .1       0
  3529.1     .16       0  3734.7      .1       0  3856.1      .1       0
    4696     .12       0  4855.4     .05       0  4993.3    .033       0
  4999.3     .05       0    5180     .16       0  5576.4     .12       0
  6897.2     .12       0  7013.4      .1       0  7143.7      .1       0
  7243.3     .05       0  7335.7      .1       0  7521.6     .05       0
  7572.5      .1       0  9061.6     .16       0
Bank Sta=1012.5,5421.7
XS Rating Curve= 0 ,0
Exp/Cntr=0.3,0.1

Type RM Length L Ch R = 1 ,21951   ,1473,1473,1473
BEGIN DESCRIPTION:
CAYAMON CREEK 23.0
END DESCRIPTION:
XS GIS Cut Line= 3
      2359387.72     13157346.84      2359844.12     13155279.87
      2360037.66     13151876.83
#Sta/Elev= 30
  2661.1    54.2  2680.4   64.02  2738.4   46.44  2772.8   33.33  2864.9   29.89
  3070.7   29.31  3091.2   35.95  3162.3   28.93  3268.1   28.85  3442.5   28.72
  3514.7   28.16  3808.1   25.37  3825.5   16.57  3828.3   16.07  3831.5   16.57
  3913.9   16.57  4248.4   25.44  4312.3   20.99  4595.2   24.31  4722.4   25.09
  4908.4   24.99  4991.2   17.47  5091.3   25.07  5100.9   25.44  5229.7   23.06
  5470.6    22.4  5738.8   41.44  5821.7   44.44    6420   49.95  8186.4   52.34
#Mann= 20 ,-1 , 0
  2661.1     .05       0  2738.4      .1       0  2864.9     .05       0
  3162.3      .1       0  3268.1     .16       0  3442.5     .05       0
  3514.7      .1       0  3825.5    .033       0  3831.5      .1       0
  3913.9      .1       0  4312.3      .1       0  4595.2     .12       0
  4722.4      .1       0  4908.4     .05       0  5091.3     .16       0
  5229.7     .12       0  5470.6      .1       0  5738.8     .16       0
  5821.7      .1       0    6420     .05       0
#XS Ineff= 2 , 0
                         5100.36           25.41
Permanent Ineff=
       F       F
Bank Sta=3808.1,5100.9
XS Rating Curve= 0 ,0
Exp/Cntr=0.3,0.1

Type RM Length L Ch R = 1 ,20478   ,3384,3384,3384
BEGIN DESCRIPTION:
CAYAMON CREEK 22.0
END DESCRIPTION:
XS GIS Cut Line= 3
      2359306.56     13158969.29      2361023.57     13154582.22
      2360537.69     13154046.83
#Sta/Elev= 30
   288.9   29.74   310.4   30.27   377.4   32.33   409.6   27.03   415.4   31.03
   529.2   29.74     560   23.51  2138.6   22.28  2149.4    26.7  2213.7   23.06
  2235.2   30.13  2450.6    27.7  2546.6   34.19  2643.3   28.91  2704.7   16.57
  2707.5   16.07  2710.7   16.57  3637.8   16.57  3734.4   16.57  3749.3   25.06
  3788.7   27.25  4172.1   23.92  4360.5    24.8  4550.2   23.06  4606.1   22.88
  4785.8   23.14  5030.4   18.44  5177.9   23.41    5355   25.14    5723   47.98
#Mann= 12 ,-1 , 0
   288.9     .05       0   310.4      .1       0   415.4     .05       0
  2704.7     .07       0  2710.7     .05       0  3637.8      .1       0
  4172.1     .12       0  4360.5      .1       0  4550.2     .12       0
  4606.1      .1       0  4785.8     .12       0  5030.4      .1       0
Bank Sta=560,5177.9
XS Rating Curve= 0 ,0
Exp/Cntr=0.3,0.1

Type RM Length L Ch R = 1 ,17094   ,534,534,534
BEGIN DESCRIPTION:
CAYAMON CREEK 21.0
END DESCRIPTION:
XS GIS Cut Line= 3
      2360437.74     13157746.83      2363637.72     13154146.85
      2361837.74     13152146.87
#Sta/Elev= 30
   188.2   31.86  1044.9   23.75  1101.7      10  1229.7   22.82  1264.8   10.94
  1356.8   19.42  1587.9    5.64  1590.7    5.14  1593.9    5.64  1803.3    5.64
    1846      30  2087.8   25.73  3034.7   22.65  3173.7   22.15  3383.8   21.39
  3536.5   31.81  3689.2   21.77    4378   21.16  4605.1   20.25  4814.3   20.33
  5217.8    21.9  5295.2   23.58    5570   28.93  5809.5   39.58  5953.7   39.78
  6322.1   30.37  6939.6   37.48  7081.7   39.34  7368.9   38.17  7695.5   50.05
#Mann= 20 ,-1 , 0
   188.2     .05       0  1587.9     .07       0  1593.9     .05       0
  2087.8      .1       0  3034.7      .1       0  3173.7     .16       0
  3383.8     .08       0  3536.5     .05       0  3689.2      .1       0
    4378      .1       0  4605.1     .16       0  4814.3     .12       0
  5217.8      .1       0    5570     .05       0  5809.5     .05       0
  5953.7      .1       0  6322.1     .05       0  6939.6     .08       0
  7081.7     .05       0  7368.9     .05       0
Bank Sta=1044.9,5295.2
XS Rating Curve= 0 ,0
Exp/Cntr=0.3,0.1

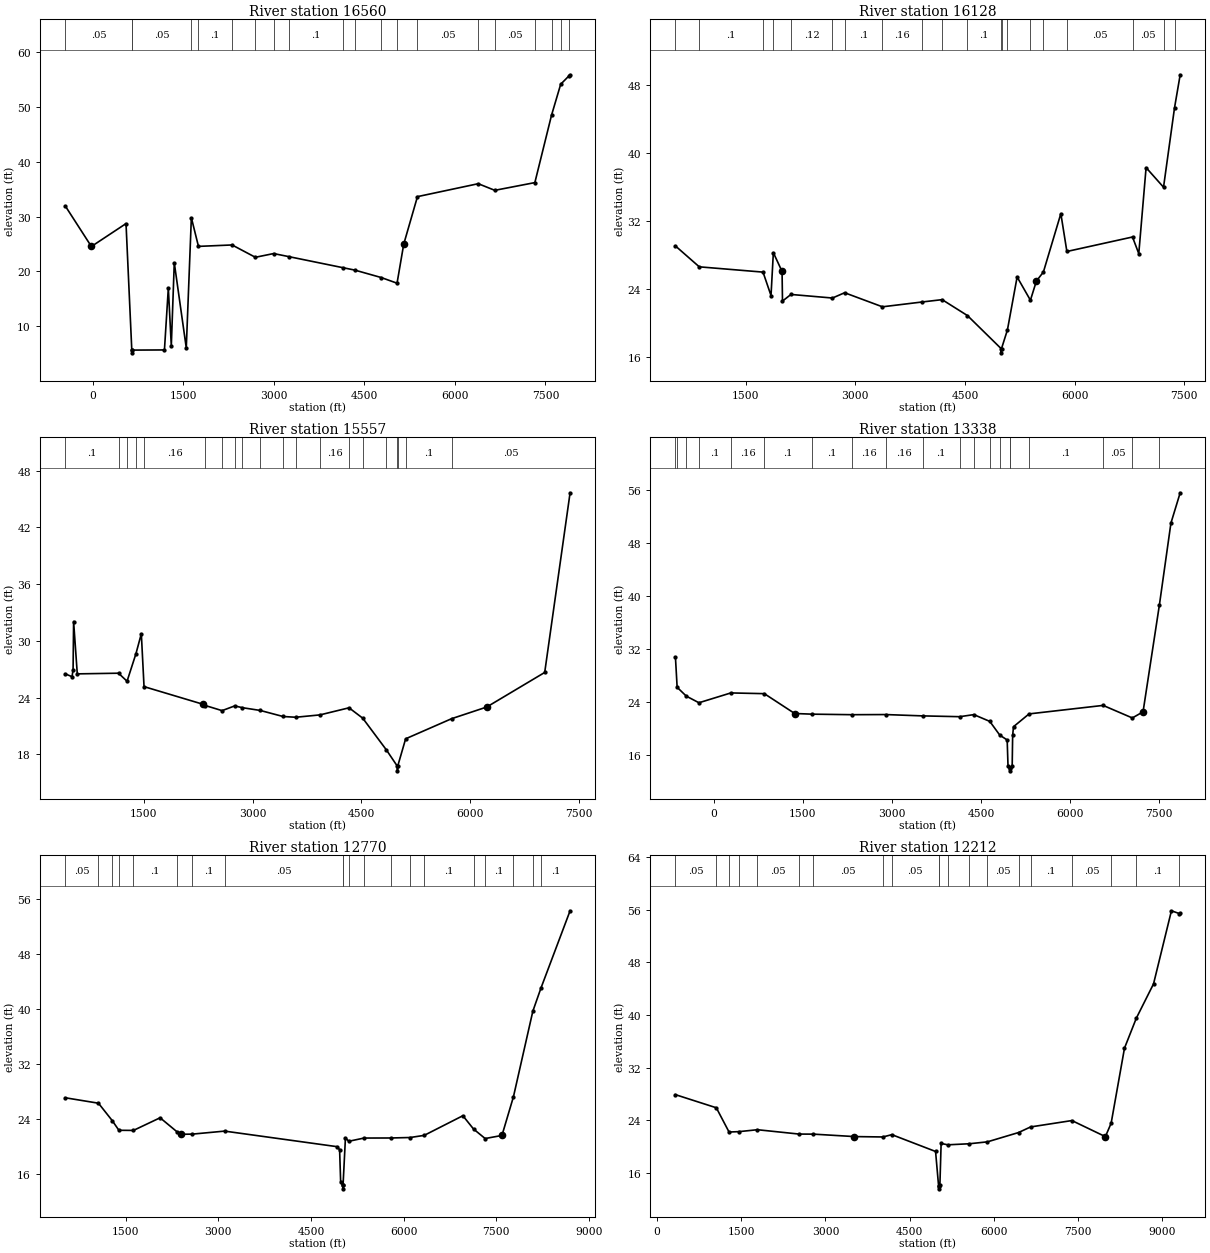
Type RM Length L Ch R = 1 ,16560   ,432,432,432
BEGIN DESCRIPTION:
CAYAMON CREEK 20.0
END DESCRIPTION:
XS GIS Cut Line= 3
      2360537.74     13158196.83      2364137.72     13154196.85
      2364837.72     13151296.86
#Sta/Elev= 30
  -456.4   31.93   -24.8   24.55   549.2   28.73   644.9    5.64   647.6    5.14
   650.9    5.64    1186    5.67  1250.3   16.95  1299.6    6.42    1349   21.58
  1547.8    6.04    1632    29.8  1749.7   24.57  2306.8   24.83  2692.8   22.58
  2995.9   23.26  3242.5   22.71  4153.1   20.66  4341.3   20.24  4779.5   18.88
  5040.8   17.85  5151.3   24.97  5378.9   33.65  6386.5   36.01  6660.6    34.8
  7324.5   36.21  7600.6    48.5  7752.6   54.16  7889.9   55.69  7908.3   55.89
#Mann= 20 ,-1 , 0
  -456.4     .05       0   644.9     .07       0   650.9     .05       0
    1632     .05       0  1749.7      .1       0  2306.8     .16       0
  2692.8     .08       0  2995.9     .16       0  3242.5      .1       0
  4153.1     .16       0  4341.3      .1       0  4779.5     .12       0
  5040.8      .1       0  5378.9     .05       0  6386.5      .1       0
  6660.6     .05       0  7324.5      .1       0  7600.6     .05       0
  7752.6      .1       0  7889.9     .05       0
Bank Sta=-24.8,5151.3
XS Rating Curve= 0 ,0
Exp/Cntr=0.3,0.1

Type RM Length L Ch R = 1 ,16128   ,571,571,571
BEGIN DESCRIPTION:
CAYAMON CREEK 19.0
END DESCRIPTION:
XS GIS Cut Line= 3
       2362160.3     13157905.92      2364580.23     13154158.09
      2364987.72     13151746.88
#Sta/Elev= 30
   538.8   29.08   864.9   26.63  1737.3   26.01  1846.6   23.26  1878.6   28.29
  1997.8   26.09  2003.7   22.61  2119.3   23.39    2687   22.97  2853.9   23.59
  3371.2   21.94  3917.8   22.51  4188.3   22.78  4534.8   20.91  4994.8   17.04
  4997.5   16.54  5000.8   17.04  5081.6   19.23  5214.2   25.44  5396.2   22.71
  5477.9   24.96  5573.7   26.02  5812.6   32.87  5895.1   28.43    6793   30.13
  6878.9   28.18  6978.9   38.27  7217.6   35.97  7367.9   45.28  7445.4   49.16
#Mann= 20 ,-1 , 0
   538.8      .1       0   864.9      .1       0  1737.3     .05       0
  1878.6     .08       0  2119.3     .12       0    2687     .16       0
  2853.9      .1       0  3371.2     .16       0  3917.8     .16       0
  4188.3     .12       0  4534.8      .1       0  4994.8     .07       0
  5000.8     .12       0  5081.6      .1       0  5396.2     .05       0
  5573.7      .1       0  5895.1     .05       0    6793     .05       0
  7217.6      .1       0  7367.9     .05       0
Bank Sta=1997.8,5477.9
XS Rating Curve= 0 ,0
Exp/Cntr=0.3,0.1

Type RM Length L Ch R = 1 ,15557   ,2219,2219,2219
BEGIN DESCRIPTION:
CAYAMON CREEK 18.0
END DESCRIPTION:
XS GIS Cut Line= 3
      2362337.72     13157846.86      2365137.72     13154246.85
      2365137.72     13151846.86
#Sta/Elev= 30
   418.2   26.51   510.5   26.21     525   26.96   532.2   32.05   582.9   26.51
  1151.5   26.58  1269.3   25.73  1391.8   28.64  1466.1   30.76  1503.4   25.16
    2314    23.3  2348.9   23.16  2579.6   22.62  2753.8   23.12  2861.1   22.93
    3106   22.64  3419.9      22  3595.8   21.92  3930.6   22.17  4330.5   22.92
  4519.5   21.82    4846   18.46  4995.9   16.75  4998.7   16.25  5001.9   16.75
  5111.1   19.64  5745.9   21.77  6228.9      23  7028.9   26.66  7378.9   45.67
#Mann= 20 ,-1 , 0
   418.2      .1       0  1151.5     .16       0  1269.3     .05       0
  1391.8     .08       0  1503.4     .16       0  2348.9     .12       0
  2579.6      .1       0  2753.8     .16       0  2861.1     .16       0
    3106     .16       0  3419.9      .1       0  3595.8     .16       0
  3930.6     .16       0  4330.5      .1       0  4519.5      .1       0
    4846     .12       0  4995.9     .07       0  5001.9     .12       0
  5111.1      .1       0  5745.9     .05       0
Bank Sta=2314,6228.9
XS Rating Curve= 0 ,0
Exp/Cntr=0.3,0.1

Type RM Length L Ch R = 1 ,13338   ,568,568,568
BEGIN DESCRIPTION:
CAYAMON CREEK 17.0
END DESCRIPTION:
XS GIS Cut Line= 3
       2363087.7     13157696.87      2367087.72     13153696.85
      2365287.73     13151496.86
#Sta/Elev= 30
  -646.1   30.77  -617.4   26.22  -463.3   24.89  -250.4   23.89   286.9   25.37
   850.9   25.26  1362.1   22.27  1657.8   22.17  2328.1   22.09    2894   22.11
  3517.4   21.91  4141.3   21.79  4378.8    22.1  4647.5   21.08  4815.6   19.01
  4940.1   18.28  4954.2   14.36  4979.5   14.13  4982.2   13.63  4985.5   14.13
  5024.4   14.34  5032.3   18.99  5046.7   20.28  5308.7   22.21  6555.6   23.49
  7047.5    21.6  7228.1   22.52  7503.4   38.63  7697.5   50.96  7853.3   55.53
#Mann= 20 ,-1 , 0
  -646.1     .08       0  -617.4      .1       0  -463.3     .16       0
  -250.4      .1       0   286.9     .16       0   850.9      .1       0
  1657.8      .1       0  2328.1     .16       0    2894     .16       0
  3517.4      .1       0  4141.3     .05       0  4378.8     .05       0
  4647.5      .1       0  4815.6     .12       0  4979.5     .07       0
  4985.5     .12       0  5308.7      .1       0  6555.6     .05       0
  7047.5      .1       0  7503.4     .05       0
Bank Sta=1362.1,7228.1
XS Rating Curve= 0 ,0
Exp/Cntr=0.3,0.1

Type RM Length L Ch R = 1 ,12770   ,558,558,558
BEGIN DESCRIPTION:
CAYAMON CREEK 16.0
END DESCRIPTION:
XS GIS Cut Line= 3
      2365637.73     13157746.83      2367637.72     13153746.85
       2365337.7     13150846.83
#Sta/Elev= 30
   523.1   27.13  1059.3   26.34  1281.4   23.82  1390.3    22.4  1625.5   22.38
  2057.6   24.22  2326.1   22.22    2393   21.82    2577   21.84  3102.4   22.28
  4928.1   20.01  4964.5   19.55  4981.2   14.92  5013.9   14.38  5016.6   13.88
  5019.9   14.38    5059   21.31  5112.2    20.8  5359.6   21.27  5797.9   21.28
  6107.7   21.35  6334.4   21.66  6960.5   24.52  7133.5   22.58  7321.1    21.2
  7593.4   21.65  7779.2   27.27  8093.5   39.73    8224   43.07  8696.6   54.34
#Mann= 20 ,-1 , 0
   523.1     .05       0  1059.3      .1       0  1281.4     .16       0
  1390.3     .07       0  1625.5      .1       0  2326.1     .05       0
    2577      .1       0  3102.4     .05       0  5013.9     .07       0
  5019.9     .12       0  5112.2      .1       0  5359.6      .1       0
  5797.9      .1       0  6107.7     .05       0  6334.4      .1       0
  7133.5     .05       0  7321.1      .1       0  7779.2      .1       0
  8093.5     .05       0    8224      .1       0
Bank Sta=2393,7593.4
XS Rating Curve= 0 ,0
Exp/Cntr=0.3,0.1

Type RM Length L Ch R = 1 ,12212   ,541,541,541
BEGIN DESCRIPTION:
CAYAMON CREEK 15.0
END DESCRIPTION:
XS GIS Cut Line= 3
      2365787.74     13157796.82      2368187.72     13153796.85
      2365287.71     13150596.84
#Sta/Elev= 30
   331.4   27.91    1059   25.92  1285.6   22.24  1463.8    22.3  1790.9   22.59
  2531.8   21.93  2787.7   21.92  3515.1   21.55  4022.6   21.49  4183.5   21.84
  4961.1   19.29  5014.4   14.12  5017.2   13.62  5020.4   14.12  5038.4   14.26
    5060   20.51  5177.8    20.3    5562   20.46  5883.7   20.75  6437.3   22.16
  6651.6   23.01  7387.3   23.98  7983.6   21.54  8086.1   23.58  8323.6   34.97
  8534.5   39.52  8840.6   44.72  9158.9   55.81  9301.7   55.38  9314.7   55.41
#Mann= 20 ,-1 , 0
   331.4     .05       0    1059     .16       0  1285.6     .07       0
  1463.8      .1       0  1790.9     .05       0  2531.8     .05       0
  2787.7     .05       0  4022.6      .1       0  4183.5     .05       0
  5014.4     .07       0  5020.4     .07       0  5177.8     .05       0
    5562      .1       0  5883.7     .05       0  6437.3     .05       0
  6651.6      .1       0  7387.3     .05       0  8086.1      .1       0
  8534.5      .1       0  9301.7     .05       0
Bank Sta=3515.1,7983.6
XS Rating Curve= 0 ,0
Exp/Cntr=0.3,0.1