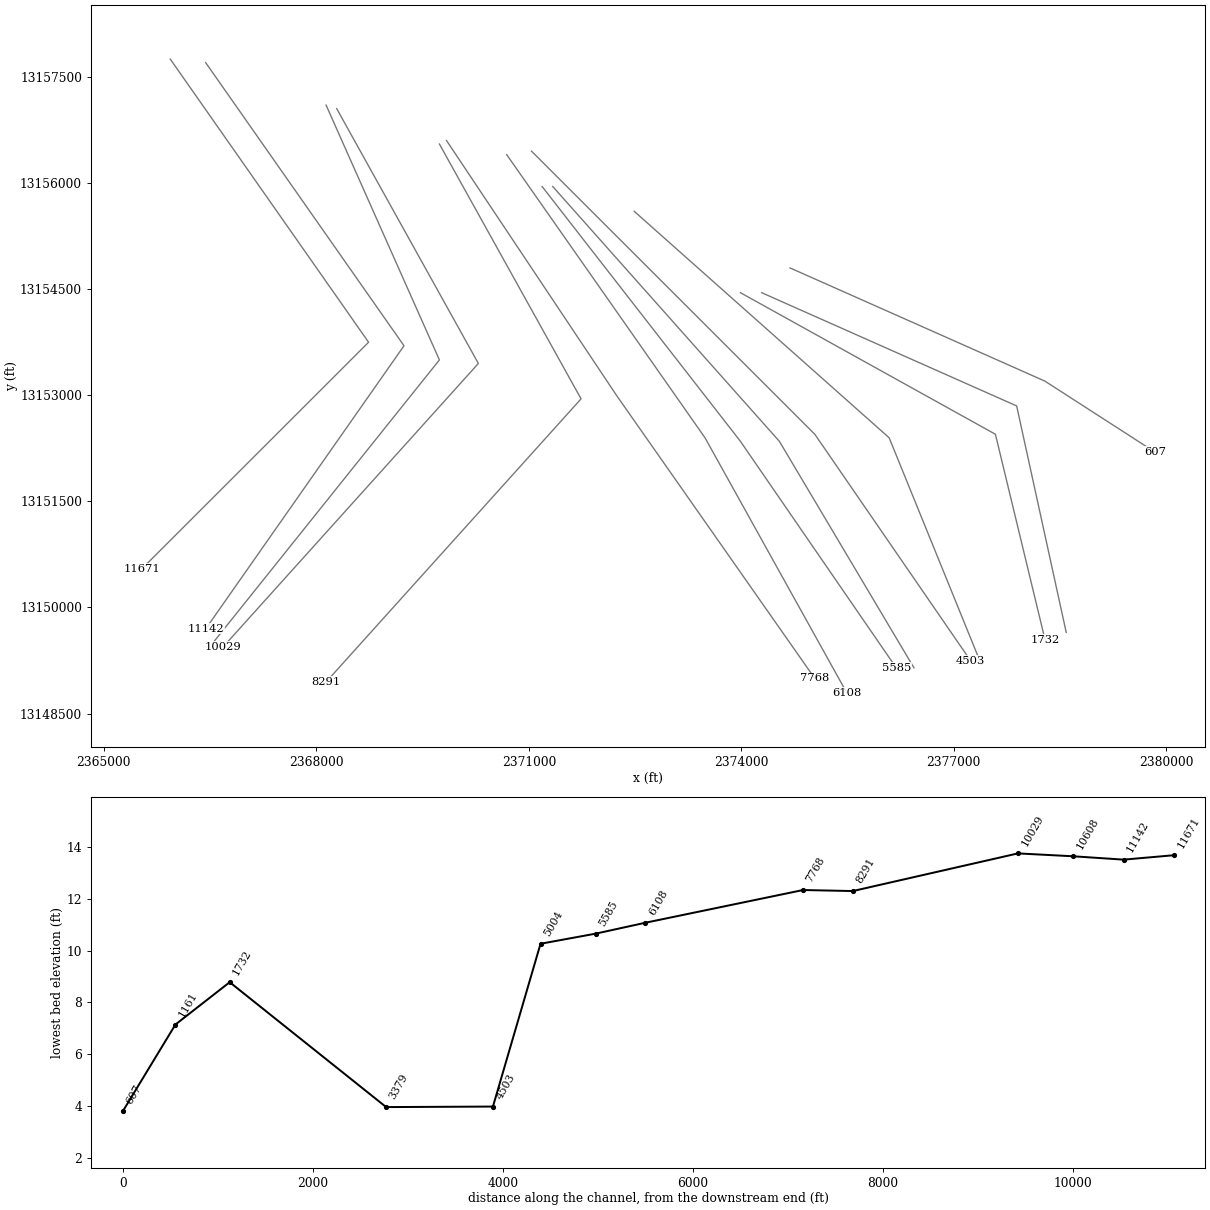
HEC-RAS study CAYAMON CREEK.prj: CAYAMON CREEK Base Level Engineering

--- CAYAMON CREEK.g01 (geometry) --- (continued)

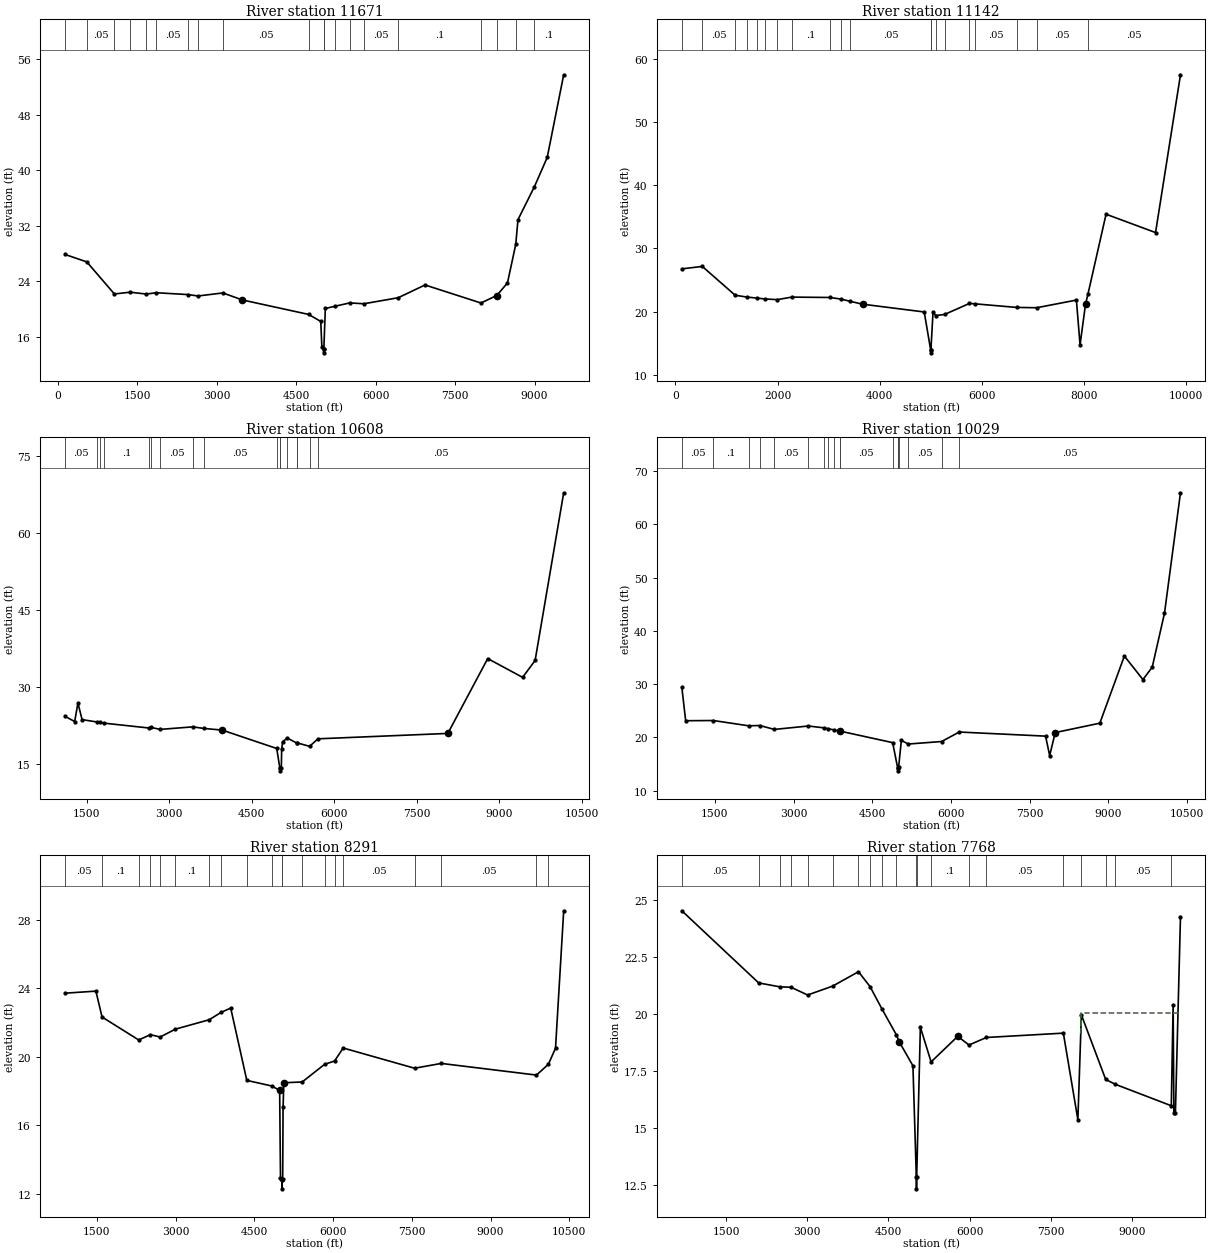
Type RM Length L Ch R = 1 ,11671   ,529,529,529
BEGIN DESCRIPTION:
CAYAMON CREEK 14.0
END DESCRIPTION:
XS GIS Cut Line= 3
      2365937.72     13157746.85      2368737.72     13153746.85
      2365537.72     13150546.85
#Sta/Elev= 30
   141.8   27.86   552.1   26.79  1072.7   22.16  1368.8   22.42  1671.5   22.15
  1866.6   22.34  2467.3   22.07  2650.5   21.87  3119.5   22.31  3486.8    21.3
  4738.3   19.21  4966.4    18.2  4987.8   14.46  5018.4   14.17  5021.1   13.67
  5024.4   14.17  5052.7   20.07  5230.3   20.38  5511.1   20.87  5781.2   20.75
  6428.1   21.62  6933.6   23.46  7988.4   20.86  8287.4   21.94  8489.2   23.76
  8645.7   29.33  8687.2   32.88  8996.6   37.62  9238.8   41.85  9549.9   53.78
#Mann= 20 ,-1 , 0
   141.8     .05       0   552.1     .05       0  1072.7     .07       0
  1368.8     .05       0  1671.5     .16       0  1866.6     .05       0
  2467.3     .16       0  2650.5     .16       0  3119.5     .05       0
  4738.3     .12       0  5018.4     .07       0  5024.4     .07       0
  5230.3      .1       0  5511.1      .1       0  5781.2     .05       0
  6428.1      .1       0  7988.4     .05       0  8287.4      .1       0
  8645.7      .1       0  8996.6      .1       0
Bank Sta=3486.8,8287.4
XS Rating Curve= 0 ,0
Exp/Cntr=0.3,0.1

Type RM Length L Ch R = 1 ,11142   ,534,534,534
BEGIN DESCRIPTION:
CAYAMON CREEK 13.0
END DESCRIPTION:
XS GIS Cut Line= 3
      2366437.72     13157696.86      2369237.72     13153696.85
      2366437.69     13149696.81
#Sta/Elev= 30
     126   26.77   526.9   27.16  1170.8    22.6  1406.5   22.31  1591.1   22.16
  1748.1   22.02  1995.2   21.91  2278.5   22.31  3028.8   22.25  3237.5      22
  3425.3   21.64  3665.9   21.19    4873   19.96  4998.2      14    5001    13.5
  5004.2      14  5045.2   19.91  5101.1   19.39  5272.6   19.57  5758.3   21.31
  5861.9   21.25  6680.1   20.68  7076.4   20.63  7852.8   21.84  7924.7   14.77
  8031.9    21.2  8079.5   22.79  8433.9   35.41    9403   32.51  9891.3   57.45
#Mann= 20 ,-1 , 0
     126      .1       0   526.9     .05       0  1170.8      .1       0
  1406.5     .05       0  1591.1     .16       0  1748.1     .05       0
  1995.2     .16       0  2278.5      .1       0  3028.8     .05       0
  3237.5      .1       0  3425.3     .05       0  4998.2     .07       0
  5004.2     .05       0  5101.1     .05       0  5272.6     .05       0
  5758.3      .1       0  5861.9     .05       0  6680.1      .1       0
  7076.4     .05       0  8079.5     .05       0
Bank Sta=3665.9,8031.9
XS Rating Curve= 0 ,0
Exp/Cntr=0.3,0.1

Type RM Length L Ch R = 1 ,10608   ,579,579,579
BEGIN DESCRIPTION:
CAYAMON CREEK 12.0
END DESCRIPTION:
XS GIS Cut Line= 3
      2368137.74     13157096.81      2369737.72     13153496.85
      2366537.72     13149496.85
#Sta/Elev= 30
  1108.9   24.27  1283.9   23.25  1343.4   26.86  1418.7   23.62  1692.8   23.16
  1736.2   23.08  1814.6   22.94  2633.4   21.99  2662.7   22.12    2838   21.72
  3432.6   22.21    3634    21.9    3965   21.58  4956.1   17.99  5013.3   14.13
    5016   13.63  5019.3   14.13  5039.5   14.19  5045.7    17.8    5062   19.28
  5146.3   20.03  5319.1   19.06  5322.1    19.1    5553   18.41  5705.8   19.88
  8065.1   20.93  8790.2   35.54  9424.1   31.87  9651.4   35.17 10170.9   67.89
#Mann= 17 ,-1 , 0
  1108.9     .05       0  1692.8      .1       0  1736.2     .05       0
  1814.6      .1       0  2633.4     .05       0  2662.7      .1       0
    2838     .05       0  3432.6      .1       0    3634     .05       0
  4956.1     .12       0  5013.3     .07       0  5019.3     .12       0
  5146.3     .05       0  5319.1      .1       0  5322.1     .05       0
    5553     .16       0  5705.8     .05       0
Bank Sta=3965,8065.1
XS Rating Curve= 0 ,0
Exp/Cntr=0.3,0.1

Type RM Length L Ch R = 1 ,10029   ,1738,1738,1738
BEGIN DESCRIPTION:
CAYAMON CREEK 11.0
END DESCRIPTION:
XS GIS Cut Line= 3
       2368287.7     13157046.89      2370287.72     13153446.85
      2366687.75     13149446.89
#Sta/Elev= 30
   872.2   29.43   945.5   23.14  1471.8   23.18  2144.4   22.19  2359.4   22.24
  2633.7   21.51  3283.7   22.15  3581.2    21.8  3664.8   21.63    3776   21.41
    3884    21.2  3886.8   21.19  4888.8   19.03  4984.6   14.24  4987.4   13.74
  4990.6   14.24  5002.3   14.42  5054.4   19.44  5188.3   18.77  5821.9   19.24
  6157.1   21.02  7801.9   20.25  7879.7    16.6  7985.8   20.92  8835.6   22.68
  9302.8   35.27    9657   30.86  9833.8   33.19 10067.4   43.32 10371.9    65.9
#Mann= 18 ,-1 , 0
   872.2     .05       0  1471.8      .1       0  2144.4     .05       0
  2359.4      .1       0  2633.7     .05       0  3283.7      .1       0
  3581.2     .05       0  3664.8      .1       0    3776     .05       0
    3884      .1       0  3886.8     .05       0  4888.8     .12       0
  4984.6     .07       0  4990.6     .12       0  5002.3      .1       0
  5188.3     .05       0  5821.9      .1       0  6157.1     .05       0
Bank Sta=3886.8,7985.8
XS Rating Curve= 0 ,0
Exp/Cntr=0.3,0.1

Type RM Length L Ch R = 1 ,8291    ,523,523,523
BEGIN DESCRIPTION:
CAYAMON CREEK 10.0
END DESCRIPTION:
XS GIS Cut Line= 3
      2369737.73     13156546.84      2371737.72     13152946.85
      2368137.71     13148946.85
#Sta/Elev= 30
   893.1   23.71  1481.1   23.83  1598.2   22.32  2296.1   20.98  2520.5   21.29
  2704.5   21.15  2995.1   21.61  3640.2   22.16  3866.2   22.59  4049.3   22.84
    4356   18.62    4836   18.29  4981.6   18.03  4997.6   12.92  5022.2   12.79
  5024.9   12.29  5028.2   12.79  5039.4   12.89  5046.8   17.05    5061   18.48
  5412.4   18.53  5838.7   19.56  6027.2   19.75  6192.1   20.51    7552   19.33
  8060.3   19.61  9874.2   18.93 10101.2   19.56   10237    20.5 10392.8   28.52
#Mann= 20 ,-1 , 0
   893.1     .05       0  1598.2      .1       0  2296.1      .1       0
  2520.5     .05       0  2704.5     .05       0  2995.1      .1       0
  3640.2     .16       0  3866.2      .1       0    4356      .1       0
    4836     .16       0  5022.2     .07       0  5028.2     .16       0
  5412.4     .07       0  5838.7      .1       0  6027.2      .1       0
  6192.1     .05       0    7552     .05       0  8060.3     .05       0
  9874.2     .08       0 10101.2     .05       0
Bank Sta=4981.6,5061
XS Rating Curve= 0 ,0
Exp/Cntr=0.3,0.1

Type RM Length L Ch R = 1 ,7768    ,1660,1660,1660
BEGIN DESCRIPTION:
CAYAMON CREEK 9.0
END DESCRIPTION:
XS GIS Cut Line= 3
      2369837.74     13156596.82      2372237.72     13152996.85
       2375037.7     13148996.89
#Sta/Elev= 30
   684.1   24.51  2103.7   21.35    2490   21.18  2701.7   21.16  3006.7   20.82
  3469.7   21.21  3946.6   21.84    4160   21.19  4377.6   20.22  4643.1   19.09
  4699.7   18.77  4952.1   17.72  5015.1   12.83  5017.9   12.33  5021.1   12.83
  5089.6   19.41  5287.7   17.89  5779.7   19.01  5987.4   18.63  6307.9   18.96
  7730.1   19.15  7998.3   15.36  8062.9   19.95  8512.5   17.12  8688.4   16.91
  9723.6   15.97  9757.8    20.4  9771.3   15.66  9799.6   15.67  9893.3   24.25
#Mann= 20 ,-1 , 0
   684.1     .05       0  2103.7      .1       0    2490     .05       0
  2701.7      .1       0  3006.7      .1       0  3469.7      .1       0
  3946.6     .05       0    4160      .1       0  4377.6     .05       0
  4643.1     .05       0  5015.1     .07       0  5021.1     .05       0
  5287.7      .1       0  5987.4     .05       0  6307.9     .05       0
  7730.1      .1       0  8062.9     .05       0  8512.5     .07       0
  8688.4     .05       0  9723.6      .1       0
#XS Ineff= 2 , 0
       0                 8051.14       0   20.03
Permanent Ineff=
       F       T
Bank Sta=4699.7,5779.7
XS Rating Curve= 0 ,0
Exp/Cntr=0.3,0.1

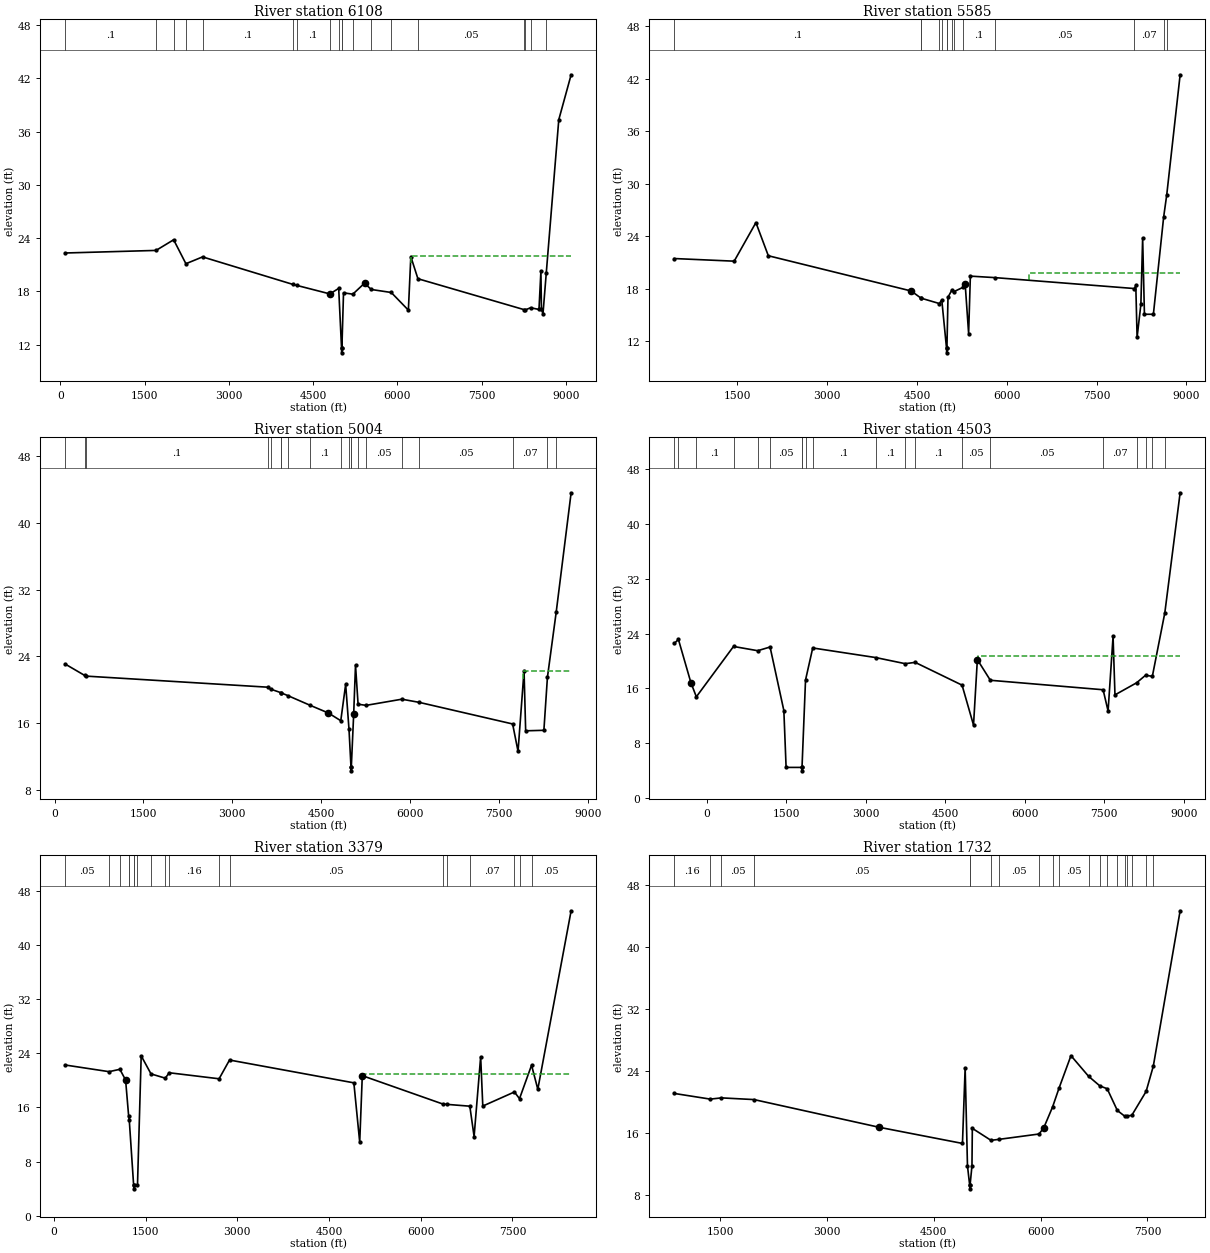
Type RM Length L Ch R = 1 ,6108    ,523,523,523
BEGIN DESCRIPTION:
CAYAMON CREEK 8.0
END DESCRIPTION:
XS GIS Cut Line= 3
       2370687.7     13156396.88      2373487.72     13152396.85
      2375487.72     13148796.86
#Sta/Elev= 30
    90.5   22.32  1703.8   22.61  2017.2   23.81  2235.5   21.11  2531.7   21.88
  4139.9   18.78  4207.9   18.67  4797.9   17.71  4954.7   18.33  5005.6   11.57
  5008.4   11.07  5011.6   11.57  5040.6   17.83  5206.2   17.68  5414.7   18.92
  5532.6   18.21  5889.9   17.87  6194.9   15.88  6238.4   21.91  6364.7   19.42
    8258   15.93  8277.2   15.91  8369.3   16.15  8519.4   15.96  8553.7   20.27
  8562.9   16.02  8590.3   15.45  8648.5   20.02  8871.8   37.34  9091.4    42.4
#Mann= 19 ,-1 , 0
    90.5      .1       0  1703.8     .16       0  2017.2      .1       0
  2235.5     .05       0  2531.7      .1       0  4139.9     .12       0
  4207.9      .1       0  4797.9     .12       0  4954.7     .05       0
  5005.6     .03       0  5011.6     .05       0  5206.2      .1       0
  5532.6     .05       0  5889.9      .1       0  6364.7     .05       0
    8258     .07       0  8277.2     .05       0  8369.3     .12       0
  8648.5      .1       0
#XS Ineff= 2 , 0
       0                 6232.95       0      22
Permanent Ineff=
       F       T
Bank Sta=4797.9,5414.7
XS Rating Curve= 0 ,0
Exp/Cntr=0.3,0.1

Type RM Length L Ch R = 1 ,5585    ,581,581,581
BEGIN DESCRIPTION:
CAYAMON CREEK 7.0
END DESCRIPTION:
XS GIS Cut Line= 3
      2371187.72     13155946.85      2373987.72     13152346.85
      2376187.72     13149146.85
#Sta/Elev= 30
   450.5   21.43  1448.6   21.13  1811.5   25.54  2018.7   21.75  4404.9   17.72
  4564.6   16.92  4574.9   16.89  4872.2   16.29  4915.1   16.68  4994.6   11.15
  4997.4   10.65  5000.6   11.15  5018.6   17.01  5087.3   17.87  5112.9   17.63
  5269.1   18.14  5305.5   18.51  5363.1   12.86  5392.1   19.42  5801.9   19.25
  8131.7      18  8154.2   18.36    8176   12.42  8239.2    16.2  8268.7   23.79
  8298.5   15.06    8448   15.06  8619.7   26.19  8671.1   28.72  8894.5   42.44
#Mann= 14 ,-1 , 0
   450.5      .1       0  4564.6     .05       0  4574.9      .1       0
  4872.2     .05       0  4915.1     .12       0  4994.6     .03       0
  5000.6     .12       0  5087.3     .12       0  5112.9     .05       0
  5269.1      .1       0  5801.9     .05       0  8131.7     .07       0
  8619.7      .1       0  8671.1     .05       0
#XS Ineff= 2 , 0
       0                    6375       0   19.77
Permanent Ineff=
       F       T
Bank Sta=4404.9,5305.5
XS Rating Curve= 0 ,0
Exp/Cntr=0.3,0.1

Type RM Length L Ch R = 1 ,5004    ,501,501,501
BEGIN DESCRIPTION:
CAYAMON CREEK 6.0
END DESCRIPTION:
XS GIS Cut Line= 3
       2371337.7     13155946.88      2374537.72     13152346.85
       2376437.7     13149146.88
#Sta/Elev= 30
   181.5   23.05   506.8    21.7   525.1   21.62  3597.2   20.29  3646.3   20.06
  3815.9   19.64  3828.4    19.6  3940.2   19.27  4302.9   18.15  4623.1   17.19
  4830.8   16.27  4913.3   20.63  4969.9   15.22    5003   10.76  5005.7   10.26
    5009   10.76  5048.8   17.08  5079.6   22.94  5122.8   18.25  5257.8   18.11
    5862   18.85  6155.4   18.47    7732   15.88  7823.5    12.6  7924.8   22.28
  7952.2   15.06  8259.9   15.12  8319.6   21.47  8467.8   29.29  8719.7    43.6
#Mann= 20 ,-1 , 0
   181.5      .1       0   506.8     .05       0   525.1      .1       0
  3597.2     .16       0  3646.3      .1       0  3815.9     .16       0
  3828.4      .1       0  3940.2     .16       0  4302.9      .1       0
  4830.8     .05       0  4969.9     .05       0    5003     .03       0
    5009     .05       0  5122.8      .1       0  5257.8     .05       0
    5862      .1       0  6155.4     .05       0    7732     .07       0
  8319.6      .1       0  8467.8     .05       0
#XS Ineff= 2 , 0
                         7914.77           22.22
Permanent Ineff=
       F       F
Bank Sta=4623.1,5048.8
XS Rating Curve= 0 ,0
Exp/Cntr=0.3,0.1

Type RM Length L Ch R = 1 ,4503    ,1124,1124,1124
BEGIN DESCRIPTION:
CAYAMON CREEK 5.0
END DESCRIPTION:
XS GIS Cut Line= 3
      2371037.73     13156446.85      2375037.72     13152446.85
       2377237.7     13149246.89
#Sta/Elev= 30
  -607.6   22.58  -531.6   23.14  -296.5   16.85  -193.6   14.78   507.8   22.12
   964.2    21.5  1197.2   22.04  1457.1   12.78  1499.6    4.49  1793.6    4.49
  1796.3    3.99  1799.6    4.49  1866.1   17.23  2001.9    21.9  3191.1    20.5
  3746.1   19.61  3934.2    19.8    4819   16.48  5035.1   10.66  5107.4    20.2
  5352.6   17.19  7479.6   15.81  7573.4   12.71  7667.4   23.58  7703.3   15.06
  8110.9   16.82  8280.2   17.92  8408.7   17.77  8643.9   27.03  8932.5   44.52
#Mann= 20 ,-1 , 0
  -607.6      .1       0  -531.6     .07       0  -193.6      .1       0
   507.8     .05       0   964.2      .1       0  1197.2     .05       0
  1793.6     .07       0  1799.6     .05       0  1866.1     .05       0
  2001.9      .1       0  3191.1      .1       0  3746.1     .16       0
  3934.2      .1       0    4819     .05       0  5352.6     .05       0
  7479.6     .07       0  8110.9     .12       0  8280.2     .07       0
  8408.7      .1       0  8643.9     .05       0
#XS Ineff= 2 , 0
                         5118.18           20.71
Permanent Ineff=
       F       F
Bank Sta=-296.5,5107.4
XS Rating Curve= 0 ,0
Exp/Cntr=0.3,0.1

Type RM Length L Ch R = 1 ,3379    ,1647,1647,1647
BEGIN DESCRIPTION:
CAYAMON CREEK 4.0
END DESCRIPTION:
XS GIS Cut Line= 3
      2372487.73     13155596.85      2376087.72     13152396.85
      2377387.72     13149196.86
#Sta/Elev= 30
   188.9   22.26     903   21.28  1079.8   21.63  1173.5   20.05  1223.8   14.68
  1233.1   14.19  1305.2    4.47  1307.9    3.97  1311.2    4.47  1367.9    4.47
  1428.6   23.62  1589.2   20.95  1822.6   20.32  1886.6   21.12  2702.5   20.23
  2873.1      23  4906.4   19.63  5002.2   10.86  5044.3   20.69  6361.3    16.5
  6429.3   16.45  6802.8   16.18  6872.8    11.7  6980.1   23.49    7015    16.2
    7532   18.28  7615.4   17.29  7812.6   22.24  7914.6   18.68  8459.5   45.05
#Mann= 19 ,-1 , 0
   188.9     .05       0     903     .12       0  1079.8      .1       0
  1223.8     .05       0  1233.1     .07       0  1305.2    .035       0
  1311.2     .07       0  1367.9      .1       0  1589.2     .05       0
  1822.6      .1       0  1886.6     .16       0  2702.5      .1       0
  2873.1     .05       0  6361.3      .1       0  6429.3     .05       0
  6802.8     .07       0    7532     .12       0  7615.4     .07       0
  7812.6     .05       0
#XS Ineff= 2 , 0
       0                 5056.82       0    20.9
Permanent Ineff=
       F       T
Bank Sta=1173.5,5044.3
XS Rating Curve= 0 ,0
Exp/Cntr=0.3,0.1

Type RM Length L Ch R = 1 ,1732    ,571,571,571
BEGIN DESCRIPTION:
CAYAMON CREEK 3.0
END DESCRIPTION:
XS GIS Cut Line= 3
       2373987.7     13154446.87      2377587.72     13152446.85
      2378287.73     13149546.82
#Sta/Elev= 30
   858.3   21.11  1362.1   20.38  1518.9   20.54  1976.4   20.32  3733.1   16.74
  4903.4   14.65  4941.1   24.44  4973.7   11.75  5004.4    9.28  5007.2    8.78
  5010.4    9.28  5036.8   11.76    5042    16.6  5304.1   15.05  5418.3   15.18
  5979.4   15.87  6046.4    16.7  6169.4   19.38  6258.3   21.77  6427.1      26
  6674.3   23.33  6832.6   22.09  6935.7   21.72  7078.3   18.91  7179.3   18.19
  7208.5   18.21  7280.2   18.27  7482.2   21.37  7583.2   24.64  7959.9   44.73
#Mann= 20 ,-1 , 0
   858.3     .16       0  1362.1      .1       0  1518.9     .05       0
  1976.4     .05       0  5004.4    .035       0  5010.4     .05       0
  5304.1      .1       0  5418.3     .05       0  5979.4     .12       0
  6169.4      .1       0  6258.3     .05       0  6674.3      .1       0
  6832.6     .16       0  6935.7      .1       0  7078.3     .05       0
  7179.3     .07       0  7208.5     .05       0  7280.2     .07       0
  7482.2      .1       0  7583.2     .05       0
Bank Sta=3733.1,6046.4
XS Rating Curve= 0 ,0
Exp/Cntr=0.3,0.1

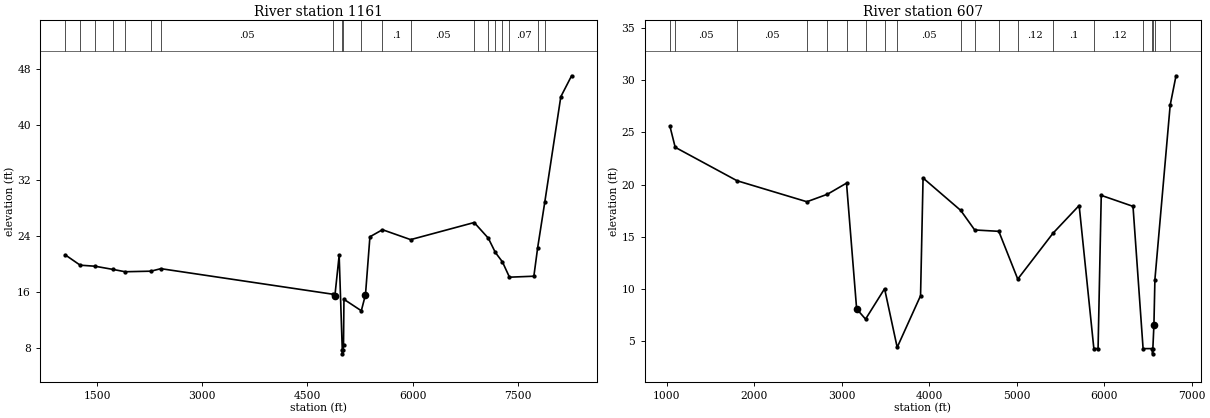
Type RM Length L Ch R = 1 ,1161    ,554,554,554
BEGIN DESCRIPTION:
CAYAMON CREEK 2.0
END DESCRIPTION:
XS GIS Cut Line= 3
      2374287.68     13154446.87      2377887.72     13152846.85
      2378587.73     13149646.81
#Sta/Elev= 30
  1049.3   21.31  1259.8   19.85    1471    19.7  1728.6   19.24  1900.1   18.91
  2268.3   18.99  2409.9   19.35  4867.1   15.68  4890.4   15.46  4951.3   21.24
  4996.1    7.65  4998.9    7.15  5002.1    7.65  5013.4    8.42  5019.6   14.96
  5267.3   13.32  5326.7   15.63  5389.9   23.92    5569   24.93  5970.2   23.51
  6876.2   25.96  7077.3   23.72  7177.9   21.67  7278.4   20.33    7379   18.13
  7726.8   18.27  7781.2   22.37  7881.8   28.84    8111   43.98  8264.6   46.98
#Mann= 20 ,-1 , 0
  1049.3     .12       0  1259.8      .1       0    1471     .05       0
  1728.6      .1       0  1900.1     .05       0  2268.3      .1       0
  2409.9     .05       0  4867.1      .1       0  4996.1     .07       0
  5002.1      .1       0  5267.3     .05       0    5569      .1       0
  5970.2     .05       0  6876.2      .1       0  7077.3      .1       0
  7177.9     .16       0  7278.4     .05       0    7379     .07       0
  7781.2      .1       0  7881.8     .05       0
Bank Sta=4890.4,5326.7
XS Rating Curve= 0 ,0
Exp/Cntr=0.3,0.1

Type RM Length L Ch R = 1 ,607     ,0,0,0
BEGIN DESCRIPTION:
CAYAMON CREEK 1.0
END DESCRIPTION:
XS GIS Cut Line= 3
      2374687.76     13154796.84      2378287.72     13153196.85
      2379837.73     13152196.85
#Sta/Elev= 30
  1037.2   25.62  1098.4   23.57  1805.1   20.37  2603.3   18.36  2838.6   19.08
  3056.2   20.14  3171.8    8.11  3273.7    7.13  3491.2   10.04  3635.2    4.43
  3902.2    9.37  3930.9   20.63  4361.3   17.53  4520.8   15.66  4796.4   15.53
  5012.9   10.96  5415.8   15.35  5714.5      18  5882.4    4.32  5930.7    4.32
    5967   18.97  6329.9   17.92  6445.1    4.31  6550.7    4.31  6553.4    3.81
  6556.7    4.31  6568.9    6.57  6580.2   10.92  6754.7    27.6  6821.3   30.41
#Mann= 20 ,-1 , 0
  1037.2     .12       0  1098.4     .05       0  1805.1     .05       0
  2603.3     .05       0  2838.6      .1       0  3056.2     .07       0
  3273.7     .05       0  3491.2     .12       0  3635.2     .05       0
  4361.3      .1       0  4520.8      .1       0  4796.4     .05       0
  5012.9     .12       0  5415.8      .1       0  5882.4     .12       0
  6445.1     .05       0  6550.7    .035       0  6556.7     .05       0
  6580.2      .1       0  6754.7     .05       0
Bank Sta=3171.8,6568.9
XS Rating Curve= 0 ,0
Exp/Cntr=0.3,0.1

Chan Stop Cuts=-1
Use User Specified Reach Order=0
Composite Channel Slope=5