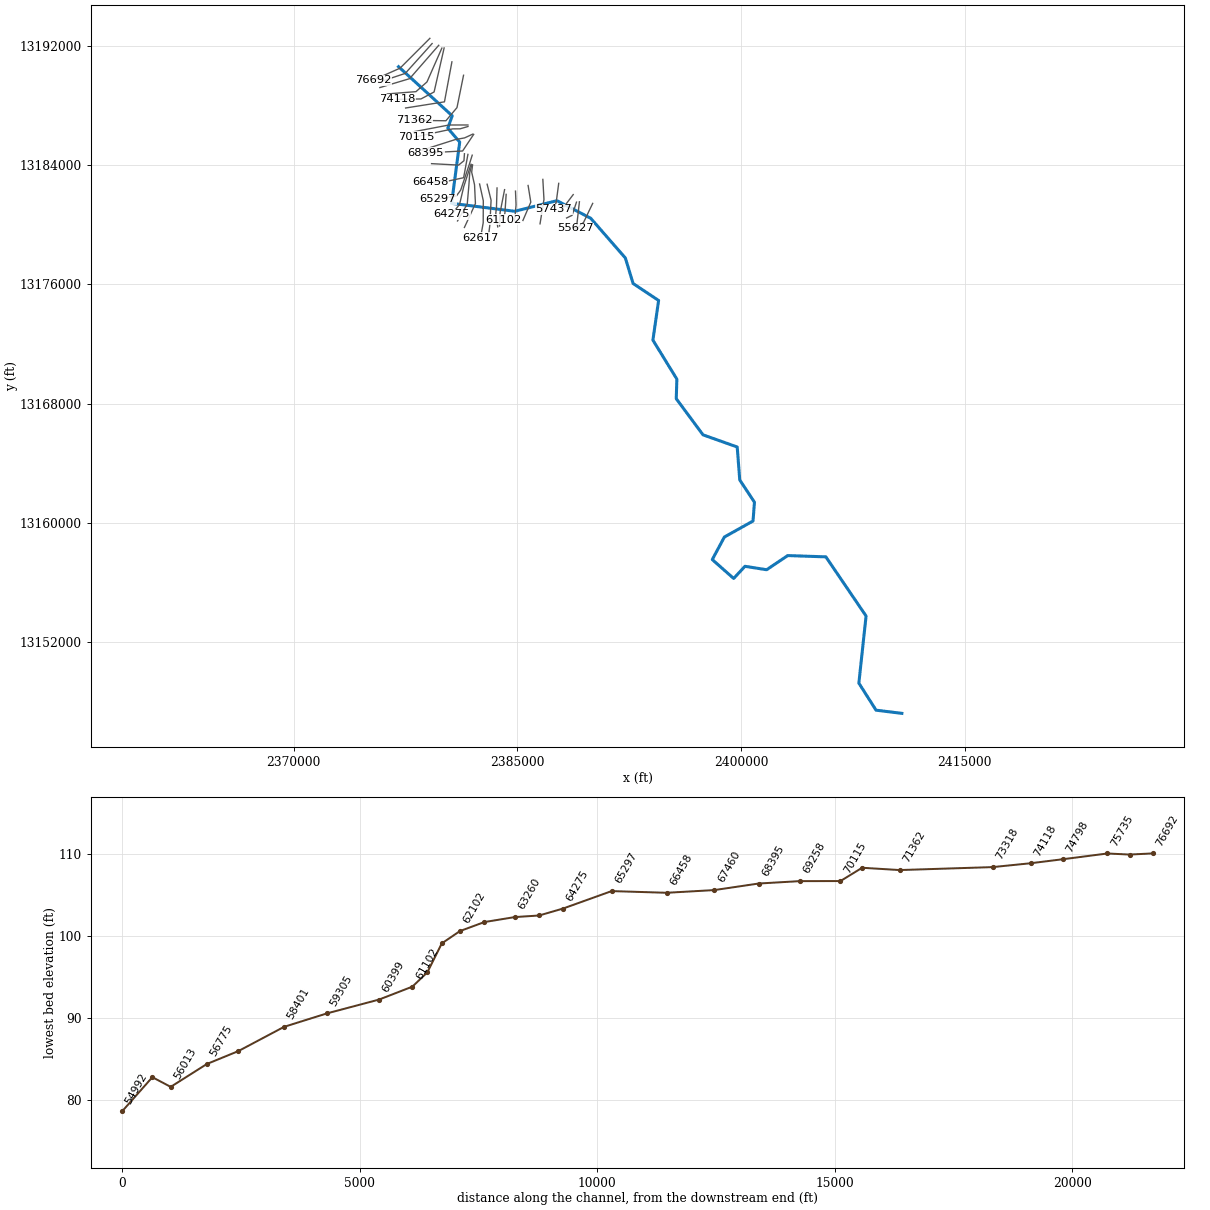
--- HONDO CREEK.prj (project) ---

Proj Title=HONDO CREEK Base Level Engineering
Current Plan=p01
Default Exp/Contr=0.3,0.1
English Units
Geom File=g01
Geom File=g02
Flow File=f01
Plan File=p01
Y Axis Title=Elevation
X Axis Title(PF)=Main Channel Distance
X Axis Title(XS)=Station
BEGIN DESCRIPTION:
HONDO CREEK
END DESCRIPTION:
DSS Export Rating Curves= 0
DSS Export Rating Curve Sorted= 0
DSS Export Volume Flow Curves= 0
DXF OffsetX= 0
DXF OffsetY= 0
DXF ScaleX= 1
DXF ScaleY= 10

--- HONDO CREEK.p01 (plan) ---

Plan Title=Multiple Run
Short Identifier=Multiple
Geom File=g01
Flow File=f01
Subcritical Flow
K Sum by GR= 0
Std Step Tol= 0.01
Critical Tol= 0.01
Num of Std Step Trials= 20
Max Error Tol= 0.3
Flow Tol Ratio= 0.001
Split Flow NTrial= 30
Split Flow Tol= 0.02
Split Flow Ratio= 0.02
Log Output Level= 0
Friction Slope Method= 1
Unsteady Friction Slope Method= 2
Unsteady Bridges Friction Slope Method= 1
Parabolic Critical Depth
Global Vel Dist=  1 , 1 , 1
Global Log Level= 0
CheckData=True
Encroach Param= -1, 0, 0, 0
BEGIN DESCRIPTION:
Multiple Run
END DESCRIPTION:

--- HONDO CREEK.f01 (steady flow) ---

Flow Title=Multiple
Program Version=4.10
Number of Profiles= 7
Profile Names=10-year,25-year,50-year,1pct_min,100-year,1pct_plu,500-year
River Rch & RM=HONDO CREEK,Reach-1         ,76692
     368     473     551     466     631     853     830
River Rch & RM=HONDO CREEK,Reach-1         ,70115
     448     582     683     583     789    1067    1056
River Rch & RM=HONDO CREEK,Reach-1         ,65297
     495     649     768     660     892    1207    1212
River Rch & RM=HONDO CREEK,Reach-1         ,62617
     725     983    1189    1046    1415    1913    2019
River Rch & RM=HONDO CREEK,Reach-1         ,61418
     725     983    1189    1046    1415    1913    2019
River Rch & RM=HONDO CREEK,Reach-1         ,57437
     810    1104    1339    1183    1600    2163    2297
River Rch & RM=HONDO CREEK,Reach-1         ,56775
     877    1202    1465    1299    1757    2376    2546
River Rch & RM=HONDO CREEK,Reach-1         ,55627
    1420    1988    2456    2207    2984    4036    4432
River Rch & RM=HONDO CREEK,Reach-1         ,52908
    1479    2077    2573    2316    3132    4236    4674
River Rch & RM=HONDO CREEK,Reach-1         ,50006
    1651    2343    2925    2654    3590    4855    5442
River Rch & RM=HONDO CREEK,Reach-1         ,47394
    1814    2588    3241    2952    3992    5399    6098
River Rch & RM=HONDO CREEK,Reach-1         ,43955
    2125    3050    3838    3513    4751    6425    7332
River Rch & RM=HONDO CREEK,Reach-1         ,43726
    2125    3050    3838    3513    4751    6425    7332
River Rch & RM=HONDO CREEK,Reach-1         ,40973
    2301    3317    4187    3844    5199    7030    8073
River Rch & RM=HONDO CREEK,Reach-1         ,39568
    2301    3317    4187    3844    5199    7030    8073
River Rch & RM=HONDO CREEK,Reach-1         ,33975
    2263    3252    4095    3750    5072    6859    7839
River Rch & RM=HONDO CREEK,Reach-1         ,28112
    2331    3355    4230    3878    5245    7093    8126
Boundary for River Rch & Prof#=HONDO CREEK,Reach-1         , 1
Up Type= 0
Dn Type= 3
Dn Slope=0.002
Boundary for River Rch & Prof#=HONDO CREEK,Reach-1         , 2
Up Type= 0
Dn Type= 3
Dn Slope=0.002
Boundary for River Rch & Prof#=HONDO CREEK,Reach-1         , 3
Up Type= 0
Dn Type= 3
Dn Slope=0.002
Boundary for River Rch & Prof#=HONDO CREEK,Reach-1         , 4
Up Type= 0
Dn Type= 3
Dn Slope=0.002
Boundary for River Rch & Prof#=HONDO CREEK,Reach-1         , 5
Up Type= 0
Dn Type= 3
Dn Slope=0.002
Boundary for River Rch & Prof#=HONDO CREEK,Reach-1         , 6
Up Type= 0
Dn Type= 3
Dn Slope=0.002
Boundary for River Rch & Prof#=HONDO CREEK,Reach-1         , 7
Up Type= 0
Dn Type= 3
Dn Slope=0.002
DSS Import GetInterval= 0
DSS Import GetPeak= 0
DSS Import FillOption= 0

--- HONDO CREEK.g01 (geometry) ---

Geom Title=Existing Conditions
Program Version=4.10

River Reach=HONDO CREEK     ,Reach-1
Reach XY= 30
      2377037.72     13190596.85      2380634.14     13187305.26
      2380340.34     13186472.55      2381137.62     13185539.69
      2380593.41     13181437.33      2384827.72     13180902.91
      2387656.41     13181615.16      2389918.61     13180435.97
      2392239.68     13177775.44      2392761.55     13176060.86
      2394471.14     13174925.44      2394087.72     13172266.86
      2395693.79     13169655.23      2395653.85     13168340.01
      2397447.17     13165917.79      2399739.58     13165103.29
      2399909.92      13162892.5      2400895.91     13161401.25
      2400799.92     13160140.87       2398880.3     13159069.44
      2398067.72     13157556.86      2399502.59     13156290.19
      2400258.91     13157105.44      2401713.53     13156875.69
      2403123.49     13157824.61      2405682.17     13157739.02
      2408377.54     13153773.54      2407893.56     13149274.97
      2409046.34      13147461.9      2410777.02     13147247.06

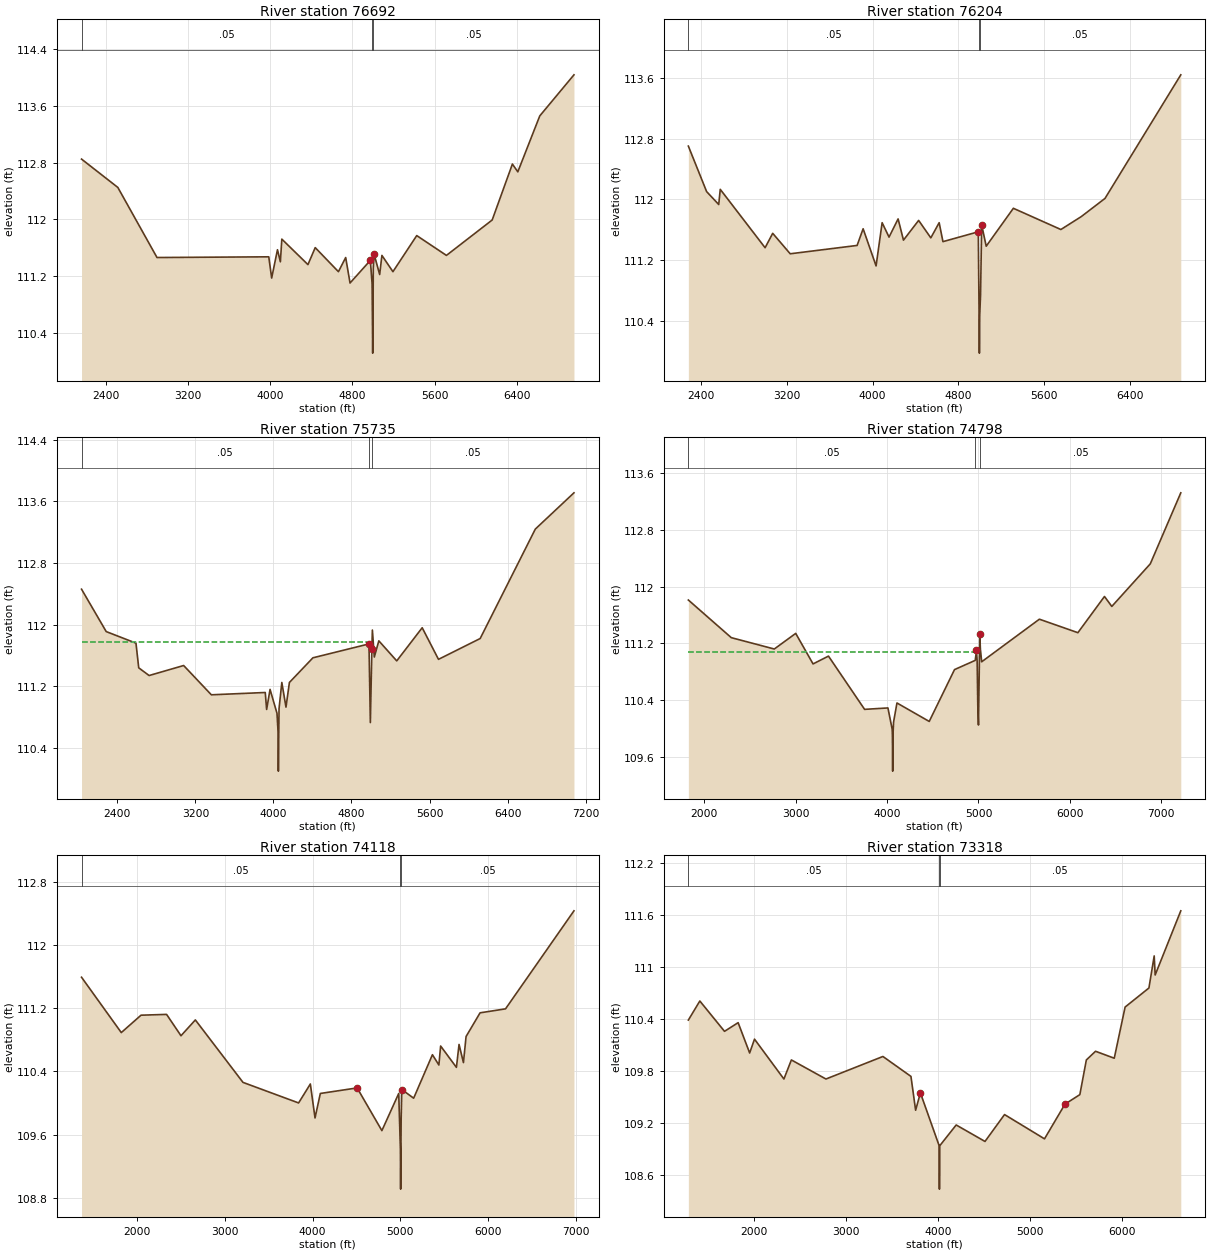
Type RM Length L Ch R = 1 ,76692   ,488,488,488
BEGIN DESCRIPTION:
HONDO CREEK 100.0
END DESCRIPTION:
XS GIS Cut Line= 3
      2379137.73     13192496.87      2377137.72     13190496.85
      2375337.74     13189696.86
#Sta/Elev= 30
  2160.1  112.85  2513.7  112.45  2895.5  111.46  3984.5  111.47  4012.7  111.17
  4069.3  111.57  4097.6   111.4  4111.7  111.72  4366.3  111.36    4437   111.6
  4663.3  111.26    4734  111.46  4776.4   111.1  4974.4  111.42  4991.3  111.09
  4994.4  110.61  4997.2  110.11  5000.4  110.61  5002.9  111.31  5010.4  111.51
  5065.1  111.22    5087  111.49  5194.4  111.26  5426.3  111.77  5715.6  111.49
  6161.5  111.99  6358.5  112.78  6411.2  112.67  6625.2  113.46  6958.3  114.04
#Mann= 3 ,-1 , 0
  2160.1     .05       0  4994.4    .035       0  5000.4     .05       0
Bank Sta=4974.4,5010.4
XS Rating Curve= 0 ,0
Exp/Cntr=0.3,0.1

Type RM Length L Ch R = 1 ,76204   ,469,469,469
BEGIN DESCRIPTION:
HONDO CREEK 99.0
END DESCRIPTION:
XS GIS Cut Line= 3
      2379287.74     13192146.88      2377487.72     13190146.85
      2375687.74     13189546.86
#Sta/Elev= 30
  2283.9   112.7    2454   112.1  2566.8  111.93    2581  112.13  2998.8  111.36
  3069.8  111.55  3232.8  111.28  3856.1  111.39  3912.2  111.61  4032.9  111.12
  4089.3  111.69  4153.6   111.5  4238.1  111.74  4288.1  111.46  4429.4  111.72
    4543  111.49  4620.7  111.69  4655.9  111.44  4985.2  111.57  4992.7  110.47
  4995.5  109.97  4998.7  110.47  5006.3  110.74  5016.8  111.66    5059  111.38
    5312  111.88  5754.7   111.6  5944.4  111.77  6165.8  112.01    6872  113.64
#Mann= 3 ,-1 , 0
  2283.9     .05       0  4992.7    .035       0  4998.7     .05       0
Bank Sta=4985.2,5016.8
XS Rating Curve= 0 ,0
Exp/Cntr=0.3,0.1

Type RM Length L Ch R = 1 ,75735   ,937,937,937
BEGIN DESCRIPTION:
HONDO CREEK 98.0
END DESCRIPTION:
XS GIS Cut Line= 3
      2379731.45     13192029.96      2377780.76     13189794.77
      2375787.72     13189196.85
#Sta/Elev= 30
  2033.3  112.46  2286.4  111.91  2591.2  111.76  2619.6  111.44    2726  111.34
    3080  111.47  3363.9  111.09  3916.4  111.12  3930.6   110.9  3965.7  111.16
  4036.9  110.85  4048.2   110.6  4050.9   110.1  4057.8  110.91  4086.3  111.25
    4129  110.93  4164.1  111.25  4405.2  111.57  4979.6  111.75  4993.8  110.73
  5009.3  111.68  5014.5  111.93  5034.5  111.58  5080.6  111.79  5264.2  111.53
  5525.2  111.96  5692.2  111.55  6119.4  111.82  6684.9  113.24  7080.8  113.71
#Mann= 3 , 0 , 0
  2033.3     .05       0  4979.6    .035       0  5009.3     .05       0
#XS Ineff= 2 , 0
       0 4955.65  111.78               0
Permanent Ineff=
       T       F
Bank Sta=4979.6,5009.3
XS Rating Curve= 0 ,0
Exp/Cntr=0.3,0.1

Type RM Length L Ch R = 1 ,74798   ,680,680,680
BEGIN DESCRIPTION:
HONDO CREEK 97.0
END DESCRIPTION:
XS GIS Cut Line= 4
      2379941.85      13191841.9       2378943.6     13189574.14
      2378205.76      13188923.1       2376285.2     13188771.19
#Sta/Elev= 30
  1825.3  111.81  2294.9  111.28  2765.7  111.12  2999.9  111.34  3189.7  110.91
  3358.5  111.02  3753.7  110.27    4009  110.29  4055.6  109.99  4058.1   109.9
  4060.8   109.4  4064.1   109.9  4070.6  110.09  4107.8  110.36  4460.9   110.1
  4737.6  110.83  4964.4  110.96  4977.9   111.1  4985.5  110.94  4992.2  110.33
  4999.7  110.05    5014  111.33  5020.6  111.12  5034.8  110.94  5666.3  111.54
  6087.6  111.35  6378.5  111.86  6458.7  111.72    6880  112.32  7213.6  113.32
#Mann= 3 ,-1 , 0
  1825.3     .05       0  4964.4    .035       0  5020.6     .05       0
#XS Ineff= 2 , 0
       0 4979.05  111.08               0
Permanent Ineff=
       T       F
Bank Sta=4977.9,5014
XS Rating Curve= 0 ,0
Exp/Cntr=0.3,0.1

Type RM Length L Ch R = 1 ,74118   ,800,800,800
BEGIN DESCRIPTION:
HONDO CREEK 96.0
END DESCRIPTION:
XS GIS Cut Line= 4
      2380093.78     13191852.81      2379421.04      13188901.4
      2378542.13     13188434.82      2376947.05     13188402.27
#Sta/Elev= 30
  1363.6  111.59  1817.1  110.89  2042.4  111.11  2333.8  111.12  2498.2  110.85
    2662  111.05  3205.6  110.26  3839.8     110    3974  110.24  4027.2  109.81
  4087.7  110.12  4507.7  110.19    4790  109.65  4982.2  110.12  5001.2  109.41
    5004  108.91  5007.2  109.41  5009.9   109.8  5017.2  110.17  5152.4  110.06
  5366.6  110.61  5440.2  110.48  5460.2  110.72  5640.3  110.45  5670.3  110.74
  5720.3  110.51  5750.3  110.84  5910.3  111.14  6200.4  111.19  6981.2  112.43
#Mann= 3 ,-1 , 0
  1363.6     .05       0  5001.2    .035       0  5007.2     .05       0
Bank Sta=4507.7,5017.2
XS Rating Curve= 0 ,0
Exp/Cntr=0.3,0.1

Type RM Length L Ch R = 1 ,73318   ,1956,1956,1956
BEGIN DESCRIPTION:
HONDO CREEK 95.0
END DESCRIPTION:
XS GIS Cut Line= 3
      2380614.61     13190919.64      2380115.48     13188239.51
      2377512.02     13187827.29
#Sta/Elev= 30
    1282  110.39  1406.9  110.61  1675.6  110.26  1823.9  110.36  1949.4  110.01
  2002.2  110.17  2322.4  109.71  2403.7  109.93  2780.1  109.71  3400.6  109.97
  3705.8  109.74  3756.6  109.35  3808.7  109.55  4013.1  108.94  4015.8  108.44
  4019.1  108.94  4198.3  109.18  4512.2  108.99  4724.8   109.3  5160.1  109.02
  5382.9  109.42  5544.9  109.53  5615.7  109.93  5715.8  110.03  5919.5  109.95
  6037.7  110.54  6297.2  110.76  6354.5  111.13    6365  110.91  6644.1  111.65
#Mann= 3 ,-1 , 0
    1282     .05       0  4013.1    .035       0  4019.1     .05       0
Bank Sta=3808.7,5382.9
XS Rating Curve= 0 ,0
Exp/Cntr=0.3,0.1

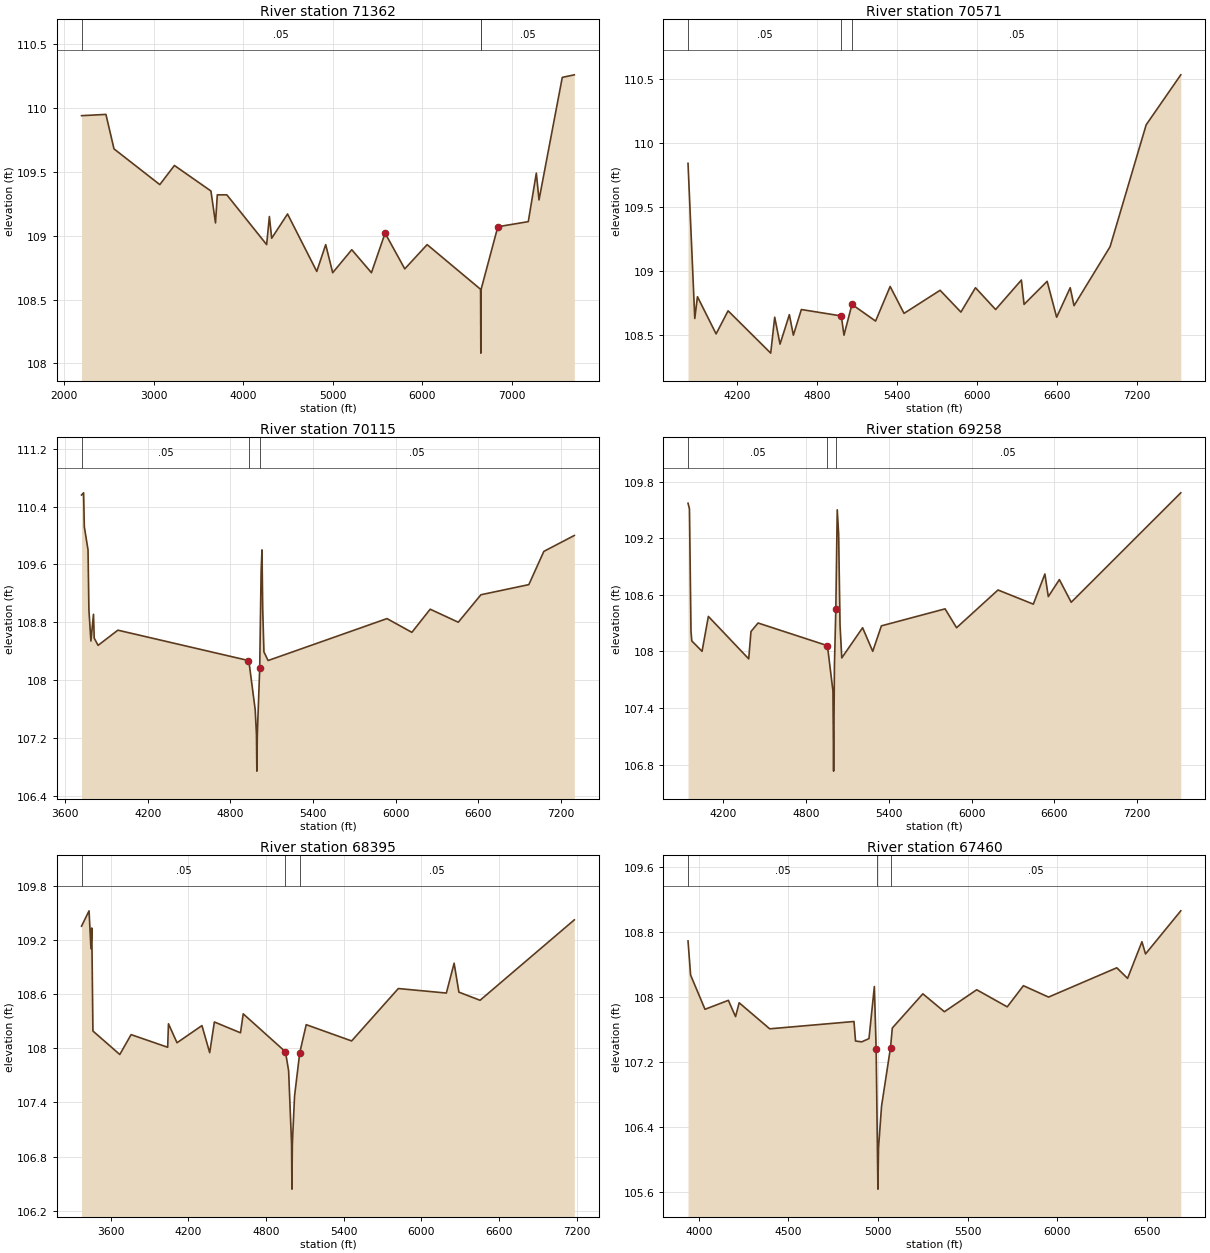
Type RM Length L Ch R = 1 ,71362   ,791,791,791
BEGIN DESCRIPTION:
HONDO CREEK 94.0
END DESCRIPTION:
XS GIS Cut Line= 4
      2381395.52     13190023.86      2380954.91     13187853.43
      2380212.72     13186971.85      2378073.32     13187001.04
#Sta/Elev= 30
  2193.2  109.94  2465.7  109.95  2555.8  109.68  3067.7   109.4    3231  109.55
  3639.1  109.35  3690.1   109.1  3710.3  109.32  3816.7  109.32  4261.6  108.93
  4292.2  109.15    4318  108.98  4495.2  109.17  4821.7  108.72  4921.7  108.93
  4999.8  108.71    5213  108.89  5432.8  108.71  5585.3  109.02  5805.3  108.74
  6055.3  108.93  6652.4  108.58  6655.2  108.08  6658.4  108.58  6845.4  109.07
  7185.5  109.11  7275.5  109.49  7305.5  109.28  7565.5  110.24  7699.9  110.26
#Mann= 3 ,-1 , 0
  2193.2     .05       0  6652.4    .035       0  6658.4     .05       0
Bank Sta=5585.3,6845.4
XS Rating Curve= 0 ,0
Exp/Cntr=0.3,0.1

Type RM Length L Ch R = 1 ,70571   ,456,456,456
BEGIN DESCRIPTION:
HONDO CREEK 93.0
END DESCRIPTION:
XS GIS Cut Line= 3
      2381688.49     13186689.27       2380419.3     13186687.86
       2378032.4     13186232.18
#Sta/Elev= 30
  3830.6  109.84  3881.4  108.63  3901.4   108.8  4041.4  108.51  4131.4  108.69
  4451.4  108.36  4481.4  108.64  4521.4  108.43  4591.4  108.66  4621.4   108.5
  4681.4   108.7  4981.4  108.65  5001.4   108.5  5061.4  108.74  5238.7  108.61
    5348  108.88  5452.2  108.67    5723  108.85  5879.3  108.68  5988.6  108.87
  6139.8   108.7  6333.2  108.93  6353.4  108.74  6526.7  108.92  6597.9  108.64
  6699.8  108.87  6728.4  108.73  6999.2  109.19  7269.9  110.14  7529.8  110.53
#Mann= 3 , 0 , 0
  3830.6     .05       0  4981.4    .035       0  5061.4     .05       0
Bank Sta=4981.4,5061.4
XS Rating Curve= 0 ,0
Exp/Cntr=0.3,0.1

Type RM Length L Ch R = 1 ,70115   ,857,857,857
BEGIN DESCRIPTION:
HONDO CREEK 92.0
END DESCRIPTION:
XS GIS Cut Line= 4
      2381692.85     13186587.27      2381162.66     13186430.91
      2380668.87     13186427.44      2378194.92     13185895.76
#Sta/Elev= 30
  3719.8  110.56  3734.7  110.59  3739.9  110.12  3766.8   109.8  3773.2  108.97
  3787.7  108.54  3806.5  108.91  3811.7  108.58  3839.8  108.48  3983.5  108.69
  4930.9  108.27    4936  108.24  4980.3  107.59  4989.6  107.24  4992.3  106.74
  4995.6  107.24    5013  108.16  5023.3   109.5  5029.6   109.8  5034.8  108.99
  5043.7  108.39  5073.9  108.27  5936.9  108.85  6117.7  108.66  6250.6  108.98
  6454.4   108.8  6618.9  109.18  6966.6  109.32  7075.7  109.78  7296.8     110
#Mann= 3 ,-1 , 0
  3719.8     .05       0    4936    .035       0    5013     .05       0
Bank Sta=4930.9,5013
XS Rating Curve= 0 ,0
Exp/Cntr=0.3,0.1

Type RM Length L Ch R = 1 ,69258   ,863,863,863
BEGIN DESCRIPTION:
HONDO CREEK 91.0
END DESCRIPTION:
XS GIS Cut Line= 4
      2382007.29     13186073.53      2381462.72     13185821.85
      2380841.76     13185711.13      2378608.65      13184999.6
#Sta/Elev= 30
  3942.9  109.57  3953.4  109.51  3964.5  108.21  3970.4  108.11  4044.7     108
  4090.5  108.37  4383.1  107.92  4399.7  108.21  4451.1   108.3  4954.2  108.06
  4994.2  107.58    4999  106.73    5005  107.85  5015.1  108.45  5025.3   109.5
  5035.5  109.24  5045.6  108.28  5058.2  107.93  5209.3  108.25  5282.8     108
  5345.7  108.27  5807.5  108.45    5891  108.25  6191.5  108.65  6447.7   108.5
  6531.7  108.82  6556.3  108.58  6636.7  108.76  6722.6  108.52  7517.3  109.68
#Mann= 3 , 0 , 0
  3942.9     .05       0  4954.2    .035       0  5015.1     .05       0
Bank Sta=4954.2,5015.1
XS Rating Curve= 0 ,0
Exp/Cntr=0.3,0.1

Type RM Length L Ch R = 1 ,68395   ,935,935,935
BEGIN DESCRIPTION:
HONDO CREEK 90.0
END DESCRIPTION:
XS GIS Cut Line= 3
       2382074.6     13186060.18      2381332.42      13184945.6
      2378871.28     13184814.61
#Sta/Elev= 30
    3376  109.35  3433.8  109.52  3448.8   109.1  3454.8  109.33  3463.8  108.19
  3671.2  107.93  3758.4  108.15  4040.8  108.01  4046.9  108.27  4112.9  108.06
  4305.3  108.25  4365.2  107.95  4401.2  108.29  4602.9  108.17  4623.9  108.38
  4950.1  107.96  4974.4  107.75  4997.2  106.94  4999.9  106.44  5003.2  106.94
  5020.2  107.47  5060.3  107.95  5110.3  108.26  5460.8  108.08  5821.3  108.66
  6191.9  108.61  6251.9  108.94  6288.9  108.62  6452.2  108.53  7179.7  109.42
#Mann= 3 , 0 , 0
    3376     .05       0  4950.1    .035       0  5060.3     .05       0
Bank Sta=4950.1,5060.3
XS Rating Curve= 0 ,0
Exp/Cntr=0.3,0.1

Type RM Length L Ch R = 1 ,67460   ,1002,1002,1002
BEGIN DESCRIPTION:
HONDO CREEK 89.0
END DESCRIPTION:
XS GIS Cut Line= 4
      2381455.47     13184761.35      2381422.59     13184292.99
      2381062.72     13183999.21      2379251.41     13184096.79
#Sta/Elev= 30
  3940.2  108.69  3954.7  108.27  4034.9  107.85  4165.2  107.96  4205.3  107.76
  4225.4  107.93  4395.8  107.61  4865.7   107.7  4874.3  107.46  4909.3  107.45
  4949.4  107.49  4979.4  108.13  4989.4  107.36  4996.4  106.14  4999.2  105.64
  5002.4  106.14  5019.5  106.66  5069.5  107.38  5079.6  107.62  5249.8  108.04
    5370  107.82  5550.2  108.09  5720.5  107.88  5810.6  108.14  5950.8     108
  6331.4  108.36  6391.5  108.23  6471.6  108.68  6491.6  108.53  6688.2  109.06
#Mann= 3 ,-1 , 0
  3940.2     .05       0  4996.4    .035       0  5069.5     .05       0
Bank Sta=4989.4,5069.5
XS Rating Curve= 0 ,0
Exp/Cntr=0.3,0.1

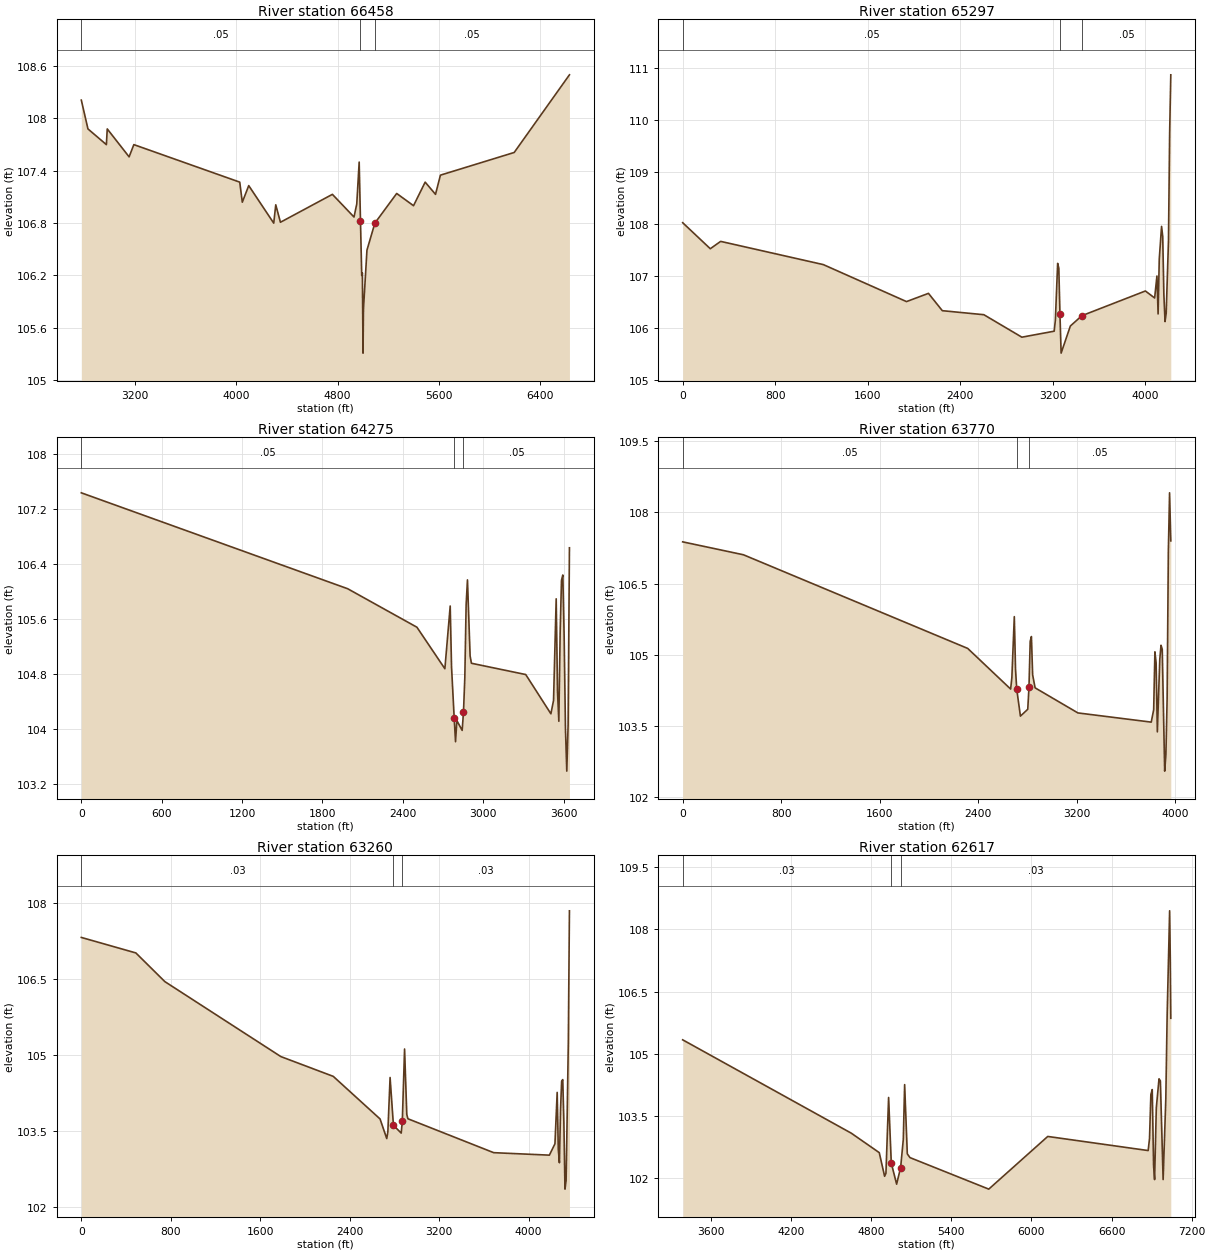
Type RM Length L Ch R = 1 ,66458   ,1161,1161,1161
BEGIN DESCRIPTION:
HONDO CREEK 88.0
END DESCRIPTION:
XS GIS Cut Line= 4
      2381688.33     13184718.34      2381399.96     13183153.95
      2380132.69     13182882.39      2379161.11     13182874.85
#Sta/Elev= 30
    2774  108.21  2826.4  107.88  2972.1   107.7  2978.9  107.88  3151.7  107.56
  3189.2   107.7  4026.2  107.27  4046.6  107.04  4097.4  107.23    4295   106.8
    4311  107.01    4348  106.81  4758.7  107.13  4929.5  106.87  4951.3  107.02
  4970.4   107.5  4980.7  106.82  4990.5   106.2  4995.6  106.23  5000.9  105.31
  5004.1  105.81  5031.8  106.49  5094.4   106.8    5267  107.14    5400     107
    5492  107.27  5573.8  107.13  5612.6  107.35  6195.8  107.61  6632.4   108.5
#Mann= 3 , 0 , 0
    2774     .05       0  4980.7    .035       0  5094.4     .05       0
Bank Sta=4980.7,5094.4
XS Rating Curve= 0 ,0
Exp/Cntr=0.3,0.1

Type RM Length L Ch R = 1 ,65297   ,1022,1022,1022
BEGIN DESCRIPTION:
HONDO CREEK 87.0
END DESCRIPTION:
XS GIS Cut Line= 5
     2381976.411     13184665.23     2381793.803     13184086.34
     2381203.837     13182324.18     2380917.191     13181931.93
     2379672.543     13181720.72
#Sta/Elev= 30
       0108.0245238.6926107.5239328.2024107.66531215.698107.21861934.543106.5072
2124.238106.66552244.045106.33222603.095106.25482931.687105.82263211.037105.9379
3221.016106.14613240.972107.2423 3250.95107.14923260.929 106.2613270.907105.5159
3350.733106.03743450.516 106.2363999.322106.71124079.148106.57674099.105106.9994
4109.083106.27044119.062107.32054139.018107.95314148.996107.76384158.975106.6442
4168.953106.12234178.931106.27834198.888107.68164208.866109.74474218.844110.8689
#Mann= 3 , 0 , 0
       0     .05       03260.929    .035       03450.516     .05       0
Bank Sta=3260.929,3450.516
XS Rating Curve= 0 ,0
Exp/Cntr=0.3,0.1

Type RM Length L Ch R = 1 ,64275   ,505,505,505
BEGIN DESCRIPTION:
HONDO CREEK 86.0
END DESCRIPTION:
XS GIS Cut Line= 5
     2381894.813     13184054.98     2381714.787     13183501.97
     2381407.506     13182550.48     2381128.404     13181366.18
     2380600.371     13180702.37
#Sta/Elev= 30
       0107.44181988.325106.04572505.045105.4856 2713.72104.88132753.468105.7945
2763.405 104.9092783.279104.16142793.216103.81932803.152104.12652842.745103.9843
 2852.63104.25152862.515104.7488  2872.4105.81622882.286106.17482902.056105.0676
2911.941104.96113317.234104.79693505.052104.22563524.823104.42093544.593105.8984
3554.478104.54893564.363104.11643574.249105.42063584.134106.16783594.019 106.246
3603.904105.35893613.789104.00493623.674103.3911 3633.56104.06353643.445106.6418
#Mann= 3 , 0 , 0
       0     .05       02783.279    .035       0 2852.63     .05       0
Bank Sta=2783.279,2852.63
XS Rating Curve= 0 ,0
Exp/Cntr=0.3,0.1

Type RM Length L Ch R = 1 ,63770   ,510,510,510
BEGIN DESCRIPTION:
HONDO CREEK 85.0
END DESCRIPTION:
XS GIS Cut Line= 5
     2381951.237    13184024.601     2381810.273    13183484.606
     2381746.956    13182565.567     2381641.349    13181381.266
     2380992.624    13180257.311
#Sta/Elev= 30
       0  107.38 492.993107.1077 2314.91105.13072663.459104.27322673.417104.5121
2693.276105.80182703.205104.68552713.134104.26662742.922103.70192802.497103.8464
2812.426 104.3132822.355105.28162832.284105.38122842.214104.57352862.072 104.299
3209.594103.76973805.345103.57523825.203103.83673835.133105.05853845.062104.8228
3854.991103.37013874.849104.90213884.779105.19763894.708105.11253914.566102.5411
3924.495 102.8883934.425104.07823944.354107.18573954.283108.41473964.212107.4005
#Mann= 3 , 0 , 0
       0     .05       02713.134    .035       02812.426     .05       0
Bank Sta=2713.134,2812.426
XS Rating Curve= 0 ,0
Exp/Cntr=0.3,0.1

Type RM Length L Ch R = 1 ,63260   ,643,643,643
BEGIN DESCRIPTION:
HONDO CREEK 84.0
END DESCRIPTION:
XS GIS Cut Line= 5
      2381998.98     13184011.58     2381940.482    13183528.009
     2382131.665    13182678.716     2382192.012    13181418.982
     2381452.766    13179819.798
#Sta/Elev= 30
       0107.3143487.7514107.0088747.2034106.44271784.668104.96412253.283 104.574
2672.019103.73372731.802103.34682741.766103.47892761.694104.55152791.585103.6084
2861.332 103.4552871.296103.69942891.224105.11372911.152103.82222921.115103.7375
3688.332103.06884186.524103.01974236.344103.24444256.271104.25764266.235103.1351
4276.199102.86954286.163103.90854296.127 104.4794306.091104.50994316.055103.6772
4326.019102.34964335.982102.51694345.946103.8462 4355.91 105.2444365.874107.8392
#Mann= 3 , 0 , 0
       0     .03       02791.585     .03       02871.296     .03       0
Bank Sta=2791.585,2871.296
XS Rating Curve= 0 ,0
Exp/Cntr=0.3,0.1

Type RM Length L Ch R = 1 ,62617   ,515,515,515
BEGIN DESCRIPTION:
HONDO CREEK 83.0
END DESCRIPTION:
XS GIS Cut Line= 4
      2382471.11     13182731.52      2382720.04     13181607.57
       2382712.5     13180129.07      2382531.78     13179120.03
#Sta/Elev= 30
  3388.5  105.34  4650.4  103.09  4860.4  102.62  4900.4  102.05  4910.4  102.12
  4930.4  103.95  4950.4  102.37  4990.4  101.86  5020.4  102.26  5040.4  102.94
  5050.4  104.26  5070.4  102.59  5090.4   102.5  5680.4  101.74    6122  103.01
  6873.8  102.67    6884  102.96  6894.1  104.02  6904.3  104.14  6914.5   102.3
    6922  101.97  6934.8   103.7  6955.1   104.4  6965.3  104.35  6985.9  101.97
  7005.9  103.91  7016.1  105.95  7034.6  108.45  7039.7  107.25  7043.3  105.86
#Mann= 3 , 0 , 0
  3388.5     .03       0  4950.4     .03       0  5020.4     .03       0
Bank Sta=4950.4,5020.4
XS Rating Curve= 0 ,0
Exp/Cntr=0.3,0.1

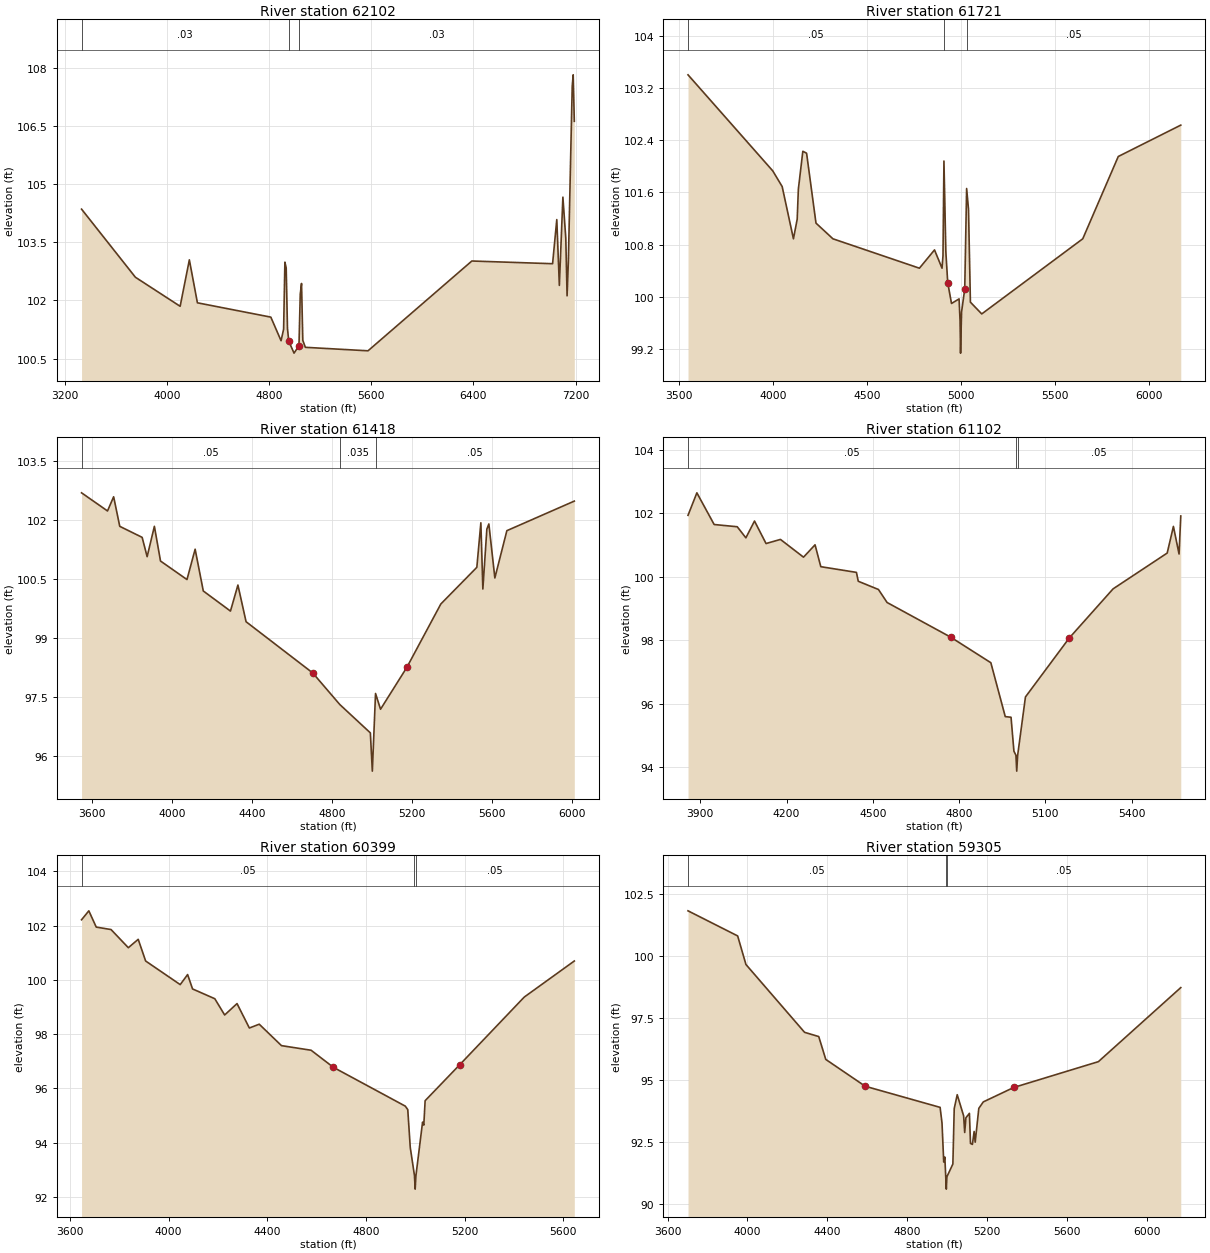
Type RM Length L Ch R = 1 ,62102   ,381,381,381
BEGIN DESCRIPTION:
HONDO CREEK 82.0
END DESCRIPTION:
XS GIS Cut Line= 4
      2382976.52     13182716.43      2383240.53     13181645.28
      2383157.56     13179985.75      2383021.93      13178900.7
#Sta/Elev= 30
  3332.1  104.36  3753.9   102.6  4104.1  101.85  4176.2  103.05  4239.3  101.94
  4814.2  101.57  4894.3  100.96  4914.3  101.26  4924.3  102.99  4934.4  102.84
  4944.4  101.28  4954.4  100.95  4995.8  100.64  5034.5  100.83  5044.5  102.16
  5054.5  102.44  5064.5  100.97  5084.5  100.79  5575.2   100.7  6388.1  103.02
  7020.3  102.95  7053.2  104.09  7073.3  102.39    7101  104.67  7123.7  103.61
  7133.8  102.12  7143.9  103.02  7174.1  107.54  7181.6  107.83  7190.4  106.63
#Mann= 3 , 0 , 0
  3332.1     .03       0  4954.4     .03       0  5034.5     .03       0
Bank Sta=4954.4,5034.5
XS Rating Curve= 0 ,0
Exp/Cntr=0.3,0.1

Type RM Length L Ch R = 1 ,61721   ,303,303,303
BEGIN DESCRIPTION:
Mapping XS aae991b7
END DESCRIPTION:
XS GIS Cut Line= 4
      2383640.33     13182467.48      2383602.61     13181207.77
      2383557.35     13180770.26      2383685.58     13179857.55
#Sta/Elev= 30
  3547.7   103.4  3998.5  101.93  4048.6  101.69  4108.6  100.89  4128.6  101.19
  4134.8  101.65  4158.6  102.23  4178.6   102.2  4228.6  101.13  4318.7  100.89
  4778.9  100.44  4859.2  100.72  4899.2  100.44  4904.3  100.63  4909.4  102.08
  4919.5  100.69  4929.5  100.22  4949.6    99.9  4989.9   99.97  4995.1   99.64
  4997.8   99.14  5003.1   99.77    5020  100.12  5030.1  101.66  5040.1  101.34
  5050.2   99.92  5110.5   99.74    5648  100.89    5837  102.15  6169.5  102.63
#Mann= 3 ,-1 , 0
  3547.7     .05       0  4909.4    .035       0  5030.1     .05       0
Bank Sta=4929.5,5020
XS Rating Curve= 0 ,0
Exp/Cntr=0.3,0.1

Type RM Length L Ch R = 1 ,61418   ,316,316,316
BEGIN DESCRIPTION:
Mapping XS 5d5cc47f
END DESCRIPTION:
XS GIS Cut Line= 3
      2384145.73     13182354.34        2383844.     13180815.52
      2383806.36     13179919.83
#Sta/Elev= 30
  3546.9  102.68  3676.8  102.22  3707.4  102.58    3738  101.83    3850  101.55
  3874.9  101.06  3911.2  101.83  3941.8  100.95  4074.2  100.48    4115  101.25
  4155.8  100.19  4291.7   99.68    4329  100.34  4369.8   99.41  4703.4   98.11
  4838.5   97.31  4991.4   96.59  5001.3   95.62  5017.3   97.59  5042.3   97.19
  5173.7   98.25  5343.9   99.86    5524  100.79  5544.1  101.92  5554.1  100.24
  5574.1  101.76  5584.1  101.89  5614.1  100.52  5674.2  101.72  6011.5  102.47
#Mann= 3 ,-1 , 0
  3546.9     .05       0  4838.5    .035       0  5017.3     .05       0
Bank Sta=4703.4,5173.7
XS Rating Curve= 0 ,0
Exp/Cntr=0.3,0.1

Type RM Length L Ch R = 1 ,61102   ,703,703,703
BEGIN DESCRIPTION:
Mapping XS d76dfdf1
END DESCRIPTION:
XS GIS Cut Line= 3
      2384251.34     13182037.58      2384168.36     13180785.34
      2384055.41     13180341.06
#Sta/Elev= 30
  3857.5  101.94  3888.3  102.65  3948.4  101.65  4028.6  101.58  4058.7  101.23
  4088.7  101.76  4128.8  101.05  4178.9  101.18  4259.1  100.62  4299.2  101.01
  4319.2  100.32  4443.1  100.14  4449.5   99.86  4519.7    99.6  4549.7   99.19
  4770.2    98.1  4910.5   97.29  4960.6   95.59  4980.7   95.57  4990.7    94.5
  4997.7   94.37  5000.5   93.87  5003.7   94.37  5030.8   96.21  5183.2   98.07
  5335.5   99.62  5523.7  100.75  5545.3  101.59  5564.9  100.72  5570.9  101.92
#Mann= 3 ,-1 , 0
  3857.5     .05       0  4997.7    .035       0  5003.7     .05       0
Bank Sta=4770.2,5183.2
XS Rating Curve= 0 ,0
Exp/Cntr=0.3,0.1

Type RM Length L Ch R = 1 ,60399   ,1094,1094,1094
BEGIN DESCRIPTION:
Mapping XS 835bae9d
END DESCRIPTION:
XS GIS Cut Line= 3
      2384877.43     13182256.29      2384915.15     13181336.01
      2384817.09     13180264.85
#Sta/Elev= 30
  3647.5  102.22    3677  102.55    3707  101.95    3767  101.86  3837.1  101.19
  3877.1   101.5  3907.2   100.7  4047.3   99.83  4077.3   100.2  4097.3   99.67
  4187.4   99.31  4227.4   98.71  4277.5   99.13  4327.5   98.23  4367.5   98.37
  4457.6   97.58  4577.7   97.41  4668.1   96.78  4959.3   95.35  4969.4   95.22
  4979.4   93.83  4996.5   92.79  4999.3   92.29  5002.5   92.79  5029.3   94.76
  5034.3   94.65  5039.7   95.55  5180.3   96.88  5441.3   99.37  5644.2   100.7
#Mann= 3 ,-1 , 0
  3647.5     .05       0  4996.5    .035       0  5002.5     .05       0
Bank Sta=4668.1,5180.3
XS Rating Curve= 0 ,0
Exp/Cntr=0.3,0.1

Type RM Length L Ch R = 1 ,59305   ,904,904,904
BEGIN DESCRIPTION:
Mapping XS 20d87482
END DESCRIPTION:
XS GIS Cut Line= 3
      2385722.29     13182633.45      2385903.32     13181517.05
      2385375.31     13180287.52
#Sta/Elev= 30
  3702.2  101.81  3950.9   100.8  3992.5   99.65  4286.3   96.92  4357.2   96.75
  4392.4   95.83  4590.2   94.75  4965.4    93.9  4974.9   93.27  4983.5    91.7
    4989    91.9  4993.6   91.11  4996.4   90.61  4999.6   91.11  5029.3   91.62
  5036.1   93.85  5051.1   94.41  5083.2   93.56  5088.6   92.89  5094.6   93.48
  5112.2   93.66  5117.6   92.45  5127.2   92.41  5135.8   92.93  5141.2    92.5
  5159.3   93.86  5181.7   94.12    5334    94.7  5758.5   95.74  6171.3   98.72
#Mann= 3 ,-1 , 0
  3702.2     .05       0  4993.6    .035       0  4999.6     .05       0
Bank Sta=4590.2,5334
XS Rating Curve= 0 ,0
Exp/Cntr=0.3,0.1

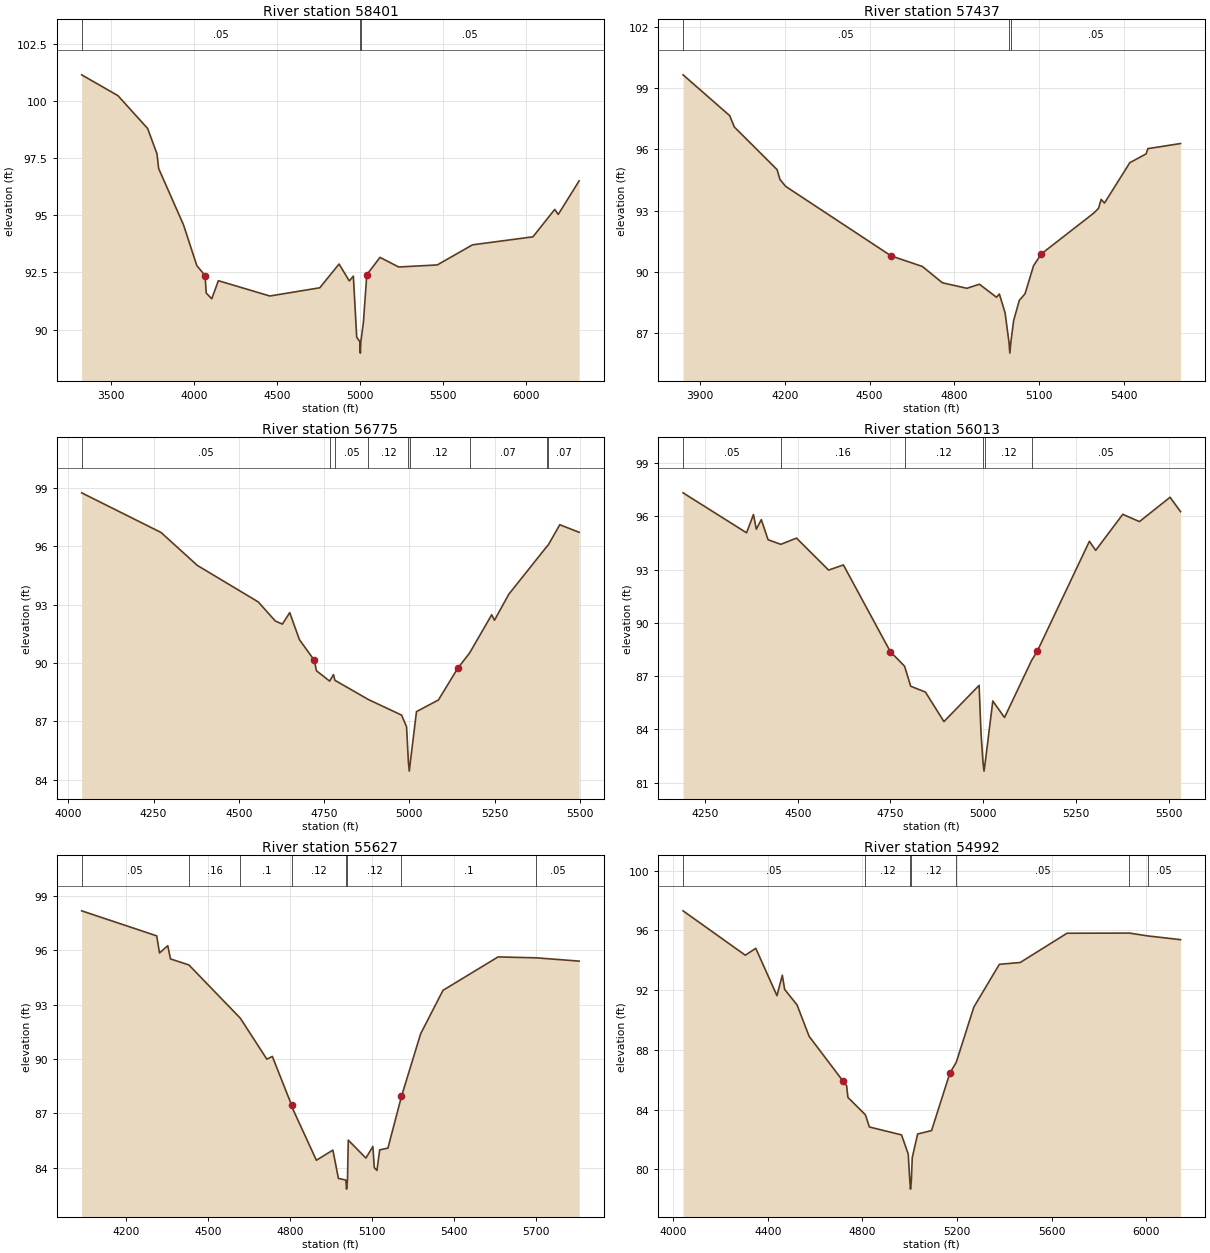
Type RM Length L Ch R = 1 ,58401   ,964,964,964
BEGIN DESCRIPTION:
Mapping XS ce2ad0ac
END DESCRIPTION:
XS GIS Cut Line= 3
      2386710.46     13183040.84      2386785.89     13181698.08
      2386521.93      13180061.5
#Sta/Elev= 30
  3320.6  101.15  3539.6  100.24  3718.9    98.8  3775.3   97.69  3785.3   97.05
  3935.5   94.58  4015.7    92.8  4065.8   92.36  4072.4    91.6  4105.8   91.35
  4145.9   92.14  4456.4   91.47  4757.9   91.83  4874.1   92.87  4935.9   92.13
  4960.5   92.34  4980.7   89.67  4999.7   89.47  5002.5   88.97  5005.7   89.47
  5021.2   90.32  5041.5    92.4  5121.2   93.16    5234   92.74  5466.9   92.83
  5679.6   93.71  6044.3   94.06    6176   95.26    6197   95.04  6323.2   96.51
#Mann= 3 ,-1 , 0
  3320.6     .05       0  4999.7    .035       0  5005.7     .05       0
Bank Sta=4065.8,5041.5
XS Rating Curve= 0 ,0
Exp/Cntr=0.3,0.1

Type RM Length L Ch R = 1 ,57437   ,662,662,662
BEGIN DESCRIPTION:
Mapping XS de694bab
END DESCRIPTION:
XS GIS Cut Line= 3
      2387774.07     13182776.77      2387608.11     13181517.05
      2387457.65     13181050.62
#Sta/Elev= 30
    3840   99.66  4004.9   97.66  4021.5    97.1  4172.8   95.01  4182.9   94.53
    4203   94.19  4576.2   90.78  4687.2   90.26  4757.8   89.46  4844.6   89.19
  4888.9   89.39  4949.4   88.75  4959.5   88.91  4979.7   87.99  4993.8   86.51
  4996.5   86.01  4999.8   86.51  5009.9    87.6  5030.1    88.6  5050.3   88.92
  5080.5    90.3  5108.2   90.88  5292.9   92.87  5310.4   93.11  5319.7   93.55
  5331.5   93.37  5421.1   95.35  5478.6   95.78  5485.2   96.04  5600.7   96.29
#Mann= 3 ,-1 , 0
    3840     .05       0  4993.8     .03       0  4999.8     .05       0
Bank Sta=4576.2,5108.2
XS Rating Curve= 0 ,0
Exp/Cntr=0.3,0.1

Type RM Length L Ch R = 1 ,56775   ,762,762,762
BEGIN DESCRIPTION:
Mapping XS d64dc6ca
END DESCRIPTION:
XS GIS Cut Line= 2
      2388747.17     13182022.46      2387864.97     13180861.28
#Sta/Elev= 30
  4039.4   98.75  4272.2   96.71  4378.3   95.02  4557.1   93.14    4607   92.16
  4627.9      92  4649.3   92.59  4677.8    91.2  4721.4   90.14  4727.7    89.6
  4766.3   89.07  4777.6    89.4  4781.8   89.11  4880.1   88.12  4977.3   87.32
  4991.8   86.72  4997.1   84.94  4999.8   84.44  5003.1   84.94  5020.9    87.5
  5085.3    88.1  5141.5   89.72  5176.8   90.52  5241.4   92.48  5249.6    92.2
  5291.3   93.53    5403   95.99  5406.9   96.06    5441   97.11  5497.7   96.72
#Mann= 9 ,-1 , 0
  4039.4     .05       0  4766.3     .12       0  4781.8     .05       0
  4880.1     .12       0  4997.1     .07       0  5003.1     .12       0
  5176.8     .07       0    5403     .05       0  5406.9     .07       0
Bank Sta=4721.4,5141.5
XS Rating Curve= 0 ,0
Exp/Cntr=0.3,0.1

Type RM Length L Ch R = 1 ,56013   ,386,386,386
BEGIN DESCRIPTION:
Mapping XS c71f6abe
END DESCRIPTION:
XS GIS Cut Line= 3
      2388965.92     13181517.06      2388671.72     13180634.48
      2388302.37     13180453.57
#Sta/Elev= 30
  4190.7   97.32  4361.9   95.07  4380.6    96.1  4388.2   95.27  4401.7   95.81
  4419.9   94.68  4454.3   94.42  4496.6   94.77  4583.2   92.97  4623.1   93.26
  4749.6   88.38    4788   87.56  4804.6   86.43  4844.4    86.1  4894.2   84.44
  4989.1   86.48  4994.3   83.75  4999.6   82.15  5002.3   81.65  5005.6   82.15
    5026    85.6  5057.6   84.67  5130.8   87.89  5145.9    88.4  5286.5   94.59
  5303.5   94.08  5376.5   96.11  5421.5    95.7  5504.1   97.07  5532.3   96.26
#Mann= 6 ,-1 , 0
  4190.7     .05       0  4454.3     .16       0    4788     .12       0
  4999.6     .07       0  5005.6     .12       0  5130.8     .05       0
Bank Sta=4749.6,5145.9
XS Rating Curve= 0 ,0
Exp/Cntr=0.3,0.1

Type RM Length L Ch R = 1 ,55627   ,635,635,635
BEGIN DESCRIPTION:
Mapping XS 289be41e
END DESCRIPTION:
XS GIS Cut Line= 3
      2389162.03     13181539.63      2388988.54     13180000.84
      2388882.95     13179751.95
#Sta/Elev= 30
  4037.8   98.16  4312.3   96.78  4322.4   95.84  4352.6   96.24  4362.6   95.51
  4429.8   95.18  4617.7   92.25  4714.8   89.99    4735   90.14  4805.4   87.46
  4808.1    87.3    4896   84.42  4956.4   84.98  4976.5   83.42  5003.7   83.33
  5006.4   82.83  5009.7   83.33  5012.6   85.53  5077.1   84.54  5102.5   85.18
  5107.6   84.02  5117.4   83.86  5127.4   84.99  5157.6   85.09  5207.2   87.94
  5277.3   91.39  5358.9   93.78  5560.2   95.62  5700.5   95.57  5856.7   95.39
#Mann= 8 ,-1 , 0
  4037.8     .05       0  4429.8     .16       0  4617.7      .1       0
  4808.1     .12       0  5003.7     .07       0  5009.7     .12       0
  5207.2      .1       0  5700.5     .05       0
Bank Sta=4805.4,5207.2
XS Rating Curve= 0 ,0
Exp/Cntr=0.3,0.1

Type RM Length L Ch R = 1 ,54992   ,574,574,574
BEGIN DESCRIPTION:
Mapping XS 5b60bfc9
END DESCRIPTION:
XS GIS Cut Line= 3
      2390052.16     13181434.08      2389441.14     13180159.25
      2388928.19      13179699.1
#Sta/Elev= 30
  4042.3   97.31  4305.4   94.34  4349.7    94.8  4439.2   91.63  4461.8      93
  4471.7   92.05  4524.2   91.01  4575.1   88.91  4716.6   85.95  4733.7    85.6
  4739.2   84.82  4813.2   83.65  4829.9   82.84  4965.8   82.31    4994   81.03
    5001   79.18  5003.7   78.68    5007   79.18  5011.1   80.79  5033.8   82.37
  5092.7    82.6  5169.7   86.43    5197   87.17  5271.5   90.87  5379.2   93.73
  5467.2   93.85  5665.3   95.81  5928.9   95.82  6006.6   95.63  6145.1   95.38
#Mann= 7 ,-1 , 0
  4042.3     .05       0  4813.2     .12       0    5001     .07       0
    5007     .12       0    5197     .05       0  5928.9      .1       0
  6006.6     .05       0
Bank Sta=4716.6,5169.7
XS Rating Curve= 0 ,0
Exp/Cntr=0.3,0.1