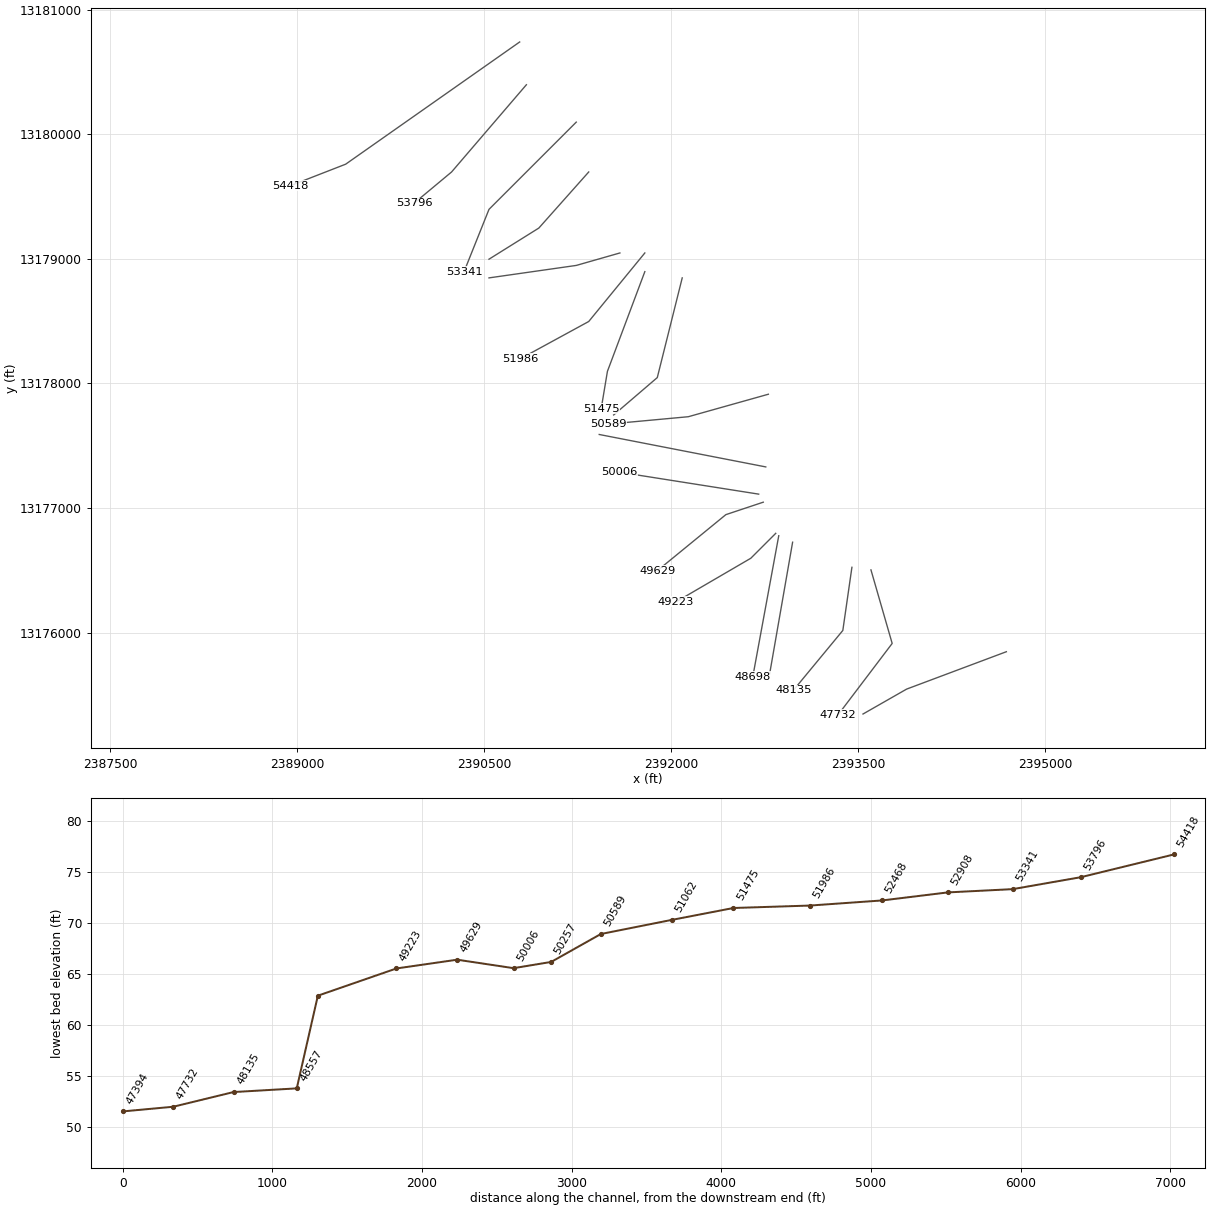
HEC-RAS study HONDO CREEK.prj: HONDO CREEK Base Level Engineering

--- HONDO CREEK.g01 (geometry) --- (continued)

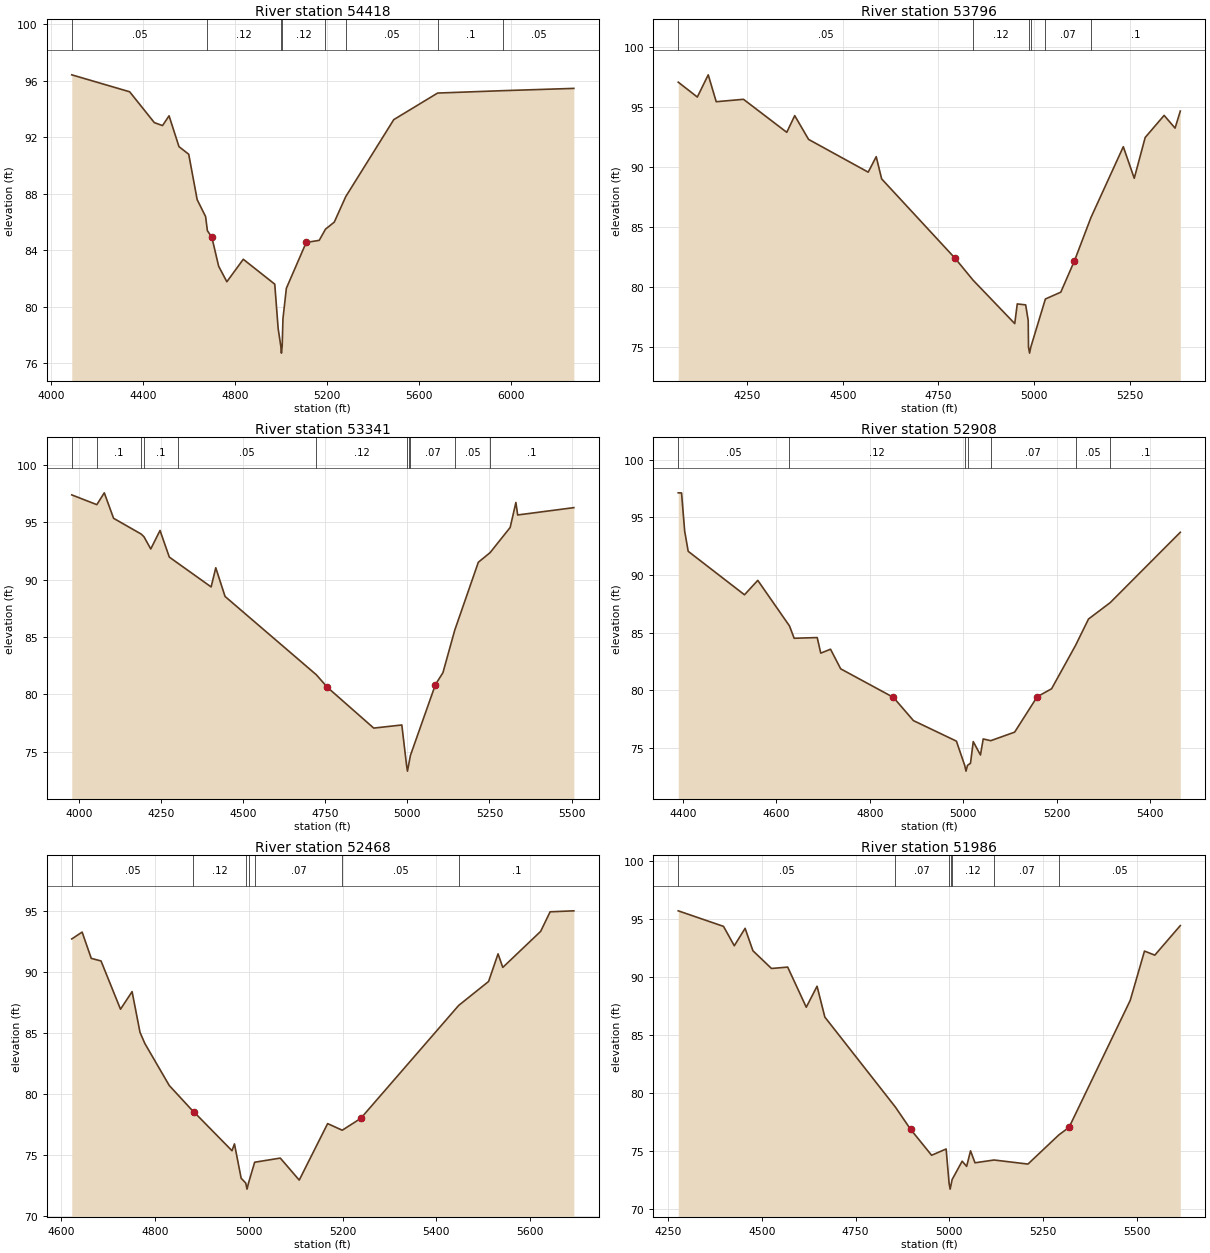
Type RM Length L Ch R = 1 ,54418   ,622,622,622
BEGIN DESCRIPTION:
Mapping XS dbb5e9ea
END DESCRIPTION:
XS GIS Cut Line= 3
      2390783.87      13180740.1      2389388.34     13179759.45
      2388943.29     13179585.96
#Sta/Elev= 30
  4091.2   96.41    4343   95.21  4450.2   93.03  4485.9   92.82  4514.3   93.51
  4557.4   91.33  4599.8   90.79  4636.5   87.58  4673.2   86.38    4681   85.38
  4700.3   84.92  4729.9   82.87  4765.6   81.77  4837.1   83.36  4973.9    81.6
  4988.7   78.46  5000.2   77.22  5002.9   76.72  5006.2   77.22  5009.6   79.16
  5024.4   81.31  5110.7   84.55  5167.3    84.7  5194.5   85.49  5232.7   85.99
  5282.5   87.79  5491.4   93.24  5682.1   95.12  5967.2   95.29  6274.5   95.45
#Mann= 8 ,-1 , 0
  4091.2     .05       0    4681     .12       0  5000.2     .07       0
  5006.2     .12       0  5194.5      .1       0  5282.5     .05       0
  5682.1      .1       0  5967.2     .05       0
Bank Sta=4700.3,5110.7
XS Rating Curve= 0 ,0
Exp/Cntr=0.3,0.1

Type RM Length L Ch R = 1 ,53796   ,455,455,455
BEGIN DESCRIPTION:
HONDO CREEK 69.0
END DESCRIPTION:
XS GIS Cut Line= 3
      2390837.69     13180396.82      2390237.72     13179696.85
      2389937.73     13179446.87
#Sta/Elev= 30
  4070.1   97.07    4120   95.83  4148.5   97.68  4169.4   95.44  4240.7   95.64
  4353.8   92.89  4374.6   94.28  4410.8    92.3  4566.7   89.57  4587.6   90.86
  4601.8   89.01  4793.9   82.39  4840.8   80.57  4949.7   76.95  4956.3   78.59
  4978.3   78.51  4984.9   77.21  4985.7   74.99  4988.5   74.49  4991.7   74.99
  5029.8      79  5070.1   79.57  5105.9   82.19  5148.8   85.78  5233.5   91.69
  5262.1   89.06  5290.7   92.46  5340.2    94.3  5368.8   93.24  5382.5   94.66
#Mann= 6 ,-1 , 0
  4070.1     .05       0  4840.8     .12       0  4985.7     .07       0
  4991.7     .12       0  5029.8     .07       0  5148.8      .1       0
Bank Sta=4793.9,5105.9
XS Rating Curve= 0 ,0
Exp/Cntr=0.3,0.1

Type RM Length L Ch R = 1 ,53341   ,433,433,433
BEGIN DESCRIPTION:
HONDO CREEK 68.0
END DESCRIPTION:
XS GIS Cut Line= 3
      2391237.74     13180096.88      2390537.72     13179396.85
      2390337.72     13178896.86
#Sta/Elev= 30
  3978.6   97.39  4054.9   96.54  4077.6   97.57  4105.9   95.35  4189.8   93.98
  4198.5   93.74  4219.1   92.68  4247.3   94.29  4275.6   91.97  4301.5   91.44
  4402.9   89.37    4417   91.04  4445.3   88.54  4723.4   81.71  4756.5   80.63
  4897.9   77.07  4983.4   77.34  4997.9   73.82  5000.6   73.32  5003.9   73.82
  5009.5   74.68  5085.7   80.86  5108.6    81.9  5144.5    85.6  5216.3   91.52
  5252.2   92.36  5313.2   94.55  5330.7   96.73  5336.1   95.64  5507.1   96.28
#Mann= 11 ,-1 , 0
  3978.6     .05       0  4054.9      .1       0  4189.8     .05       0
  4198.5      .1       0  4301.5     .05       0  4723.4     .12       0
  4997.9     .07       0  5003.9     .12       0  5009.5     .07       0
  5144.5     .05       0  5252.2      .1       0
Bank Sta=4756.5,5085.7
XS Rating Curve= 0 ,0
Exp/Cntr=0.3,0.1

Type RM Length L Ch R = 1 ,52908   ,440,440,440
BEGIN DESCRIPTION:
HONDO CREEK 67.0
END DESCRIPTION:
XS GIS Cut Line= 3
       2391337.7     13179696.83      2390937.72     13179246.85
      2390537.76     13178996.88
#Sta/Elev= 30
  4390.2   97.13  4397.3   97.12    4404    93.8  4411.5   92.06  4531.9   88.29
  4560.3   89.54  4628.1   85.59  4638.1   84.52  4687.4   84.58    4695   83.23
  4715.9   83.57  4737.6   81.87  4850.5   79.39  4893.2   77.38  4985.1    75.6
  5002.8    73.5  5005.6      73  5008.8    73.5  5015.2   73.68  5021.1   75.56
  5036.5    74.4  5042.4   75.79  5058.5   75.64  5109.6   76.38  5157.9   79.45
  5188.6   80.14  5240.1   83.92  5267.6   86.19    5314   87.61  5463.9   93.71
#Mann= 7 ,-1 , 0
  4390.2     .05       0  4628.1     .12       0  5002.8     .07       0
  5008.8     .12       0  5058.5     .07       0  5240.1     .05       0
    5314      .1       0
Bank Sta=4850.5,5157.9
XS Rating Curve= 0 ,0
Exp/Cntr=0.3,0.1

Type RM Length L Ch R = 1 ,52468   ,482,482,482
BEGIN DESCRIPTION:
HONDO CREEK 66.0
END DESCRIPTION:
XS GIS Cut Line= 3
      2391587.76     13179046.87      2391237.72     13178946.85
      2390537.67     13178846.85
#Sta/Elev= 30
  4622.3   92.68  4644.4   93.24  4663.9   91.09  4684.7   90.88  4726.3   86.93
    4751   88.37  4767.9   85.04  4778.3   84.12  4830.3   80.69  4881.5   78.56
  4882.3   78.55  4964.2   75.35  4969.4   75.91  4983.7    73.1  4993.4   72.71
  4996.2   72.21  4999.4   72.71  5012.5   74.41  5067.2   74.75  5107.6   72.95
  5168.2   77.57  5199.4   77.03  5238.9      78  5447.8   87.24  5511.6    89.2
  5531.8   91.46  5541.9   90.35  5622.7    93.3  5642.9    94.9  5693.5   94.98
#Mann= 7 ,-1 , 0
  4622.3     .05       0  4881.5     .12       0  4993.4     .07       0
  4999.4     .12       0  5012.5     .07       0  5199.4     .05       0
  5447.8      .1       0
Bank Sta=4882.3,5238.9
XS Rating Curve= 0 ,0
Exp/Cntr=0.3,0.1

Type RM Length L Ch R = 1 ,51986   ,511,511,511
BEGIN DESCRIPTION:
HONDO CREEK 65.0
END DESCRIPTION:
XS GIS Cut Line= 3
      2391787.75     13179046.89      2391337.72     13178496.85
       2390787.7     13178196.84
#Sta/Elev= 30
  4277.7    95.7  4398.3   94.36    4427   92.69  4455.8   94.19  4476.6   92.26
  4526.1   90.73  4569.2   90.85  4618.7   87.39  4647.4    89.2  4668.2   86.54
  4855.7    78.8  4896.5   76.87  4952.5   74.63  4991.2   75.17  4999.1   72.21
  5001.9   71.71  5005.1   72.21  5007.2   72.54  5033.9   74.12  5045.8   73.67
  5056.2   75.01  5068.1   73.98  5118.9   74.22  5209.1   73.87  5291.6   76.39
  5318.7   77.04  5481.5   87.98  5519.5   92.23    5547   91.88  5614.9   94.43
#Mann= 7 ,-1 , 0
  4277.7     .05       0  4855.7     .07       0  4999.1     .07       0
  5005.1     .07       0  5007.2     .12       0  5118.9     .07       0
  5291.6     .05       0
Bank Sta=4896.5,5318.7
XS Rating Curve= 0 ,0
Exp/Cntr=0.3,0.1

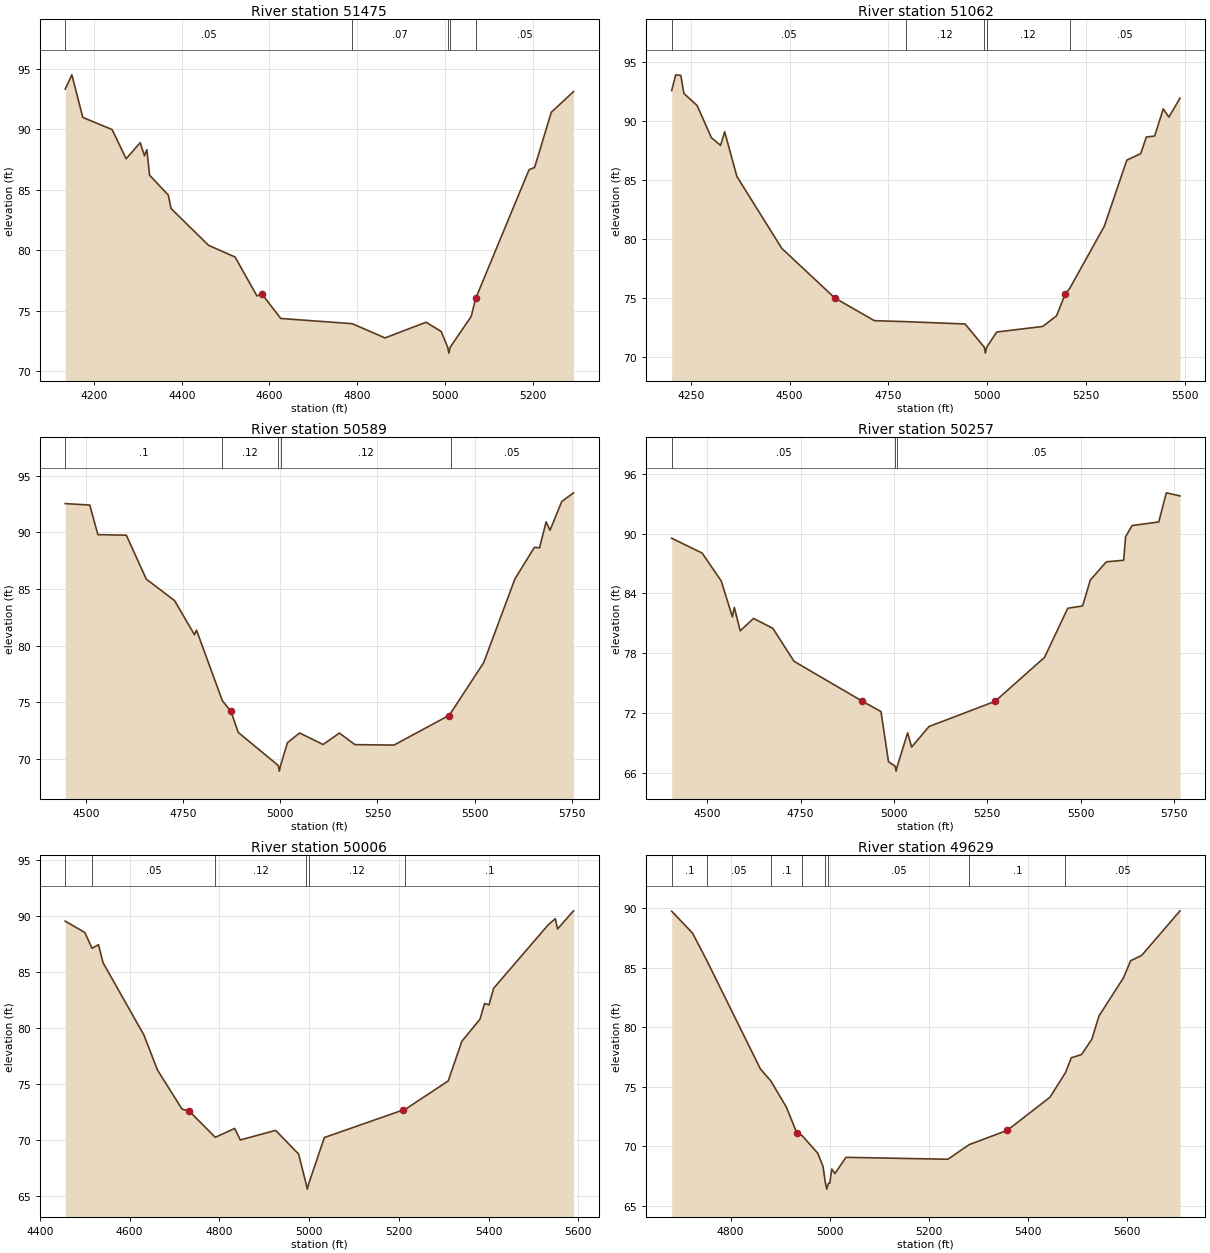
Type RM Length L Ch R = 1 ,51475   ,413,413,413
BEGIN DESCRIPTION:
HONDO CREEK 64.0
END DESCRIPTION:
XS GIS Cut Line= 3
      2391787.74      13178896.9      2391487.72     13178096.85
      2391437.72     13177796.84
#Sta/Elev= 30
  4134.5   93.34  4149.7   94.52  4174.6   90.99  4241.3   89.99  4273.4   87.57
  4305.4    88.9  4315.2   87.82  4320.6   88.32  4326.8   86.21  4369.5   84.56
  4375.7   83.45  4461.2    80.4  4521.7   79.43  4571.5   76.21  4583.1   76.36
  4625.8   74.34  4788.7   73.91  4863.5   72.73  4956.9   74.03  4991.5   73.26
  5006.2   71.97    5009   71.47  5012.2   71.97  5059.9   74.51  5070.1   76.01
  5070.2   76.01  5191.7   86.66  5204.4   86.85  5242.4   91.42  5293.1   93.13
#Mann= 5 ,-1 , 0
  4134.5     .05       0  4788.7     .07       0  5006.2     .07       0
  5012.2     .07       0  5070.2     .05       0
Bank Sta=4583.1,5070.1
XS Rating Curve= 0 ,0
Exp/Cntr=0.3,0.1

Type RM Length L Ch R = 1 ,51062   ,473,473,473
BEGIN DESCRIPTION:
HONDO CREEK 63.0
END DESCRIPTION:
XS GIS Cut Line= 3
      2392087.72     13178846.84      2391887.72     13178046.85
      2391537.71     13177746.85
#Sta/Elev= 30
    4202   92.56  4212.3   93.89  4225.2   93.84  4232.9   92.31  4266.4   91.29
  4302.5   88.56  4325.7   87.91    4336   89.07  4366.9   85.28  4480.3   79.19
  4614.3   74.98  4714.8   73.05  4793.9   72.97  4944.1   72.77  4992.7    70.8
  4995.4    70.3  4998.7    70.8    5024   72.09  5140.2   72.56  5175.3   73.46
  5197.3    75.3  5208.4   75.77  5296.1   81.05  5353.1   86.66  5388.3   87.21
  5402.5   88.62  5423.4    88.7  5445.3      91  5459.6   90.31  5487.6   91.92
#Mann= 5 ,-1 , 0
    4202     .05       0  4793.9     .12       0  4992.7     .07       0
  4998.7     .12       0  5208.4     .05       0
Bank Sta=4614.3,5197.3
XS Rating Curve= 0 ,0
Exp/Cntr=0.3,0.1

Type RM Length L Ch R = 1 ,50589   ,332,332,332
BEGIN DESCRIPTION:
Mapping XS 233a5ac2
END DESCRIPTION:
XS GIS Cut Line= 3
       2392778.7     13177913.21      2392136.31     13177732.65
      2391497.41     13177673.62
#Sta/Elev= 30
    4446   92.54  4509.3   92.41  4530.1    89.8  4603.4   89.75  4654.8   85.87
  4727.5   83.98  4778.9   80.96  4784.1   81.37  4850.6   75.14  4872.9   74.19
  4891.5   72.34  4994.6   69.42  4997.3   68.92  5000.6   69.42  5018.3   71.43
  5049.5   72.29    5110   71.27    5152   72.28  5192.2   71.26  5292.6   71.22
  5433.2   73.82  5438.3   74.02  5523.6    78.5    5604   85.89  5654.2   88.68
  5667.3   88.63  5684.3   90.93  5694.3   90.18  5724.5   92.72  5754.9   93.49
#Mann= 5 ,-1 , 0
    4446      .1       0  4850.6     .12       0  4994.6     .07       0
  5000.6     .12       0  5438.3     .05       0
Bank Sta=4872.9,5433.2
XS Rating Curve= 0 ,0
Exp/Cntr=0.3,0.1

Type RM Length L Ch R = 1 ,50257   ,251,251,251
BEGIN DESCRIPTION:
HONDO CREEK 62.0
END DESCRIPTION:
XS GIS Cut Line= 2
      2392757.83     13177329.88      2391421.84     13177590.13
#Sta/Elev= 30
  4404.9   89.53  4486.5   88.04  4537.5   85.25  4567.5   81.65  4572.6    82.6
  4588.4   80.25  4624.2   81.49  4675.9   80.49  4732.6   77.19  4914.4   73.21
  4965.4   72.15  4985.6   67.11  5003.1   66.68  5005.9   66.18  5009.1   66.68
  5036.7   70.02  5047.4   68.59  5093.9   70.65    5271   73.18  5403.4   77.59
  5465.4   82.51  5505.3   82.74  5525.7   85.33  5568.7   87.16  5615.2   87.32
  5620.3   89.68  5637.8    90.8  5709.1   91.16  5729.4   94.08    5766   93.77
#Mann= 3 ,-1 , 0
  4404.9     .05       0  5003.1     .04       0  5009.1     .05       0
Bank Sta=4914.4,5271
XS Rating Curve= 0 ,0
Exp/Cntr=0.3,0.1

Type RM Length L Ch R = 1 ,50006   ,377,377,377
BEGIN DESCRIPTION:
HONDO CREEK 61.0
END DESCRIPTION:
XS GIS Cut Line= 2
      2392701.01     13177111.45      2391581.75     13177288.05
#Sta/Elev= 30
  4456.3   89.51  4500.1   88.49  4516.2   87.08  4530.5   87.41  4540.6    85.8
  4631.7   79.34  4662.1    76.2  4716.7   72.72    4733   72.53  4790.9    70.2
  4834.2   70.99  4846.6   69.96  4925.3   70.82  4976.6    68.7  4993.2   66.07
  4995.9   65.57  4999.2   66.07    5034   70.18  5208.8   72.63  5214.7   72.71
    5310   75.23  5340.4   78.77  5380.9   80.75    5391   82.15  5401.1   82.03
  5411.3   83.51  5532.7   89.17  5548.8   89.73  5553.8   88.81  5589.4   90.43
#Mann= 6 ,-1 , 0
  4456.3      .1       0  4516.2     .05       0  4790.9     .12       0
  4993.2     .07       0  4999.2     .12       0  5214.7      .1       0
Bank Sta=4733,5208.8
XS Rating Curve= 0 ,0
Exp/Cntr=0.3,0.1

Type RM Length L Ch R = 1 ,49629   ,406,406,406
BEGIN DESCRIPTION:
HONDO CREEK 60.0
END DESCRIPTION:
XS GIS Cut Line= 3
       2392737.7     13177046.85      2392437.72     13176946.85
      2391887.76     13176496.88
#Sta/Elev= 30
  4680.9   89.75    4723   87.91  4752.3   85.57  4860.1    76.5  4881.2   75.49
  4912.8   73.27  4933.9    71.1    4944   70.91    4976   69.42  4986.6   68.31
  4991.5    66.9  4994.2    66.4  4997.5    66.9  5000.3    66.9  5004.3   68.09
  5010.7   67.71    5033   69.07    5239   68.91  5281.9   70.14  5358.9   71.34
    5445   74.12  5476.2   76.17  5488.1   77.43  5508.9   77.71  5529.7      79
  5544.1   80.95  5593.6   84.16    5608   85.59  5630.2   86.03  5707.7   89.78
#Mann= 8 ,-1 , 0
  4680.9      .1       0  4752.3     .05       0  4881.2      .1       0
    4944     .05       0  4991.5     .03       0  4997.5     .05       0
  5281.9      .1       0  5476.2     .05       0
Bank Sta=4933.9,5358.9
XS Rating Curve= 0 ,0
Exp/Cntr=0.3,0.1

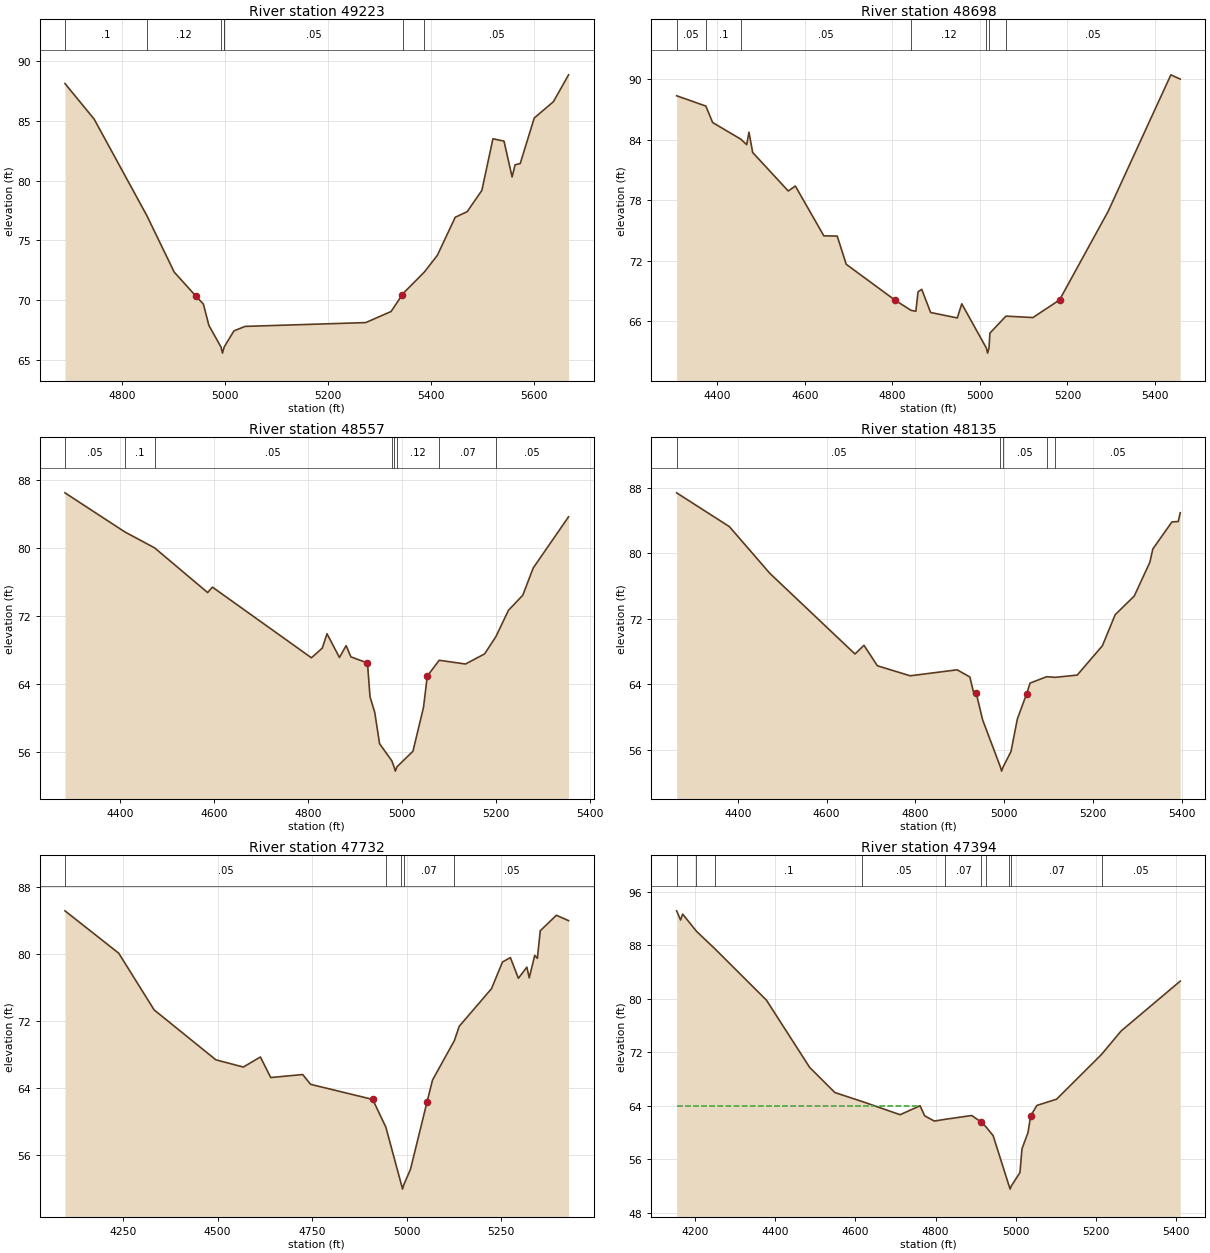
Type RM Length L Ch R = 1 ,49223   ,525,525,525
BEGIN DESCRIPTION:
HONDO CREEK 59.0
END DESCRIPTION:
XS GIS Cut Line= 3
      2392837.72     13176796.85      2392637.72     13176596.85
      2392037.69     13176246.84
#Sta/Elev= 30
  4689.2   88.14  4745.8   85.16    4848   77.08  4901.3   72.33  4943.8    70.3
  4957.9   69.65  4968.5   67.87  4992.2   66.04  4994.9   65.54  4998.2   66.04
  4998.6   66.08  5017.1    67.4  5038.6   67.78    5273    68.1  5322.2   69.03
  5343.7   70.42  5346.2   70.57  5386.8   72.34    5412   73.74  5446.7   76.93
  5469.9    77.4  5498.4   79.18  5519.9   83.51  5541.4   83.31  5557.1   80.31
  5562.9   81.33  5572.8   81.43  5600.1   85.25  5637.3   86.62  5666.7   88.87
#Mann= 7 ,-1 , 0
  4689.2      .1       0    4848     .12       0  4992.2     .03       0
  4998.2     .12       0  4998.6     .05       0  5346.2      .1       0
  5386.8     .05       0
Bank Sta=4943.8,5343.7
XS Rating Curve= 0 ,0
Exp/Cntr=0.3,0.1

Type RM Length L Ch R = 1 ,48698   ,141,141,141
BEGIN DESCRIPTION:
Mapping XS e112fc92
END DESCRIPTION:
XS GIS Cut Line= 2
      2392862.01     13176777.78      2392653.67      13175645.8
#Sta/Elev= 30
  4306.7   88.33  4373.5   87.31    4389   85.68  4453.2   84.04  4466.9   83.49
    4472   84.73  4480.5   82.72  4561.8   78.91    4578    79.4  4643.2   74.47
  4673.7   74.45  4694.3   71.66  4805.9   68.11  4842.1   67.11  4853.4   67.01
  4858.5   68.94  4866.9   69.18  4887.2   66.89  4948.2   66.35  4958.4   67.75
  5014.6   63.37  5017.4   62.87  5020.6   63.37  5022.7   64.85  5059.4   66.53
  5121.1   66.39  5181.8   68.13    5293    76.9  5436.3    90.4  5457.7   89.98
#Mann= 7 ,-1 , 0
  4306.7     .05       0  4373.5      .1       0  4453.2     .05       0
  4842.1     .12       0  5014.6     .07       0  5020.6     .12       0
  5059.4     .05       0
Bank Sta=4805.9,5181.8
XS Rating Curve= 0 ,0
Exp/Cntr=0.3,0.1

Type RM Length L Ch R = 1 ,48557   ,422,422,422
BEGIN DESCRIPTION:
HONDO CREEK 58.0
END DESCRIPTION:
XS GIS Cut Line= 2
      2392973.11     13176725.68      2392789.24     13175670.99
#Sta/Elev= 30
    4283   86.54  4410.2   81.94  4473.6   80.06  4586.3    74.8  4596.5   75.44
  4806.9   67.12    4830   68.26  4840.1   69.95  4866.5   67.16  4880.7   68.55
  4890.9   67.23  4926.1   66.51  4931.5   62.53  4941.6   60.69  4951.8   57.01
  4977.8      55  4982.6   54.28  4985.4   53.78  4988.6   54.28  5022.8   56.12
  5045.2   61.29  5053.3   64.98  5078.6   66.83  5134.5   66.39  5175.1   67.58
    5199    69.6  5225.8   72.71  5256.3   74.49  5278.4   77.69  5353.6   83.72
#Mann= 8 ,-1 , 0
    4283     .05       0  4410.2      .1       0  4473.6     .05       0
  4977.8     .12       0  4982.6     .07       0  4988.6     .12       0
  5078.6     .07       0    5199     .05       0
Bank Sta=4926.1,5053.3
XS Rating Curve= 0 ,0
Exp/Cntr=0.3,0.1

Type RM Length L Ch R = 1 ,48135   ,403,403,403
BEGIN DESCRIPTION:
HONDO CREEK 57.0
END DESCRIPTION:
XS GIS Cut Line= 3
      2393448.81      13176524.3       2393375.9     13176017.37
      2392980.04     13175538.18
#Sta/Elev= 30
  4262.4   87.37  4381.1   83.25    4472   77.56  4663.9   67.71  4684.1   68.77
  4714.4   66.27  4788.2   65.05  4893.9   65.78  4922.6    64.9  4930.5   63.09
  4936.9   62.92  4951.3   59.67  4991.3   53.92    4994   53.42  4997.3   53.92
  5015.1   55.81  5029.4   59.78  5050.3   62.85  5058.1   64.16  5095.5   64.94
  5114.6   64.86  5164.3   65.14  5220.9   68.72  5249.6    72.5  5292.6   74.78
  5327.8   78.91  5334.3   80.51  5377.3   83.82  5391.6   83.87  5396.1   84.94
#Mann= 5 ,-1 , 0
  4262.4     .05       0  4991.3    .035       0  4997.3     .05       0
  5095.5     .07       0  5114.6     .05       0
Bank Sta=4936.9,5050.3
XS Rating Curve= 0 ,0
Exp/Cntr=0.3,0.1

Type RM Length L Ch R = 1 ,47732   ,338,338,338
BEGIN DESCRIPTION:
HONDO CREEK 56.0
END DESCRIPTION:
XS GIS Cut Line= 3
      2393601.58     13176503.51      2393771.73     13175913.21
       2393338.3     13175341.08
#Sta/Elev= 30
  4096.4   85.15  4238.6    80.1  4332.3   73.34  4495.6   67.39  4568.2   66.53
  4613.3   67.73  4640.7   65.28  4725.3   65.64  4746.1   64.47  4910.5   62.67
  4945.3   59.35  4986.5   52.48  4989.3   51.98  4992.5   52.48  5010.4   54.36
    5054   62.35  5068.6   64.98  5126.5   69.69  5139.3   71.39  5224.6   75.87
  5253.7   79.05  5274.6   79.58  5295.8   77.11  5318.2   78.44  5324.5   77.16
    5339   79.84    5346   79.49  5353.6   82.77  5396.2   84.62  5428.5   83.98
#Mann= 5 ,-1 , 0
  4096.4     .05       0  4945.3     .07       0  4986.5     .07       0
  4992.5     .07       0  5126.5     .05       0
Bank Sta=4910.5,5054
XS Rating Curve= 0 ,0
Exp/Cntr=0.3,0.1

Type RM Length L Ch R = 1 ,47394   ,528,528,528
BEGIN DESCRIPTION:
HONDO CREEK 55.0
END DESCRIPTION:
XS GIS Cut Line= 3
      2394687.71     13175846.85      2393887.72     13175546.85
      2393537.72     13175346.86
#Sta/Elev= 30
  4153.4   93.14  4163.2   91.77  4168.5   92.65  4202.6    90.1  4249.7   87.42
  4377.7   79.78  4485.4   69.74  4548.6   65.96  4617.3   64.61  4711.4   62.65
  4761.3   63.99  4772.8   62.48  4796.9    61.7  4824.7   61.97  4890.3   62.53
  4914.2   61.54  4925.7   60.85  4943.7   59.52  4983.4   52.02  4986.2   51.52
  4989.4   52.02  5010.7      54  5015.7   57.55  5030.8   59.98  5037.3   62.48
  5053.1   64.04  5102.1   64.97  5214.3   71.66  5263.3   75.17  5410.9   82.63
#Mann= 10 ,-1 , 0
  4153.4      .1       0  4202.6     .05       0  4249.7      .1       0
  4617.3     .05       0  4824.7     .07       0  4914.2     .12       0
  4925.7     .07       0  4983.4     .07       0  4989.4     .07       0
  5214.3     .05       0
#XS Ineff= 2 , 0
         4752.73   63.95
Permanent Ineff=
       F       F
Bank Sta=4914.2,5037.3
XS Rating Curve= 0 ,0
Exp/Cntr=0.3,0.1