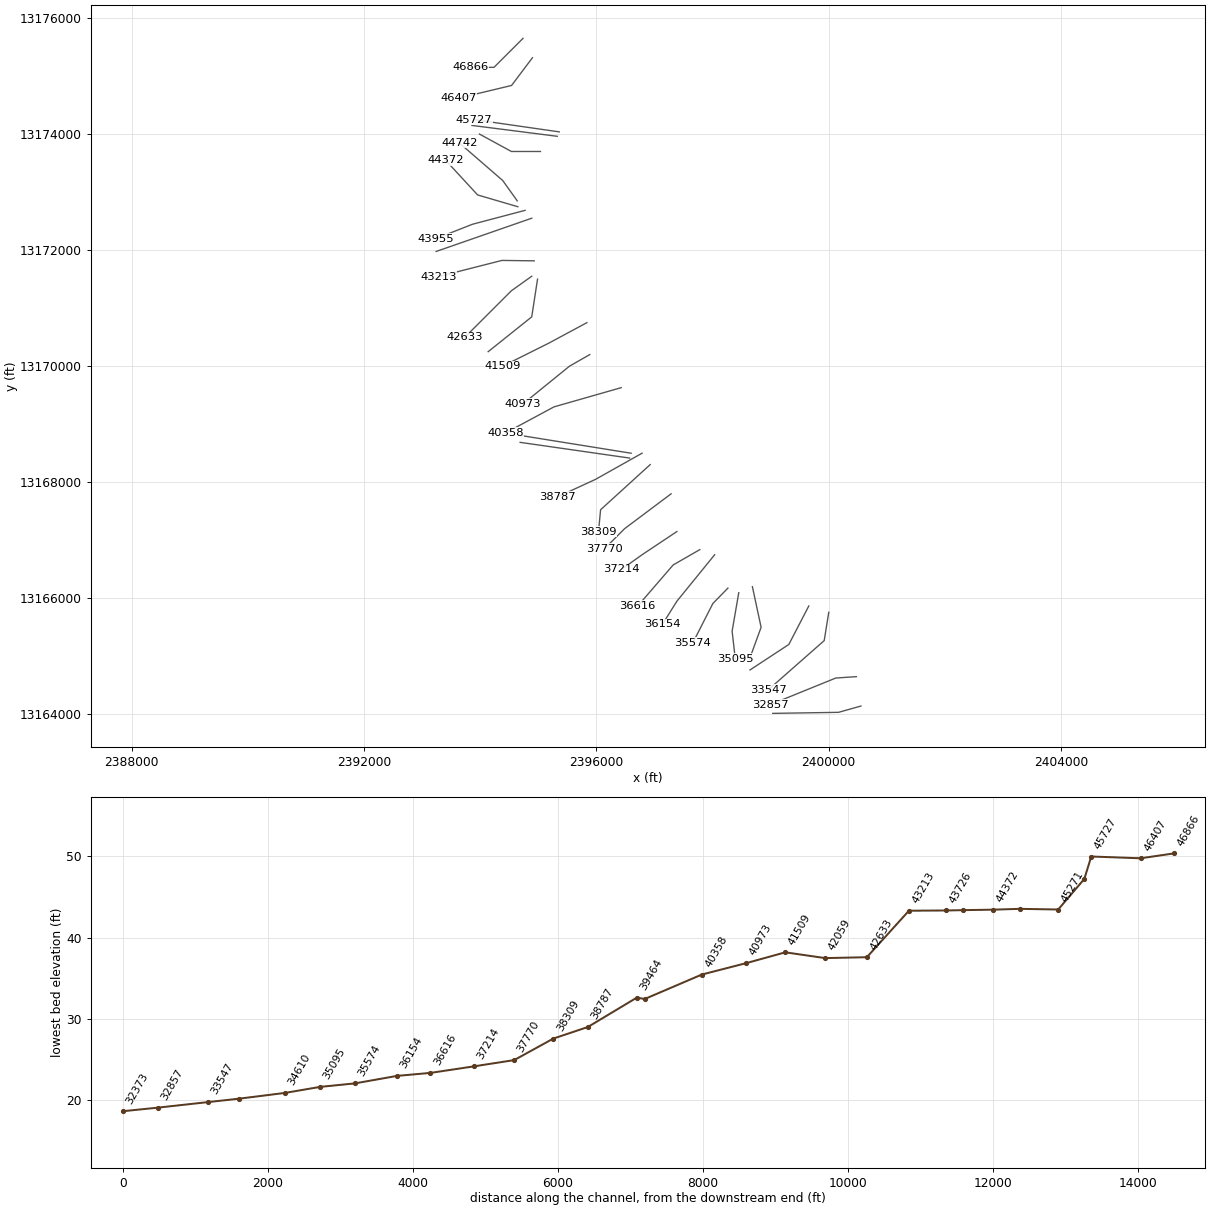
HEC-RAS study HONDO CREEK.prj: HONDO CREEK Base Level Engineering

--- HONDO CREEK.g01 (geometry) --- (continued)

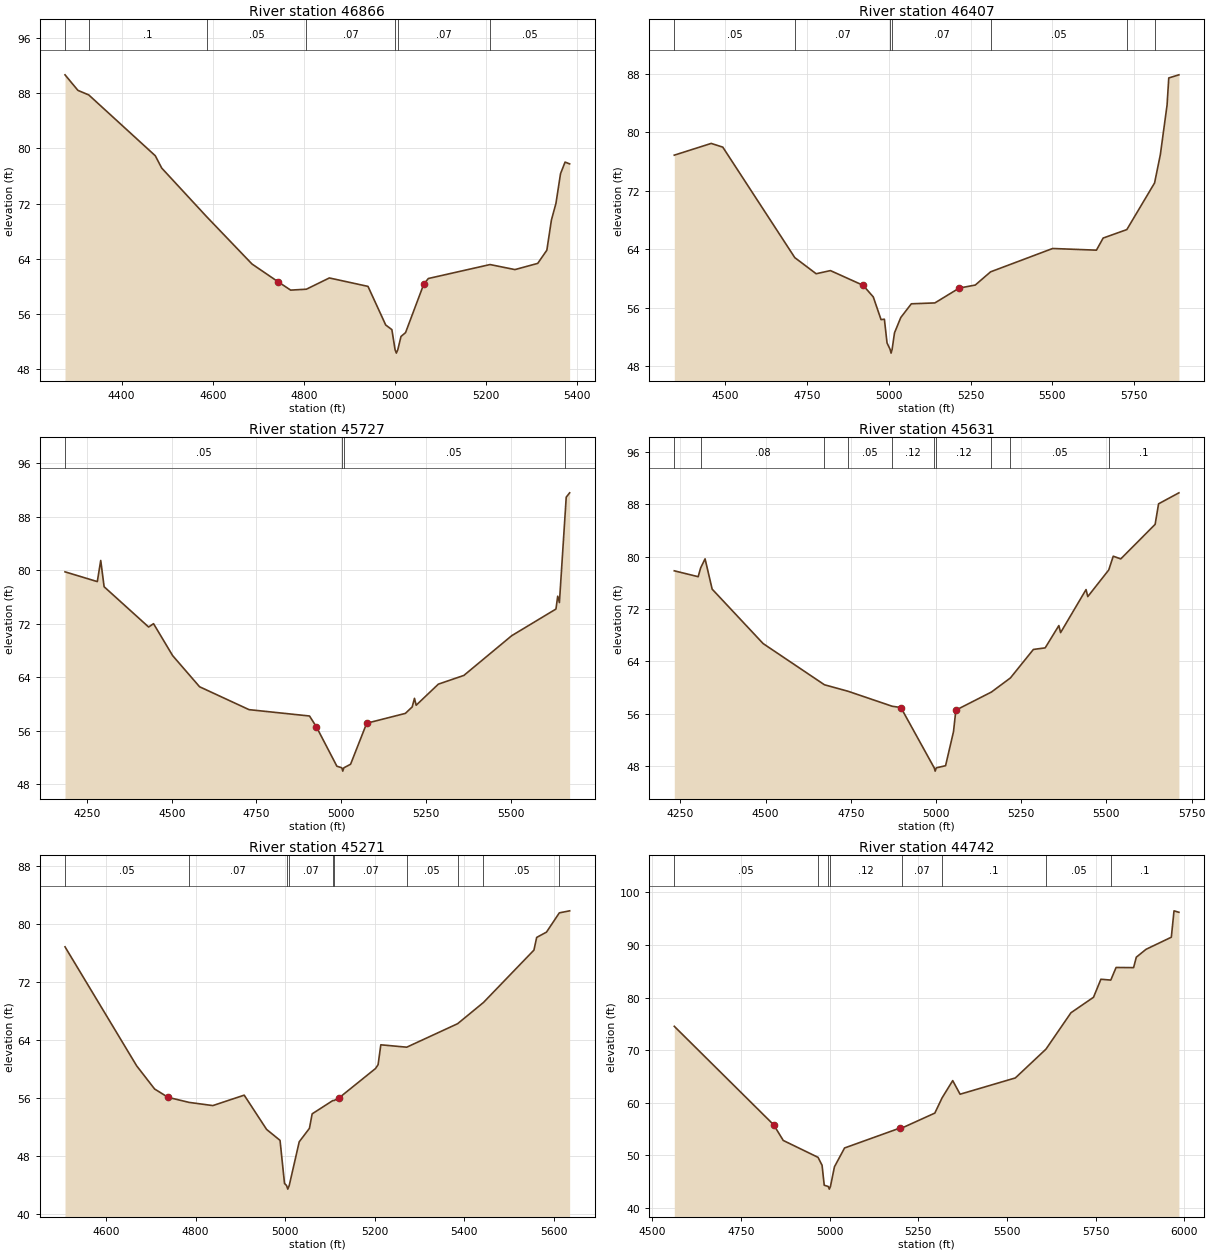
Type RM Length L Ch R = 1 ,46866   ,459,459,459
BEGIN DESCRIPTION:
HONDO CREEK 54.0
END DESCRIPTION:
XS GIS Cut Line= 3
      2394737.75     13175646.88      2394237.72     13175146.85
      2393837.77     13175146.85
#Sta/Elev= 30
  4275.9   90.63  4304.2   88.38    4328   87.72  4473.9   78.92  4488.1   77.13
  4586.3   70.12  4686.1   63.25  4742.6   60.71  4770.9   59.47  4805.4    59.6
  4855.8   61.23  4940.6   60.01  4979.5   54.42    4993   53.75    5000   50.85
  5002.8   50.35    5006   50.85    5013   52.76    5023   53.32    5063   60.34
    5073   61.15  5208.4   63.17    5263   62.44    5313   63.34    5333   65.25
    5343   69.61    5353   72.04    5363   76.32    5373      78    5383   77.74
#Mann= 7 ,-1 , 0
  4275.9     .05       0    4328      .1       0  4586.3     .05       0
  4805.4     .07       0    5000     .07       0    5006     .07       0
  5208.4     .05       0
Bank Sta=4742.6,5063
XS Rating Curve= 0 ,0
Exp/Cntr=0.3,0.1

Type RM Length L Ch R = 1 ,46407   ,680,680,680
BEGIN DESCRIPTION:
HONDO CREEK 53.0
END DESCRIPTION:
XS GIS Cut Line= 3
      2394900.19      13175312.5       2394540.4     13174834.65
      2393622.56     13174614.63
#Sta/Elev= 30
  4344.8   76.88  4457.6   78.49    4493   77.98    4713   62.84  4778.3   60.63
    4822   61.06  4921.9   59.04  4952.9   57.45  4976.6   54.34  4986.8    54.4
  4994.9   51.15  5004.4   50.25  5007.2   49.75  5010.4   50.25  5017.7   52.53
  5036.9   54.63  5069.1   56.51  5141.1   56.63  5215.3   58.66  5264.5   59.08
  5311.3   60.89    5501   64.09  5634.7   63.86  5655.3   65.52  5727.6   66.68
  5812.4   73.07  5830.1   76.96  5850.6   83.75  5855.8   87.46  5886.8   87.89
#Mann= 7 ,-1 , 0
  4344.8     .05       0    4713     .07       0  5004.4     .07       0
  5010.4     .07       0  5311.3     .05       0  5727.6      .1       0
  5812.4     .05       0
Bank Sta=4921.9,5215.3
XS Rating Curve= 0 ,0
Exp/Cntr=0.3,0.1

Type RM Length L Ch R = 1 ,45727   ,96,96,96
BEGIN DESCRIPTION:
HONDO CREEK 52.0
END DESCRIPTION:
XS GIS Cut Line= 2
      2395362.05     13174034.73      2393887.73     13174246.85
#Sta/Elev= 30
    4185   79.76  4280.3    78.3  4290.4   81.46  4300.4   77.53  4431.8   71.51
  4446.3   72.01  4502.6   67.24  4582.2   62.58  4728.2   59.16  4906.7   58.21
  4926.9    56.6  4987.5    50.7  5002.1   50.47  5004.8   49.97  5008.1   50.47
  5027.9      51  5075.5   57.13  5189.6    58.6  5209.8   59.57  5216.5   60.85
  5221.5   59.82  5286.9   62.97  5362.4   64.28  5503.4   70.21  5634.1    74.2
  5639.3   76.12  5644.3   75.17  5659.7   87.24  5664.4   90.92  5674.5   91.57
#Mann= 4 ,-1 , 0
    4185     .05       0  5002.1     .04       0  5008.1     .05       0
  5659.7      .1       0
Bank Sta=4926.9,5075.5
XS Rating Curve= 0 ,0
Exp/Cntr=0.3,0.1

Type RM Length L Ch R = 1 ,45631   ,360,360,360
BEGIN DESCRIPTION:
Mapping XS 6112e3b8
END DESCRIPTION:
XS GIS Cut Line= 2
      2395327.27     13173958.35      2393858.49     13174145.85
#Sta/Elev= 30
    4232   77.83  4302.1   76.93  4309.4   78.28  4322.3   79.66  4343.1   75.03
  4492.6   66.71  4672.6   60.41  4741.7   59.42  4871.2   57.13  4896.9   56.93
  4994.7   47.71  4997.5   47.21  5000.7   47.71    5028   48.04  5051.3   53.25
  5058.2   56.53  5162.6    59.3  5218.2   61.45  5285.7   65.81  5320.3   66.05
  5360.4   69.46  5365.5   68.38  5440.2   74.96  5445.3   73.89  5506.8   77.96
    5520   80.06  5542.1   79.65  5642.9   84.93    5653   88.07  5712.7   89.75
#Mann= 10 ,-1 , 0
    4232     .05       0  4309.4     .08       0  4672.6     .07       0
  4741.7     .05       0  4871.2     .12       0  4994.7     .07       0
  5000.7     .12       0  5162.6     .07       0  5218.2     .05       0
  5506.8      .1       0
Bank Sta=4896.9,5058.2
XS Rating Curve= 0 ,0
Exp/Cntr=0.3,0.1

Type RM Length L Ch R = 1 ,45271   ,529,529,529
BEGIN DESCRIPTION:
HONDO CREEK 51.0
END DESCRIPTION:
XS GIS Cut Line= 3
      2395037.74     13173696.85      2394537.72     13173696.85
      2393987.73     13173996.85
#Sta/Elev= 30
  4508.6    76.9  4668.6   60.47  4708.6   57.28  4738.6   56.13  4785.6   55.43
  4838.6   54.99  4908.6   56.43  4958.6    51.7  4988.6   50.19  4998.6   44.24
  5003.1   43.96  5005.9   43.46  5009.1   43.96  5031.4   49.99  5054.2   51.85
  5060.3   53.85  5106.3   55.68  5109.2   55.69  5120.1   56.04  5201.8   60.11
  5207.5   60.64  5213.6   63.38  5271.4   63.05    5385   66.29  5442.7   69.22
  5555.4   76.45  5561.5    78.2  5583.4   78.93  5612.1   81.59  5635.1   81.87
#Mann= 10 ,-1 , 0
  4508.6     .05       0  4785.6     .07       0  5003.1     .07       0
  5009.1     .07       0  5106.3     .12       0  5109.2     .07       0
  5271.4     .05       0    5385      .1       0  5442.7     .05       0
  5612.1      .1       0
Bank Sta=4738.6,5120.1
XS Rating Curve= 0 ,0
Exp/Cntr=0.3,0.1

Type RM Length L Ch R = 1 ,44742   ,370,370,370
BEGIN DESCRIPTION:
HONDO CREEK 50.0
END DESCRIPTION:
XS GIS Cut Line= 3
      2394637.72     13172846.86      2394387.72     13173196.85
      2393637.71     13173846.86
#Sta/Elev= 30
  4562.2   74.52  4842.4   55.78  4869.4    52.8  4967.4   49.59  4978.8   48.08
  4984.9   44.28  4996.4   44.04  4999.2   43.54  5002.4   44.04  5013.7   47.79
  5042.2   51.37  5197.9   55.15    5203   55.14  5296.7   58.01    5317   60.89
  5347.1   64.19  5367.9    61.6  5523.7    64.7    5610   70.18  5680.4    77.1
    5744   80.05  5764.9   83.48  5792.7   83.32  5807.7   85.72    5857   85.69
  5864.7   87.68  5892.2   89.18  5963.4   91.48    5971    96.5  5984.8   96.22
#Mann= 8 ,-1 , 0
  4562.2     .05       0  4967.4     .12       0  4996.4     .07       0
  5002.4     .12       0    5203     .07       0    5317      .1       0
    5610     .05       0  5792.7      .1       0
Bank Sta=4842.4,5197.9
XS Rating Curve= 0 ,0
Exp/Cntr=0.3,0.1

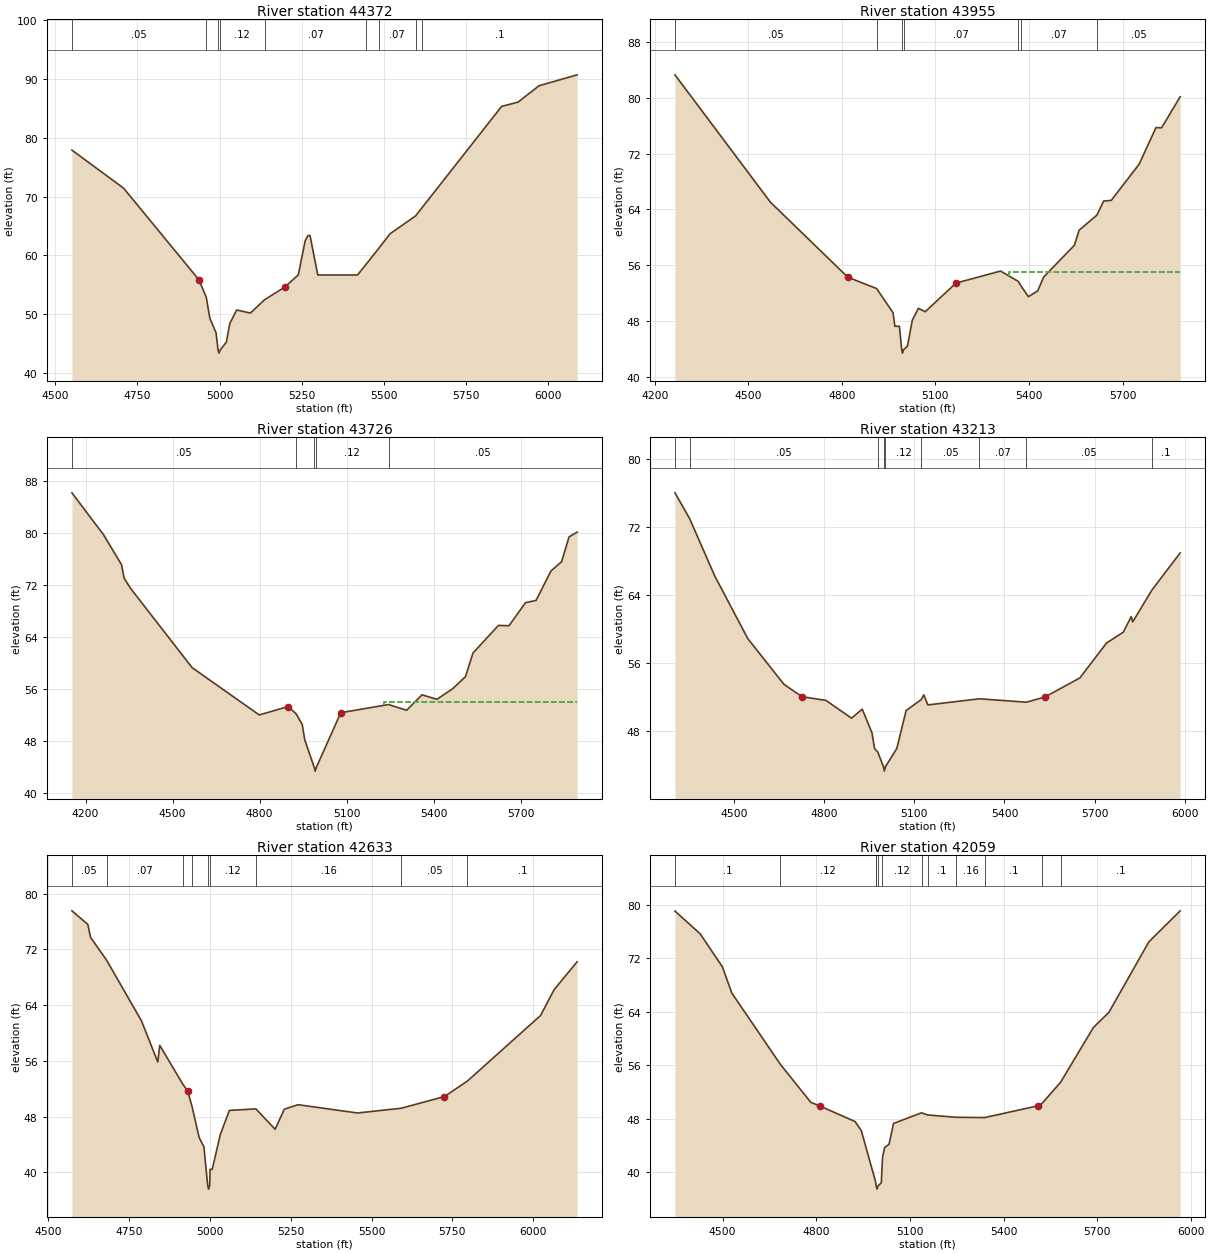
Type RM Length L Ch R = 1 ,44372   ,417,417,417
BEGIN DESCRIPTION:
Mapping XS b008ce94
END DESCRIPTION:
XS GIS Cut Line= 3
      2394648.45     13172744.81      2393955.76     13172947.93
       2393403.7     13173546.86
#Sta/Elev= 30
  4550.9   77.87    4708   71.42  4937.2   55.87  4959.6    52.9  4970.3   49.36
  4989.3   46.88  4995.5   43.94  4998.2   43.44  5001.5   43.94  5020.6   45.31
    5031   48.45  5051.9   50.76  5093.6   50.23  5136.9    52.5  5197.8   54.62
  5239.4   56.71  5260.3   62.51  5269.1   63.39    5275   63.39  5298.6   56.69
  5419.4   56.69  5446.6   58.58  5484.9   61.27  5518.1   63.67    5596   66.71
  5615.8   68.12  5857.8   85.29  5907.7   86.01  5971.2   88.78  6087.3   90.64
#Mann= 9 ,-1 , 0
  4550.9     .05       0  4959.6     .12       0  4995.5     .07       0
  5001.5     .12       0  5136.9     .07       0  5446.6     .05       0
  5484.9     .07       0    5596     .05       0  5615.8      .1       0
Bank Sta=4937.2,5197.8
XS Rating Curve= 0 ,0
Exp/Cntr=0.3,0.1

Type RM Length L Ch R = 1 ,43955   ,229,229,229
BEGIN DESCRIPTION:
HONDO CREEK 49.0
END DESCRIPTION:
XS GIS Cut Line= 3
      2394773.46      13172682.3      2393867.22     13172442.72
      2393232.27     13172192.91
#Sta/Elev= 30
  4265.1   83.32    4571   65.05  4819.5   54.27  4911.6   52.65  4964.1   49.19
  4970.2   47.23  4984.7   47.24  4992.1   43.88  4994.8   43.38  4998.1   43.88
  5010.4   44.38  5026.1    48.1  5045.5   49.81  5067.5   49.33  5166.2   53.43
  5309.1   55.16  5366.2   53.66  5373.1   53.12  5398.4   51.48  5428.2   52.32
  5447.2    54.3  5545.8   58.87  5560.9   61.02    5618   63.19  5639.5   65.21
  5663.9    65.3  5753.2   70.49  5807.4   75.75  5825.2   75.71  5884.8   80.17
#Mann= 7 ,-1 , 0
  4265.1     .05       0  4911.6     .07       0  4992.1     .07       0
  4998.1     .07       0  5366.2     .12       0  5373.1     .07       0
    5618     .05       0
#XS Ineff= 2 , 0
                         5336.25           55.02
Permanent Ineff=
       F       F
Bank Sta=4819.5,5166.2
XS Rating Curve= 0 ,0
Exp/Cntr=0.3,0.1

Type RM Length L Ch R = 1 ,43726   ,513,513,513
BEGIN DESCRIPTION:
HONDO CREEK 48.0
END DESCRIPTION:
XS GIS Cut Line= 2
      2394887.76     13172546.87      2393242.51     13171974.07
#Sta/Elev= 30
  4152.8   86.18  4261.7   79.74  4323.8   75.12  4332.8   73.04  4354.9   71.48
  4567.3   59.27  4798.7   51.99  4898.7   53.28  4925.9   52.16    4947   50.53
  4955.5   48.19  4988.9   43.84  4991.7   43.34  4994.9   43.84  5079.9   52.33
  5244.6   53.59    5307   52.71    5360   55.09  5411.3   54.39  5465.8   56.03
  5509.9   57.88  5535.7   61.52  5623.6   65.77    5660   65.72  5716.9   69.27
  5753.3   69.62  5804.7   74.15  5841.3   75.57  5867.1    79.4  5894.9   80.13
#Mann= 5 ,-1 , 0
  4152.8     .05       0  4925.9     .12       0  4988.9     .07       0
  4994.9     .12       0  5244.6     .05       0
#XS Ineff= 2 , 0
                         5228.41           54.02
Permanent Ineff=
       F       F
Bank Sta=4898.7,5079.9
XS Rating Curve= 0 ,0
Exp/Cntr=0.3,0.1

Type RM Length L Ch R = 1 ,43213   ,580,580,580
BEGIN DESCRIPTION:
HONDO CREEK 47.0
END DESCRIPTION:
XS GIS Cut Line= 3
      2394929.98     13171812.43      2394374.42     13171819.38
      2393284.64     13171541.73
#Sta/Elev= 30
  4304.1   76.05  4352.5   73.05  4436.4   66.27  4546.4    58.9  4666.4   53.53
  4726.4   52.07  4806.4   51.63  4891.3   49.54    4927    50.6  4959.5    47.8
  4967.9   45.96  4978.8   45.54  4997.8   43.81  5000.5   43.31  5003.8   43.81
    5042   45.98    5073   50.44  5123.8   51.74  5131.5   52.29  5145.2    51.1
  5316.5   51.82  5472.7   51.42  5535.2   52.04  5650.9   54.28  5739.7   58.39
  5795.4   59.66  5821.5   61.49  5826.6   60.87  5890.5   64.62  5984.3   68.98
#Mann= 9 ,-1 , 0
  4304.1      .1       0  4352.5     .05       0  4978.8     .12       0
  4997.8     .07       0  5003.8     .12       0  5123.8     .05       0
  5316.5     .07       0  5472.7     .05       0  5890.5      .1       0
Bank Sta=4726.4,5535.2
XS Rating Curve= 0 ,0
Exp/Cntr=0.3,0.1

Type RM Length L Ch R = 1 ,42633   ,574,574,574
BEGIN DESCRIPTION:
HONDO CREEK 46.0
END DESCRIPTION:
XS GIS Cut Line= 3
      2394887.69     13171546.83      2394537.72     13171296.85
      2393737.75     13170496.89
#Sta/Elev= 30
    4574   77.55  4623.1   75.61  4631.7   73.73    4681   70.48    4789   61.75
  4839.4   55.85  4845.5   58.24  4916.1   52.71  4931.6   51.71  4945.4   49.43
  4967.2   45.01    4982   43.66  4993.7    38.1  4996.5    37.6  4999.7    38.1
    5001   40.44  5007.6   40.44  5032.4    45.4  5060.6    48.9  5142.6   49.12
  5202.1   46.19  5230.3   49.07  5272.8   49.72  5456.6   48.53  5591.7   49.21
  5725.3   50.89  5796.5   53.12  6022.3   62.52  6064.7   66.26  6135.4   70.24
#Mann= 9 ,-1 , 0
    4574     .05       0    4681     .07       0  4916.1      .1       0
  4945.4     .12       0  4993.7     .07       0  4999.7     .12       0
  5142.6     .16       0  5591.7     .05       0  5796.5      .1       0
Bank Sta=4931.6,5725.3
XS Rating Curve= 0 ,0
Exp/Cntr=0.3,0.1

Type RM Length L Ch R = 1 ,42059   ,550,550,550
BEGIN DESCRIPTION:
HONDO CREEK 45.0
END DESCRIPTION:
XS GIS Cut Line= 3
      2394987.73      13171496.9      2394887.72     13170846.85
      2394137.69     13170246.83
#Sta/Elev= 30
  4347.6   79.07  4428.6   75.65  4499.4   70.74  4529.8    66.8  4685.3   56.15
  4782.7   50.47  4813.1   49.89  4924.4    47.6  4944.6   46.23    4990   38.64
  4992.2   37.99  4994.9   37.49  4998.2   37.99  5008.5   38.43  5010.6   40.41
  5012.5   42.21  5018.9   43.68  5033.3    44.2  5047.7   47.31  5137.4    48.9
  5156.6   48.58  5248.6   48.23    5340   48.19  5510.3   49.95  5522.9   50.27
    5583   53.48    5688   61.66  5737.7   63.93  5865.7   74.47  5965.8    79.1
#Mann= 12 ,-1 , 0
  4347.6      .1       0  4685.3     .12       0    4990     .07       0
  4992.2     .07       0  4998.2     .07       0  5010.6     .12       0
  5137.4     .16       0  5156.6      .1       0  5248.6     .16       0
    5340      .1       0  5522.9     .16       0    5583      .1       0
Bank Sta=4813.1,5510.3
XS Rating Curve= 0 ,0
Exp/Cntr=0.3,0.1

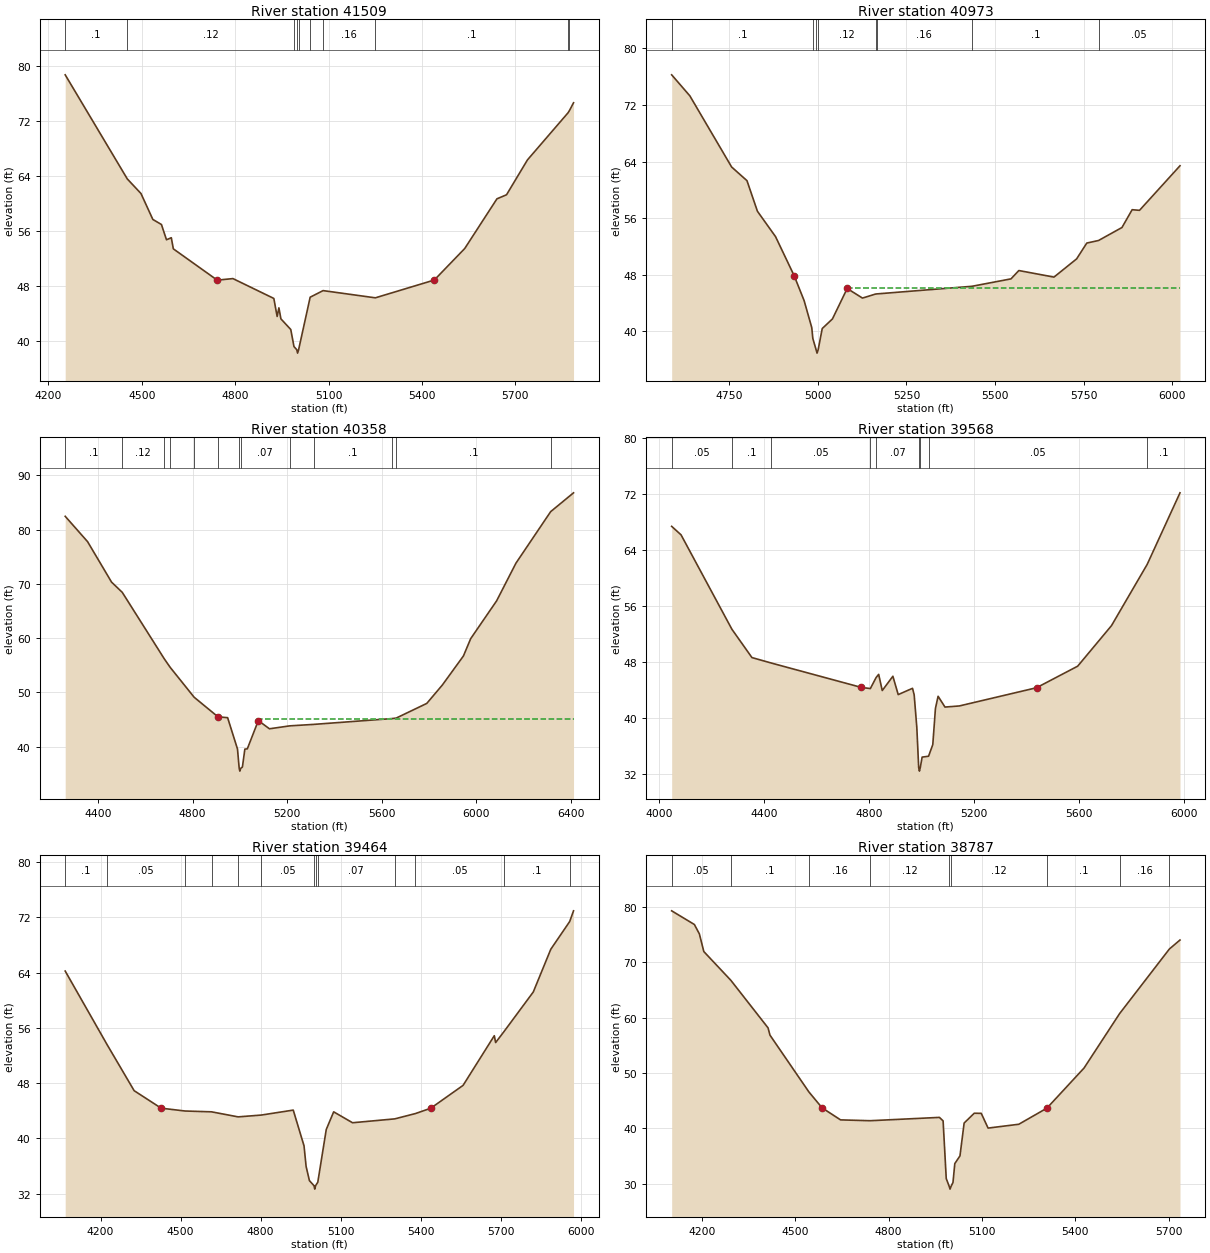
Type RM Length L Ch R = 1 ,41509   ,536,536,536
BEGIN DESCRIPTION:
HONDO CREEK 44.0
END DESCRIPTION:
XS GIS Cut Line= 3
      2395837.75     13170746.87      2395187.72     13170396.85
      2394387.72     13169996.86
#Sta/Elev= 30
  4254.1   78.71  4453.5   63.56  4497.5   61.43  4535.6   57.66  4563.2   56.92
  4579.4    54.7  4594.9      55  4601.4   53.38  4742.5   48.82  4792.8   49.05
  4924.2   46.16  4934.8   43.54  4940.5   44.79  4946.9   43.19  4978.6   41.64
  4988.9   39.15  4997.8    38.7  5000.5    38.2  5003.8    38.7  5040.9   46.34
  5082.4    47.3  5250.3   46.25  5439.6   48.84  5537.4   53.43  5640.8   60.66
  5671.6   61.25  5738.7   66.32  5869.3   73.19  5873.7   73.51  5886.8   74.64
#Mann= 10 ,-1 , 0
  4254.1      .1       0  4453.5     .12       0  4988.9      .1       0
  4997.8     .07       0  5003.8      .1       0  5040.9     .12       0
  5082.4     .16       0  5250.3      .1       0  5869.3     .05       0
  5873.7      .1       0
Bank Sta=4742.5,5439.6
XS Rating Curve= 0 ,0
Exp/Cntr=0.3,0.1

Type RM Length L Ch R = 1 ,40973   ,615,615,615
BEGIN DESCRIPTION:
HONDO CREEK 43.0
END DESCRIPTION:
XS GIS Cut Line= 3
      2395887.76     13170196.88      2395537.72     13169996.85
      2394737.75     13169346.88
#Sta/Elev= 30
  4587.7   76.27  4638.9    73.3  4756.9   63.22  4800.1   61.29  4829.6   56.96
  4880.7   53.37  4933.3   47.83  4961.3   44.31  4982.9   40.49  4985.9   38.95
    4995   37.38  4997.8   36.88    5001   37.38  5012.4   40.36  5041.2   41.72
  5082.8   46.03  5125.9   44.67  5162.7   45.24  5166.1   45.26  5434.9   46.34
  5544.9   47.39    5567   48.57  5666.1   47.64    5730   50.22  5758.7   52.46
  5791.8   52.82  5857.9   54.66  5886.6   57.18  5907.4   57.09  6021.6    63.4
#Mann= 8 ,-1 , 0
  4587.7      .1       0  4985.9     .12       0    4995     .07       0
    5001     .12       0  5162.7     .07       0  5166.1     .16       0
  5434.9      .1       0  5791.8     .05       0
#XS Ineff= 2 , 0
                         5085.23           46.08
Permanent Ineff=
       F       F
Bank Sta=4933.3,5082.8
XS Rating Curve= 0 ,0
Exp/Cntr=0.3,0.1

Type RM Length L Ch R = 1 ,40358   ,790,790,790
BEGIN DESCRIPTION:
HONDO CREEK 42.0
END DESCRIPTION:
XS GIS Cut Line= 3
      2396428.23     13169626.67      2395270.28     13169295.15
      2394437.68     13168846.83
#Sta/Elev= 30
  4261.3   82.47    4356   77.79  4457.4   70.33  4502.7   68.44    4681   56.14
  4705.2   54.62  4806.4   49.11  4907.6   45.48  4948.3   45.33    4990   39.55
  4997.3   35.97    5000   35.47  5003.3   35.97  5010.8   36.22  5021.2   39.53
  5031.6   39.58  5078.2   44.79  5125.2   43.28  5211.3   43.82  5312.5   44.09
  5643.3   45.16  5661.2   45.25  5790.7   47.96  5856.5   51.35  5945.7   56.71
  5976.5   59.91    6086   66.87    6168   73.84  6314.7   83.33  6411.4    86.8
#Mann= 13 ,-1 , 0
  4261.3      .1       0  4502.7     .12       0    4681      .1       0
  4705.2     .12       0  4806.4     .05       0  4907.6     .07       0
  4997.3     .07       0  5003.3     .07       0  5211.3     .12       0
  5312.5      .1       0  5643.3     .05       0  5661.2      .1       0
  6314.7     .05       0
#XS Ineff= 2 , 0
                         5083.81           45.17
Permanent Ineff=
       F       F
Bank Sta=4907.6,5078.2
XS Rating Curve= 0 ,0
Exp/Cntr=0.3,0.1

Type RM Length L Ch R = 1 ,39568   ,104,104,104
BEGIN DESCRIPTION:
HONDO CREEK 41.0
END DESCRIPTION:
XS GIS Cut Line= 2
      2396599.57     13168496.45      2394688.12     13168803.75
#Sta/Elev= 30
  4049.2   67.42  4084.9   66.21  4278.5   52.73  4354.9   48.68  4428.5    47.9
  4770.2   44.43  4805.8   44.25  4827.9   45.83  4837.6   46.28  4851.2   43.97
  4891.7   46.01    4912   43.39  4966.5   44.29  4972.8   43.35  4982.9   38.68
    4990   32.96  4992.8   32.46    4996   32.96  5003.1   34.46  5027.6   34.59
  5043.7   36.25  5053.8   41.42  5063.9   43.15  5090.2   41.61  5144.9   41.77
  5438.7   44.37  5595.5   47.45  5724.3   53.24  5860.4      62  5985.2   72.21
#Mann= 9 ,-1 , 0
  4049.2     .05       0  4278.5      .1       0  4428.5     .05       0
  4805.8      .1       0  4827.9     .07       0    4990     .07       0
    4996     .07       0  5027.6     .05       0  5860.4      .1       0
Bank Sta=4770.2,5438.7
XS Rating Curve= 0 ,0
Exp/Cntr=0.3,0.1

Type RM Length L Ch R = 1 ,39464   ,677,677,677
BEGIN DESCRIPTION:
HONDO CREEK 40.0
END DESCRIPTION:
XS GIS Cut Line= 2
      2396573.52     13168413.12      2394688.07     13168683.96
#Sta/Elev= 30
  4067.7   64.22  4223.9   53.62  4326.1    46.9  4427.2   44.37  4516.5   43.96
  4616.1   43.84  4715.6   43.11    4802   43.37  4922.2   44.09  4962.6   38.92
  4970.4   35.94  4982.8   33.88    5000   33.15  5002.8   32.65    5006   33.15
  5014.2   33.65  5045.9   41.28  5073.7   43.84  5144.4   42.26  5302.6   42.82
  5380.1   43.59  5437.4   44.36  5558.6   47.67  5675.6   54.86  5680.6   53.87
    5711   55.41  5821.7   61.19  5887.2   67.37  5958.1   71.39  5972.5   72.94
#Mann= 13 ,-1 , 0
  4067.7      .1       0  4223.9     .05       0  4516.5      .1       0
  4616.1     .16       0  4715.6     .12       0    4802     .05       0
    5000     .04       0    5006     .05       0  5014.2     .07       0
  5302.6     .12       0  5380.1     .05       0    5711      .1       0
  5958.1     .05       0
Bank Sta=4427.2,5437.4
XS Rating Curve= 0 ,0
Exp/Cntr=0.3,0.1

Type RM Length L Ch R = 1 ,38787   ,478,478,478
BEGIN DESCRIPTION:
HONDO CREEK 39.0
END DESCRIPTION:
XS GIS Cut Line= 3
      2396787.76     13168496.88      2395987.72     13168046.85
      2395337.74     13167746.86
#Sta/Elev= 30
  4103.1   79.27  4176.1    76.8  4192.1   75.11  4206.4   71.92  4293.4   66.72
  4412.9   58.14    4419   56.83  4544.1   46.58  4586.6    43.7  4645.9   41.53
  4740.8   41.38  4963.7   41.98  4975.5   41.35  4985.6   30.94  4995.1   29.53
  4997.8   29.03  5001.1   29.53  5007.3   30.24  5013.1   33.64  5029.7   35.03
  5043.1   40.96  5075.6   42.73  5098.1   42.71  5120.1   40.05  5218.8   40.74
  5309.2   43.65  5428.5   50.89  5542.7   60.71  5702.8   72.38  5736.9      74
#Mann= 9 ,-1 , 0
  4103.1     .05       0  4293.4      .1       0  4544.1     .16       0
  4740.8     .12       0  4995.1     .07       0  5001.1     .12       0
  5309.2      .1       0  5542.7     .16       0  5702.8      .1       0
Bank Sta=4586.6,5309.2
XS Rating Curve= 0 ,0
Exp/Cntr=0.3,0.1

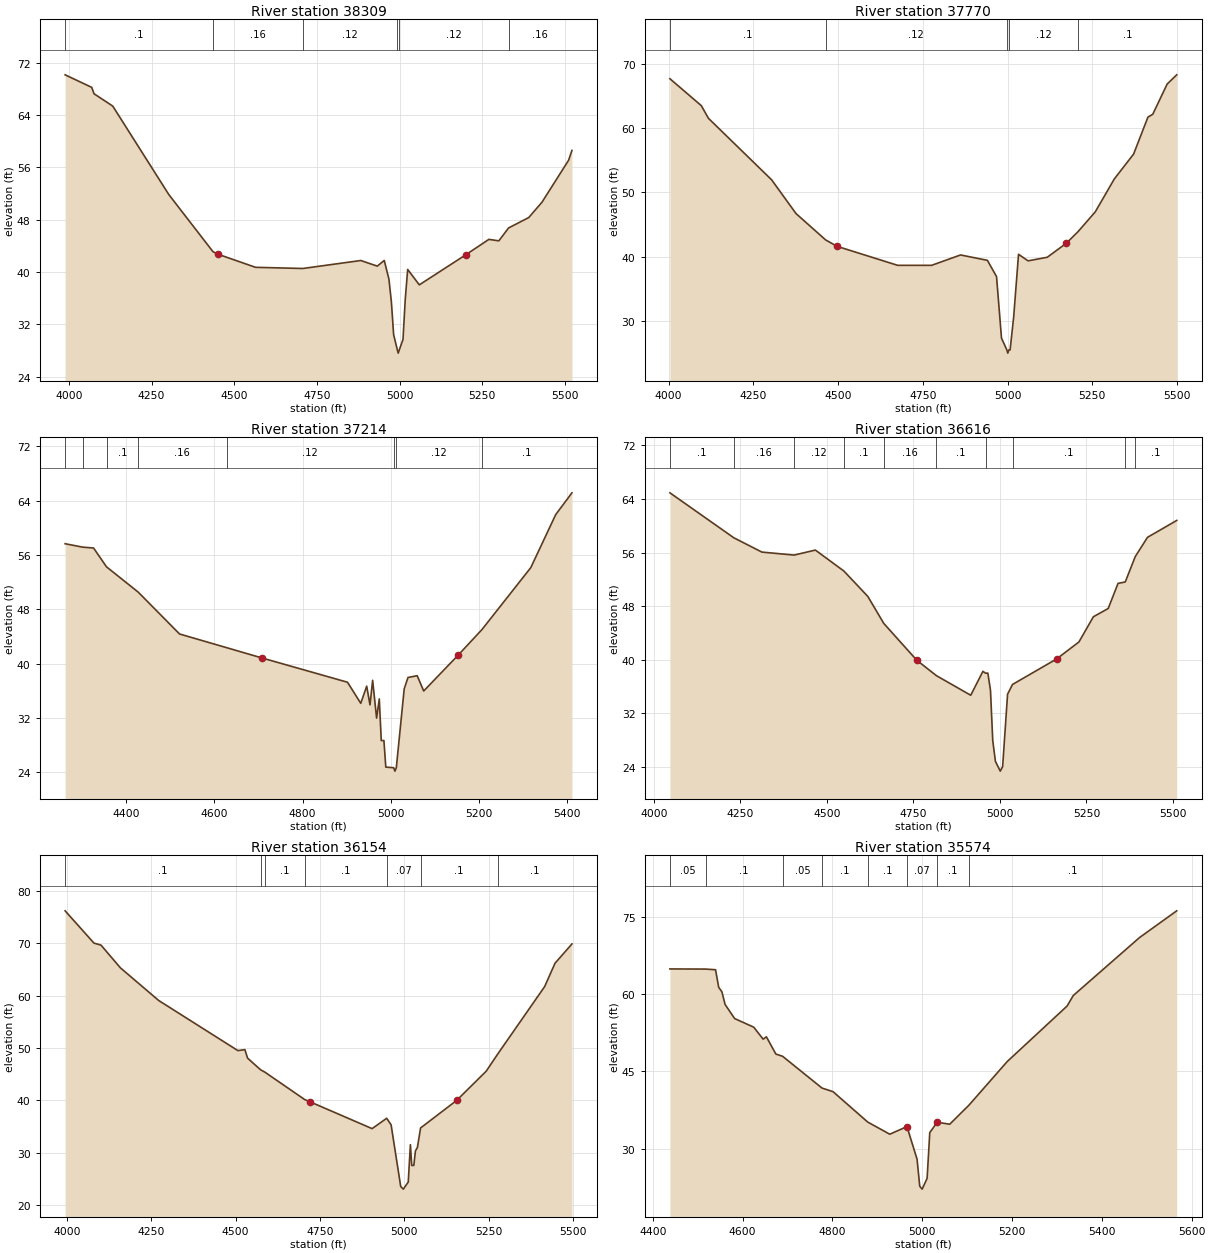
Type RM Length L Ch R = 1 ,38309   ,539,539,539
BEGIN DESCRIPTION:
HONDO CREEK 38.0
END DESCRIPTION:
XS GIS Cut Line= 3
      2396927.65     13168300.27       2396073.5      13167522.5
      2396037.72     13167146.81
#Sta/Elev= 30
  3988.7   70.15  4069.2   68.23    4076   67.26  4132.7   65.37  4302.3   51.84
  4435.8   43.11    4451   42.72  4564.5   40.72  4707.4   40.54  4882.8   41.76
  4932.7    40.9  4953.7   41.77  4967.9   38.91  4975.3   35.45  4982.1   30.42
  4993.3    28.1    4996    27.6  4999.3    28.1  5010.4   29.68  5017.2    35.8
  5024.6   40.39  5059.8   38.04  5199.8   42.62  5270.1   44.99  5300.3   44.77
  5329.8   46.74  5390.7   48.33  5430.8   50.68  5511.2   57.09  5521.3   58.59
#Mann= 6 ,-1 , 0
  3988.7      .1       0  4435.8     .16       0  4707.4     .12       0
  4993.3     .07       0  4999.3     .12       0  5329.8     .16       0
Bank Sta=4451,5199.8
XS Rating Curve= 0 ,0
Exp/Cntr=0.3,0.1

Type RM Length L Ch R = 1 ,37770   ,556,556,556
BEGIN DESCRIPTION:
HONDO CREEK 37.0
END DESCRIPTION:
XS GIS Cut Line= 3
      2397287.72     13167796.85      2396487.72     13167196.85
       2396137.7     13166846.84
#Sta/Elev= 30
  4003.9   67.72  4096.6   63.52  4117.4   61.56  4303.9   51.97  4375.8   46.71
  4463.1   42.61  4496.6   41.61  4675.8   38.64  4775.8   38.64  4861.2   40.26
  4940.4   39.42  4967.4   36.88    4982    27.3  4997.8   25.46  5000.5   24.96
  5003.8   25.46  5007.4   25.46    5018   30.65  5032.2   40.36  5060.5   39.34
    5117    39.9  5173.6    42.1  5208.1   43.91  5258.5   46.97    5315   52.12
  5371.6   55.97    5414   61.74  5428.2   62.18  5470.6   66.89  5498.9   68.33
#Mann= 5 ,-1 , 0
  4003.9      .1       0  4463.1     .12       0  4997.8     .07       0
  5003.8     .12       0  5208.1      .1       0
Bank Sta=4496.6,5173.6
XS Rating Curve= 0 ,0
Exp/Cntr=0.3,0.1

Type RM Length L Ch R = 1 ,37214   ,598,598,598
BEGIN DESCRIPTION:
HONDO CREEK 36.0
END DESCRIPTION:
XS GIS Cut Line= 3
      2397387.69     13167146.83      2396787.72     13166746.85
      2396437.71     13166496.85
#Sta/Elev= 30
  4260.8   57.65  4300.3   57.15  4325.4   57.02  4354.8   54.25  4426.8   50.53
  4520.7   44.37  4627.4   42.36  4706.9   40.86  4902.2   37.27  4932.3   34.17
  4945.8   36.69  4953.3   33.94  4959.3   37.55  4968.3   31.99  4974.4   34.82
  4978.9   28.69  4984.9   28.69  4989.2   24.78  5007.1   24.69  5009.9   24.19
  5013.1   24.69    5031   36.29  5039.6   37.97  5060.5   38.23  5075.3   35.98
  5153.9   41.28  5207.5   45.01  5318.6   54.14  5375.1   61.93    5412   65.14
#Mann= 8 ,-1 , 0
  4260.8      .1       0  4300.3     .16       0  4354.8      .1       0
  4426.8     .16       0  4627.4     .12       0  5007.1     .07       0
  5013.1     .12       0  5207.5      .1       0
Bank Sta=4706.9,5153.9
XS Rating Curve= 0 ,0
Exp/Cntr=0.3,0.1

Type RM Length L Ch R = 1 ,36616   ,462,462,462
BEGIN DESCRIPTION:
HONDO CREEK 35.0
END DESCRIPTION:
XS GIS Cut Line= 3
      2397781.85     13166835.02       2397323.5     13166571.11
      2396712.53     13165862.94
#Sta/Elev= 30
  4046.8   64.91  4231.5    58.2  4312.4   56.07  4405.6   55.62    4467   56.37
  4549.4   53.24  4618.6   49.45  4664.6   45.43  4760.1   39.93  4816.8   37.63
  4915.9   34.71  4951.1   38.28  4958.7      38  4965.3   38.02  4972.9   35.46
  4979.5   27.93  4987.2   24.85  5001.2   23.39    5008   24.06  5022.3   34.87
  5036.6   36.32  5163.8   40.12  5228.5   42.66  5270.2   46.42    5313   47.65
  5341.5    51.4  5362.3   51.61  5391.3   55.41  5426.6   58.27    5511   60.79
#Mann= 10 ,-1 , 0
  4046.8      .1       0  4231.5     .16       0  4405.6     .12       0
  4549.4      .1       0  4664.6     .16       0  4816.8      .1       0
  4958.7     .07       0  5036.6      .1       0  5362.3     .16       0
  5391.3      .1       0
Bank Sta=4760.1,5163.8
XS Rating Curve= 0 ,0
Exp/Cntr=0.3,0.1

Type RM Length L Ch R = 1 ,36154   ,580,580,580
BEGIN DESCRIPTION:
HONDO CREEK 34.0
END DESCRIPTION:
XS GIS Cut Line= 3
      2398037.74     13166746.88      2397387.72     13165946.85
      2397137.73     13165546.86
#Sta/Elev= 30
  3994.7    76.2  4080.2   70.03    4101   69.65  4158.5   65.31    4272   59.07
  4506.9   49.49  4527.7   49.67  4535.6   48.05  4574.1   45.83  4587.2   45.36
  4704.6   40.15  4719.5   39.74  4904.8   34.58    4948   36.56  4961.1   35.31
  4989.6   23.52  4997.3   23.02  5011.9   24.37  5018.3    31.5  5022.3   27.55
  5028.5   27.55  5033.2   30.31  5039.1   30.99  5048.5   34.71  5155.2   39.96
  5243.1   45.56  5276.6   48.78  5416.4   61.73  5447.1   66.19  5497.2   69.87
#Mann= 7 ,-1 , 0
  3994.7      .1       0  4574.1     .16       0  4587.2      .1       0
  4704.6      .1       0    4948     .07       0  5048.5      .1       0
  5276.6      .1       0
Bank Sta=4719.5,5155.2
XS Rating Curve= 0 ,0
Exp/Cntr=0.3,0.1

Type RM Length L Ch R = 1 ,35574   ,479,479,479
BEGIN DESCRIPTION:
HONDO CREEK 33.0
END DESCRIPTION:
XS GIS Cut Line= 3
      2398266.27     13166171.95      2398006.95     13165906.59
      2397663.38     13165231.52
#Sta/Elev= 30
  4438.3   64.96  4517.7   64.93  4539.9    64.8  4546.9   61.39  4554.1    60.5
  4561.1   58.05  4582.4    55.3  4624.8   53.63  4645.9   51.29  4653.1   51.75
  4674.2   48.39  4689.3   47.95    4777   41.77  4801.5   41.07  4878.8   35.15
  4927.9   32.79  4966.1   34.27  4988.6   27.93  4994.6   22.66    5000    22.1
    5011   24.21  5016.9   33.11  5033.5   35.12  5061.3   34.73  5104.2   38.45
  5189.2   46.92  5322.7   57.74  5336.4   59.78    5484   71.07  5566.8   76.27
#Mann= 8 ,-1 , 0
  4438.3     .05       0  4517.7      .1       0  4689.3     .05       0
    4777      .1       0  4878.8      .1       0  4966.1     .07       0
  5033.5      .1       0  5104.2      .1       0
Bank Sta=4966.1,5033.5
XS Rating Curve= 0 ,0
Exp/Cntr=0.3,0.1

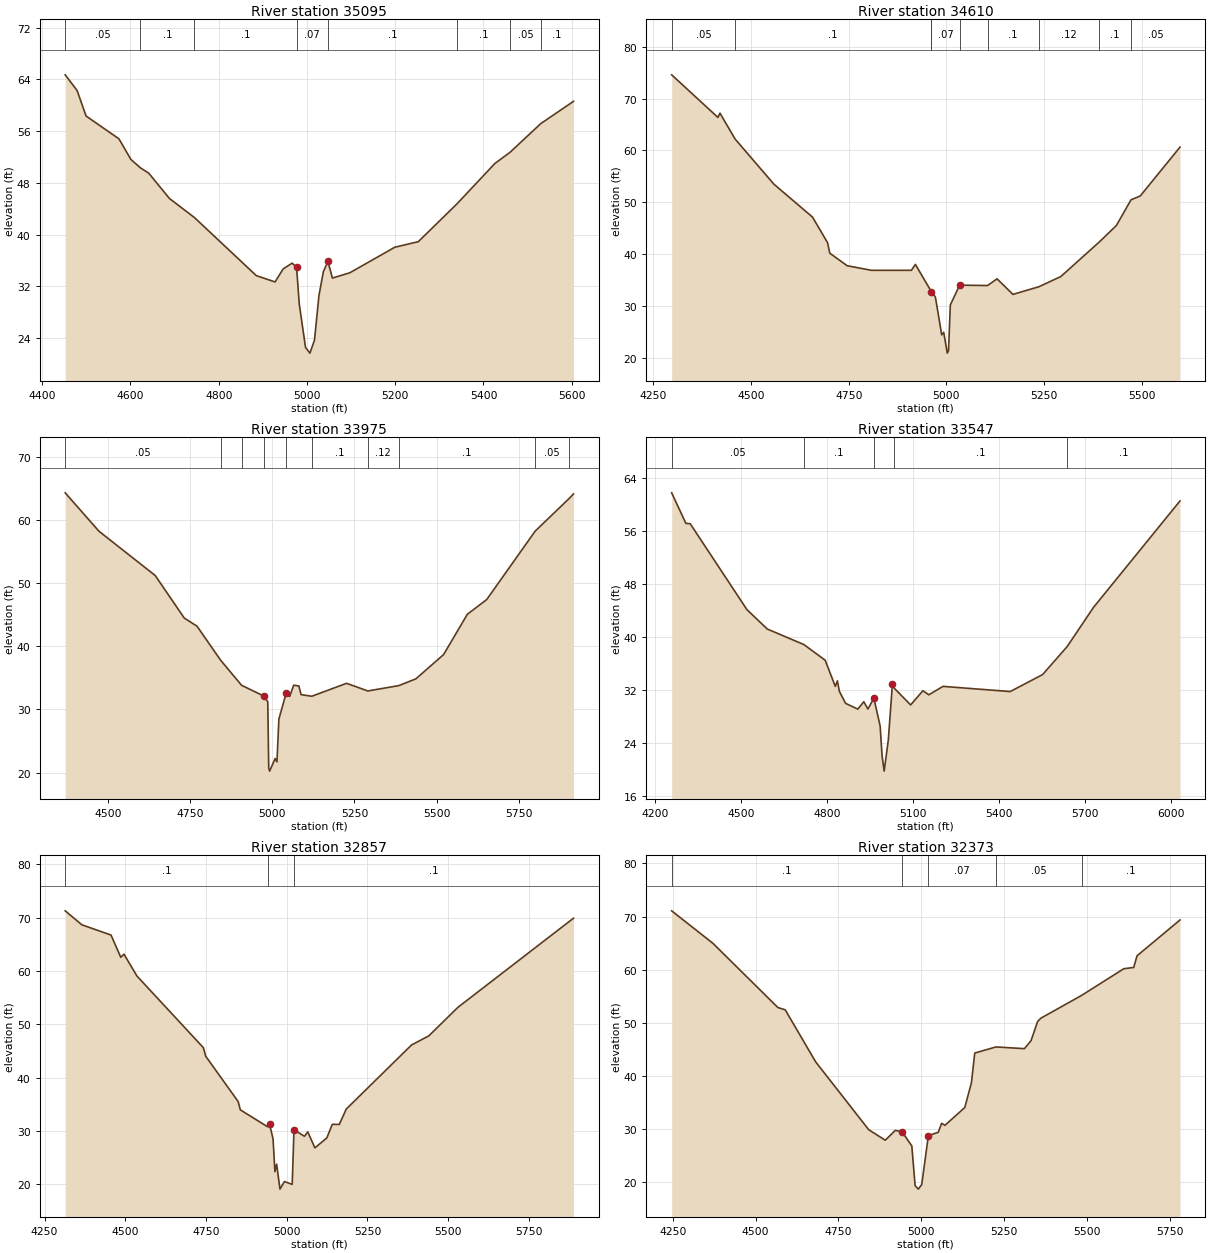
Type RM Length L Ch R = 1 ,35095   ,485,485,485
BEGIN DESCRIPTION:
HONDO CREEK 32.0
END DESCRIPTION:
XS GIS Cut Line= 3
      2398453.17      13166093.5      2398338.61     13165430.21
       2398392.8      13164954.5
#Sta/Elev= 30
  4452.2   64.72  4479.2   62.29  4499.5   58.35    4574   54.82    4601   51.64
  4621.9   50.37  4641.6    49.5  4688.6   45.58  4745.1   42.64  4885.2   33.66
  4927.8   32.68    4946   34.69  4966.3   35.59  4976.5   34.96  4982.6   29.25
  4996.8   22.55  5006.7   21.67  5017.1   23.68  5027.2   30.58  5037.3   34.29
  5047.5   35.85  5057.7   33.28  5097.2    34.1  5199.1   38.05  5252.3   38.91
  5339.4   44.72  5426.1   51.02  5460.3   52.74  5529.8   57.17  5604.1   60.62
#Mann= 8 ,-1 , 0
  4452.2     .05       0  4621.9      .1       0  4745.1      .1       0
  4976.5     .07       0  5047.5      .1       0  5339.4      .1       0
  5460.3     .05       0  5529.8      .1       0
Bank Sta=4976.5,5047.5
XS Rating Curve= 0 ,0
Exp/Cntr=0.3,0.1

Type RM Length L Ch R = 1 ,34610   ,635,635,635
BEGIN DESCRIPTION:
HONDO CREEK 31.0
END DESCRIPTION:
XS GIS Cut Line= 3
      2398687.72     13166196.84      2398837.72     13165496.85
      2398637.72     13164946.86
#Sta/Elev= 30
  4296.9   74.57  4415.3   66.36  4420.5   67.19  4459.2    62.2  4558.5    53.5
  4657.4   47.15  4695.7   42.25  4701.7   40.19    4746   37.78  4808.2   36.89
  4910.5   36.89  4920.7   38.03  4961.6   32.78  4971.9   31.75  4988.1   24.45
  4993.2   24.95  5002.3   20.93  5005.5   21.43  5010.2   30.23  5034.1   34.03
  5105.5   33.96  5129.8   35.25  5170.4   32.25  5236.6   33.72  5292.8   35.68
  5391.3   42.34  5435.1   45.52  5472.7   50.49  5496.3   51.22    5598   60.64
#Mann= 9 ,-1 , 0
  4296.9     .05       0  4459.2      .1       0  4961.6     .12       0
  4961.6     .07       0  5034.1      .1       0  5105.5      .1       0
  5236.6     .12       0  5391.3      .1       0  5472.7     .05       0
Bank Sta=4961.6,5034.1
XS Rating Curve= 0 ,0
Exp/Cntr=0.3,0.1

Type RM Length L Ch R = 1 ,33975   ,428,428,428
BEGIN DESCRIPTION:
HONDO CREEK 30.0
END DESCRIPTION:
XS GIS Cut Line= 3
       2399659.2     13165864.36      2399315.49     13165201.06
      2398646.88     13164761.35
#Sta/Elev= 30
  4369.8   64.34  4472.4   58.26  4643.8   51.23  4732.3   44.48    4771    43.2
  4842.7   37.82  4906.8   33.82  4975.8   32.09  4986.4   31.18  4989.3   20.72
    4992   20.22  5008.8   22.22  5014.4   21.69  5020.2   28.47  5042.8   32.65
    5053   32.05  5065.3   33.84  5080.8   33.73  5087.8   32.35  5120.4   32.09
  5226.3   34.14    5291   32.93  5385.5   33.78  5437.2   34.85  5521.5   38.69
  5593.8   45.08  5652.8   47.42  5800.6   58.28  5902.7   63.39  5917.1   64.17
#Mann= 10 ,-1 , 0
  4369.8     .05       0  4842.7      .1       0  4906.8      .1       0
  4975.8     .07       0  5042.8      .1       0  5120.4      .1       0
    5291     .12       0  5385.5      .1       0  5800.6     .05       0
  5902.7      .1       0
Bank Sta=4975.8,5042.8
XS Rating Curve= 0 ,0
Exp/Cntr=0.3,0.1

Type RM Length L Ch R = 1 ,33547   ,690,690,690
BEGIN DESCRIPTION:
HONDO CREEK 29.0
END DESCRIPTION:
XS GIS Cut Line= 3
      2400002.93     13165755.82      2399924.54      13165267.4
      2398965.72     13164423.16
#Sta/Elev= 30
    4258    61.8  4307.6   57.19  4322.6   57.14  4520.3   44.18  4591.2   41.25
  4718.9    38.9  4793.2   36.54  4828.4   32.59  4835.9   33.43  4842.5   31.85
  4864.3   30.03    4907   29.16  4927.9   30.27  4942.1   29.17    4963    30.8
  4984.8   26.61  4991.5   22.15  4998.8    19.8  5013.3    24.5  5027.5   32.89
  5034.2   32.31  5091.1   29.79  5133.8   31.93  5154.7   31.32    5204   32.59
  5438.3   31.81  5551.2   34.37  5636.9    38.6  5728.6   44.51  6030.2   60.58
#Mann= 5 ,-1 , 0
    4258     .05       0  4718.9      .1       0    4963     .07       0
  5034.2      .1       0  5636.9      .1       0
Bank Sta=4963,5027.5
XS Rating Curve= 0 ,0
Exp/Cntr=0.3,0.1

Type RM Length L Ch R = 1 ,32857   ,484,484,484
BEGIN DESCRIPTION:
HONDO CREEK 28.0
END DESCRIPTION:
XS GIS Cut Line= 3
      2400479.33     13164646.29      2400123.53     13164622.17
      2398995.92     13164163.89
#Sta/Elev= 30
  4314.1   71.25  4365.8   68.63    4456   66.71  4486.1   62.55  4496.1   63.13
  4536.2   59.04  4741.8   45.62  4749.2   44.01  4849.7   35.51  4856.3   33.97
  4940.5   30.81  4946.8   31.29  4957.6   28.53  4963.4   22.39  4968.8   23.79
    4979   19.12  4992.8   20.54  5016.9   20.01  5022.4   30.25  5054.8   29.02
  5065.1   29.84  5087.2   26.85    5124   28.71  5141.1   31.26  5162.7   31.24
  5184.3   34.12  5386.3   46.12  5439.9   47.83  5529.7   53.16  5887.9   69.87
#Mann= 3 ,-1 , 0
  4314.1      .1       0  4940.5     .07       0  5022.4      .1       0
Bank Sta=4946.8,5022.4
XS Rating Curve= 0 ,0
Exp/Cntr=0.3,0.1

Type RM Length L Ch R = 1 ,32373   ,519,519,519
BEGIN DESCRIPTION:
HONDO CREEK 27.0
END DESCRIPTION:
XS GIS Cut Line= 3
      2400557.67     13164139.75      2400171.77     13164031.21
      2399038.08     13164013.12
#Sta/Elev= 30
  4246.4   71.08    4371   64.96  4567.1   52.87  4589.1   52.45  4681.3   42.63
  4841.3   29.87  4891.3   27.89  4921.4   29.73  4941.4   29.53  4971.4   26.82
  4981.4   19.33  4991.1   18.68  5001.4   19.56  5021.4   28.75  5051.4   29.39
  5061.4   31.07  5071.4   30.69  5131.4   34.05  5151.4   38.72  5161.4    44.3
  5225.5   45.45  5311.4   45.13  5331.4   46.64  5351.4   50.26  5361.4   50.88
  5484.5   55.17  5611.4   60.18  5641.4   60.42  5651.4   62.61  5781.1   69.36
#Mann= 5 ,-1 , 0
  4246.4      .1       0  4941.4     .07       0  5021.4     .07       0
  5225.5     .05       0  5484.5      .1       0
Bank Sta=4941.4,5021.4
XS Rating Curve= 0 ,0
Exp/Cntr=0.3,0.1