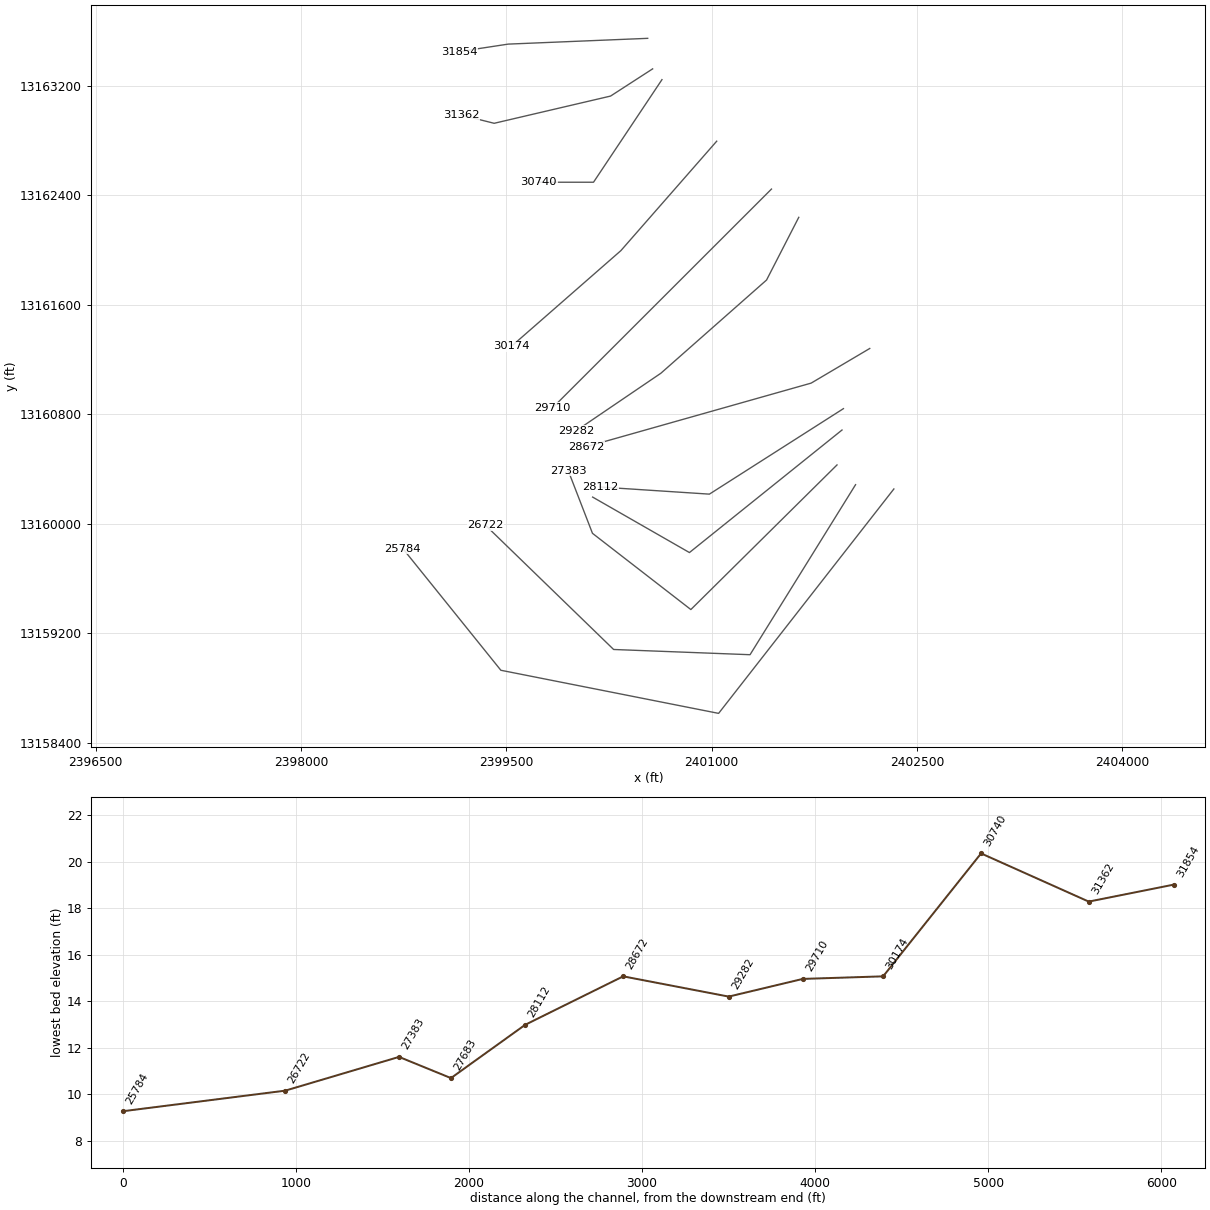
HEC-RAS study HONDO CREEK.prj: HONDO CREEK Base Level Engineering

--- HONDO CREEK.g01 (geometry) --- (continued)

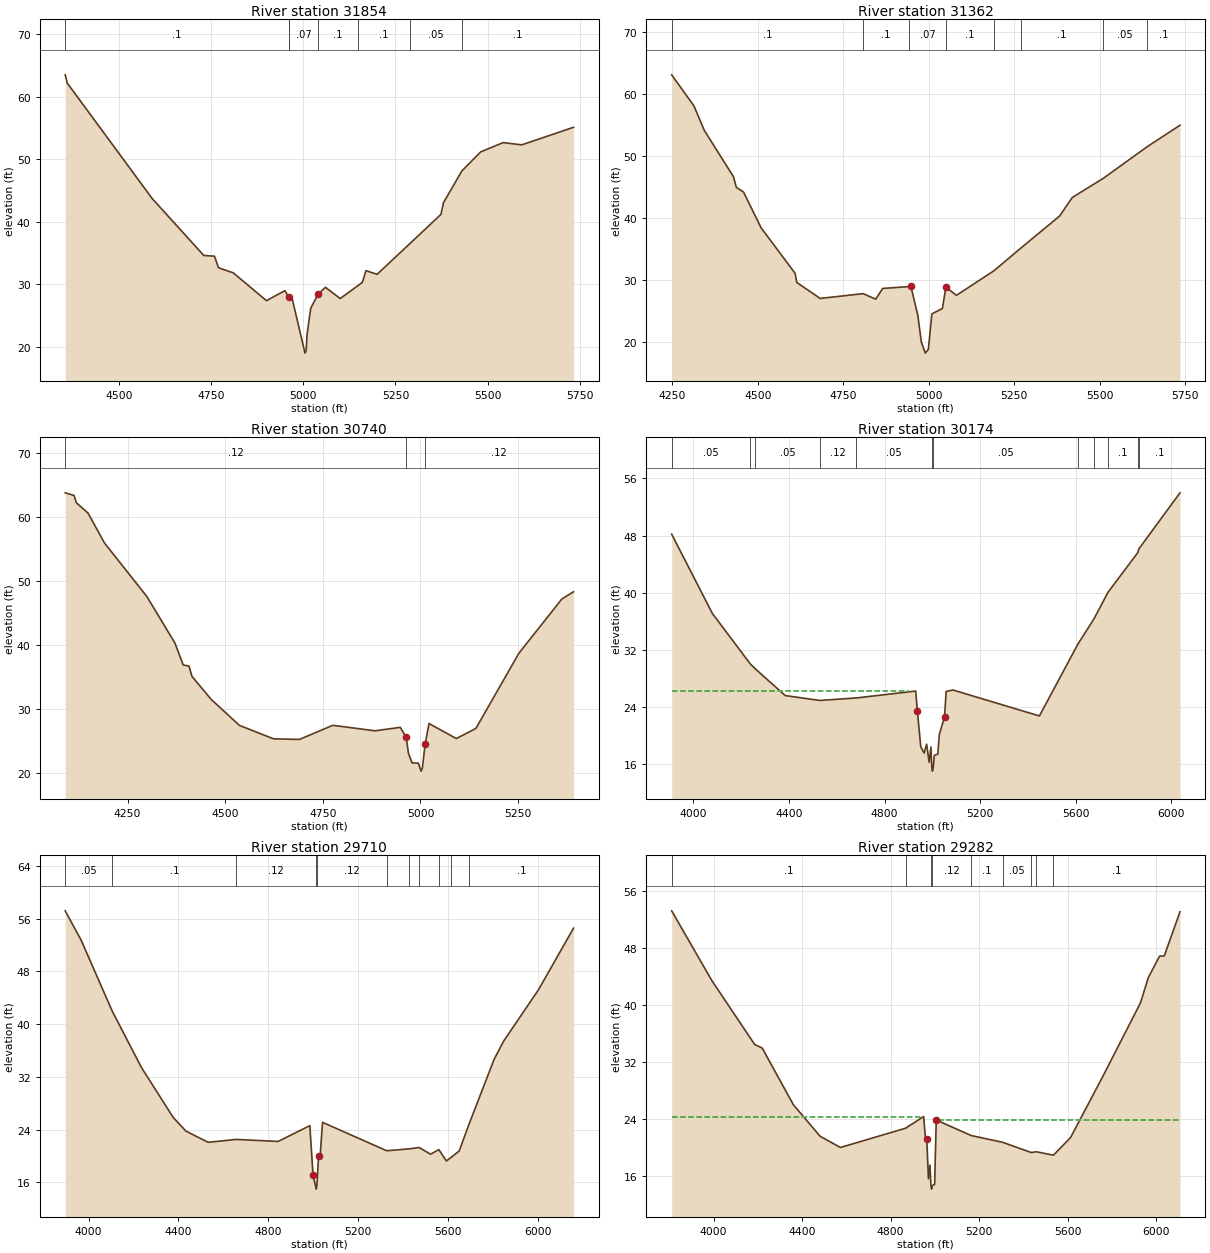
Type RM Length L Ch R = 1 ,31854   ,492,492,492
BEGIN DESCRIPTION:
HONDO CREEK 26.0
END DESCRIPTION:
XS GIS Cut Line= 3
      2400533.56      13163548.8      2399514.49     13163506.59
      2399158.75     13163452.33
#Sta/Elev= 30
  4353.6   63.52  4359.4   62.18  4589.6   43.74  4729.8   34.63  4758.9   34.51
  4769.8   32.66  4809.8   31.85  4899.9    27.4  4949.9      29    4960   28.04
    4970   27.65  5004.6   19.01  5007.8   19.51    5010   21.94    5020   26.18
    5040   28.43    5060   29.54  5100.1   27.74  5147.9   29.79  5160.1   30.33
  5170.1    32.2  5200.2   31.61  5290.8   36.62  5373.5    41.2  5380.4   43.07
  5430.3   48.15  5481.5    51.2  5542.4   52.68  5592.8   52.32  5733.4   55.13
#Mann= 7 ,-1 , 0
  4353.6      .1       0    4960     .12       0    4960     .07       0
    5040      .1       0  5147.9      .1       0  5290.8     .05       0
  5430.3      .1       0
Bank Sta=4960,5040
XS Rating Curve= 0 ,0
Exp/Cntr=0.3,0.1

Type RM Length L Ch R = 1 ,31362   ,622,622,622
BEGIN DESCRIPTION:
HONDO CREEK 25.0
END DESCRIPTION:
XS GIS Cut Line= 4
      2400569.75     13163325.68      2400262.22     13163126.69
      2399411.97      13162927.7      2399171.78     13162987.74
#Sta/Elev= 30
  4247.7   63.11  4312.8   58.11  4343.1   54.17  4428.8   46.67  4436.8   44.99
  4457.9   44.23  4509.3   38.47  4608.9   31.13  4613.7   29.66  4682.2   27.09
  4807.9   27.86  4844.6   26.97  4865.1    28.7  4942.3      29  4947.4   29.09
  4967.8   24.36  4978.1   20.07  4989.6   18.28  4998.6   18.89  5008.9    24.6
  5039.7   25.47    5050   28.92  5080.8   27.59  5190.3   31.54  5269.7   35.22
  5382.5   40.36  5419.7   43.35  5510.2   46.43  5638.8   51.53  5734.8   54.99
#Mann= 8 ,-1 , 0
  4247.7      .1       0  4807.9      .1       0  4942.3     .07       0
    5050      .1       0  5190.3     .05       0  5269.7      .1       0
  5510.2     .05       0  5638.8      .1       0
Bank Sta=4947.4,5050
XS Rating Curve= 0 ,0
Exp/Cntr=0.3,0.1

Type RM Length L Ch R = 1 ,30740   ,566,566,566
BEGIN DESCRIPTION:
HONDO CREEK 24.0
END DESCRIPTION:
XS GIS Cut Line= 3
      2400637.74     13163246.88      2400137.72     13162496.85
      2399737.74     13162496.85
#Sta/Elev= 30
  4090.4   63.84    4113   63.44    4119   62.29    4149   60.66  4191.1   55.99
  4299.2   47.66  4371.4   40.36  4392.4   36.95  4407.4   36.76  4414.9   35.16
  4464.5   31.54  4536.6   27.49  4623.7    25.4  4689.9    25.3  4775.5   27.51
  4883.7   26.65  4948.2   27.19  4963.3   25.67  4969.3   23.11  4978.3   21.64
  4994.3    21.6  5001.6   20.35  5004.8   20.85  5011.8   24.56  5021.8   27.79
  5091.8   25.44  5141.8   27.02  5251.8   38.76  5361.8   47.24  5391.8   48.38
#Mann= 3 , 0 , 0
  4090.4     .12       0  4963.3     .07       0  5011.8     .12       0
Bank Sta=4963.3,5011.8
XS Rating Curve= 0 ,0
Exp/Cntr=0.3,0.1

Type RM Length L Ch R = 1 ,30174   ,464,464,464
BEGIN DESCRIPTION:
HONDO CREEK 23.0
END DESCRIPTION:
XS GIS Cut Line= 3
      2401037.74     13162796.88      2400337.72     13161996.85
      2399537.69     13161296.83
#Sta/Elev= 30
  3909.6   48.19    4080    37.1  4238.4   30.06  4259.9   29.35  4384.7   25.63
  4529.4   24.95  4682.6    25.3  4930.4   26.26  4937.1   23.52  4951.3   18.49
  4965.5    17.6    4976   18.84  4986.4   16.32    4994   18.45  4997.6   15.57
  5000.4   15.07  5003.6   15.57  5008.2   17.29  5022.5   17.44  5029.1    20.2
    5051   22.68  5057.6   26.21  5086.1   26.41  5447.7   22.78  5608.8   32.83
  5676.9   36.41  5734.3   40.05  5859.5   45.63  5863.4   46.12  6035.7   53.97
#Mann= 12 ,-1 , 0
  3909.6     .05       0  4238.4      .1       0  4259.9     .05       0
  4529.4     .12       0  4682.6     .05       0  4997.6    .035       0
  5003.6     .05       0  5608.8      .1       0  5676.9     .05       0
  5734.3      .1       0  5859.5     .05       0  5863.4      .1       0
#XS Ineff= 2 , 0
       0 4899.43   26.27 5086.93       0   26.39
Permanent Ineff=
       T       T
Bank Sta=4937.1,5051
XS Rating Curve= 0 ,0
Exp/Cntr=0.3,0.1

Type RM Length L Ch R = 1 ,29710   ,428,428,428
BEGIN DESCRIPTION:
HONDO CREEK 22.0
END DESCRIPTION:
XS GIS Cut Line= 3
      2401437.75     13162446.88      2400637.72     13161646.85
      2399837.71     13160846.84
#Sta/Elev= 30
  3895.9   57.17  3966.6   52.74  4105.5   41.94  4235.3   33.41  4376.8   25.83
  4433.3   23.76  4532.3   22.06  4657.6    22.5  4843.5   22.19  4984.9   24.59
    4999   17.13  5010.2   15.46  5012.9   14.96  5016.2   15.46  5023.8   20.02
  5030.8   20.02  5041.4   25.09  5327.2   20.78  5424.4   21.06  5471.2   21.27
  5522.3   20.26  5559.2   20.95    5593   19.23  5615.1   19.81  5649.6   20.74
  5694.1   24.86  5805.1   34.64  5847.6   37.41  6003.1   45.22  6158.7   54.54
#Mann= 11 ,-1 , 0
  3895.9     .05       0  4105.5      .1       0  4657.6     .12       0
  5010.2     .07       0  5016.2     .12       0  5327.2     .05       0
  5424.4     .12       0  5471.2     .05       0  5559.2     .12       0
  5615.1     .05       0  5694.1      .1       0
#XS Ineff= 2 , 0
       0 4981.25   24.42 5047.73       0   24.84
Permanent Ineff=
       T       T
Bank Sta=4999,5023.8
XS Rating Curve= 0 ,0
Exp/Cntr=0.3,0.1

Type RM Length L Ch R = 1 ,29282   ,610,610,610
BEGIN DESCRIPTION:
HONDO CREEK 21.0
END DESCRIPTION:
XS GIS Cut Line= 4
      2401637.08     13162240.23      2401401.92     13161781.97
      2400630.06     13161100.56        2400009.     13160678.47
#Sta/Elev= 30
    3811   53.23  3992.4   43.45  4185.7   34.49  4219.9   33.98  4360.7   26.03
  4481.2   21.62  4573.2   20.04    4867   22.74  4948.9   24.38  4956.4   21.52
  4963.1   21.19  4970.6   15.64  4977.3   17.57  4981.9    14.7  4984.6    14.2
  4987.9    14.7  4998.6   14.86  5005.8   23.89  5164.3   21.71  5305.2   20.77
  5435.2   19.33  5458.3   19.44  5535.1   18.96  5612.4   21.43    5757   29.94
  5927.8    40.3  5963.7   43.88  6014.5   46.88  6035.6   46.91  6106.6    53.1
#Mann= 9 ,-1 , 0
    3811      .1       0    4867     .12       0  4981.9     .07       0
  4987.9     .12       0  5164.3      .1       0  5305.2     .05       0
  5435.2      .1       0  5458.3     .05       0  5535.1      .1       0
#XS Ineff= 2 , 0
       0 4945.45   24.36 5022.16       0   23.83
Permanent Ineff=
       T       T
Bank Sta=4963.1,5005.8
XS Rating Curve= 0 ,0
Exp/Cntr=0.3,0.1

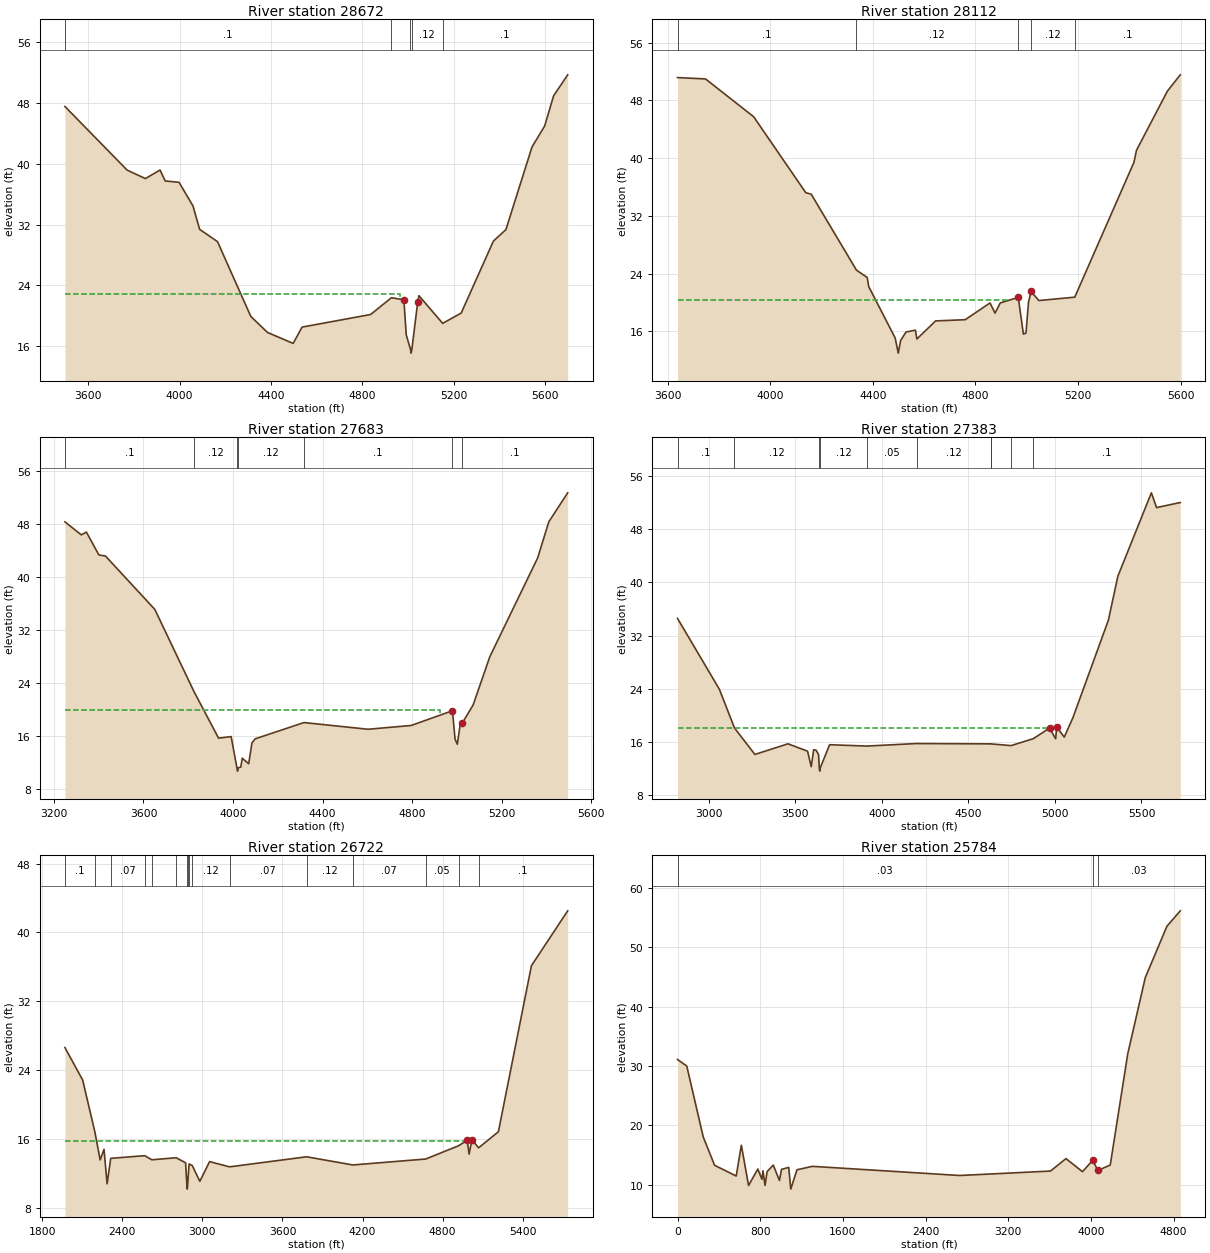
Type RM Length L Ch R = 1 ,28672   ,566,566,566
BEGIN DESCRIPTION:
HONDO CREEK 20.0
END DESCRIPTION:
XS GIS Cut Line= 3
      2402155.68     13161281.46      2401727.55      13161028.2
      2400087.34     13160563.87
#Sta/Elev= 30
    3498   47.56  3770.4   39.18  3850.4   38.06  3914.7   39.19  3937.1   37.75
  3997.9   37.57  4059.1   34.45  4087.9   31.38  4166.2   29.76  4312.3    19.9
  4385.4   17.79  4497.6   16.35  4536.8    18.5  4837.1   20.16  4928.1   22.37
  4982.6   22.09    4993   17.47  5011.5   15.57  5014.2   15.07  5017.5   15.57
  5043.2   21.81  5048.4   22.64  5152.6   18.99  5233.7   20.35  5374.7   29.83
  5429.5   31.34  5543.8   42.23  5599.2   44.99  5638.3   48.96  5700.1   51.73
#Mann= 5 ,-1 , 0
    3498      .1       0  4928.1     .12       0  5011.5     .07       0
  5017.5     .12       0  5152.6      .1       0
#XS Ineff= 2 , 0
       0 4967.05   22.91 5050.57       0   22.34
Permanent Ineff=
       T       T
Bank Sta=4982.6,5043.2
XS Rating Curve= 0 ,0
Exp/Cntr=0.3,0.1

Type RM Length L Ch R = 1 ,28112   ,429,429,429
BEGIN DESCRIPTION:
Mapping XS e9d0468e
END DESCRIPTION:
XS GIS Cut Line= 3
      2401963.42     13160841.57      2400984.26     13160216.57
      2400187.38     13160268.65
#Sta/Elev= 30
  3638.2   51.15  3747.5   50.96  3935.3   45.72  4138.4    35.2  4159.5      35
    4336   24.48  4377.8   23.47  4383.8    22.2    4487   15.08  4498.9   12.99
  4508.1   14.74  4529.3   15.92  4565.7   16.17  4571.6   14.95  4644.4   17.45
  4760.1   17.62  4856.5   19.94  4876.2   18.53  4896.6   19.94  4966.7   20.71
  4986.8   15.62  4996.8   15.77  5006.8   20.07  5016.8   21.54  5046.9   20.27
  5187.1   20.74  5417.7   39.41  5427.7   41.08    5548   49.26  5598.4   51.53
#Mann= 5 ,-1 , 0
  3638.2      .1       0    4336     .12       0  4966.7     .07       0
  5016.8     .12       0  5187.1      .1       0
#XS Ineff= 2 , 0
       0 4924.72   20.37               0
Permanent Ineff=
       T       F
Bank Sta=4966.7,5016.8
XS Rating Curve= 0 ,0
Exp/Cntr=0.3,0.1

Type RM Length L Ch R = 1 ,27683   ,300,300,300
BEGIN DESCRIPTION:
Mapping XS c5de878c
END DESCRIPTION:
XS GIS Cut Line= 3
      2401953.04     13160685.34      2400838.42     13159789.49
      2400131.36     13160195.01
#Sta/Elev= 30
  3249.5   48.38  3322.9   46.41  3345.3   46.84  3401.3   43.37  3430.1   43.23
  3650.9   35.15    3826   22.71  3935.7   15.68  3991.7   15.92  4017.5    11.2
  4020.2    10.7  4023.5    11.2  4034.9   11.31  4041.3   12.65  4070.1   11.82
  4084.5   14.94  4098.9   15.58  4316.9   18.04  4603.4   17.03  4795.6    17.6
    4980   19.83  4991.6   15.54  5001.6   14.76  5014.6   17.78  5023.2   17.93
  5072.3    20.7  5146.9      28  5360.5   42.93  5410.1   48.38  5494.6   52.77
#Mann= 7 ,-1 , 0
  3249.5      .1       0    3826     .12       0  4017.5     .07       0
  4023.5     .12       0  4316.9      .1       0    4980     .05       0
  5023.2      .1       0
#XS Ineff= 2 , 0
       0 4926.14   19.89               0
Permanent Ineff=
       T       F
Bank Sta=4980,5023.2
XS Rating Curve= 0 ,0
Exp/Cntr=0.3,0.1

Type RM Length L Ch R = 1 ,27383   ,658,658,658
BEGIN DESCRIPTION:
Mapping XS 9f20ca51
END DESCRIPTION:
XS GIS Cut Line= 4
      2401916.54     13160430.11      2400848.84     13159372.82
      2400130.09     13159930.11      2399952.99     13160388.48
#Sta/Elev= 30
  2820.7   34.58  3062.6   23.92  3149.8    18.1  3267.7   14.12  3458.6   15.72
  3571.7   14.61    3593   12.28  3607.1   14.83  3621.2   14.75  3635.3   14.11
  3639.4   12.11  3642.2   11.61  3645.4   12.11    3699   15.58  3915.1   15.38
  4201.2   15.76  4631.7   15.71  4631.9    15.7  4747.6   15.45  4876.2    16.5
  4969.1   18.08  5004.4   16.48  5010.8   18.22  5054.2   16.73    5104   19.63
  5309.2   34.33  5363.8   40.93  5557.4   53.47  5587.3   51.25  5724.2   52.01
#Mann= 10 ,-1 , 0
  2820.7      .1       0  3149.8     .12       0  3639.4     .07       0
  3645.4     .12       0  3915.1     .05       0  4201.2     .12       0
  4631.7     .05       0  4631.9      .1       0  4747.6     .05       0
  4876.2      .1       0
#XS Ineff= 2 , 0
       0 4962.45   18.11 5013.87       0   18.04
Permanent Ineff=
       T       T
Bank Sta=4969.1,5010.8
XS Rating Curve= 0 ,0
Exp/Cntr=0.3,0.1

Type RM Length L Ch R = 1 ,26722   ,938,938,938
BEGIN DESCRIPTION:
Mapping XS b4b53805
END DESCRIPTION:
XS GIS Cut Line= 4
      2402052.07     13160285.75      2401281.21     13159042.66
      2400284.69     13159080.85      2399347.18     13159990.58
#Sta/Elev= 30
  1970.3   26.62  2103.1   22.85  2195.1   16.78  2234.2   13.56  2263.2   14.79
  2286.2   10.78  2313.5   13.74  2568.6   14.05  2621.6   13.57  2803.6   13.81
  2874.5   13.22  2883.8   10.66  2886.6   10.16  2889.8   10.66  2900.3   13.09
  2924.5   12.89  2980.9   11.07    3054   13.36  3203.2   12.75  3780.8   13.92
  4126.6   12.97  4673.1   13.66  4918.6    15.2  4983.9   15.83    4998   14.23
  5019.3   15.92  5068.9   14.96  5217.4   16.83  5464.9   36.14  5736.6   42.52
#Mann= 16 ,-1 , 0
  1970.3      .1       0  2195.1     .12       0  2313.5     .07       0
  2568.6     .12       0  2621.6     .07       0  2803.6     .12       0
  2883.8     .07       0  2889.8     .12       0  2900.3     .07       0
  2924.5     .12       0  3203.2     .07       0  3780.8     .12       0
  4126.6     .07       0  4673.1     .05       0  4918.6     .07       0
  5068.9      .1       0
#XS Ineff= 2 , 0
       0 4959.52    15.8               0
Permanent Ineff=
       T       F
Bank Sta=4983.9,5019.3
XS Rating Curve= 0 ,0
Exp/Cntr=0.3,0.1

Type RM Length L Ch R = 1 ,25784   ,0,0,0
BEGIN DESCRIPTION:
HONDO CREEK 1.0
END DESCRIPTION:
XS GIS Cut Line= 4
     2402331.924      13160254.4     2401051.542    13158613.775
       2399460.9     13158928.94      2398744.78     13159818.67
#Sta/Elev= 30
       0 31.112689.68053 30.0143249.1126 18.0664358.7221 13.2941567.9767 11.4843
617.7992 16.6743687.5507  9.8881777.2312 12.6608817.0892 10.9362827.0538 12.3691
846.9827   9.903866.9117  12.223926.6988 13.3255986.4858 10.73691006.415 12.6057
1076.166 12.93821096.095  9.27671155.882 12.5366 1305.35 13.11612731.197  11.572
3609.364  12.3223758.989 14.42023918.408 12.21644018.045 14.13294067.863 12.4234
4187.427 13.3416 4356.81 32.07844526.192 44.89784735.429 53.55094864.957 56.1594
#Mann= 3 , 0 , 0
       0     .03       04018.045     .03       04067.863     .03       0
Bank Sta=4018.045,4067.863
XS Rating Curve= 0 ,0
Exp/Cntr=0.3,0.1

Chan Stop Cuts=-1
Use User Specified Reach Order=0
Composite Channel Slope=5

--- HONDO CREEK.g02 (geometry) ---

Geom Title=Dummy
Program Version=4.10

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
River Reach=HONDO CREEK     ,Reach-1

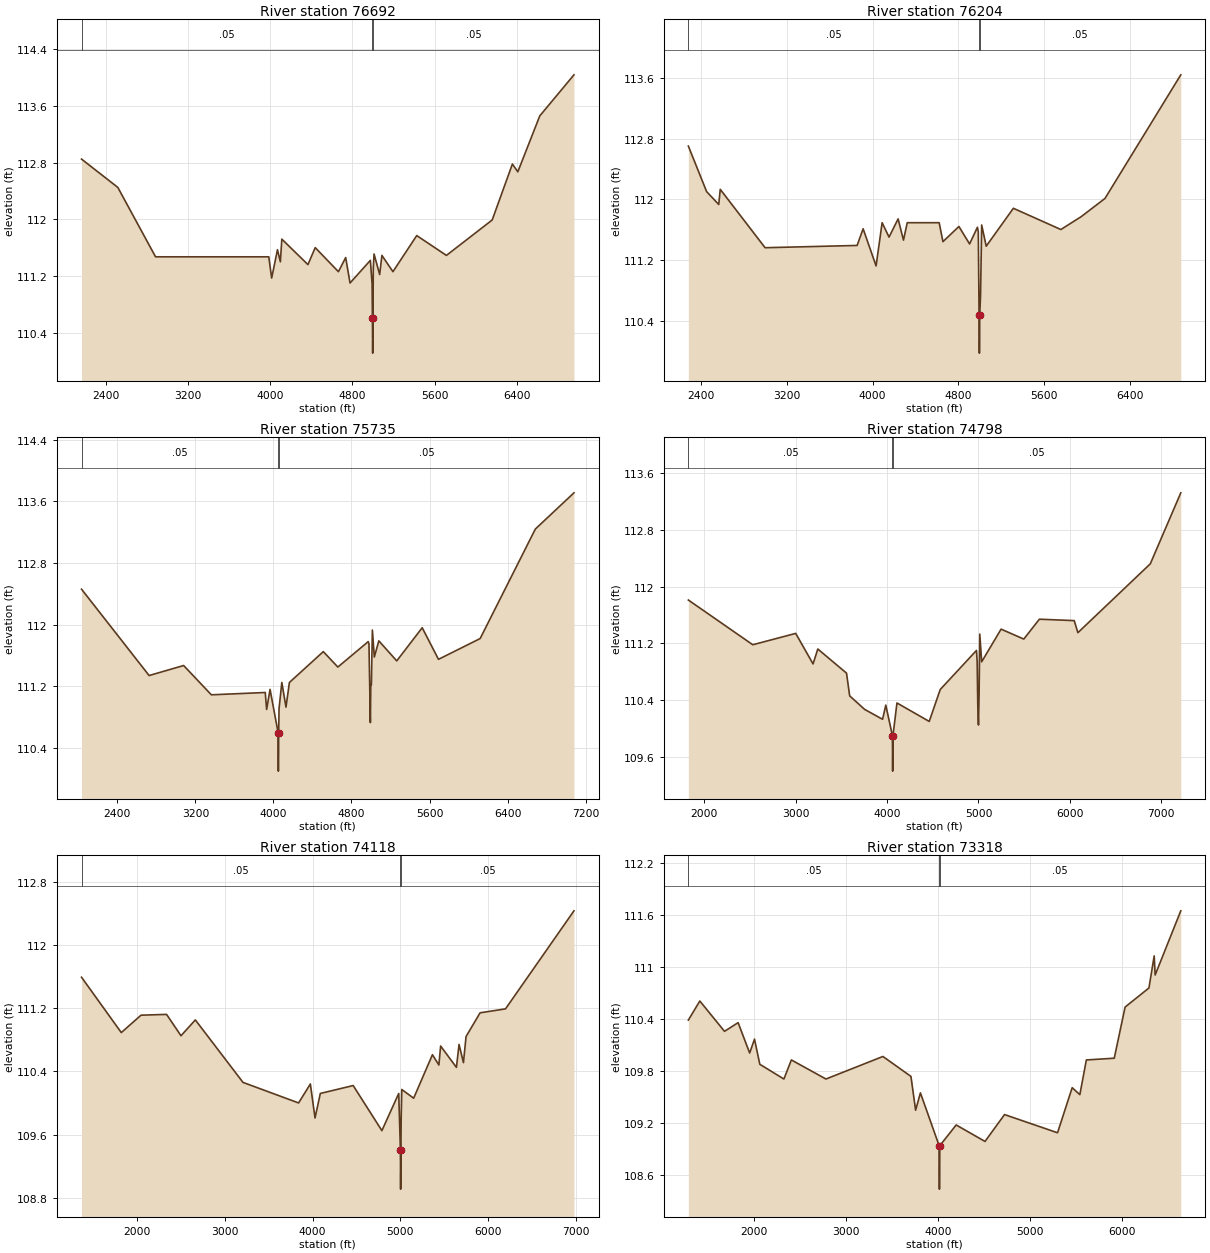
Type RM Length L Ch R = 1 ,76692   ,488,488,488
BEGIN DESCRIPTION:
HONDO CREEK 100.0
END DESCRIPTION:
XS GIS Cut Line= 3
      2379137.73     13192496.87      2377137.72     13190496.85
      2375337.74     13189696.86
#Sta/Elev= 30
  2160.1  112.85  2513.7  112.45  2881.4  111.47  3984.5  111.47  4012.7  111.17
  4069.3  111.57  4097.6   111.4  4111.7  111.72  4366.3  111.36    4437   111.6
  4663.3  111.26    4734  111.46  4776.4   111.1  4974.4  111.42  4991.3  111.09
  4994.4  110.61  4997.2  110.11  5000.4  110.61  5002.9  111.31  5010.4  111.51
  5065.1  111.22    5087  111.49  5194.4  111.26  5426.3  111.77  5715.6  111.49
  6161.5  111.99  6358.5  112.78  6411.2  112.67  6625.2  113.46  6958.3  114.04
#Mann= 3 ,-1 , 0
  2160.1     .05       0  4994.4    .035       0  5000.4     .05       0
Bank Sta=4994.4,5000.4
XS Rating Curve= 0 ,0
Exp/Cntr=0.3,0.1

Type RM Length L Ch R = 1 ,76204   ,469,469,469
BEGIN DESCRIPTION:
HONDO CREEK 99.0
END DESCRIPTION:
XS GIS Cut Line= 3
      2379287.74     13192146.88      2377487.72     13190146.85
      2375687.74     13189546.86
#Sta/Elev= 30
  2283.9   112.7    2454   112.1  2566.8  111.93    2581  112.13  2998.8  111.36
  3856.1  111.39  3912.2  111.61  4032.9  111.12  4089.3  111.69  4153.6   111.5
  4238.1  111.74  4288.1  111.46  4323.3  111.69  4620.7  111.69  4655.9  111.44
  4804.6  111.64    4904  111.41  4977.3  111.63  4985.2  111.57  4992.7  110.47
  4995.5  109.97  4998.7  110.47  5006.3  110.74  5016.8  111.66    5059  111.38
    5312  111.88  5754.7   111.6  5944.4  111.77  6165.8  112.01    6872  113.64
#Mann= 3 ,-1 , 0
  2283.9     .05       0  4992.7    .035       0  4998.7     .05       0
Bank Sta=4992.7,4998.7
XS Rating Curve= 0 ,0
Exp/Cntr=0.3,0.1

Type RM Length L Ch R = 1 ,75735   ,937,937,937
BEGIN DESCRIPTION:
HONDO CREEK 98.0
END DESCRIPTION:
XS GIS Cut Line= 3
      2379731.45     13192029.96      2377780.76     13189794.77
      2375787.72     13189196.85
#Sta/Elev= 30
  2033.3  112.46    2726  111.34    3080  111.47  3363.9  111.09  3916.4  111.12
  3930.6   110.9  3965.7  111.16  4048.2   110.6  4050.9   110.1  4054.2   110.6
  4057.8  110.91  4086.3  111.25    4129  110.93  4164.1  111.25  4511.6  111.65
  4660.6  111.45    4972  111.78  4979.6  111.75  4993.8  110.73  4998.5  111.22
  5004.2  111.22  5014.5  111.93  5034.5  111.58  5080.6  111.79  5264.2  111.53
  5525.2  111.96  5692.2  111.55  6119.4  111.82  6684.9  113.24  7080.8  113.71
#Mann= 3 ,-1 , 0
  2033.3     .05       0  4048.2    .035       0  4054.2     .05       0
Bank Sta=4048.2,4054.2
XS Rating Curve= 0 ,0
Exp/Cntr=0.3,0.1

Type RM Length L Ch R = 1 ,74798   ,680,680,680
BEGIN DESCRIPTION:
HONDO CREEK 97.0
END DESCRIPTION:
XS GIS Cut Line= 4
      2379941.85      13191841.9       2378943.6     13189574.14
      2378205.76      13188923.1       2376285.2     13188771.19
#Sta/Elev= 30
  1825.3  111.81  2530.1  111.18  2999.9  111.34  3189.7  110.91  3241.8  111.12
  3556.1  110.78  3590.4  110.46  3753.7  110.27  3950.4  110.13  3985.6  110.33
  4058.1   109.9  4060.8   109.4  4064.1   109.9  4107.8  110.36  4460.9   110.1
  4581.4  110.55  4977.9   111.1  4985.5  110.94  4992.2  110.33  4999.7  110.05
  5006.4  110.47    5014  111.33  5034.8  110.94  5247.3   111.4  5495.7  111.26
  5666.3  111.54  6047.5  111.52  6087.6  111.35    6880  112.32  7213.6  113.32
#Mann= 3 ,-1 , 0
  1825.3     .05       0  4058.1    .035       0  4064.1     .05       0
Bank Sta=4058.1,4064.1
XS Rating Curve= 0 ,0
Exp/Cntr=0.3,0.1

Type RM Length L Ch R = 1 ,74118   ,800,800,800
BEGIN DESCRIPTION:
HONDO CREEK 96.0
END DESCRIPTION:
XS GIS Cut Line= 4
      2380093.78     13191852.81      2379421.04      13188901.4
      2378542.13     13188434.82      2376947.05     13188402.27
#Sta/Elev= 30
  1363.6  111.59  1817.1  110.89  2042.4  111.11  2333.8  111.12  2498.2  110.85
    2662  111.05  3205.6  110.26  3839.8     110    3974  110.24  4027.2  109.81
  4087.7  110.12  4462.4  110.22    4790  109.65  4982.2  110.12  5001.2  109.41
    5004  108.91  5007.2  109.41  5009.9   109.8  5017.2  110.17  5152.4  110.06
  5366.6  110.61  5440.2  110.48  5460.2  110.72  5640.3  110.45  5670.3  110.74
  5720.3  110.51  5750.3  110.84  5910.3  111.14  6200.4  111.19  6981.2  112.43
#Mann= 3 ,-1 , 0
  1363.6     .05       0  5001.2    .035       0  5007.2     .05       0
Bank Sta=5001.2,5007.2
XS Rating Curve= 0 ,0
Exp/Cntr=0.3,0.1

Type RM Length L Ch R = 1 ,73318   ,1956,1956,1956
BEGIN DESCRIPTION:
HONDO CREEK 95.0
END DESCRIPTION:
XS GIS Cut Line= 3
      2380614.61     13190919.64      2380115.48     13188239.51
      2377512.02     13187827.29
#Sta/Elev= 30
    1282  110.39  1406.9  110.61  1675.6  110.26  1823.9  110.36  1949.4  110.01
  2002.2  110.17    2060  109.88  2322.4  109.71  2403.7  109.93  2780.1  109.71
  3400.6  109.97  3705.8  109.74  3756.6  109.35  3808.7  109.55  4013.1  108.94
  4015.8  108.44  4019.1  108.94  4198.3  109.18  4512.2  108.99  4724.8   109.3
  5301.9  109.09  5461.4  109.61  5544.9  109.53  5615.7  109.93  5919.5  109.95
  6037.7  110.54  6297.2  110.76  6354.5  111.13    6365  110.91  6644.1  111.65
#Mann= 3 ,-1 , 0
    1282     .05       0  4013.1    .035       0  4019.1     .05       0
Bank Sta=4013.1,4019.1
XS Rating Curve= 0 ,0
Exp/Cntr=0.3,0.1

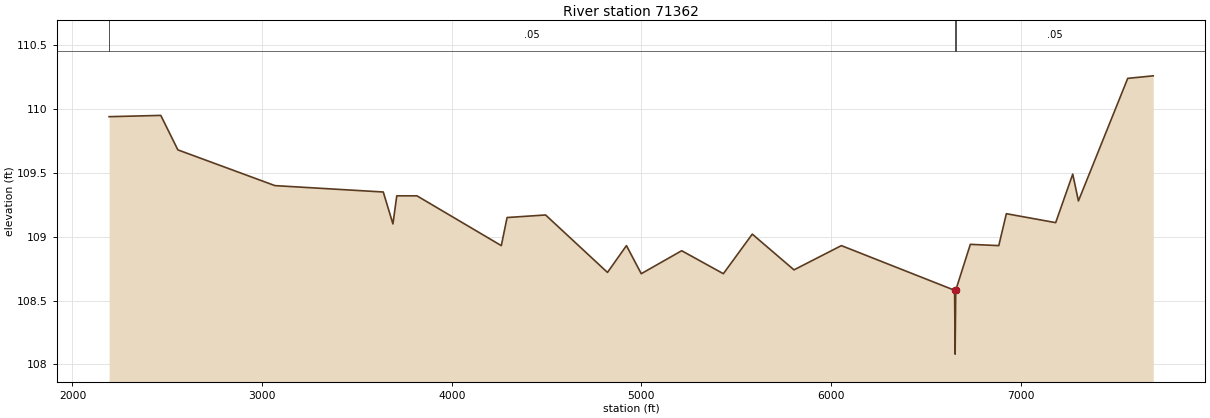
Type RM Length L Ch R = 1 ,71362   ,791,791,791
BEGIN DESCRIPTION:
HONDO CREEK 94.0
END DESCRIPTION:
XS GIS Cut Line= 4
      2381395.52     13190023.86      2380954.91     13187853.43
      2380212.72     13186971.85      2378073.32     13187001.04
#Sta/Elev= 30
  2193.2  109.94  2465.7  109.95  2555.8  109.68  3067.7   109.4  3639.1  109.35
  3690.1   109.1  3710.3  109.32  3816.7  109.32  4261.6  108.93  4292.2  109.15
  4495.2  109.17  4821.7  108.72  4921.7  108.93  4999.8  108.71    5213  108.89
  5432.8  108.71  5585.3  109.02  5805.3  108.74  6055.3  108.93  6652.4  108.58
  6655.2  108.08  6658.4  108.58  6735.4  108.94  6885.4  108.93  6925.4  109.18
  7185.5  109.11  7275.5  109.49  7305.5  109.28  7565.5  110.24  7699.9  110.26
#Mann= 3 ,-1 , 0
  2193.2     .05       0  6652.4    .035       0  6658.4     .05       0
Bank Sta=6652.4,6658.4
XS Rating Curve= 0 ,0
Exp/Cntr=0.3,0.1