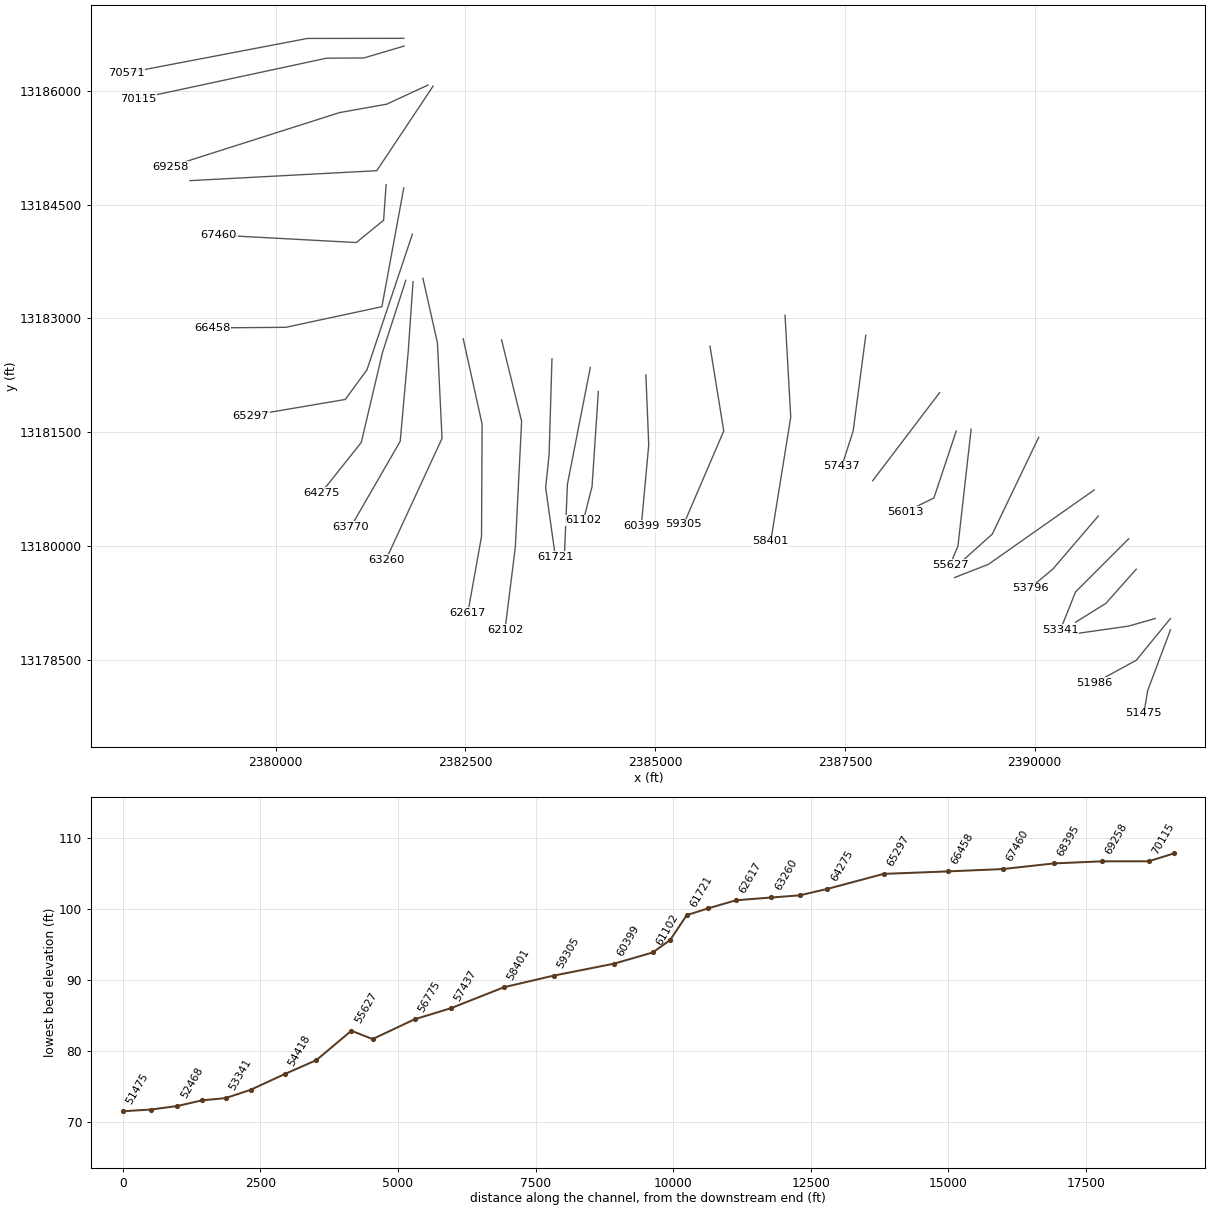
HEC-RAS study HONDO CREEK.prj: HONDO CREEK Base Level Engineering

--- HONDO CREEK.g02 (geometry) --- (continued)

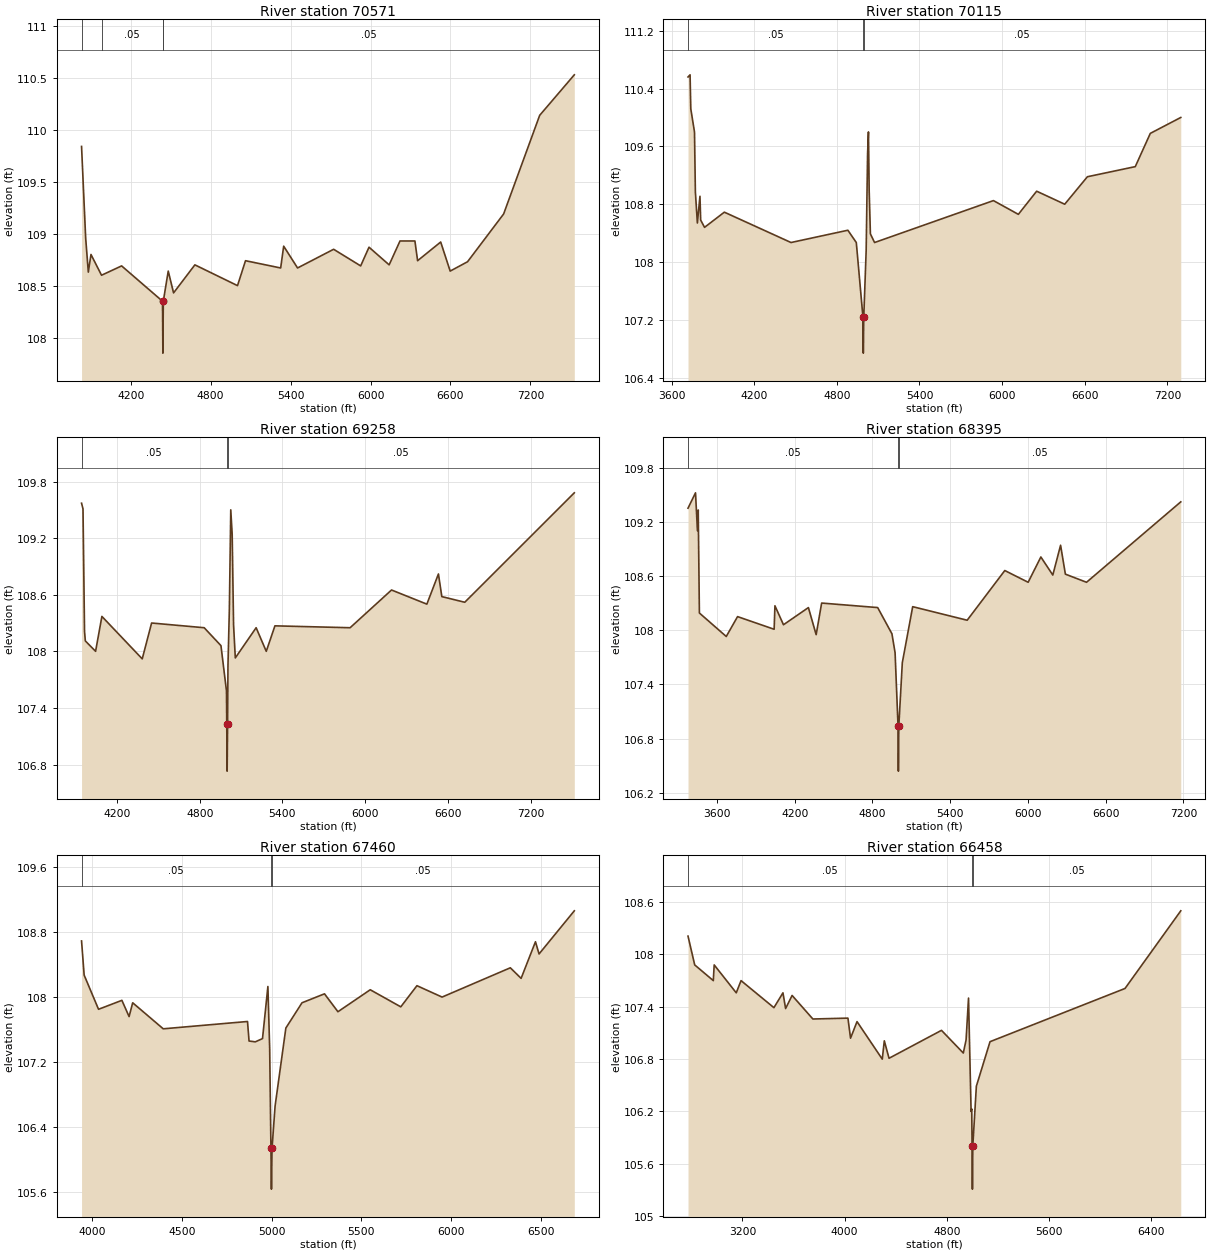
Type RM Length L Ch R = 1 ,70571   ,456,456,456
BEGIN DESCRIPTION:
HONDO CREEK 93.0
END DESCRIPTION:
XS GIS Cut Line= 3
      2381688.49     13186689.27       2380419.3     13186687.86
       2378032.4     13186232.18
#Sta/Elev= 30
  3830.6  109.84  3861.4  108.96  3881.4  108.63  3901.4   108.8  3980.6   108.6
  4131.4  108.69  4438.4  108.35  4441.1  107.85  4444.4  108.35  4481.4  108.64
  4521.4  108.43  4681.4   108.7  5001.4   108.5  5061.4  108.74  5325.4  108.67
    5348  108.88  5452.2  108.67    5723  108.85    5926  108.69  5988.6  108.87
  6139.8   108.7  6221.3  108.93  6333.2  108.93  6353.4  108.74  6526.7  108.92
  6597.9  108.64  6728.4  108.73  6999.2  109.19  7269.9  110.14  7529.8  110.53
#Mann= 4 ,-1 , 0
  3830.6     .08       0  3980.6     .05       0  4438.4    .035       0
  4444.4     .05       0
Bank Sta=4438.4,4444.4
XS Rating Curve= 0 ,0
Exp/Cntr=0.3,0.1

Type RM Length L Ch R = 1 ,70115   ,857,857,857
BEGIN DESCRIPTION:
HONDO CREEK 92.0
END DESCRIPTION:
XS GIS Cut Line= 4
      2381692.85     13186587.27      2381162.66     13186430.91
      2380668.87     13186427.44      2378194.92     13185895.76
#Sta/Elev= 30
  3719.8  110.56  3734.7  110.59  3739.9  110.12  3766.8   109.8  3773.2  108.97
  3787.7  108.54  3806.5  108.91  3811.7  108.58  3839.8  108.48  3983.5  108.69
  4467.5  108.27  4880.1  108.44  4941.4  108.27  4989.6  107.24  4992.3  106.74
  4995.6  107.24    5013  108.16  5023.3   109.5  5029.6   109.8  5034.8  108.99
  5043.7  108.39  5073.9  108.27  5936.9  108.85  6117.7  108.66  6250.6  108.98
  6454.4   108.8  6618.9  109.18  6966.6  109.32  7075.7  109.78  7296.8     110
#Mann= 3 ,-1 , 0
  3719.8     .05       0  4989.6    .035       0  4995.6     .05       0
Bank Sta=4989.6,4995.6
XS Rating Curve= 0 ,0
Exp/Cntr=0.3,0.1

Type RM Length L Ch R = 1 ,69258   ,863,863,863
BEGIN DESCRIPTION:
HONDO CREEK 91.0
END DESCRIPTION:
XS GIS Cut Line= 4
      2382007.29     13186073.53      2381462.72     13185821.85
      2380841.76     13185711.13      2378608.65      13184999.6
#Sta/Elev= 30
  3942.9  109.57  3953.4  109.51  3964.5  108.21  3970.4  108.11  4044.7     108
  4090.5  108.37  4383.1  107.92  4451.1   108.3  4832.5  108.25  4954.2  108.06
  4994.2  107.58  4996.2  107.23    4999  106.73  5002.2  107.23    5005  107.85
  5015.1  108.45  5025.3   109.5  5035.5  109.24  5045.6  108.28  5058.2  107.93
  5209.3  108.25  5282.8     108  5345.7  108.27    5891  108.25  6191.5  108.65
  6447.7   108.5  6531.7  108.82  6556.3  108.58  6722.6  108.52  7517.3  109.68
#Mann= 3 ,-1 , 0
  3942.9     .05       0  4996.2    .035       0  5002.2     .05       0
Bank Sta=4996.2,5002.2
XS Rating Curve= 0 ,0
Exp/Cntr=0.3,0.1

Type RM Length L Ch R = 1 ,68395   ,935,935,935
BEGIN DESCRIPTION:
HONDO CREEK 90.0
END DESCRIPTION:
XS GIS Cut Line= 3
       2382074.6     13186060.18      2381332.42      13184945.6
      2378871.28     13184814.61
#Sta/Elev= 30
    3376  109.35  3433.8  109.52  3448.8   109.1  3454.8  109.33  3463.8  108.19
  3671.2  107.93  3758.4  108.15  4040.8  108.01  4046.9  108.27  4112.9  108.06
  4305.3  108.25  4365.2  107.95  4407.5   108.3    4840  108.25  4950.1  107.96
  4974.4  107.75  4997.2  106.94  4999.9  106.44  5003.2  106.94  5030.2  107.64
  5110.3  108.26  5530.9  108.11  5821.3  108.66  6001.6  108.53  6099.7  108.81
  6191.9  108.61  6251.9  108.94  6288.9  108.62  6452.2  108.53  7179.7  109.42
#Mann= 3 ,-1 , 0
    3376     .05       0  4997.2    .035       0  5003.2     .05       0
Bank Sta=4997.2,5003.2
XS Rating Curve= 0 ,0
Exp/Cntr=0.3,0.1

Type RM Length L Ch R = 1 ,67460   ,1002,1002,1002
BEGIN DESCRIPTION:
HONDO CREEK 89.0
END DESCRIPTION:
XS GIS Cut Line= 4
      2381455.47     13184761.35      2381422.59     13184292.99
      2381062.72     13183999.21      2379251.41     13184096.79
#Sta/Elev= 30
  3940.2  108.69  3954.7  108.27  4034.9  107.85  4165.2  107.96  4205.3  107.76
  4225.4  107.93  4395.8  107.61  4865.7   107.7  4874.3  107.46  4909.3  107.45
  4949.4  107.49  4979.4  108.13  4989.4  107.36  4996.4  106.14  4999.2  105.64
  5002.4  106.14  5019.5  106.66  5079.6  107.62  5169.7  107.93    5295  108.04
    5370  107.82  5550.2  108.09  5720.5  107.88  5810.6  108.14  5950.8     108
  6331.4  108.36  6391.5  108.23  6471.6  108.68  6491.6  108.53  6688.2  109.06
#Mann= 3 ,-1 , 0
  3940.2     .05       0  4996.4    .035       0  5002.4     .05       0
Bank Sta=4996.4,5002.4
XS Rating Curve= 0 ,0
Exp/Cntr=0.3,0.1

Type RM Length L Ch R = 1 ,66458   ,1161,1161,1161
BEGIN DESCRIPTION:
HONDO CREEK 88.0
END DESCRIPTION:
XS GIS Cut Line= 4
      2381688.33     13184718.34      2381399.96     13183153.95
      2380132.69     13182882.39      2379161.11     13182874.85
#Sta/Elev= 30
    2774  108.21  2826.4  107.88  2972.1   107.7  2978.9  107.88  3151.7  107.56
  3189.2   107.7  3446.6  107.39  3517.4  107.56  3538.1  107.38    3589  107.53
  3751.7  107.26  4026.2  107.27  4046.6  107.04  4097.4  107.23    4295   106.8
    4311  107.01    4348  106.81  4758.7  107.13  4929.5  106.87  4951.3  107.02
  4970.4   107.5  4990.5   106.2  4995.6  106.23  4998.1  105.81  5000.9  105.31
  5004.1  105.81  5031.8  106.49  5138.8     107  6195.8  107.61  6632.4   108.5
#Mann= 3 ,-1 , 0
    2774     .05       0  4998.1    .035       0  5004.1     .05       0
Bank Sta=4998.1,5004.1
XS Rating Curve= 0 ,0
Exp/Cntr=0.3,0.1

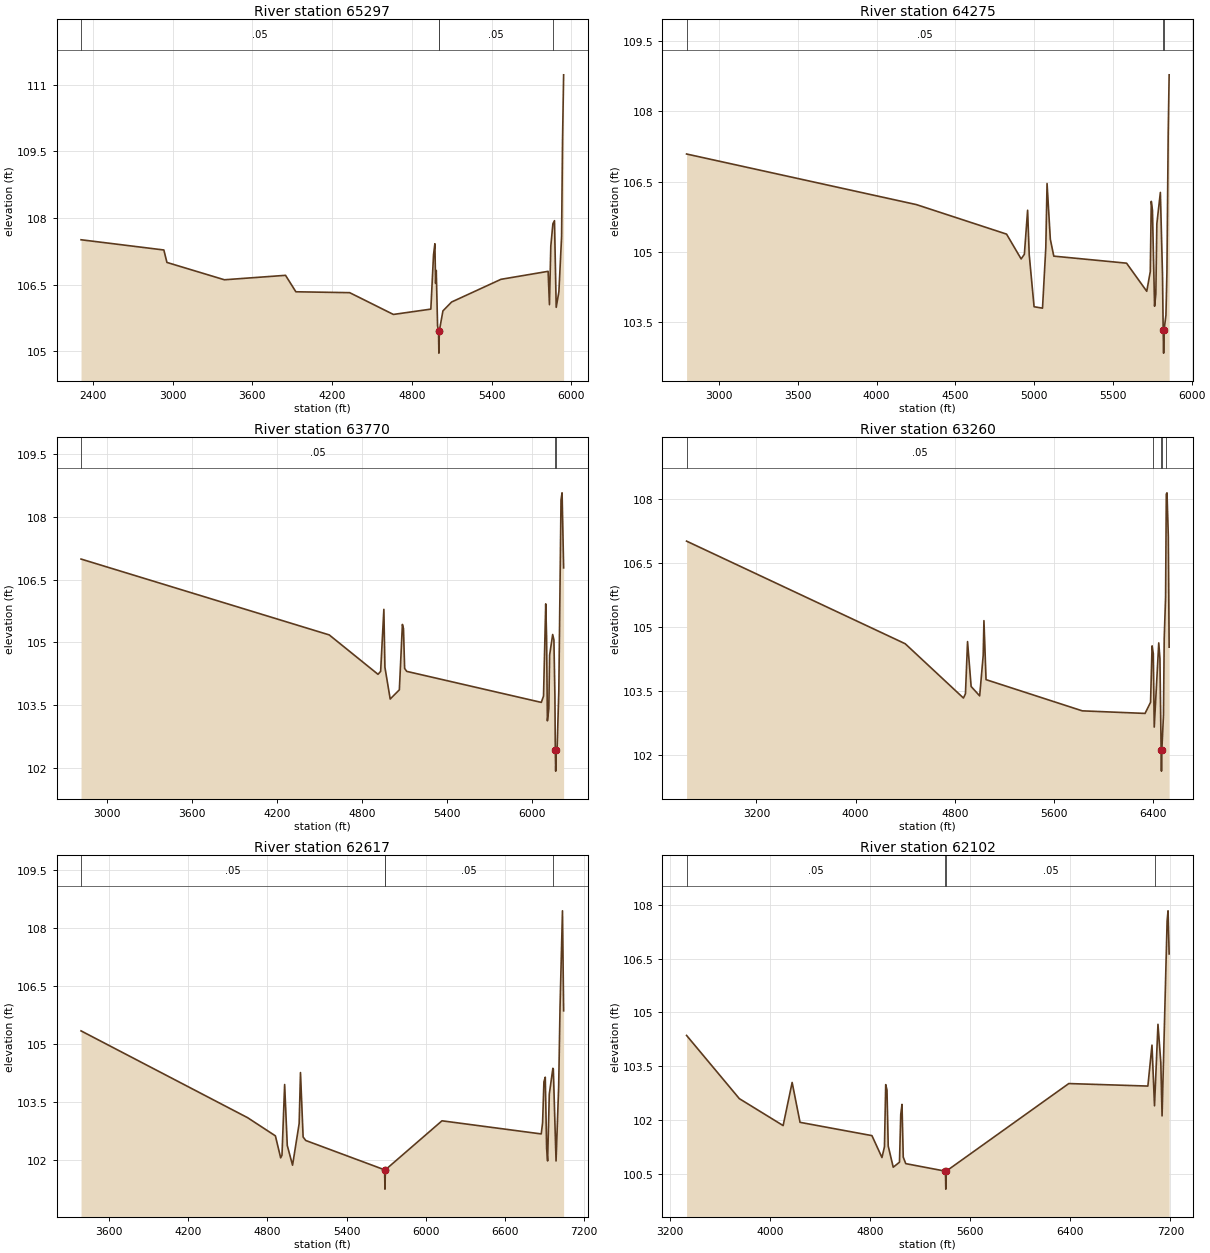
Type RM Length L Ch R = 1 ,65297   ,1022,1022,1022
BEGIN DESCRIPTION:
HONDO CREEK 87.0
END DESCRIPTION:
XS GIS Cut Line= 5
      2381801.19     13184109.76       2381793.8     13184086.34
      2381203.84     13182324.18      2380917.19     13181931.93
      2379672.67     13181720.74
#Sta/Elev= 30
    2311  107.51  2934.1  107.28  2957.2     107  3389.6  106.61  3849.6  106.71
  3927.4  106.34  4332.2  106.32  4661.2  105.83  4942.9  105.95  4963.1  107.17
  4973.3  107.42  4978.7  106.53  4983.7  106.82  4993.6  105.57  5000.7  105.46
  5003.5  104.96  5006.7  105.46  5033.9  105.91  5099.3  106.11  5470.3  106.62
  5825.3   106.8  5835.4  106.05  5845.6  107.37  5861.3  107.87  5873.2  107.94
  5886.2  105.99  5906.4  106.34  5926.7  107.58  5933.6  109.69    5942  111.22
#Mann= 4 ,-1 , 0
    2311     .05       0  5000.7    .035       0  5006.7     .05       0
  5861.3     .08       0
Bank Sta=5000.7,5006.7
XS Rating Curve= 0 ,0
Exp/Cntr=0.3,0.1

Type RM Length L Ch R = 1 ,64275   ,505,505,505
BEGIN DESCRIPTION:
HONDO CREEK 86.0
END DESCRIPTION:
XS GIS Cut Line= 4
      2381714.79     13183501.96      2381407.51     13182550.48
       2381128.4     13181366.18      2380601.57     13180703.88
#Sta/Elev= 30
  2794.2  107.09  4252.9  106.01  4825.2  105.38  4917.7  104.85  4938.2  104.95
  4958.8  105.89    4969  104.94  4999.8  103.83  5053.4   103.8  5074.2  105.09
  5082.2  106.46    5103  105.27    5125  104.91  5586.8  104.76  5714.9  104.16
  5737.4  104.58  5743.7  106.08  5751.1  105.89  5764.6  103.84  5772.6   104.1
    5779   105.6  5801.4  106.27    5815   104.5  5819.2  103.34    5822  102.84
  5825.2  103.34  5836.7  103.65    5843  104.57  5851.1  107.53  5857.1  108.78
#Mann= 3 ,-1 , 0
  2794.2     .05       0  5819.2    .035       0  5825.2     .05       0
Bank Sta=5819.2,5825.2
XS Rating Curve= 0 ,0
Exp/Cntr=0.3,0.1

Type RM Length L Ch R = 1 ,63770   ,510,510,510
BEGIN DESCRIPTION:
HONDO CREEK 85.0
END DESCRIPTION:
XS GIS Cut Line= 4
      2381810.27     13183484.56      2381746.96     13182565.57
      2381641.35     13181381.27      2380992.68      13180257.4
#Sta/Elev= 30
  2815.3  106.99  4567.9  105.18  4912.4  104.24  4930.9  104.31  4953.7  105.79
  4961.1  104.41  4998.4  103.65  5063.1  103.87  5084.6  105.43  5092.2  105.33
  5100.4  104.38  5115.3  104.31  6065.4  103.57  6081.2  103.72  6096.7  105.92
  6102.7  105.14  6108.5  103.13  6118.5  103.42  6124.3   104.7  6145.8  105.19
  6154.5  105.06  6161.6  103.72  6164.4  102.43  6167.1  101.93  6170.4  102.43
  6177.4   102.5  6189.1  103.84  6204.7   108.4  6212.2  108.57  6223.1  106.78
#Mann= 3 ,-1 , 0
  2815.3     .05       0  6164.4    .035       0  6170.4     .05       0
Bank Sta=6164.4,6170.4
XS Rating Curve= 0 ,0
Exp/Cntr=0.3,0.1

Type RM Length L Ch R = 1 ,63260   ,643,643,643
BEGIN DESCRIPTION:
HONDO CREEK 84.0
END DESCRIPTION:
XS GIS Cut Line= 4
      2381940.48       13183528.      2382131.67     13182678.72
      2382192.01     13181418.98      2381453.23      13179820.8
#Sta/Elev= 30
  2636.7  107.01  4400.1  104.61  4869.9  103.34  4886.2  103.44    4903  104.66
    4932  103.61  5000.8  103.39  5029.3  104.34  5035.2  105.15  5052.2  103.77
  5828.4  103.04  6334.6  102.98  6379.2  103.24  6391.5  104.56  6397.7  104.44
  6401.2  104.38  6408.9  102.66  6445.3  104.63  6454.8  104.26  6464.3  102.13
  6467.1  101.63  6470.3  102.13  6483.3  102.94  6489.4  104.74  6500.4   105.7
  6502.4  106.53  6506.2  108.11  6511.7  108.14  6522.4  107.12  6529.1  104.53
#Mann= 5 ,-1 , 0
  2636.7     .05       0  6397.7     .08       0  6464.3    .035       0
  6470.3     .08       0  6502.4     .05       0
Bank Sta=6464.3,6470.3
XS Rating Curve= 0 ,0
Exp/Cntr=0.3,0.1

Type RM Length L Ch R = 1 ,62617   ,515,515,515
BEGIN DESCRIPTION:
HONDO CREEK 83.0
END DESCRIPTION:
XS GIS Cut Line= 4
      2382471.11     13182731.52      2382720.04     13181607.57
       2382712.5     13180129.07      2382531.78     13179120.03
#Sta/Elev= 30
  3388.5  105.34  4650.4  103.09  4860.4  102.62  4900.4  102.05  4910.4  102.12
  4930.4  103.95  4950.4  102.37  4990.4  101.86  5040.4  102.94  5050.4  104.26
  5070.4  102.59  5090.4   102.5  5687.4  101.74  5690.2  101.24  5693.4  101.74
    6122  103.01  6873.8  102.67    6884  102.96  6894.1  104.02  6904.3  104.14
  6914.5   102.3    6922  101.97  6934.8   103.7  6961.9  104.37  6965.3  104.35
  6985.9  101.97  7005.9  103.91  7016.1  105.95  7034.6  108.45  7043.3  105.86
#Mann= 4 ,-1 , 0
  3388.5     .05       0  5687.4    .035       0  5693.4     .05       0
  6961.9     .08       0
Bank Sta=5687.4,5693.4
XS Rating Curve= 0 ,0
Exp/Cntr=0.3,0.1

Type RM Length L Ch R = 1 ,62102   ,381,381,381
BEGIN DESCRIPTION:
HONDO CREEK 82.0
END DESCRIPTION:
XS GIS Cut Line= 4
      2382976.52     13182716.43      2383240.53     13181645.28
      2383157.56     13179985.75      2383021.93      13178900.7
#Sta/Elev= 30
  3332.1  104.36  3753.9   102.6  4104.1  101.85  4176.2  103.05  4239.3  101.94
  4814.2  101.57  4894.3  100.96  4914.3  101.26  4924.3  102.99  4934.4  102.84
  4944.4  101.28  4984.4  100.69  5034.5  100.83  5044.5  102.16  5054.5  102.44
  5064.5  100.97  5084.5  100.79  5401.9  100.58  5404.7  100.08  5407.9  100.58
  6388.1  103.02  7020.3  102.95  7053.2  104.09  7073.4   102.4    7101  104.67
  7123.7  103.61  7133.8  102.12  7174.1  107.54  7181.6  107.83  7190.4  106.63
#Mann= 4 ,-1 , 0
  3332.1     .05       0  5401.9    .035       0  5407.9     .05       0
  7073.4     .08       0
Bank Sta=5401.9,5407.9
XS Rating Curve= 0 ,0
Exp/Cntr=0.3,0.1

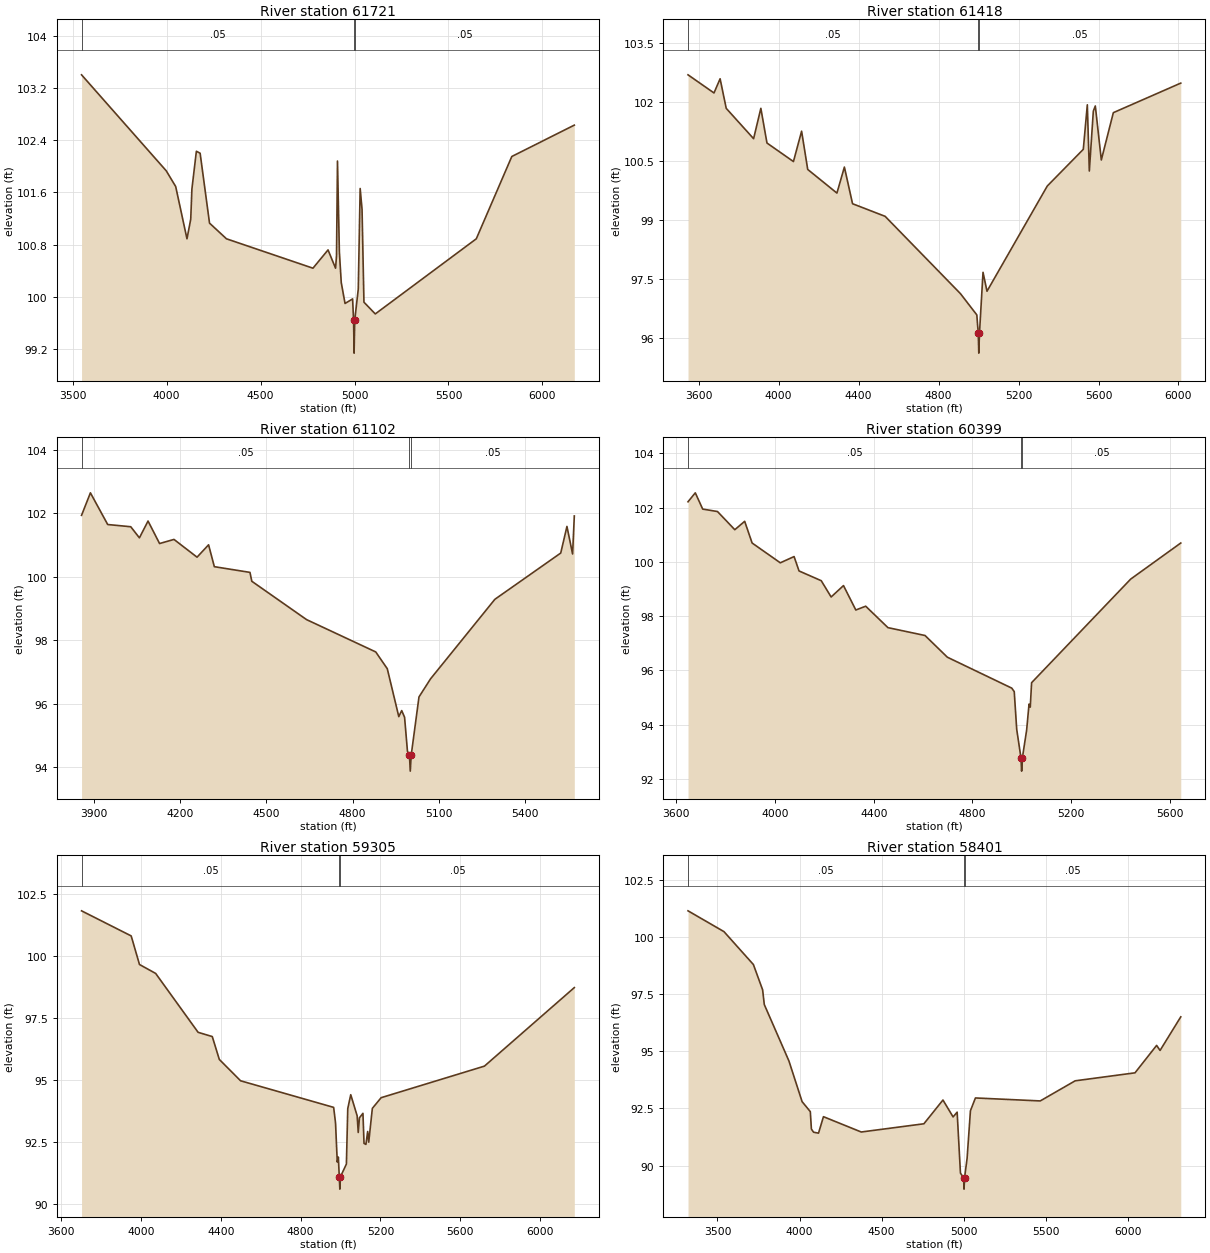
Type RM Length L Ch R = 1 ,61721   ,303,303,303
BEGIN DESCRIPTION:
Mapping XS aae991b7
END DESCRIPTION:
XS GIS Cut Line= 4
      2383640.33     13182467.48      2383602.61     13181207.77
      2383557.35     13180770.26      2383685.58     13179857.55
#Sta/Elev= 30
  3547.7   103.4  3998.5  101.93  4048.6  101.69  4108.6  100.89  4128.6  101.19
  4134.8  101.65  4158.6  102.23  4178.6   102.2  4228.6  101.13  4318.7  100.89
  4778.9  100.44  4859.2  100.72  4899.2  100.44  4904.3  100.63  4909.4  102.08
  4919.5  100.69  4929.5  100.22  4949.6    99.9  4989.9   99.97  4995.1   99.64
  4997.8   99.14  5001.1   99.64    5020  100.12  5030.1  101.66  5040.1  101.34
  5050.2   99.92  5110.5   99.74    5648  100.89    5837  102.15  6169.5  102.63
#Mann= 3 ,-1 , 0
  3547.7     .05       0  4995.1    .035       0  5001.1     .05       0
Bank Sta=4995.1,5001.1
XS Rating Curve= 0 ,0
Exp/Cntr=0.3,0.1

Type RM Length L Ch R = 1 ,61418   ,316,316,316
BEGIN DESCRIPTION:
Mapping XS 5d5cc47f
END DESCRIPTION:
XS GIS Cut Line= 3
      2384145.73     13182354.34        2383844.     13180815.52
      2383806.36     13179919.83
#Sta/Elev= 30
  3546.9  102.68  3676.8  102.22  3707.4  102.58    3738  101.83  3874.9  101.06
  3911.2  101.83  3941.8  100.95  4074.2  100.48    4115  101.25  4145.6  100.28
  4291.7   99.68    4329  100.34  4369.8   99.41  4532.8   99.09  4909.3   97.13
  4991.4   96.59  4998.6   96.12  5001.3   95.62  5004.6   96.12  5022.4   97.67
  5042.3   97.19  5343.9   99.86    5524  100.79  5544.1  101.92  5554.1  100.24
  5574.1  101.76  5584.1  101.89  5614.1  100.52  5674.2  101.72  6011.5  102.47
#Mann= 3 ,-1 , 0
  3546.9     .05       0  4998.6    .035       0  5004.6     .05       0
Bank Sta=4998.6,5004.6
XS Rating Curve= 0 ,0
Exp/Cntr=0.3,0.1

Type RM Length L Ch R = 1 ,61102   ,703,703,703
BEGIN DESCRIPTION:
Mapping XS d76dfdf1
END DESCRIPTION:
XS GIS Cut Line= 3
      2384251.34     13182037.58      2384168.36     13180785.34
      2384055.41     13180341.06
#Sta/Elev= 30
  3857.5  101.94  3888.3  102.65  3948.4  101.65  4028.6  101.58  4058.7  101.23
  4088.7  101.76  4128.8  101.05  4178.9  101.18  4259.1  100.62  4299.2  101.01
  4319.2  100.32  4443.1  100.14  4449.5   99.86  4639.9   98.65  4880.5   97.63
  4920.6    97.1  4960.6   95.59  4970.7   95.78  4980.7   95.57  4990.7    94.5
  4997.7   94.37  5000.5   93.87  5003.7   94.37  5030.8   96.21  5070.9   96.78
  5294.6   99.29  5523.7  100.75  5545.3  101.59  5564.9  100.72  5570.9  101.92
#Mann= 3 ,-1 , 0
  3857.5     .05       0  4997.7    .035       0  5003.7     .05       0
Bank Sta=4997.7,5003.7
XS Rating Curve= 0 ,0
Exp/Cntr=0.3,0.1

Type RM Length L Ch R = 1 ,60399   ,1094,1094,1094
BEGIN DESCRIPTION:
Mapping XS 835bae9d
END DESCRIPTION:
XS GIS Cut Line= 3
      2384877.43     13182256.29      2384915.15     13181336.01
      2384817.09     13180264.85
#Sta/Elev= 30
  3647.5  102.22    3677  102.55    3707  101.95    3767  101.86  3837.1  101.19
  3877.1   101.5  3907.2   100.7  4021.5   99.97  4077.3   100.2  4097.3   99.67
  4187.4   99.31  4227.4   98.71  4277.5   99.13  4327.5   98.23  4367.5   98.37
  4457.6   97.58  4607.9   97.29  4698.3   96.49  4959.3   95.35  4969.4   95.22
  4979.4   93.83  4996.5   92.79  4999.3   92.29  5002.5   92.79  5019.6    93.8
  5029.3   94.76  5034.3   94.65  5039.7   95.55  5441.3   99.37  5644.2   100.7
#Mann= 3 ,-1 , 0
  3647.5     .05       0  4996.5    .035       0  5002.5     .05       0
Bank Sta=4996.5,5002.5
XS Rating Curve= 0 ,0
Exp/Cntr=0.3,0.1

Type RM Length L Ch R = 1 ,59305   ,904,904,904
BEGIN DESCRIPTION:
Mapping XS 20d87482
END DESCRIPTION:
XS GIS Cut Line= 3
      2385722.29     13182633.45      2385903.32     13181517.05
      2385375.31     13180287.52
#Sta/Elev= 30
  3702.2  101.81  3950.9   100.8  3992.5   99.65  4073.6   99.29  4286.3   96.92
  4357.2   96.75  4392.4   95.83  4499.1   94.97  4965.4    93.9  4974.9   93.27
  4983.5    91.7    4989    91.9  4993.6   91.11  4996.4   90.61  4999.6   91.11
  5029.3   91.62  5036.1   93.85  5051.1   94.41  5083.2   93.56  5088.6   92.89
  5094.6   93.48  5112.2   93.66  5117.6   92.45  5127.2   92.41  5135.8   92.93
  5141.2    92.5  5159.3   93.86  5203.4   94.29    5721   95.56  6171.3   98.72
#Mann= 3 ,-1 , 0
  3702.2     .05       0  4993.6    .035       0  4999.6     .05       0
Bank Sta=4993.6,4999.6
XS Rating Curve= 0 ,0
Exp/Cntr=0.3,0.1

Type RM Length L Ch R = 1 ,58401   ,964,964,964
BEGIN DESCRIPTION:
Mapping XS ce2ad0ac
END DESCRIPTION:
XS GIS Cut Line= 3
      2386710.46     13183040.84      2386785.89     13181698.08
      2386521.93      13180061.5
#Sta/Elev= 30
  3320.6  101.15  3539.6  100.24  3718.9    98.8  3775.3   97.69  3785.3   97.05
  3935.5   94.58  4015.7    92.8  4065.8   92.36  4072.4    91.6  4085.8   91.46
  4115.8   91.42  4145.9   92.14  4376.2   91.47  4757.9   91.83  4874.1   92.87
  4935.9   92.13  4960.5   92.34  4980.7   89.67  4999.7   89.47  5002.5   88.97
  5005.7   89.47  5021.2   90.32  5041.5    92.4  5071.9   92.96  5466.9   92.83
  5679.6   93.71  6044.3   94.06    6176   95.26    6197   95.04  6323.2   96.51
#Mann= 3 ,-1 , 0
  3320.6     .05       0  4999.7    .035       0  5005.7     .05       0
Bank Sta=4999.7,5005.7
XS Rating Curve= 0 ,0
Exp/Cntr=0.3,0.1

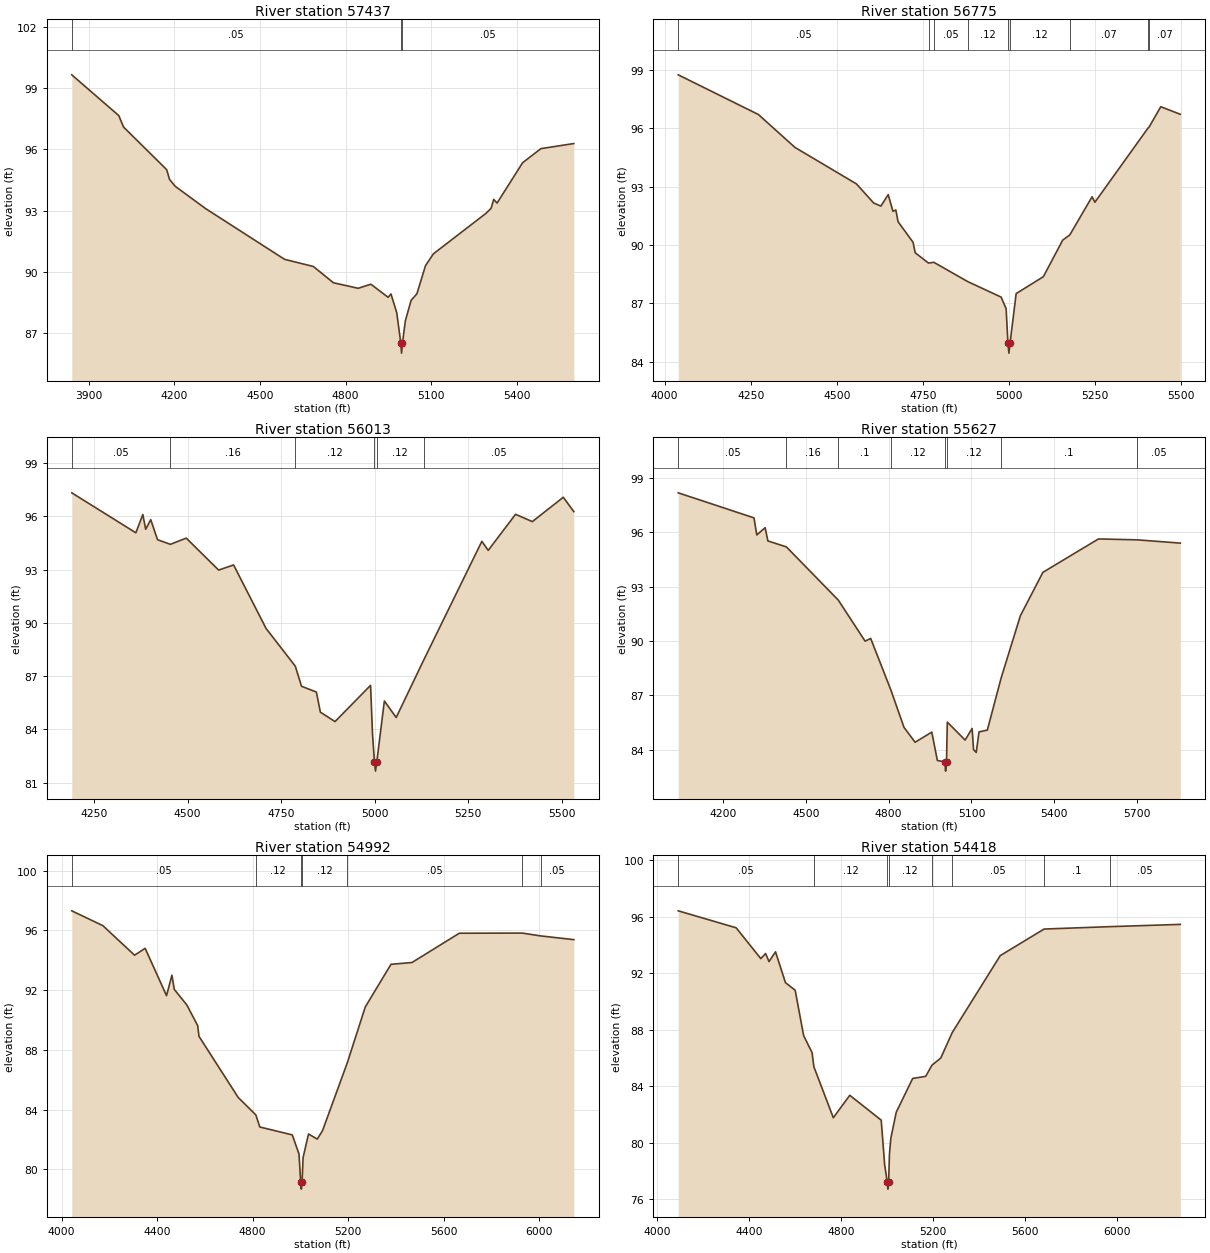
Type RM Length L Ch R = 1 ,57437   ,662,662,662
BEGIN DESCRIPTION:
Mapping XS de694bab
END DESCRIPTION:
XS GIS Cut Line= 3
      2387774.07     13182776.77      2387608.11     13181517.05
      2387457.65     13181050.62
#Sta/Elev= 30
    3840   99.66  4004.9   97.66  4021.5    97.1  4172.8   95.01  4182.9   94.53
    4203   94.19  4309.3    93.1  4586.3   90.61  4687.2   90.26  4757.8   89.46
  4844.6   89.19  4888.9   89.39  4949.4   88.75  4959.5   88.91  4979.7   87.99
  4993.8   86.51  4996.5   86.01  4999.8   86.51  5009.9    87.6  5030.1    88.6
  5050.3   88.92  5080.5    90.3  5108.2   90.88  5292.9   92.87  5310.4   93.11
  5319.7   93.55  5331.5   93.37  5421.1   95.35  5485.2   96.04  5600.7   96.29
#Mann= 3 ,-1 , 0
    3840     .05       0  4993.8     .03       0  4999.8     .05       0
Bank Sta=4993.8,4999.8
XS Rating Curve= 0 ,0
Exp/Cntr=0.3,0.1

Type RM Length L Ch R = 1 ,56775   ,762,762,762
BEGIN DESCRIPTION:
Mapping XS d64dc6ca
END DESCRIPTION:
XS GIS Cut Line= 2
      2388747.17     13182022.46      2387864.97     13180861.28
#Sta/Elev= 30
  4039.4   98.75  4272.2   96.71  4378.3   95.02  4557.1   93.14    4607   92.16
  4627.9      92  4649.3   92.59  4663.2   91.73  4671.5    91.8  4677.8    91.2
  4721.4   90.14  4727.7    89.6  4766.3   89.07  4781.8   89.11  4880.1   88.12
  4977.3   87.32  4991.8   86.72  4997.1   84.94  4999.8   84.44  5003.1   84.94
  5020.9    87.5  5099.9   88.37  5156.1   90.25  5176.8   90.52  5241.4   92.48
  5249.6    92.2    5403   95.99  5406.9   96.06    5441   97.11  5497.7   96.72
#Mann= 9 ,-1 , 0
  4039.4     .05       0  4766.3     .12       0  4781.8     .05       0
  4880.1     .12       0  4997.1     .07       0  5003.1     .12       0
  5176.8     .07       0    5403     .05       0  5406.9     .07       0
Bank Sta=4997.1,5003.1
XS Rating Curve= 0 ,0
Exp/Cntr=0.3,0.1

Type RM Length L Ch R = 1 ,56013   ,386,386,386
BEGIN DESCRIPTION:
Mapping XS c71f6abe
END DESCRIPTION:
XS GIS Cut Line= 3
      2388965.92     13181517.06      2388671.72     13180634.48
      2388302.37     13180453.57
#Sta/Elev= 30
  4190.7   97.32  4361.9   95.07  4380.6    96.1  4388.2   95.27  4401.7   95.81
  4419.9   94.68  4454.3   94.42  4496.6   94.77  4583.2   92.97  4623.1   93.26
  4709.7   89.69    4788   87.56  4804.6   86.43  4844.4    86.1    4855   84.97
  4894.2   84.44  4989.1   86.48  4994.3   83.75  4999.6   82.15  5002.3   81.65
  5005.6   82.15    5026    85.6  5057.6   84.67  5130.8   87.89  5286.5   94.59
  5303.5   94.08  5376.5   96.11  5421.5    95.7  5504.1   97.07  5532.3   96.26
#Mann= 6 ,-1 , 0
  4190.7     .05       0  4454.3     .16       0    4788     .12       0
  4999.6     .07       0  5005.6     .12       0  5130.8     .05       0
Bank Sta=4999.6,5005.6
XS Rating Curve= 0 ,0
Exp/Cntr=0.3,0.1

Type RM Length L Ch R = 1 ,55627   ,635,635,635
BEGIN DESCRIPTION:
Mapping XS 289be41e
END DESCRIPTION:
XS GIS Cut Line= 3
      2389162.03     13181539.63      2388988.54     13180000.84
      2388882.95     13179751.95
#Sta/Elev= 30
  4037.8   98.16  4312.3   96.78  4322.4   95.84  4352.6   96.24  4362.6   95.51
  4429.8   95.18  4617.7   92.25  4714.8   89.99    4735   90.14  4808.1    87.3
  4855.7   85.24    4896   84.42  4956.4   84.98  4976.5   83.42  5003.7   83.33
  5006.4   82.83  5009.7   83.33  5012.6   85.53  5077.1   84.54  5102.5   85.18
  5107.6   84.02  5117.4   83.86  5127.4   84.99  5157.6   85.09  5207.2   87.94
  5277.3   91.39  5358.9   93.78  5560.2   95.62  5700.5   95.57  5856.7   95.39
#Mann= 8 ,-1 , 0
  4037.8     .05       0  4429.8     .16       0  4617.7      .1       0
  4808.1     .12       0  5003.7     .07       0  5009.7     .12       0
  5207.2      .1       0  5700.5     .05       0
Bank Sta=5003.7,5009.7
XS Rating Curve= 0 ,0
Exp/Cntr=0.3,0.1

Type RM Length L Ch R = 1 ,54992   ,574,574,574
BEGIN DESCRIPTION:
Mapping XS 5b60bfc9
END DESCRIPTION:
XS GIS Cut Line= 3
      2390052.16     13181434.08      2389441.14     13180159.25
      2388928.19      13179699.1
#Sta/Elev= 30
  4042.3   97.31  4172.3   96.32  4305.4   94.34  4349.7    94.8  4439.2   91.63
  4461.8      93  4471.7   92.05  4524.2   91.01  4569.6   89.63  4575.1   88.91
  4739.2   84.82  4813.2   83.65  4829.9   82.84  4965.8   82.31    4994   81.03
    5001   79.18  5003.7   78.68    5007   79.18  5011.1   80.79  5033.8   82.37
  5070.5   82.03  5092.7    82.6    5197   87.17  5271.5   90.87  5379.2   93.73
  5467.2   93.85  5665.3   95.81  5928.9   95.82  6006.6   95.63  6145.1   95.38
#Mann= 7 ,-1 , 0
  4042.3     .05       0  4813.2     .12       0    5001     .07       0
    5007     .12       0    5197     .05       0  5928.9      .1       0
  6006.6     .05       0
Bank Sta=5001,5007
XS Rating Curve= 0 ,0
Exp/Cntr=0.3,0.1

Type RM Length L Ch R = 1 ,54418   ,622,622,622
BEGIN DESCRIPTION:
Mapping XS dbb5e9ea
END DESCRIPTION:
XS GIS Cut Line= 3
      2390783.87      13180740.1      2389388.34     13179759.45
      2388943.29     13179585.96
#Sta/Elev= 30
  4091.2   96.41    4343   95.21  4450.2   93.03  4471.1   93.39  4485.9   92.82
  4514.3   93.51  4557.4   91.33  4599.8   90.79  4636.5   87.58  4673.2   86.38
    4681   85.38  4765.6   81.77  4837.1   83.36  4973.9    81.6  4988.7   78.46
  5000.2   77.22  5002.9   76.72  5006.2   77.22  5009.6   79.16  5015.7   80.32
  5039.2   82.16  5110.7   84.55  5167.3    84.7  5194.5   85.49  5232.7   85.99
  5282.5   87.79  5491.4   93.24  5682.1   95.12  5967.2   95.29  6274.5   95.45
#Mann= 8 ,-1 , 0
  4091.2     .05       0    4681     .12       0  5000.2     .07       0
  5006.2     .12       0  5194.5      .1       0  5282.5     .05       0
  5682.1      .1       0  5967.2     .05       0
Bank Sta=5000.2,5006.2
XS Rating Curve= 0 ,0
Exp/Cntr=0.3,0.1

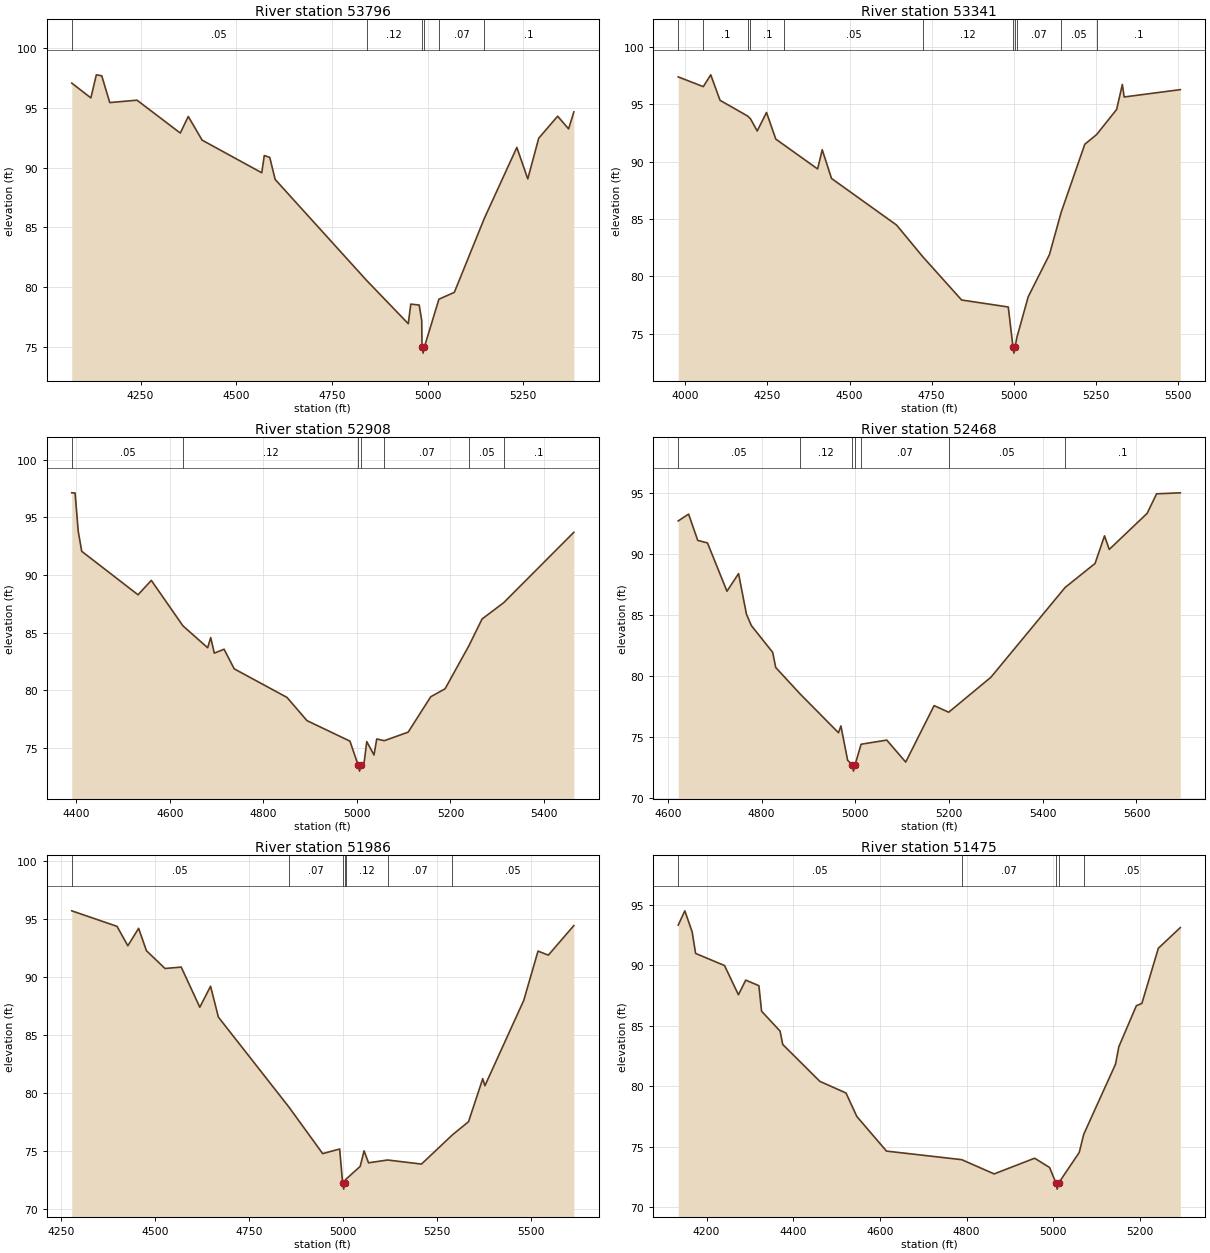
Type RM Length L Ch R = 1 ,53796   ,455,455,455
BEGIN DESCRIPTION:
HONDO CREEK 69.0
END DESCRIPTION:
XS GIS Cut Line= 3
      2390837.69     13180396.82      2390237.72     13179696.85
      2389937.73     13179446.87
#Sta/Elev= 30
  4070.1   97.07    4120   95.83  4134.3   97.76  4148.5   97.68  4169.4   95.44
  4240.7   95.64  4353.8   92.89  4374.6   94.28  4410.8    92.3  4566.7   89.57
  4573.3   91.01  4587.6   90.86  4601.8   89.01  4840.8   80.57  4949.7   76.95
  4956.3   78.59  4978.3   78.51  4984.9   77.21  4985.7   74.99  4988.5   74.49
  4991.7   74.99  5029.8      79  5070.1   79.57  5148.8   85.78  5233.5   91.69
  5262.1   89.06  5290.7   92.46  5340.2    94.3  5368.8   93.24  5382.5   94.66
#Mann= 6 ,-1 , 0
  4070.1     .05       0  4840.8     .12       0  4985.7     .07       0
  4991.7     .12       0  5029.8     .07       0  5148.8      .1       0
Bank Sta=4985.7,4991.7
XS Rating Curve= 0 ,0
Exp/Cntr=0.3,0.1

Type RM Length L Ch R = 1 ,53341   ,433,433,433
BEGIN DESCRIPTION:
HONDO CREEK 68.0
END DESCRIPTION:
XS GIS Cut Line= 3
      2391237.74     13180096.88      2390537.72     13179396.85
      2390337.72     13178896.86
#Sta/Elev= 30
  3978.6   97.39  4054.9   96.54  4077.6   97.57  4105.9   95.35  4189.8   93.98
  4198.5   93.74  4219.1   92.68  4247.3   94.29  4275.6   91.97  4301.5   91.44
  4402.9   89.37    4417   91.04  4445.3   88.54  4643.3   84.48  4723.4   81.71
  4841.3   77.95  4983.4   77.34  4997.9   73.82  5000.6   73.32  5003.9   73.82
  5009.5   74.68    5044   78.23  5108.6    81.9  5144.5    85.6  5216.3   91.52
  5252.2   92.36  5313.2   94.55  5330.7   96.73  5336.1   95.64  5507.1   96.28
#Mann= 11 ,-1 , 0
  3978.6     .05       0  4054.9      .1       0  4189.8     .05       0
  4198.5      .1       0  4301.5     .05       0  4723.4     .12       0
  4997.9     .07       0  5003.9     .12       0  5009.5     .07       0
  5144.5     .05       0  5252.2      .1       0
Bank Sta=4997.9,5003.9
XS Rating Curve= 0 ,0
Exp/Cntr=0.3,0.1

Type RM Length L Ch R = 1 ,52908   ,440,440,440
BEGIN DESCRIPTION:
HONDO CREEK 67.0
END DESCRIPTION:
XS GIS Cut Line= 3
       2391337.7     13179696.83      2390937.72     13179246.85
      2390537.76     13178996.88
#Sta/Elev= 30
  4390.2   97.13  4397.3   97.12    4404    93.8  4411.5   92.06  4531.9   88.29
  4560.3   89.54  4628.1   85.59  4680.8    83.7  4687.4   84.58    4695   83.23
  4715.9   83.57  4737.6   81.87  4850.5   79.39  4893.2   77.38  4985.1    75.6
  5002.8    73.5  5005.6      73  5008.8    73.5  5015.2   73.68  5021.1   75.56
  5036.5    74.4  5042.4   75.79  5058.5   75.64  5109.6   76.38  5157.9   79.45
  5188.6   80.14  5240.1   83.92  5267.6   86.19    5314   87.61  5463.9   93.71
#Mann= 7 ,-1 , 0
  4390.2     .05       0  4628.1     .12       0  5002.8     .07       0
  5008.8     .12       0  5058.5     .07       0  5240.1     .05       0
    5314      .1       0
Bank Sta=5002.8,5008.8
XS Rating Curve= 0 ,0
Exp/Cntr=0.3,0.1

Type RM Length L Ch R = 1 ,52468   ,482,482,482
BEGIN DESCRIPTION:
HONDO CREEK 66.0
END DESCRIPTION:
XS GIS Cut Line= 3
      2391587.76     13179046.87      2391237.72     13178946.85
      2390537.67     13178846.85
#Sta/Elev= 30
  4622.3   92.68  4644.4   93.24  4663.9   91.09  4684.7   90.88  4726.3   86.93
    4751   88.37  4767.9   85.04  4778.3   84.12  4823.8   81.93  4830.3   80.69
  4881.5   78.56  4964.2   75.35  4969.4   75.91  4983.7    73.1  4993.4   72.71
  4996.2   72.21  4999.4   72.71  5012.5   74.41  5067.2   74.75  5107.6   72.95
  5168.2   77.57  5199.4   77.03  5289.4   79.89  5447.8   87.24  5511.6    89.2
  5531.8   91.46  5541.9   90.35  5622.7    93.3  5642.9    94.9  5693.5   94.98
#Mann= 7 ,-1 , 0
  4622.3     .05       0  4881.5     .12       0  4993.4     .07       0
  4999.4     .12       0  5012.5     .07       0  5199.4     .05       0
  5447.8      .1       0
Bank Sta=4993.4,4999.4
XS Rating Curve= 0 ,0
Exp/Cntr=0.3,0.1

Type RM Length L Ch R = 1 ,51986   ,511,511,511
BEGIN DESCRIPTION:
HONDO CREEK 65.0
END DESCRIPTION:
XS GIS Cut Line= 3
      2391787.75     13179046.89      2391337.72     13178496.85
       2390787.7     13178196.84
#Sta/Elev= 30
  4277.7    95.7  4398.3   94.36    4427   92.69  4455.8   94.19  4476.6   92.26
  4526.1   90.73  4569.2   90.85  4618.7   87.39  4647.4    89.2  4668.2   86.54
  4855.7    78.8    4946   74.77  4991.2   75.17  4999.1   72.21  5001.9   71.71
  5005.1   72.21  5007.2   72.54  5045.8   73.67  5056.2   75.01  5068.1   73.98
  5118.9   74.22  5209.1   73.87  5291.6   76.39  5334.4   77.52  5372.3   81.23
    5378   80.62  5481.5   87.98  5519.5   92.23    5547   91.88  5614.9   94.43
#Mann= 7 ,-1 , 0
  4277.7     .05       0  4855.7     .07       0  4999.1     .07       0
  5005.1     .07       0  5007.2     .12       0  5118.9     .07       0
  5291.6     .05       0
Bank Sta=4999.1,5005.1
XS Rating Curve= 0 ,0
Exp/Cntr=0.3,0.1

Type RM Length L Ch R = 1 ,51475   ,413,413,413
BEGIN DESCRIPTION:
HONDO CREEK 64.0
END DESCRIPTION:
XS GIS Cut Line= 3
      2391787.74      13178896.9      2391487.72     13178096.85
      2391437.72     13177796.84
#Sta/Elev= 30
  4134.5   93.34  4149.7   94.52  4166.6   92.78  4174.6   90.99  4241.3   89.99
  4273.4   87.57  4290.3   88.78  4320.6   88.32  4326.8   86.21  4369.5   84.56
  4375.7   83.45  4461.2    80.4  4521.7   79.43  4546.6   77.49  4615.1   74.62
  4788.7   73.91  4863.5   72.73  4956.9   74.03  4991.5   73.26  5006.2   71.97
    5009   71.47  5012.2   71.97  5059.9   74.51  5070.2   76.01  5143.6   81.82
  5151.2   83.26  5191.7   86.66  5204.4   86.85  5242.4   91.42  5293.1   93.13
#Mann= 5 ,-1 , 0
  4134.5     .05       0  4788.7     .07       0  5006.2     .07       0
  5012.2     .07       0  5070.2     .05       0
Bank Sta=5006.2,5012.2
XS Rating Curve= 0 ,0
Exp/Cntr=0.3,0.1