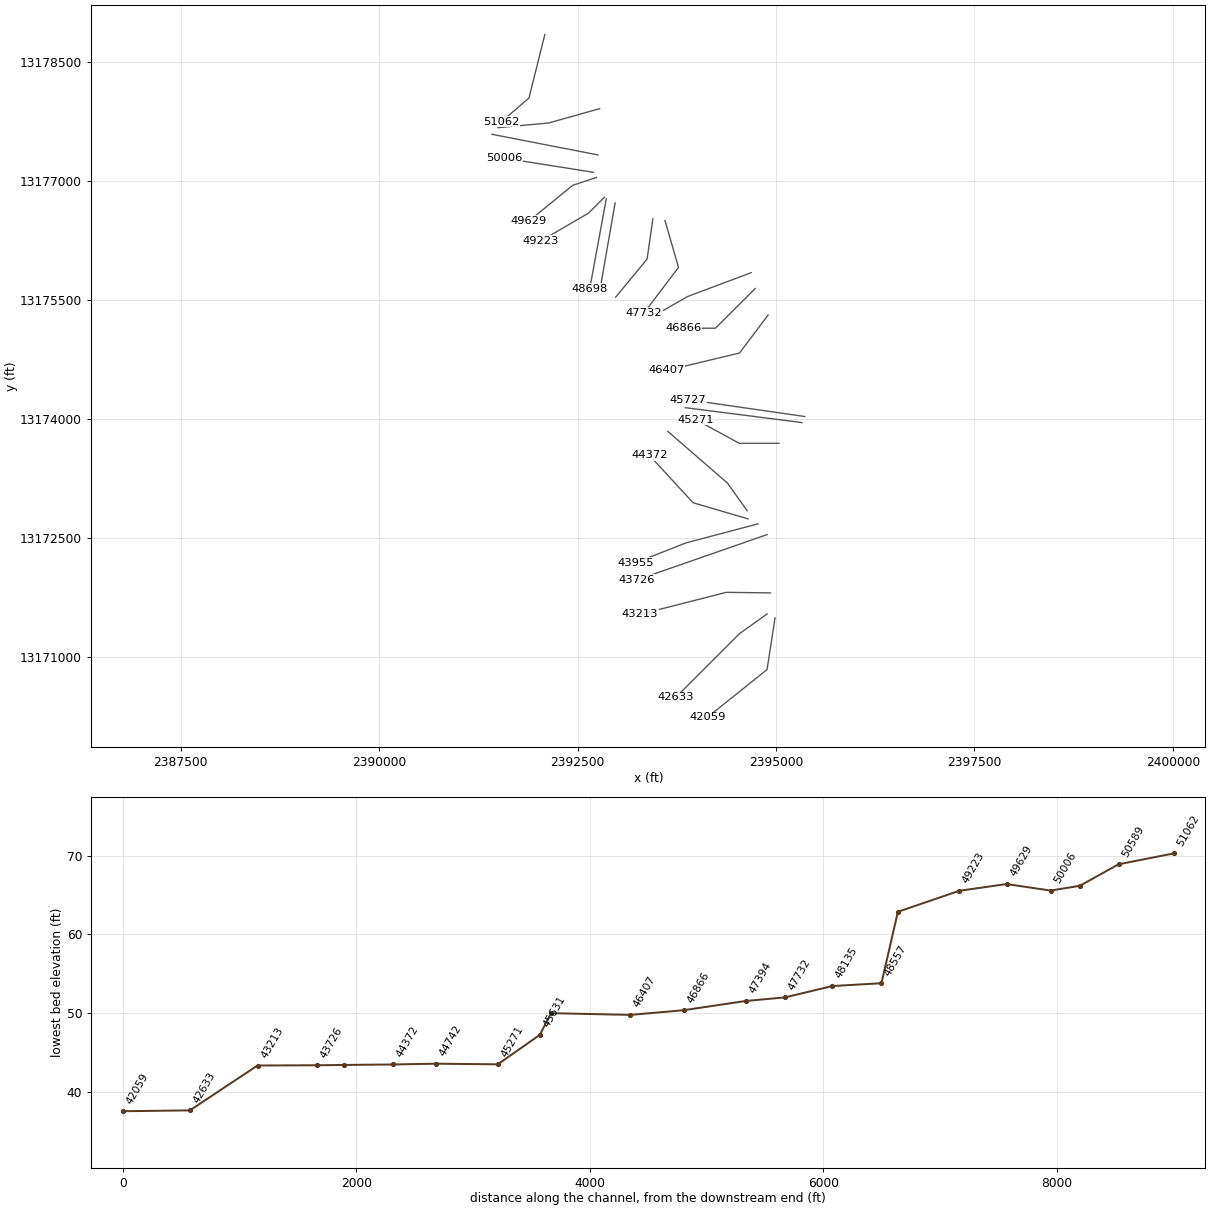
HEC-RAS study HONDO CREEK.prj: HONDO CREEK Base Level Engineering

--- HONDO CREEK.g02 (geometry) --- (continued)

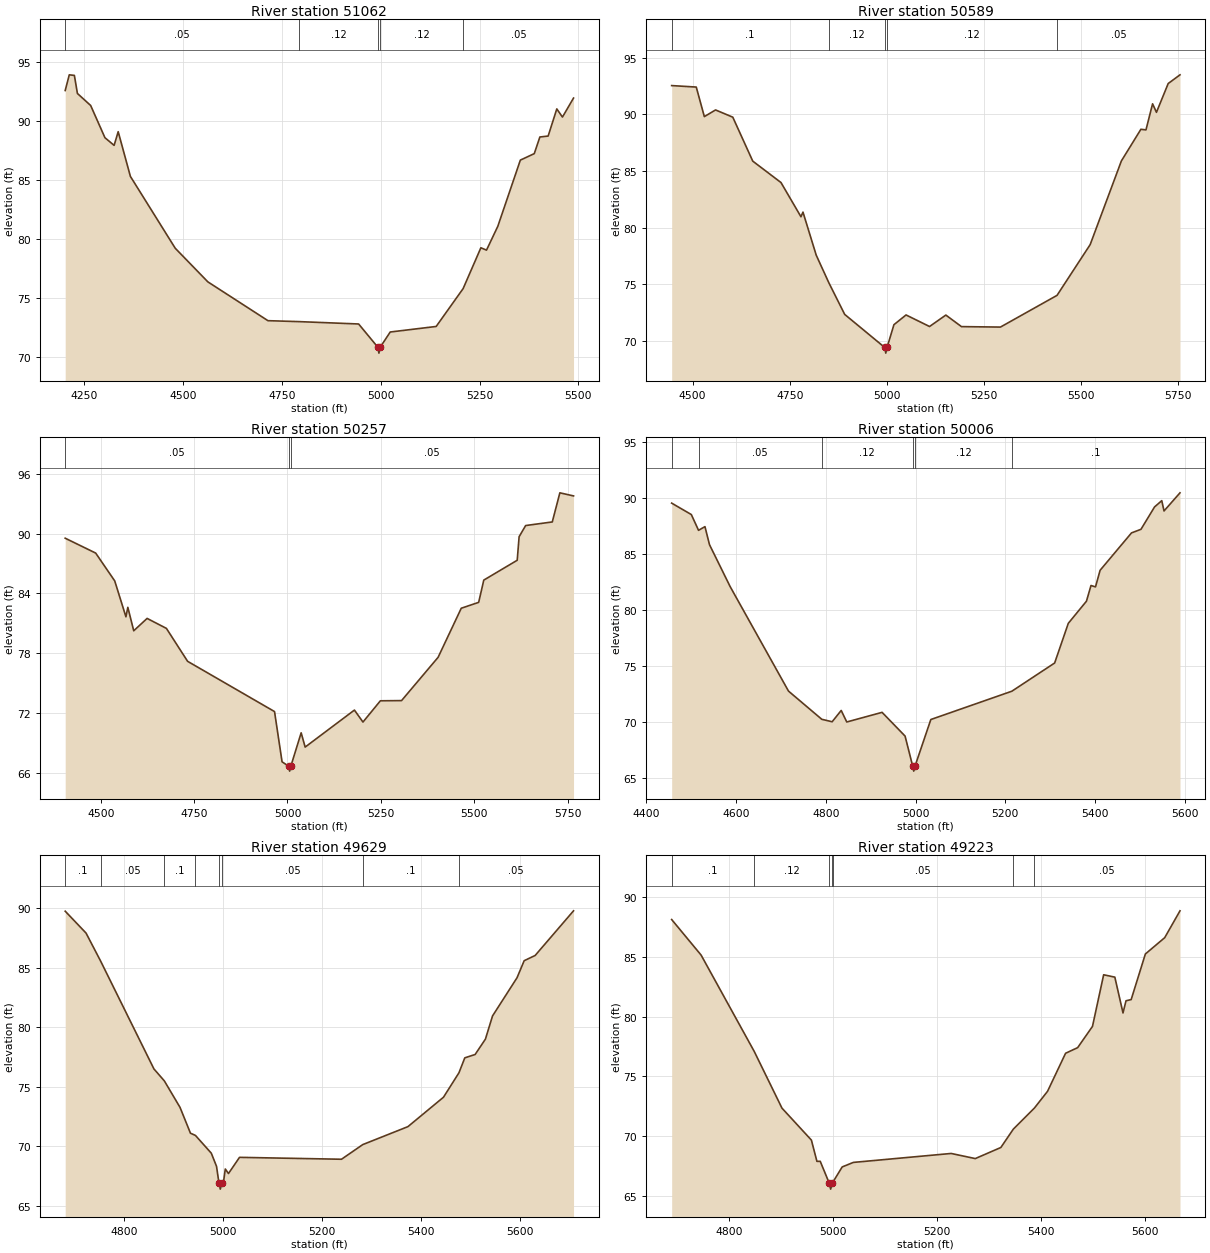
Type RM Length L Ch R = 1 ,51062   ,473,473,473
BEGIN DESCRIPTION:
HONDO CREEK 63.0
END DESCRIPTION:
XS GIS Cut Line= 3
      2392087.72     13178846.84      2391887.72     13178046.85
      2391537.71     13177746.85
#Sta/Elev= 30
    4202   92.56  4212.3   93.89  4225.2   93.84  4232.9   92.31  4266.4   91.29
  4302.5   88.56  4325.7   87.91    4336   89.07  4366.9   85.28  4480.3   79.19
  4562.8   76.34  4714.8   73.05  4793.9   72.97  4944.1   72.77  4992.7    70.8
  4995.4    70.3  4998.7    70.8    5024   72.09  5140.2   72.56  5208.4   75.77
  5253.3   79.23  5267.5   79.03  5296.1   81.05  5353.1   86.66  5388.3   87.21
  5402.5   88.62  5423.4    88.7  5445.3      91  5459.6   90.31  5487.6   91.92
#Mann= 5 ,-1 , 0
    4202     .05       0  4793.9     .12       0  4992.7     .07       0
  4998.7     .12       0  5208.4     .05       0
Bank Sta=4992.7,4998.7
XS Rating Curve= 0 ,0
Exp/Cntr=0.3,0.1

Type RM Length L Ch R = 1 ,50589   ,332,332,332
BEGIN DESCRIPTION:
Mapping XS 233a5ac2
END DESCRIPTION:
XS GIS Cut Line= 3
       2392778.7     13177913.21      2392136.31     13177732.65
      2391497.41     13177673.62
#Sta/Elev= 30
    4446   92.54  4509.3   92.41  4530.1    89.8    4559   90.39  4603.4   89.75
  4654.8   85.87  4727.5   83.98  4778.9   80.96  4784.1   81.37  4818.2   77.57
  4850.6   75.14  4891.5   72.34  4994.6   69.42  4997.3   68.92  5000.6   69.42
  5018.3   71.43  5049.5   72.29    5110   71.27    5152   72.28  5192.2   71.26
  5292.6   71.22  5438.3   74.02  5523.6    78.5    5604   85.89  5654.2   88.68
  5667.3   88.63  5684.3   90.93  5694.3   90.18  5724.5   92.72  5754.9   93.49
#Mann= 5 ,-1 , 0
    4446      .1       0  4850.6     .12       0  4994.6     .07       0
  5000.6     .12       0  5438.3     .05       0
Bank Sta=4994.6,5000.6
XS Rating Curve= 0 ,0
Exp/Cntr=0.3,0.1

Type RM Length L Ch R = 1 ,50257   ,251,251,251
BEGIN DESCRIPTION:
HONDO CREEK 62.0
END DESCRIPTION:
XS GIS Cut Line= 2
      2392757.83     13177329.88      2391421.84     13177590.13
#Sta/Elev= 30
  4404.9   89.53  4486.5   88.04  4537.5   85.25  4567.5   81.65  4572.6    82.6
  4588.4   80.25  4624.2   81.49  4675.9   80.49  4732.6   77.19  4965.4   72.15
  4985.6   67.11  5003.1   66.68  5005.9   66.18  5009.1   66.68  5036.7   70.02
  5047.4   68.59  5179.3    72.3  5202.2    71.1  5248.8   73.23  5305.5   73.25
  5403.4   77.59  5465.4   82.51    5512    83.1  5525.7   85.33  5615.2   87.32
  5620.3   89.68  5637.8    90.8  5709.1   91.16  5729.4   94.08    5766   93.77
#Mann= 3 ,-1 , 0
  4404.9     .05       0  5003.1     .04       0  5009.1     .05       0
Bank Sta=5003.1,5009.1
XS Rating Curve= 0 ,0
Exp/Cntr=0.3,0.1

Type RM Length L Ch R = 1 ,50006   ,377,377,377
BEGIN DESCRIPTION:
HONDO CREEK 61.0
END DESCRIPTION:
XS GIS Cut Line= 2
      2392701.01     13177111.45      2391581.75     13177288.05
#Sta/Elev= 30
  4456.3   89.51  4500.1   88.49  4516.2   87.08  4530.5   87.41  4540.6    85.8
  4586.7   82.05  4716.7   72.72  4790.9    70.2    4814   69.98  4834.2   70.99
  4846.6   69.96  4925.3   70.82  4976.6    68.7  4993.2   66.07  4995.9   65.57
  4999.2   66.07    5034   70.18  5214.7   72.71    5310   75.23  5340.4   78.77
  5380.9   80.75    5391   82.15  5401.1   82.03  5411.3   83.51  5481.3   86.85
  5502.4   87.17  5532.7   89.17  5548.8   89.73  5553.8   88.81  5589.4   90.43
#Mann= 6 ,-1 , 0
  4456.3      .1       0  4516.2     .05       0  4790.9     .12       0
  4993.2     .07       0  4999.2     .12       0  5214.7      .1       0
Bank Sta=4993.2,4999.2
XS Rating Curve= 0 ,0
Exp/Cntr=0.3,0.1

Type RM Length L Ch R = 1 ,49629   ,406,406,406
BEGIN DESCRIPTION:
HONDO CREEK 60.0
END DESCRIPTION:
XS GIS Cut Line= 3
       2392737.7     13177046.85      2392437.72     13176946.85
      2391887.76     13176496.88
#Sta/Elev= 30
  4680.9   89.75    4723   87.91  4752.3   85.57  4860.1    76.5  4881.2   75.49
  4912.8   73.27  4933.9    71.1    4944   70.91    4976   69.42  4986.6   68.31
  4991.5    66.9  4994.2    66.4  4997.5    66.9  5000.3    66.9  5004.3   68.09
  5010.7   67.71    5033   69.07    5239   68.91  5281.9   70.14  5373.2   71.65
    5445   74.12  5476.2   76.17  5488.1   77.43  5508.9   77.71  5529.7      79
  5544.1   80.95  5593.6   84.16    5608   85.59  5630.2   86.03  5707.7   89.78
#Mann= 8 ,-1 , 0
  4680.9      .1       0  4752.3     .05       0  4881.2      .1       0
    4944     .05       0  4991.5     .03       0  4997.5     .05       0
  5281.9      .1       0  5476.2     .05       0
Bank Sta=4991.5,4997.5
XS Rating Curve= 0 ,0
Exp/Cntr=0.3,0.1

Type RM Length L Ch R = 1 ,49223   ,525,525,525
BEGIN DESCRIPTION:
HONDO CREEK 59.0
END DESCRIPTION:
XS GIS Cut Line= 3
      2392837.72     13176796.85      2392637.72     13176596.85
      2392037.69     13176246.84
#Sta/Elev= 30
  4689.2   88.14  4745.8   85.16    4848   77.08  4901.3   72.33  4957.9   69.65
  4968.5   67.87  4974.9   67.87  4992.2   66.04  4994.9   65.54  4998.2   66.04
  4998.6   66.08  5017.1    67.4  5038.6   67.78  5226.7   68.53    5273    68.1
  5322.2   69.03  5346.2   70.57  5386.8   72.34    5412   73.74  5446.7   76.93
  5469.9    77.4  5498.4   79.18  5519.9   83.51  5541.4   83.31  5557.1   80.31
  5562.9   81.33  5572.8   81.43  5600.1   85.25  5637.3   86.62  5666.7   88.87
#Mann= 7 ,-1 , 0
  4689.2      .1       0    4848     .12       0  4992.2     .03       0
  4998.2     .12       0  4998.6     .05       0  5346.2      .1       0
  5386.8     .05       0
Bank Sta=4992.2,4998.2
XS Rating Curve= 0 ,0
Exp/Cntr=0.3,0.1

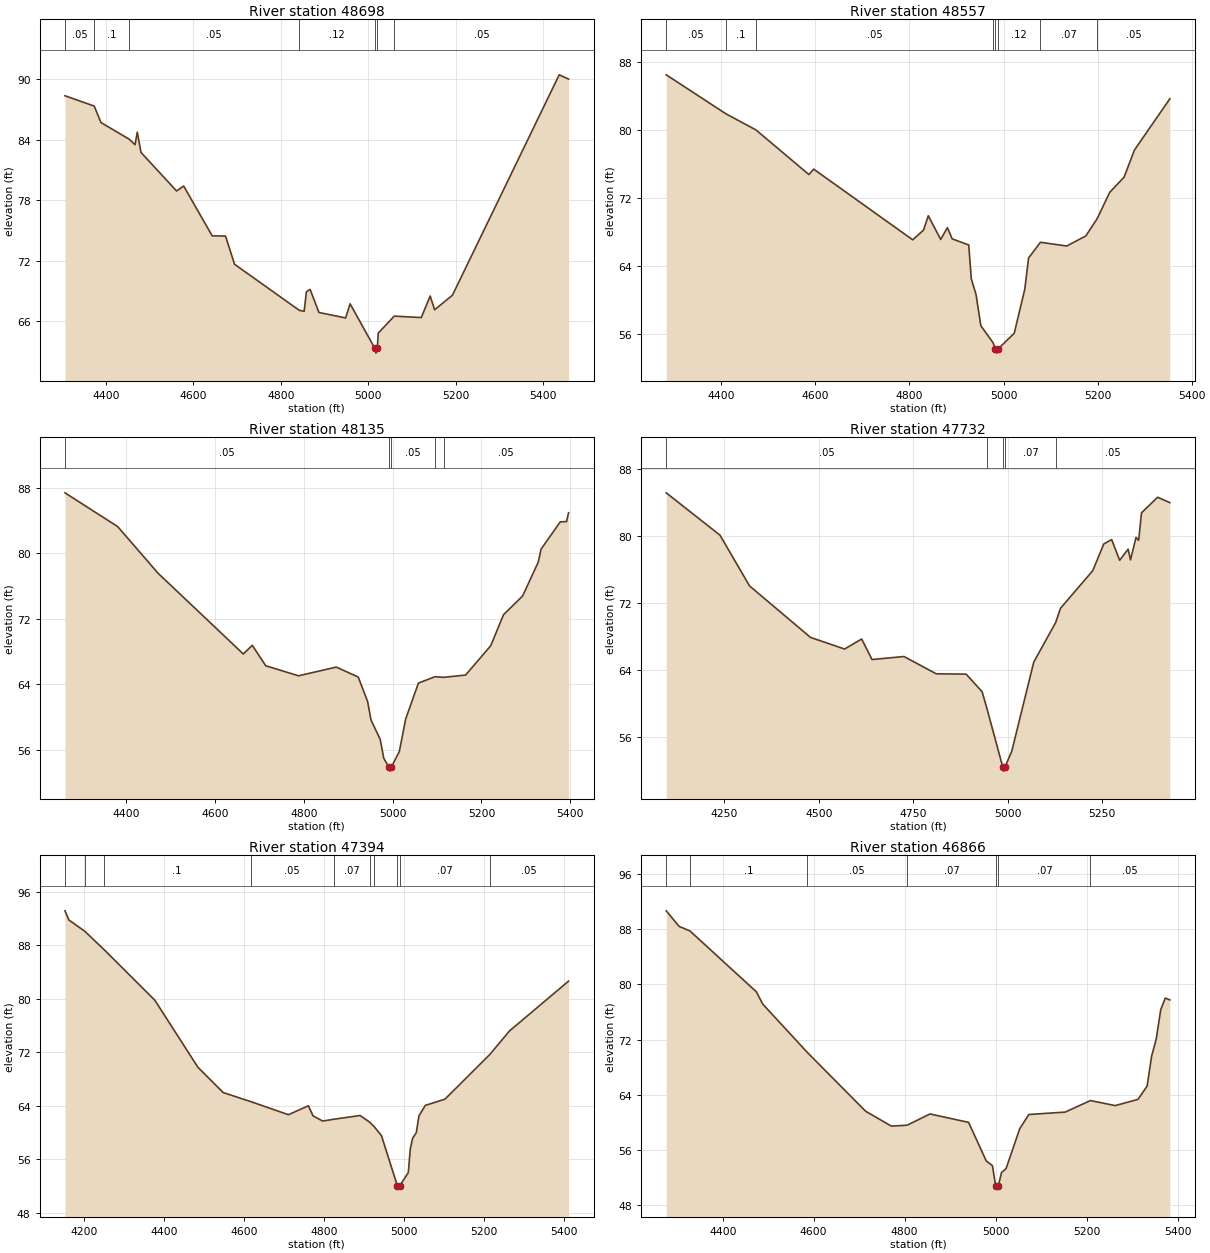
Type RM Length L Ch R = 1 ,48698   ,141,141,141
BEGIN DESCRIPTION:
Mapping XS e112fc92
END DESCRIPTION:
XS GIS Cut Line= 2
      2392862.01     13176777.78      2392653.67      13175645.8
#Sta/Elev= 30
  4306.7   88.33  4373.5   87.31    4389   85.68  4453.2   84.04  4466.9   83.49
    4472   84.73  4480.5   82.72  4561.8   78.91    4578    79.4  4643.2   74.47
  4673.7   74.45  4694.3   71.66  4842.1   67.11  4853.4   67.01  4858.5   68.94
  4866.9   69.18  4887.2   66.89  4948.2   66.35  4958.4   67.75  5014.6   63.37
  5017.4   62.87  5020.6   63.37  5022.7   64.85  5059.4   66.53  5121.1   66.39
  5141.4   68.52  5151.6   67.16  5192.3    68.6  5436.3    90.4  5457.7   89.98
#Mann= 7 ,-1 , 0
  4306.7     .05       0  4373.5      .1       0  4453.2     .05       0
  4842.1     .12       0  5014.6     .07       0  5020.6     .12       0
  5059.4     .05       0
Bank Sta=5014.6,5020.6
XS Rating Curve= 0 ,0
Exp/Cntr=0.3,0.1

Type RM Length L Ch R = 1 ,48557   ,422,422,422
BEGIN DESCRIPTION:
HONDO CREEK 58.0
END DESCRIPTION:
XS GIS Cut Line= 2
      2392973.11     13176725.68      2392789.24     13175670.99
#Sta/Elev= 30
    4283   86.54  4410.2   81.94  4473.6   80.06  4586.3    74.8  4596.5   75.44
  4806.9   67.12    4830   68.26  4840.1   69.95  4866.5   67.16  4880.7   68.55
  4890.9   67.23  4926.1   66.51  4931.5   62.53  4941.6   60.69  4951.8   57.01
  4977.8      55  4982.6   54.28  4985.4   53.78  4988.6   54.28  5022.8   56.12
  5045.2   61.29  5053.3   64.98  5078.6   66.83  5134.5   66.39  5175.1   67.58
    5199    69.6  5225.8   72.71  5256.3   74.49  5278.4   77.69  5353.6   83.72
#Mann= 8 ,-1 , 0
    4283     .05       0  4410.2      .1       0  4473.6     .05       0
  4977.8     .12       0  4982.6     .07       0  4988.6     .12       0
  5078.6     .07       0    5199     .05       0
Bank Sta=4982.6,4988.6
XS Rating Curve= 0 ,0
Exp/Cntr=0.3,0.1

Type RM Length L Ch R = 1 ,48135   ,403,403,403
BEGIN DESCRIPTION:
HONDO CREEK 57.0
END DESCRIPTION:
XS GIS Cut Line= 3
      2393448.81      13176524.3       2393375.9     13176017.37
      2392980.04     13175538.18
#Sta/Elev= 30
  4262.4   87.37  4381.1   83.25    4472   77.56  4663.9   67.71  4684.1   68.77
  4714.4   66.27  4788.2   65.05  4873.1   66.11  4922.6    64.9  4943.8    61.9
  4951.3   59.67  4972.1   57.29    4980      55  4991.3   53.92    4994   53.42
  4997.3   53.92  5015.1   55.81  5029.4   59.78  5058.1   64.16  5095.5   64.94
  5114.6   64.86  5164.3   65.14  5220.9   68.72  5249.6    72.5  5292.6   74.78
  5327.8   78.91  5334.3   80.51  5377.3   83.82  5391.6   83.87  5396.1   84.94
#Mann= 5 ,-1 , 0
  4262.4     .05       0  4991.3    .035       0  4997.3     .05       0
  5095.5     .07       0  5114.6     .05       0
Bank Sta=4991.3,4997.3
XS Rating Curve= 0 ,0
Exp/Cntr=0.3,0.1

Type RM Length L Ch R = 1 ,47732   ,338,338,338
BEGIN DESCRIPTION:
HONDO CREEK 56.0
END DESCRIPTION:
XS GIS Cut Line= 3
      2393601.58     13176503.51      2393771.73     13175913.21
       2393338.3     13175341.08
#Sta/Elev= 30
  4096.4   85.15  4238.6    80.1  4316.9   74.05    4478   67.92  4568.2   66.53
  4613.3   67.73  4640.7   65.28  4725.3   65.64  4810.6   63.58  4889.7   63.54
    4932   61.44  4945.3   59.35  4986.5   52.48  4989.3   51.98  4992.5   52.48
  5010.4   54.36  5068.6   64.98  5126.5   69.69  5139.3   71.39  5224.6   75.87
  5253.7   79.05  5274.6   79.58  5295.8   77.11  5318.2   78.44  5324.5   77.16
    5339   79.84    5346   79.49  5353.6   82.77  5396.2   84.62  5428.5   83.98
#Mann= 5 ,-1 , 0
  4096.4     .05       0  4945.3     .07       0  4986.5     .07       0
  4992.5     .07       0  5126.5     .05       0
Bank Sta=4986.5,4992.5
XS Rating Curve= 0 ,0
Exp/Cntr=0.3,0.1

Type RM Length L Ch R = 1 ,47394   ,528,528,528
BEGIN DESCRIPTION:
HONDO CREEK 55.0
END DESCRIPTION:
XS GIS Cut Line= 3
      2394687.71     13175846.85      2393887.72     13175546.85
      2393537.72     13175346.86
#Sta/Elev= 30
  4153.4   93.14  4163.2   91.77  4202.6    90.1  4249.7   87.42  4377.7   79.78
  4485.4   69.74  4548.6   65.96  4617.3   64.61  4711.4   62.65  4761.3   63.99
  4772.8   62.48  4796.9    61.7  4824.7   61.97  4890.3   62.53  4914.2   61.54
  4925.7   60.85  4943.7   59.52  4983.4   52.02  4986.2   51.52  4989.4   52.02
  5010.7      54  5015.7   57.55  5021.5   59.12  5030.8   59.98  5037.3   62.48
  5053.1   64.04  5102.1   64.97  5214.3   71.66  5263.3   75.17  5410.9   82.63
#Mann= 10 ,-1 , 0
  4153.4      .1       0  4202.6     .05       0  4249.7      .1       0
  4617.3     .05       0  4824.7     .07       0  4914.2     .12       0
  4925.7     .07       0  4983.4     .07       0  4989.4     .07       0
  5214.3     .05       0
Bank Sta=4983.4,4989.4
XS Rating Curve= 0 ,0
Exp/Cntr=0.3,0.1

Type RM Length L Ch R = 1 ,46866   ,459,459,459
BEGIN DESCRIPTION:
HONDO CREEK 54.0
END DESCRIPTION:
XS GIS Cut Line= 3
      2394737.75     13175646.88      2394237.72     13175146.85
      2393837.77     13175146.85
#Sta/Elev= 30
  4275.9   90.63  4304.2   88.38    4328   87.72  4473.9   78.92  4488.1   77.13
  4586.3   70.12  4714.3   61.62  4770.9   59.47  4805.4    59.6  4855.8   61.23
  4940.6   60.01  4979.5   54.42    4993   53.75    5000   50.85  5002.8   50.35
    5006   50.85    5013   52.76    5023   53.32    5053   59.09    5073   61.15
    5153    61.5  5208.4   63.17    5263   62.44    5313   63.34    5333   65.25
    5343   69.61    5353   72.04    5363   76.32    5373      78    5383   77.74
#Mann= 7 ,-1 , 0
  4275.9     .05       0    4328      .1       0  4586.3     .05       0
  4805.4     .07       0    5000     .07       0    5006     .07       0
  5208.4     .05       0
Bank Sta=5000,5006
XS Rating Curve= 0 ,0
Exp/Cntr=0.3,0.1

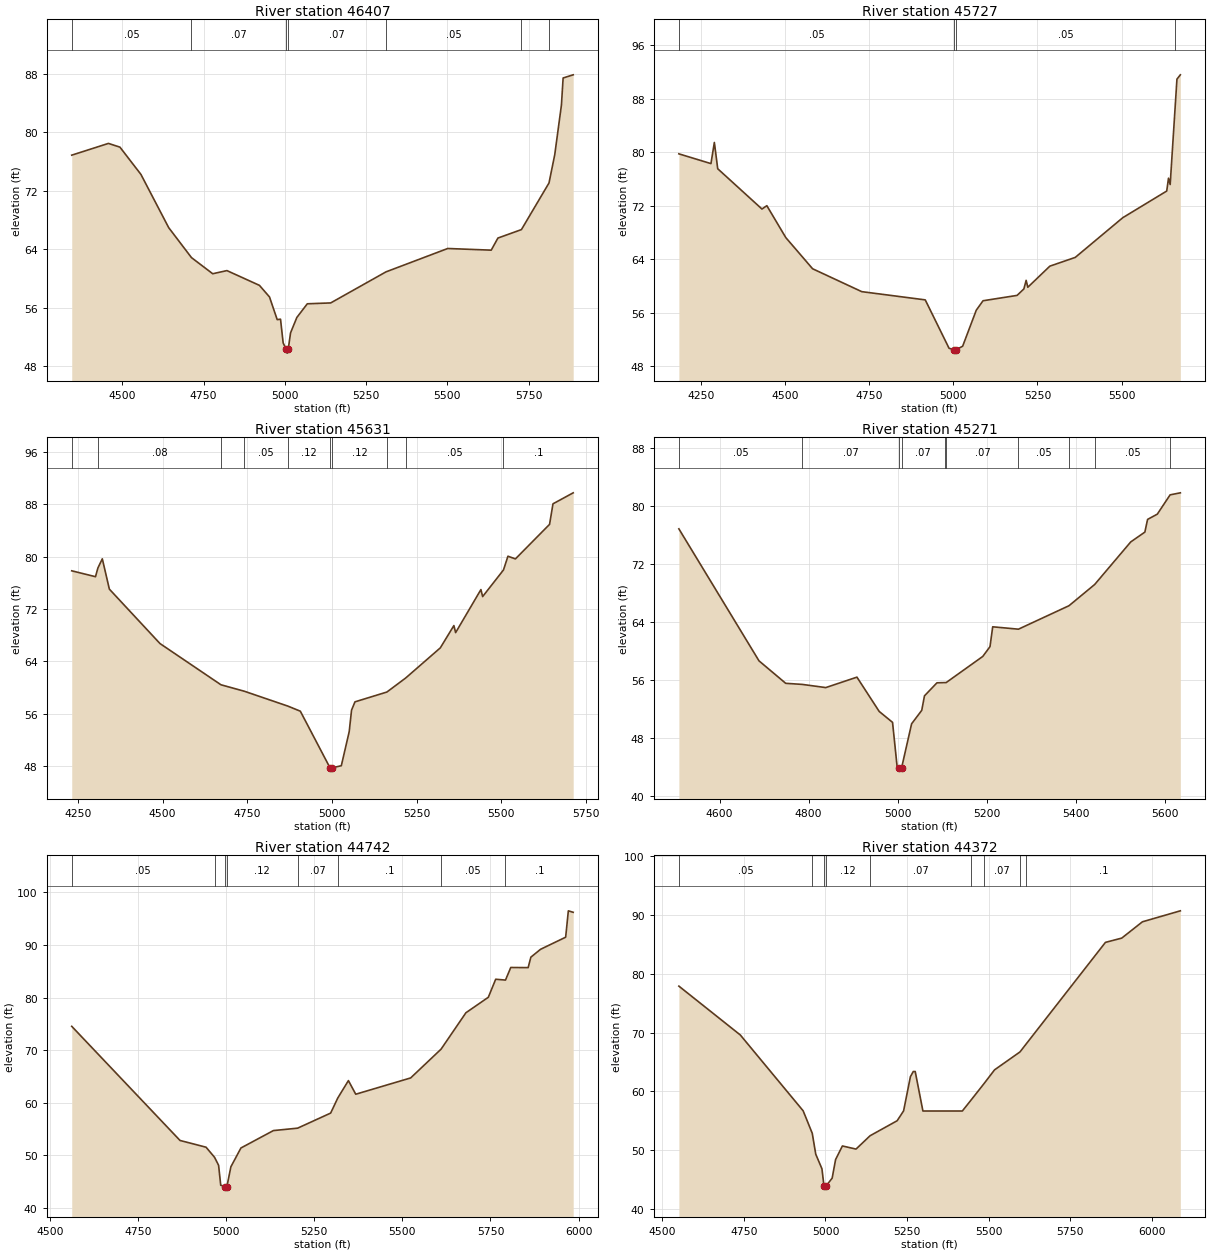
Type RM Length L Ch R = 1 ,46407   ,680,680,680
BEGIN DESCRIPTION:
HONDO CREEK 53.0
END DESCRIPTION:
XS GIS Cut Line= 3
      2394900.19      13175312.5       2394540.4     13174834.65
      2393622.56     13174614.63
#Sta/Elev= 30
  4344.8   76.88  4457.6   78.49    4493   77.98  4557.6   74.24  4642.9   66.95
    4713   62.84  4778.3   60.63    4822   61.06  4921.9   59.04  4952.9   57.45
  4976.6   54.34  4986.8    54.4  4994.9   51.15  5004.4   50.25  5007.2   49.75
  5010.4   50.25  5017.7   52.53  5036.9   54.63  5069.1   56.51  5141.1   56.63
  5311.3   60.89    5501   64.09  5634.7   63.86  5655.3   65.52  5727.6   66.68
  5812.4   73.07  5830.1   76.96  5850.6   83.75  5855.8   87.46  5886.8   87.89
#Mann= 7 ,-1 , 0
  4344.8     .05       0    4713     .07       0  5004.4     .07       0
  5010.4     .07       0  5311.3     .05       0  5727.6      .1       0
  5812.4     .05       0
Bank Sta=5004.4,5010.4
XS Rating Curve= 0 ,0
Exp/Cntr=0.3,0.1

Type RM Length L Ch R = 1 ,45727   ,96,96,96
BEGIN DESCRIPTION:
HONDO CREEK 52.0
END DESCRIPTION:
XS GIS Cut Line= 2
      2395362.05     13174034.73      2393887.73     13174246.85
#Sta/Elev= 30
    4185   79.76  4280.3    78.3  4290.4   81.46  4300.4   77.53  4431.8   71.51
  4446.3   72.01  4502.6   67.24  4582.2   62.58  4728.2   59.16  4916.8   57.93
  4987.5    50.7  5002.1   50.47  5004.8   49.97  5008.1   50.47  5027.9      51
  5068.3   56.38  5088.5    57.8  5189.6    58.6  5209.8   59.57  5216.5   60.85
  5221.5   59.82  5286.9   62.97  5362.4   64.28  5503.4   70.21  5634.1    74.2
  5639.3   76.12  5644.3   75.17  5659.7   87.24  5664.4   90.92  5674.5   91.57
#Mann= 4 ,-1 , 0
    4185     .05       0  5002.1     .04       0  5008.1     .05       0
  5659.7      .1       0
Bank Sta=5002.1,5008.1
XS Rating Curve= 0 ,0
Exp/Cntr=0.3,0.1

Type RM Length L Ch R = 1 ,45631   ,360,360,360
BEGIN DESCRIPTION:
Mapping XS 6112e3b8
END DESCRIPTION:
XS GIS Cut Line= 2
      2395327.27     13173958.35      2393858.49     13174145.85
#Sta/Elev= 30
    4232   77.83  4302.1   76.93  4309.4   78.28  4322.3   79.66  4343.1   75.03
  4492.6   66.71  4672.6   60.41  4741.7   59.42  4871.2   57.13    4907   56.37
  4994.7   47.71  4997.5   47.21  5000.7   47.71    5028   48.04  5051.3   53.25
  5058.2   56.53  5068.3    57.8  5162.6    59.3  5218.2   61.45  5320.3   66.05
  5360.4   69.46  5365.5   68.38  5440.2   74.96  5445.3   73.89  5506.8   77.96
    5520   80.06  5542.1   79.65  5642.9   84.93    5653   88.07  5712.7   89.75
#Mann= 10 ,-1 , 0
    4232     .05       0  4309.4     .08       0  4672.6     .07       0
  4741.7     .05       0  4871.2     .12       0  4994.7     .07       0
  5000.7     .12       0  5162.6     .07       0  5218.2     .05       0
  5506.8      .1       0
Bank Sta=4994.7,5000.7
XS Rating Curve= 0 ,0
Exp/Cntr=0.3,0.1

Type RM Length L Ch R = 1 ,45271   ,529,529,529
BEGIN DESCRIPTION:
HONDO CREEK 51.0
END DESCRIPTION:
XS GIS Cut Line= 3
      2395037.74     13173696.85      2394537.72     13173696.85
      2393987.73     13173996.85
#Sta/Elev= 30
  4508.6    76.9  4688.6   58.68  4748.6   55.58  4785.6   55.43  4838.6   54.99
  4908.6   56.43  4958.6    51.7  4988.6   50.19  4998.6   44.24  5003.1   43.96
  5005.9   43.46  5009.1   43.96  5031.4   49.99  5054.2   51.85  5060.3   53.85
  5088.4   55.65  5106.3   55.68  5109.2   55.69  5191.3   59.29  5207.5   60.64
  5213.6   63.38  5271.4   63.05    5385   66.29  5442.7   69.22  5523.6   75.09
  5555.4   76.45  5561.5    78.2  5583.4   78.93  5612.1   81.59  5635.1   81.87
#Mann= 10 ,-1 , 0
  4508.6     .05       0  4785.6     .07       0  5003.1     .07       0
  5009.1     .07       0  5106.3     .12       0  5109.2     .07       0
  5271.4     .05       0    5385      .1       0  5442.7     .05       0
  5612.1      .1       0
Bank Sta=5003.1,5009.1
XS Rating Curve= 0 ,0
Exp/Cntr=0.3,0.1

Type RM Length L Ch R = 1 ,44742   ,370,370,370
BEGIN DESCRIPTION:
HONDO CREEK 50.0
END DESCRIPTION:
XS GIS Cut Line= 3
      2394637.72     13172846.86      2394387.72     13173196.85
      2393637.71     13173846.86
#Sta/Elev= 30
  4562.2   74.52  4869.4    52.8  4943.2   51.52  4967.4   49.59  4978.8   48.08
  4984.9   44.28  4996.4   44.04  4999.2   43.54  5002.4   44.04  5013.7   47.79
  5042.2   51.37  5134.3   54.68    5203   55.14  5296.7   58.01    5317   60.89
  5347.1   64.19  5367.9    61.6  5523.7    64.7    5610   70.18  5680.4    77.1
    5744   80.05  5764.9   83.48  5792.7   83.32  5807.7   85.72    5857   85.69
  5864.7   87.68  5892.2   89.18  5963.4   91.48    5971    96.5  5984.8   96.22
#Mann= 8 ,-1 , 0
  4562.2     .05       0  4967.4     .12       0  4996.4     .07       0
  5002.4     .12       0    5203     .07       0    5317      .1       0
    5610     .05       0  5792.7      .1       0
Bank Sta=4996.4,5002.4
XS Rating Curve= 0 ,0
Exp/Cntr=0.3,0.1

Type RM Length L Ch R = 1 ,44372   ,417,417,417
BEGIN DESCRIPTION:
Mapping XS b008ce94
END DESCRIPTION:
XS GIS Cut Line= 3
      2394648.45     13172744.81      2393955.76     13172947.93
       2393403.7     13173546.86
#Sta/Elev= 30
  4550.9   77.87  4739.2   69.58  4931.7   56.72  4959.6    52.9  4970.3   49.36
  4989.3   46.88  4995.5   43.94  4998.2   43.44  5001.5   43.94  5020.6   45.31
    5031   48.45  5051.9   50.76  5093.6   50.23  5136.9    52.5  5219.7   55.04
  5239.4   56.71  5260.3   62.51  5269.1   63.39    5275   63.39  5298.6   56.69
  5419.4   56.69  5446.6   58.58  5484.9   61.27  5518.1   63.67    5596   66.71
  5615.8   68.12  5857.8   85.29  5907.7   86.01  5971.2   88.78  6087.3   90.64
#Mann= 9 ,-1 , 0
  4550.9     .05       0  4959.6     .12       0  4995.5     .07       0
  5001.5     .12       0  5136.9     .07       0  5446.6     .05       0
  5484.9     .07       0    5596     .05       0  5615.8      .1       0
Bank Sta=4995.5,5001.5
XS Rating Curve= 0 ,0
Exp/Cntr=0.3,0.1

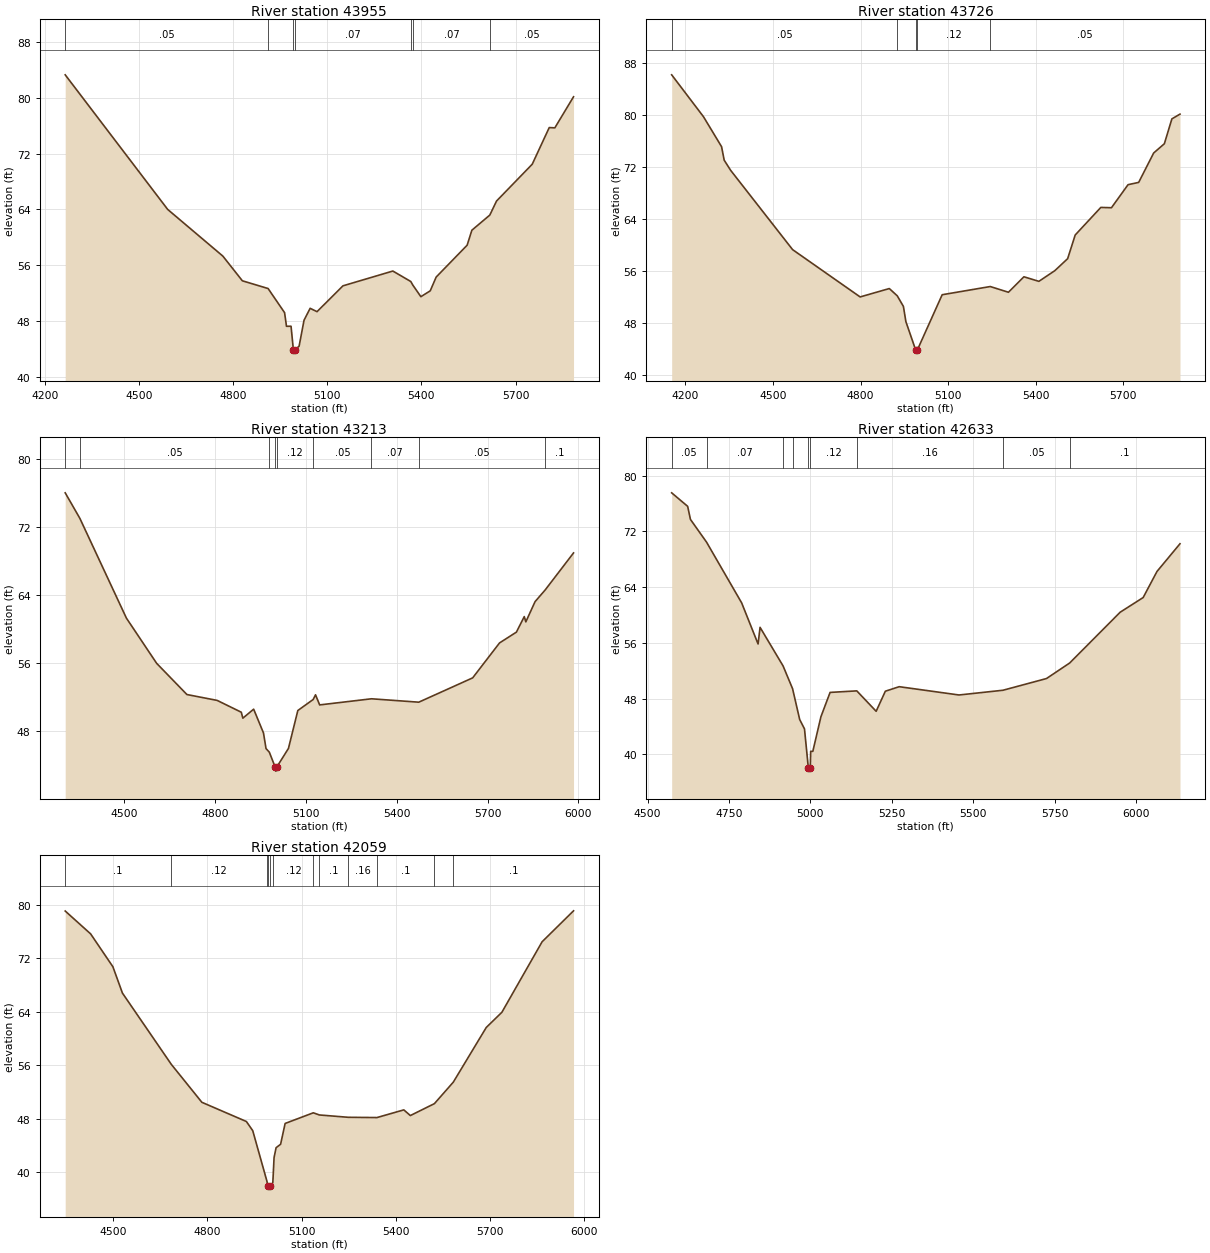
Type RM Length L Ch R = 1 ,43955   ,229,229,229
BEGIN DESCRIPTION:
HONDO CREEK 49.0
END DESCRIPTION:
XS GIS Cut Line= 3
      2394773.46      13172682.3      2393867.22     13172442.72
      2393232.27     13172192.91
#Sta/Elev= 30
  4265.1   83.32  4591.7      64  4767.5    57.3  4829.6   53.76  4911.6   52.65
  4964.1   49.19  4970.2   47.23  4984.7   47.24  4992.1   43.88  4994.8   43.38
  4998.1   43.88  5010.4   44.38  5026.1    48.1  5045.5   49.81  5067.5   49.33
  5150.2   53.04  5309.1   55.16  5366.2   53.66  5373.1   53.12  5398.4   51.48
  5428.2   52.32  5447.2    54.3  5545.8   58.87  5560.9   61.02    5618   63.19
  5639.5   65.21  5753.2   70.49  5807.4   75.75  5825.2   75.71  5884.8   80.17
#Mann= 7 ,-1 , 0
  4265.1     .05       0  4911.6     .07       0  4992.1     .07       0
  4998.1     .07       0  5366.2     .12       0  5373.1     .07       0
    5618     .05       0
Bank Sta=4992.1,4998.1
XS Rating Curve= 0 ,0
Exp/Cntr=0.3,0.1

Type RM Length L Ch R = 1 ,43726   ,513,513,513
BEGIN DESCRIPTION:
HONDO CREEK 48.0
END DESCRIPTION:
XS GIS Cut Line= 2
      2394887.76     13172546.87      2393242.51     13171974.07
#Sta/Elev= 30
  4152.8   86.18  4261.7   79.74  4323.8   75.12  4332.8   73.04  4354.9   71.48
  4567.3   59.27  4798.7   51.99  4898.7   53.28  4925.9   52.16    4947   50.53
  4955.5   48.19  4988.9   43.84  4991.7   43.34  4994.9   43.84  5079.9   52.33
  5244.6   53.59    5307   52.71    5360   55.09  5411.3   54.39  5465.8   56.03
  5509.9   57.88  5535.7   61.52  5623.6   65.77    5660   65.72  5716.9   69.27
  5753.3   69.62  5804.7   74.15  5841.3   75.57  5867.1    79.4  5894.9   80.13
#Mann= 5 ,-1 , 0
  4152.8     .05       0  4925.9     .12       0  4988.9     .07       0
  4994.9     .12       0  5244.6     .05       0
Bank Sta=4988.9,4994.9
XS Rating Curve= 0 ,0
Exp/Cntr=0.3,0.1

Type RM Length L Ch R = 1 ,43213   ,580,580,580
BEGIN DESCRIPTION:
HONDO CREEK 47.0
END DESCRIPTION:
XS GIS Cut Line= 3
      2394929.98     13171812.43      2394374.42     13171819.38
      2393284.64     13171541.73
#Sta/Elev= 30
  4304.1   76.05  4352.5   73.05  4506.4   61.31  4606.4   55.99  4706.4   52.32
  4806.4   51.63  4886.1   50.24  4891.3   49.54    4927    50.6  4959.5    47.8
  4967.9   45.96  4978.8   45.54  4997.8   43.81  5000.5   43.31  5003.8   43.81
    5042   45.98    5073   50.44  5123.8   51.74  5131.5   52.29  5145.2    51.1
  5316.5   51.82  5472.7   51.42  5650.9   54.28  5739.7   58.39  5795.4   59.66
  5821.5   61.49  5826.6   60.87  5857.2   63.25  5890.5   64.62  5984.3   68.98
#Mann= 9 ,-1 , 0
  4304.1      .1       0  4352.5     .05       0  4978.8     .12       0
  4997.8     .07       0  5003.8     .12       0  5123.8     .05       0
  5316.5     .07       0  5472.7     .05       0  5890.5      .1       0
Bank Sta=4997.8,5003.8
XS Rating Curve= 0 ,0
Exp/Cntr=0.3,0.1

Type RM Length L Ch R = 1 ,42633   ,574,574,574
BEGIN DESCRIPTION:
HONDO CREEK 46.0
END DESCRIPTION:
XS GIS Cut Line= 3
      2394887.69     13171546.83      2394537.72     13171296.85
      2393737.75     13170496.89
#Sta/Elev= 30
    4574   77.55  4623.1   75.61  4631.7   73.73    4681   70.48    4789   61.75
  4839.4   55.85  4845.5   58.24  4916.1   52.71  4945.4   49.43  4967.2   45.01
    4982   43.66  4993.7    38.1  4996.5    37.6  4999.7    38.1    5001   40.44
  5007.6   40.44  5032.4    45.4  5060.6    48.9  5142.6   49.12  5202.1   46.19
  5230.3   49.07  5272.8   49.72  5456.6   48.53  5591.7   49.21  5725.3   50.89
  5796.5   53.12  5951.6   60.41  6022.3   62.52  6064.7   66.26  6135.4   70.24
#Mann= 9 ,-1 , 0
    4574     .05       0    4681     .07       0  4916.1      .1       0
  4945.4     .12       0  4993.7     .07       0  4999.7     .12       0
  5142.6     .16       0  5591.7     .05       0  5796.5      .1       0
Bank Sta=4993.7,4999.7
XS Rating Curve= 0 ,0
Exp/Cntr=0.3,0.1

Type RM Length L Ch R = 1 ,42059   ,550,550,550
BEGIN DESCRIPTION:
HONDO CREEK 45.0
END DESCRIPTION:
XS GIS Cut Line= 3
      2394987.73      13171496.9      2394887.72     13170846.85
      2394137.69     13170246.83
#Sta/Elev= 30
  4347.6   79.07  4428.6   75.65  4499.4   70.74  4529.8    66.8  4685.3   56.15
  4782.7   50.47  4924.4    47.6  4944.6   46.23    4990   38.64  4992.2   37.99
  4994.9   37.49  4998.2   37.99  5008.5   38.43  5010.6   40.41  5012.5   42.21
  5018.9   43.68  5033.3    44.2  5047.7   47.31  5137.4    48.9  5156.6   48.58
  5248.6   48.23    5340   48.19  5425.5   49.34  5446.3   48.49  5522.9   50.27
    5583   53.48    5688   61.66  5737.7   63.93  5865.7   74.47  5965.8    79.1
#Mann= 12 ,-1 , 0
  4347.6      .1       0  4685.3     .12       0    4990     .07       0
  4992.2     .07       0  4998.2     .07       0  5010.6     .12       0
  5137.4     .16       0  5156.6      .1       0  5248.6     .16       0
    5340      .1       0  5522.9     .16       0    5583      .1       0
Bank Sta=4992.2,4998.2
XS Rating Curve= 0 ,0
Exp/Cntr=0.3,0.1