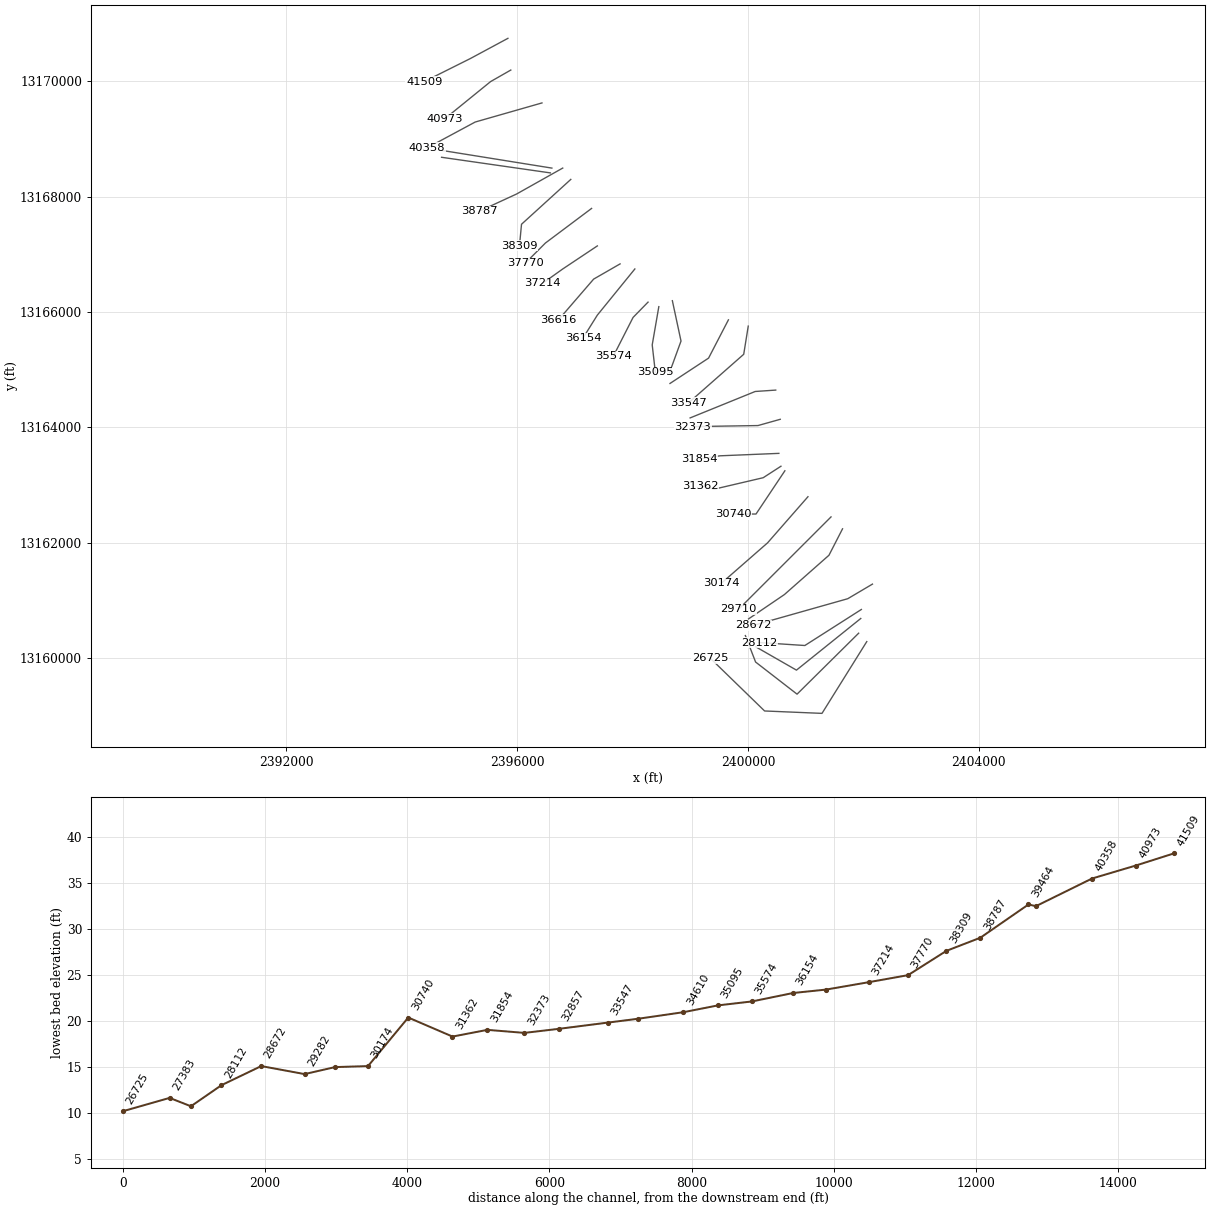
HEC-RAS study HONDO CREEK.prj: HONDO CREEK Base Level Engineering

--- HONDO CREEK.g02 (geometry) --- (continued)

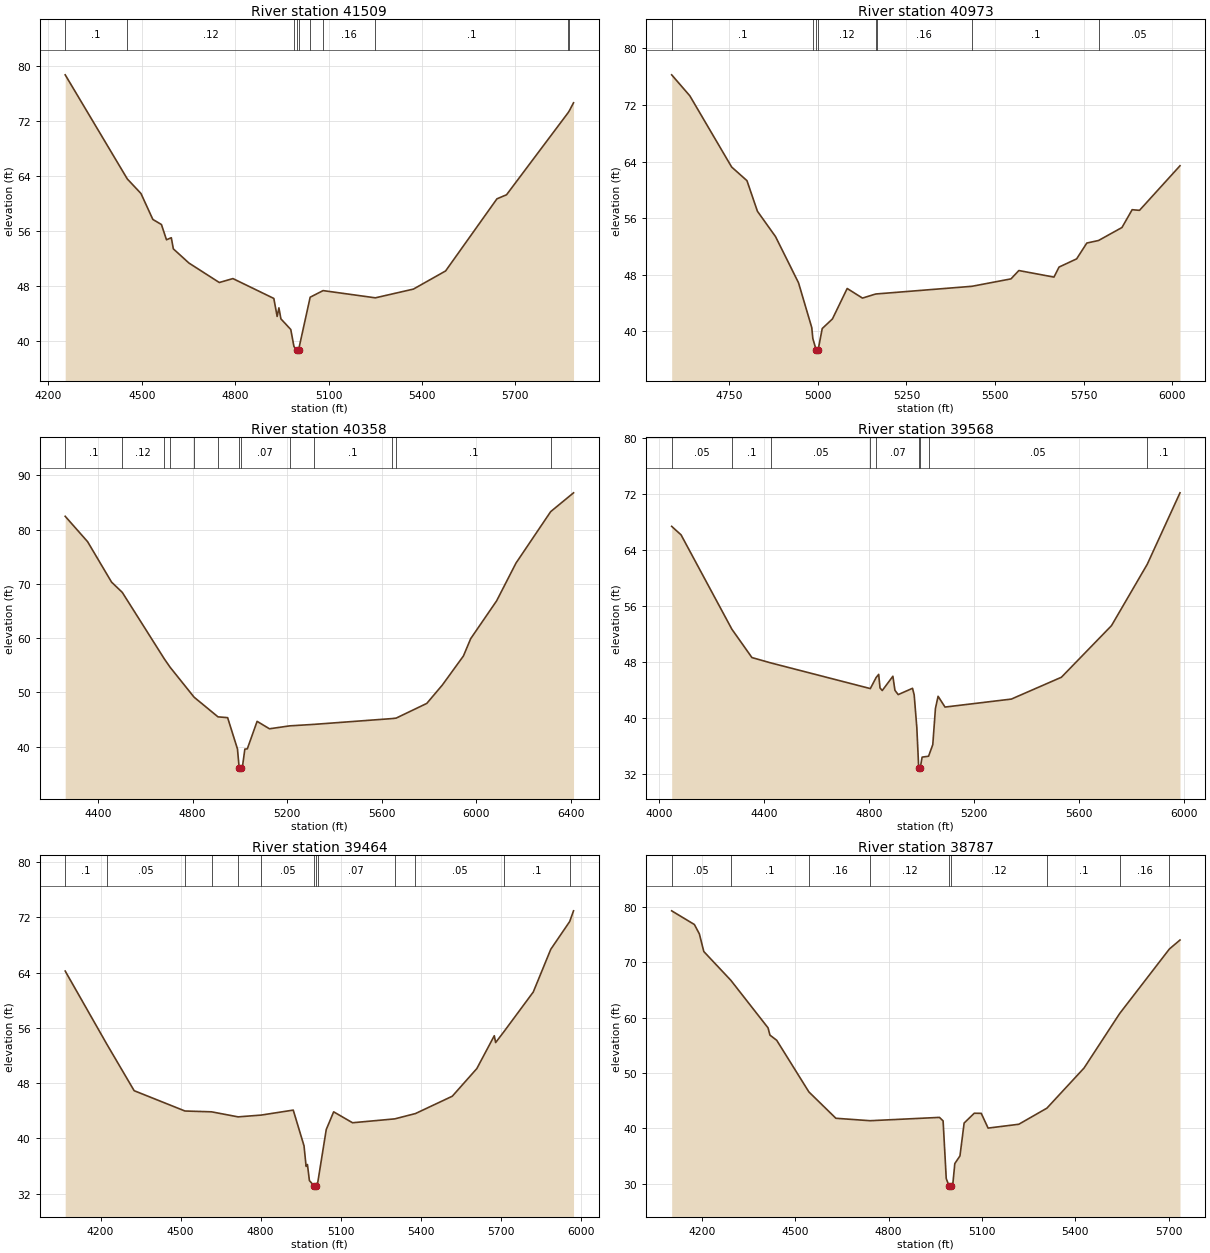
Type RM Length L Ch R = 1 ,41509   ,536,536,536
BEGIN DESCRIPTION:
HONDO CREEK 44.0
END DESCRIPTION:
XS GIS Cut Line= 3
      2395837.75     13170746.87      2395187.72     13170396.85
      2394387.72     13169996.86
#Sta/Elev= 30
  4254.1   78.71  4453.5   63.56  4497.5   61.43  4535.6   57.66  4563.2   56.92
  4579.4    54.7  4594.9      55  4601.4   53.38  4651.6   51.31    4749   48.48
  4792.8   49.05  4924.2   46.16  4934.8   43.54  4940.5   44.79  4946.9   43.19
  4978.6   41.64  4988.9   39.15  4997.8    38.7  5000.5    38.2  5003.8    38.7
  5040.9   46.34  5082.4    47.3  5250.3   46.25  5372.5   47.52  5475.9   50.16
  5640.8   60.66  5671.6   61.25  5869.3   73.19  5873.7   73.51  5886.8   74.64
#Mann= 10 ,-1 , 0
  4254.1      .1       0  4453.5     .12       0  4988.9      .1       0
  4997.8     .07       0  5003.8      .1       0  5040.9     .12       0
  5082.4     .16       0  5250.3      .1       0  5869.3     .05       0
  5873.7      .1       0
Bank Sta=4997.8,5003.8
XS Rating Curve= 0 ,0
Exp/Cntr=0.3,0.1

Type RM Length L Ch R = 1 ,40973   ,615,615,615
BEGIN DESCRIPTION:
HONDO CREEK 43.0
END DESCRIPTION:
XS GIS Cut Line= 3
      2395887.76     13170196.88      2395537.72     13169996.85
      2394737.75     13169346.88
#Sta/Elev= 30
  4587.7   76.27  4638.9    73.3  4756.9   63.22  4800.1   61.29  4829.6   56.96
  4880.7   53.37  4945.5   46.84  4982.9   40.49  4985.9   38.95    4995   37.38
  4997.8   36.88    5001   37.38  5012.4   40.36  5041.2   41.72  5082.8   46.03
  5125.9   44.67  5162.7   45.24  5166.1   45.26  5434.9   46.34  5544.9   47.39
    5567   48.57  5666.1   47.64  5680.4   49.06    5730   50.22  5758.7   52.46
  5791.8   52.82  5857.9   54.66  5886.6   57.18  5907.4   57.09  6021.6    63.4
#Mann= 8 ,-1 , 0
  4587.7      .1       0  4985.9     .12       0    4995     .07       0
    5001     .12       0  5162.7     .07       0  5166.1     .16       0
  5434.9      .1       0  5791.8     .05       0
Bank Sta=4995,5001
XS Rating Curve= 0 ,0
Exp/Cntr=0.3,0.1

Type RM Length L Ch R = 1 ,40358   ,790,790,790
BEGIN DESCRIPTION:
HONDO CREEK 42.0
END DESCRIPTION:
XS GIS Cut Line= 3
      2396428.23     13169626.67      2395270.28     13169295.15
      2394437.68     13168846.83
#Sta/Elev= 30
  4261.3   82.47    4356   77.79  4457.4   70.33  4502.7   68.44    4681   56.14
  4705.2   54.62  4806.4   49.11  4907.6   45.48  4948.3   45.33    4990   39.55
  4997.3   35.97    5000   35.47  5003.3   35.97  5010.8   36.22  5021.2   39.53
  5031.6   39.58    5073   44.65  5125.2   43.28  5211.3   43.82  5312.5   44.09
  5643.3   45.16  5661.2   45.25  5790.7   47.96  5856.5   51.35  5945.7   56.71
  5976.5   59.91    6086   66.87    6168   73.84  6314.7   83.33  6411.4    86.8
#Mann= 13 ,-1 , 0
  4261.3      .1       0  4502.7     .12       0    4681      .1       0
  4705.2     .12       0  4806.4     .05       0  4907.6     .07       0
  4997.3     .07       0  5003.3     .07       0  5211.3     .12       0
  5312.5      .1       0  5643.3     .05       0  5661.2      .1       0
  6314.7     .05       0
Bank Sta=4997.3,5003.3
XS Rating Curve= 0 ,0
Exp/Cntr=0.3,0.1

Type RM Length L Ch R = 1 ,39568   ,104,104,104
BEGIN DESCRIPTION:
HONDO CREEK 41.0
END DESCRIPTION:
XS GIS Cut Line= 2
      2396599.57     13168496.45      2394688.12     13168803.75
#Sta/Elev= 30
  4049.2   67.42  4084.9   66.21  4278.5   52.73  4354.9   48.68  4428.5    47.9
  4805.8   44.25  4827.9   45.83  4837.6   46.28  4842.7   44.34  4851.2   43.97
  4891.7   46.01  4899.5      44    4912   43.39  4966.5   44.29  4972.8   43.35
  4982.9   38.68    4990   32.96  4992.8   32.46    4996   32.96  5003.1   34.46
  5027.6   34.59  5043.7   36.25  5053.8   41.42  5063.9   43.15  5090.2   41.61
  5342.9   42.75  5533.6   45.87  5724.3   53.24  5860.4      62  5985.2   72.21
#Mann= 9 ,-1 , 0
  4049.2     .05       0  4278.5      .1       0  4428.5     .05       0
  4805.8      .1       0  4827.9     .07       0    4990     .07       0
    4996     .07       0  5027.6     .05       0  5860.4      .1       0
Bank Sta=4990,4996
XS Rating Curve= 0 ,0
Exp/Cntr=0.3,0.1

Type RM Length L Ch R = 1 ,39464   ,677,677,677
BEGIN DESCRIPTION:
HONDO CREEK 40.0
END DESCRIPTION:
XS GIS Cut Line= 2
      2396573.52     13168413.12      2394688.07     13168683.96
#Sta/Elev= 30
  4067.7   64.22  4223.9   53.62  4326.1    46.9  4516.5   43.96  4616.1   43.84
  4715.6   43.11    4802   43.37  4922.2   44.09  4962.6   38.92  4970.4   35.94
  4975.4   36.21  4982.8   33.88    5000   33.15  5002.8   32.65    5006   33.15
  5014.2   33.65  5045.9   41.28  5073.7   43.84  5144.4   42.26  5302.6   42.82
  5380.1   43.59  5518.2    46.1  5610.1    50.1  5675.6   54.86  5680.6   53.87
    5711   55.41  5821.7   61.19  5887.2   67.37  5958.1   71.39  5972.5   72.94
#Mann= 13 ,-1 , 0
  4067.7      .1       0  4223.9     .05       0  4516.5      .1       0
  4616.1     .16       0  4715.6     .12       0    4802     .05       0
    5000     .04       0    5006     .05       0  5014.2     .07       0
  5302.6     .12       0  5380.1     .05       0    5711      .1       0
  5958.1     .05       0
Bank Sta=5000,5006
XS Rating Curve= 0 ,0
Exp/Cntr=0.3,0.1

Type RM Length L Ch R = 1 ,38787   ,478,478,478
BEGIN DESCRIPTION:
HONDO CREEK 39.0
END DESCRIPTION:
XS GIS Cut Line= 3
      2396787.76     13168496.88      2395987.72     13168046.85
      2395337.74     13167746.86
#Sta/Elev= 30
  4103.1   79.27  4176.1    76.8  4192.1   75.11  4206.4   71.92  4293.4   66.72
  4412.9   58.14    4419   56.83  4440.7    55.9  4544.1   46.58  4630.9   41.82
  4740.8   41.38  4963.7   41.98  4975.5   41.35  4985.6   30.94  4995.1   29.53
  4997.8   29.03  5001.1   29.53  5007.3   30.24  5013.1   33.64  5029.7   35.03
  5043.1   40.96  5075.6   42.73  5098.1   42.71  5120.1   40.05  5218.8   40.74
  5309.2   43.65  5428.5   50.89  5542.7   60.71  5702.8   72.38  5736.9      74
#Mann= 9 ,-1 , 0
  4103.1     .05       0  4293.4      .1       0  4544.1     .16       0
  4740.8     .12       0  4995.1     .07       0  5001.1     .12       0
  5309.2      .1       0  5542.7     .16       0  5702.8      .1       0
Bank Sta=4995.1,5001.1
XS Rating Curve= 0 ,0
Exp/Cntr=0.3,0.1

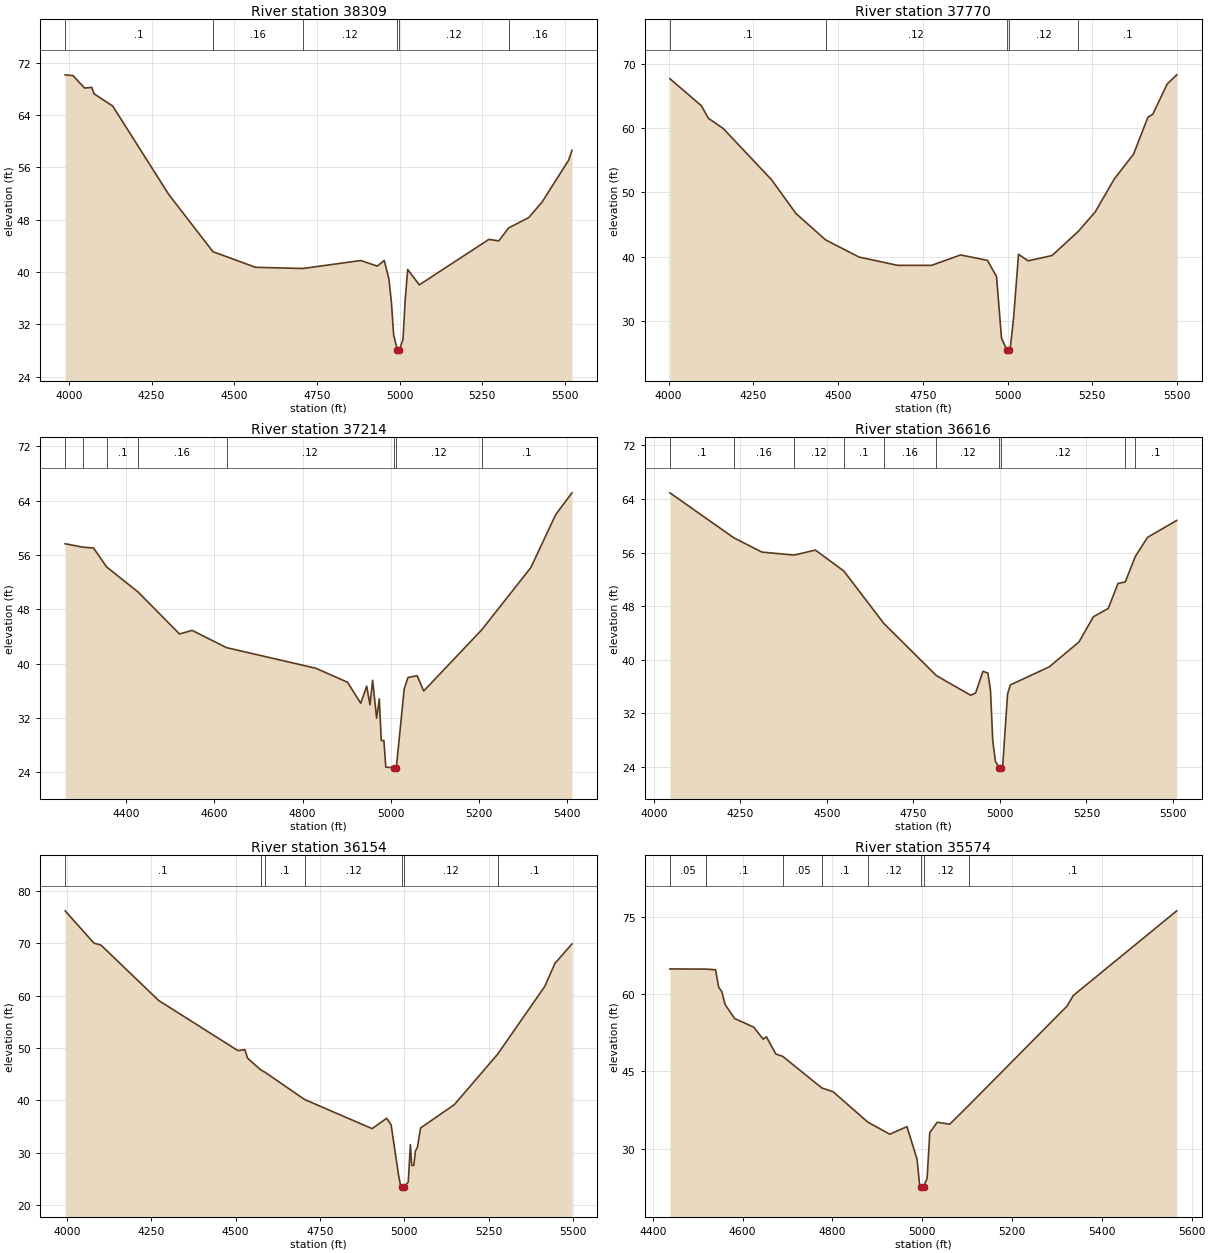
Type RM Length L Ch R = 1 ,38309   ,539,539,539
BEGIN DESCRIPTION:
HONDO CREEK 38.0
END DESCRIPTION:
XS GIS Cut Line= 3
      2396927.65     13168300.27       2396073.5      13167522.5
      2396037.72     13167146.81
#Sta/Elev= 30
  3988.7   70.15  4012.5   70.03  4047.6   68.13  4069.2   68.23    4076   67.26
  4132.7   65.37  4302.3   51.84  4435.8   43.11  4564.5   40.72  4707.4   40.54
  4882.8   41.76  4932.7    40.9  4953.7   41.77  4967.9   38.91  4975.3   35.45
  4982.1   30.42  4993.3    28.1    4996    27.6  4999.3    28.1  5010.4   29.68
  5017.2    35.8  5024.6   40.39  5059.8   38.04  5270.1   44.99  5300.3   44.77
  5329.8   46.74  5390.7   48.33  5430.8   50.68  5511.2   57.09  5521.3   58.59
#Mann= 6 ,-1 , 0
  3988.7      .1       0  4435.8     .16       0  4707.4     .12       0
  4993.3     .07       0  4999.3     .12       0  5329.8     .16       0
Bank Sta=4993.3,4999.3
XS Rating Curve= 0 ,0
Exp/Cntr=0.3,0.1

Type RM Length L Ch R = 1 ,37770   ,556,556,556
BEGIN DESCRIPTION:
HONDO CREEK 37.0
END DESCRIPTION:
XS GIS Cut Line= 3
      2397287.72     13167796.85      2396487.72     13167196.85
       2396137.7     13166846.84
#Sta/Elev= 30
  4003.9   67.72  4096.6   63.52  4117.4   61.56  4161.2   59.96  4303.9   51.97
  4375.8   46.71  4463.1   42.61  4561.2   39.94  4675.8   38.64  4775.8   38.64
  4861.2   40.26  4940.4   39.42  4967.4   36.88    4982    27.3  4997.8   25.46
  5000.5   24.96  5003.8   25.46  5007.4   25.46    5018   30.65  5032.2   40.36
  5060.5   39.34  5131.2   40.17  5208.1   43.91  5258.5   46.97    5315   52.12
  5371.6   55.97    5414   61.74  5428.2   62.18  5470.6   66.89  5498.9   68.33
#Mann= 5 ,-1 , 0
  4003.9      .1       0  4463.1     .12       0  4997.8     .07       0
  5003.8     .12       0  5208.1      .1       0
Bank Sta=4997.8,5003.8
XS Rating Curve= 0 ,0
Exp/Cntr=0.3,0.1

Type RM Length L Ch R = 1 ,37214   ,598,598,598
BEGIN DESCRIPTION:
HONDO CREEK 36.0
END DESCRIPTION:
XS GIS Cut Line= 3
      2397387.69     13167146.83      2396787.72     13166746.85
      2396437.71     13166496.85
#Sta/Elev= 30
  4260.8   57.65  4300.3   57.15  4325.4   57.02  4354.8   54.25  4426.8   50.53
  4520.7   44.37  4549.2    44.9  4627.4   42.36  4830.1   39.33  4902.2   37.27
  4932.3   34.17  4945.8   36.69  4953.3   33.94  4959.3   37.55  4968.3   31.99
  4974.4   34.82  4978.9   28.69  4984.9   28.69  4989.2   24.78  5007.1   24.69
  5009.9   24.19  5013.1   24.69    5031   36.29  5039.6   37.97  5060.5   38.23
  5075.3   35.98  5207.5   45.01  5318.6   54.14  5375.1   61.93    5412   65.14
#Mann= 8 ,-1 , 0
  4260.8      .1       0  4300.3     .16       0  4354.8      .1       0
  4426.8     .16       0  4627.4     .12       0  5007.1     .07       0
  5013.1     .12       0  5207.5      .1       0
Bank Sta=5007.1,5013.1
XS Rating Curve= 0 ,0
Exp/Cntr=0.3,0.1

Type RM Length L Ch R = 1 ,36616   ,462,462,462
BEGIN DESCRIPTION:
HONDO CREEK 35.0
END DESCRIPTION:
XS GIS Cut Line= 3
      2397781.85     13166835.02       2397323.5     13166571.11
      2396712.53     13165862.94
#Sta/Elev= 30
  4046.8   64.91  4231.5    58.2  4312.4   56.07  4405.6   55.62    4467   56.37
  4549.4   53.24  4664.6   45.43  4816.8   37.63  4915.9   34.71  4930.1   35.05
  4951.1   38.28  4965.3   38.02  4972.9   35.46  4979.5   27.93  4987.2   24.85
  4998.4   23.89  5001.2   23.39  5004.4   23.89    5008   24.06  5022.3   34.87
    5030   36.24    5143   38.96  5228.5   42.66  5270.2   46.42    5313   47.65
  5341.5    51.4  5362.3   51.61  5391.3   55.41  5426.6   58.27    5511   60.79
#Mann= 10 ,-1 , 0
  4046.8      .1       0  4231.5     .16       0  4405.6     .12       0
  4549.4      .1       0  4664.6     .16       0  4816.8     .12       0
  4998.4     .07       0  5004.4     .12       0  5362.3     .16       0
  5391.3      .1       0
Bank Sta=4998.4,5004.4
XS Rating Curve= 0 ,0
Exp/Cntr=0.3,0.1

Type RM Length L Ch R = 1 ,36154   ,580,580,580
BEGIN DESCRIPTION:
HONDO CREEK 34.0
END DESCRIPTION:
XS GIS Cut Line= 3
      2398037.74     13166746.88      2397387.72     13165946.85
      2397137.73     13165546.86
#Sta/Elev= 30
  3994.7    76.2  4080.2   70.03    4101   69.65    4272   59.07  4506.9   49.49
  4527.7   49.67  4535.6   48.05  4574.1   45.83  4587.2   45.36  4704.6   40.15
  4904.8   34.58    4948   36.56  4961.1   35.31  4983.1   25.75  4989.6   23.52
  4994.5   23.52  4997.3   23.02  5000.5   23.52  5011.9   24.37  5018.3    31.5
  5022.3   27.55  5028.5   27.55  5033.2   30.31  5039.1   30.99  5048.5   34.71
  5148.7   39.17  5276.6   48.78  5416.4   61.73  5447.1   66.19  5497.2   69.87
#Mann= 7 ,-1 , 0
  3994.7      .1       0  4574.1     .16       0  4587.2      .1       0
  4704.6     .12       0  4994.5     .07       0  5000.5     .12       0
  5276.6      .1       0
Bank Sta=4994.5,5000.5
XS Rating Curve= 0 ,0
Exp/Cntr=0.3,0.1

Type RM Length L Ch R = 1 ,35574   ,479,479,479
BEGIN DESCRIPTION:
HONDO CREEK 33.0
END DESCRIPTION:
XS GIS Cut Line= 3
      2398266.27     13166171.95      2398006.95     13165906.59
      2397663.38     13165231.52
#Sta/Elev= 30
  4438.3   64.96  4517.7   64.93  4539.9    64.8  4546.9   61.39  4554.1    60.5
  4561.1   58.05  4582.4    55.3  4624.8   53.63  4645.9   51.29  4653.1   51.75
  4674.2   48.39  4689.3   47.95    4777   41.77  4801.5   41.07  4878.8   35.15
  4927.9   32.79  4966.1   34.27  4988.6   27.93  4994.6   22.66  4997.2    22.6
    5000    22.1  5003.2    22.6    5011   24.21  5016.9   33.11  5033.5   35.12
  5061.3   34.73  5104.2   38.45  5322.7   57.74  5336.4   59.78  5566.8   76.27
#Mann= 8 ,-1 , 0
  4438.3     .05       0  4517.7      .1       0  4689.3     .05       0
    4777      .1       0  4878.8     .12       0  4997.2     .07       0
  5003.2     .12       0  5104.2      .1       0
Bank Sta=4997.2,5003.2
XS Rating Curve= 0 ,0
Exp/Cntr=0.3,0.1

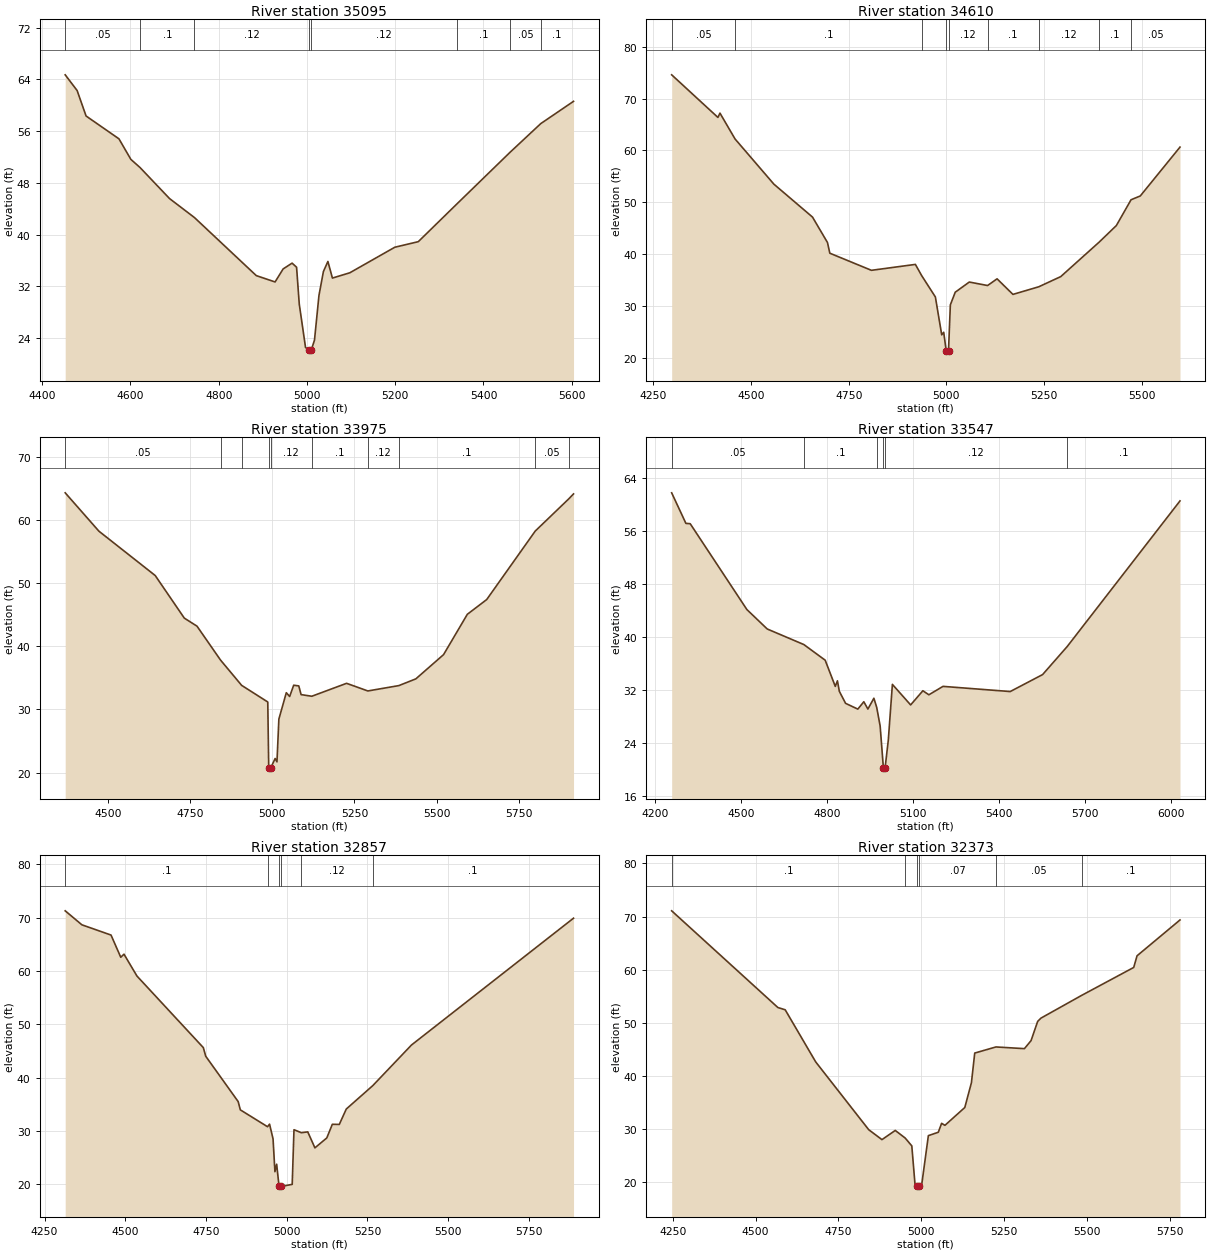
Type RM Length L Ch R = 1 ,35095   ,485,485,485
BEGIN DESCRIPTION:
HONDO CREEK 32.0
END DESCRIPTION:
XS GIS Cut Line= 3
      2398453.17      13166093.5      2398338.61     13165430.21
       2398392.8      13164954.5
#Sta/Elev= 30
  4452.2   64.72  4479.2   62.29  4499.5   58.35    4574   54.82    4601   51.64
  4621.9   50.37  4688.6   45.58  4745.1   42.64  4885.2   33.66  4927.8   32.68
    4946   34.69  4966.3   35.59  4976.5   34.96  4982.6   29.25  4996.8   22.55
  5003.9   22.17  5006.7   21.67  5009.9   22.17  5017.1   23.68  5027.2   30.58
  5037.3   34.29  5047.5   35.85  5057.7   33.28  5097.2    34.1  5199.1   38.05
  5252.3   38.91  5339.4   44.72  5460.3   52.74  5529.8   57.17  5604.1   60.62
#Mann= 8 ,-1 , 0
  4452.2     .05       0  4621.9      .1       0  4745.1     .12       0
  5003.9     .07       0  5009.9     .12       0  5339.4      .1       0
  5460.3     .05       0  5529.8      .1       0
Bank Sta=5003.9,5009.9
XS Rating Curve= 0 ,0
Exp/Cntr=0.3,0.1

Type RM Length L Ch R = 1 ,34610   ,635,635,635
BEGIN DESCRIPTION:
HONDO CREEK 31.0
END DESCRIPTION:
XS GIS Cut Line= 3
      2398687.72     13166196.84      2398837.72     13165496.85
      2398637.72     13164946.86
#Sta/Elev= 30
  4296.9   74.57  4415.3   66.36  4420.5   67.19  4459.2    62.2  4558.5    53.5
  4657.4   47.15  4695.7   42.25  4701.7   40.19  4808.2   36.89  4920.7   38.03
  4936.9   35.86  4971.9   31.75  4988.1   24.45  4993.2   24.95  4999.5   21.43
  5002.3   20.93  5005.5   21.43  5010.2   30.23  5022.7   32.67  5058.7   34.63
  5105.5   33.96  5129.8   35.25  5170.4   32.25  5236.6   33.72  5292.8   35.68
  5391.3   42.34  5435.1   45.52  5472.7   50.49  5496.3   51.22    5598   60.64
#Mann= 9 ,-1 , 0
  4296.9     .05       0  4459.2      .1       0  4936.9     .12       0
  4999.5     .07       0  5005.5     .12       0  5105.5      .1       0
  5236.6     .12       0  5391.3      .1       0  5472.7     .05       0
Bank Sta=4999.5,5005.5
XS Rating Curve= 0 ,0
Exp/Cntr=0.3,0.1

Type RM Length L Ch R = 1 ,33975   ,428,428,428
BEGIN DESCRIPTION:
HONDO CREEK 30.0
END DESCRIPTION:
XS GIS Cut Line= 3
       2399659.2     13165864.36      2399315.49     13165201.06
      2398646.88     13164761.35
#Sta/Elev= 30
  4369.8   64.34  4472.4   58.26  4643.8   51.23  4732.3   44.48    4771    43.2
  4842.7   37.82  4906.8   33.82  4986.4   31.18  4989.3   20.72    4992   20.22
  4995.3   20.72  5008.8   22.22  5014.4   21.69  5020.2   28.47  5042.8   32.65
    5053   32.05  5065.3   33.84  5080.8   33.73  5087.8   32.35  5120.4   32.09
  5226.3   34.14    5291   32.93  5385.5   33.78  5437.2   34.85  5521.5   38.69
  5593.8   45.08  5652.8   47.42  5800.6   58.28  5902.7   63.39  5917.1   64.17
#Mann= 10 ,-1 , 0
  4369.8     .05       0  4842.7      .1       0  4906.8     .12       0
  4989.3     .07       0  4995.3     .12       0  5120.4      .1       0
    5291     .12       0  5385.5      .1       0  5800.6     .05       0
  5902.7      .1       0
Bank Sta=4989.3,4995.3
XS Rating Curve= 0 ,0
Exp/Cntr=0.3,0.1

Type RM Length L Ch R = 1 ,33547   ,690,690,690
BEGIN DESCRIPTION:
HONDO CREEK 29.0
END DESCRIPTION:
XS GIS Cut Line= 3
      2400002.93     13165755.82      2399924.54      13165267.4
      2398965.72     13164423.16
#Sta/Elev= 30
    4258    61.8  4307.6   57.19  4322.6   57.14  4520.3   44.18  4591.2   41.25
  4718.9    38.9  4793.2   36.54  4828.4   32.59  4835.9   33.43  4842.5   31.85
  4864.3   30.03    4907   29.16  4927.9   30.27  4942.1   29.17    4963    30.8
  4972.8   29.43  4984.8   26.61  4996.1    20.3  4998.8    19.8  5002.1    20.3
  5013.3    24.5  5027.5   32.89  5091.1   29.79  5133.8   31.93  5154.7   31.32
    5204   32.59  5438.3   31.81  5551.2   34.37  5636.9    38.6  6030.2   60.58
#Mann= 6 ,-1 , 0
    4258     .05       0  4718.9      .1       0  4972.8     .12       0
  4996.1     .07       0  5002.1     .12       0  5636.9      .1       0
Bank Sta=4996.1,5002.1
XS Rating Curve= 0 ,0
Exp/Cntr=0.3,0.1

Type RM Length L Ch R = 1 ,32857   ,484,484,484
BEGIN DESCRIPTION:
HONDO CREEK 28.0
END DESCRIPTION:
XS GIS Cut Line= 3
      2400479.33     13164646.29      2400123.53     13164622.17
      2398995.92     13164163.89
#Sta/Elev= 30
  4314.1   71.25  4365.8   68.63    4456   66.71  4486.1   62.55  4496.1   63.13
  4536.2   59.04  4741.8   45.62  4749.2   44.01  4849.7   35.51  4856.3   33.97
  4940.5   30.81  4946.8   31.29  4957.6   28.53  4963.4   22.39  4968.8   23.79
  4976.2   19.62    4979   19.12  4982.2   19.62  5016.9   20.01  5022.4   30.25
  5045.2   29.69  5065.1   29.84  5087.2   26.85    5124   28.71  5141.1   31.26
  5162.7   31.24  5184.3   34.12  5266.4   38.51  5386.3   46.12  5887.9   69.87
#Mann= 6 ,-1 , 0
  4314.1      .1       0  4940.5     .16       0  4976.2     .07       0
  4982.2     .16       0  5045.2     .12       0  5266.4      .1       0
Bank Sta=4976.2,4982.2
XS Rating Curve= 0 ,0
Exp/Cntr=0.3,0.1

Type RM Length L Ch R = 1 ,32373   ,519,519,519
BEGIN DESCRIPTION:
HONDO CREEK 27.0
END DESCRIPTION:
XS GIS Cut Line= 3
      2400557.67     13164139.75      2400171.77     13164031.21
      2399038.08     13164013.12
#Sta/Elev= 30
  4246.4   71.08  4567.1   52.87  4589.1   52.45  4681.3   42.63  4841.3   29.87
  4881.3      28  4921.4   29.73  4951.2   28.31  4971.4   26.82  4981.4   19.33
  4988.4   19.18  4991.1   18.68  4994.4   19.18  5001.4   19.56  5021.4   28.75
  5051.4   29.39  5061.4   31.07  5071.4   30.69  5131.4   34.05  5151.4   38.72
  5161.4    44.3  5225.5   45.45  5311.4   45.13  5331.4   46.64  5351.4   50.26
  5361.4   50.88  5484.5   55.17  5641.4   60.42  5651.4   62.61  5781.1   69.36
#Mann= 6 ,-1 , 0
  4246.4      .1       0  4951.2     .07       0  4988.4     .07       0
  4994.4     .07       0  5225.5     .05       0  5484.5      .1       0
Bank Sta=4988.4,4994.4
XS Rating Curve= 0 ,0
Exp/Cntr=0.3,0.1

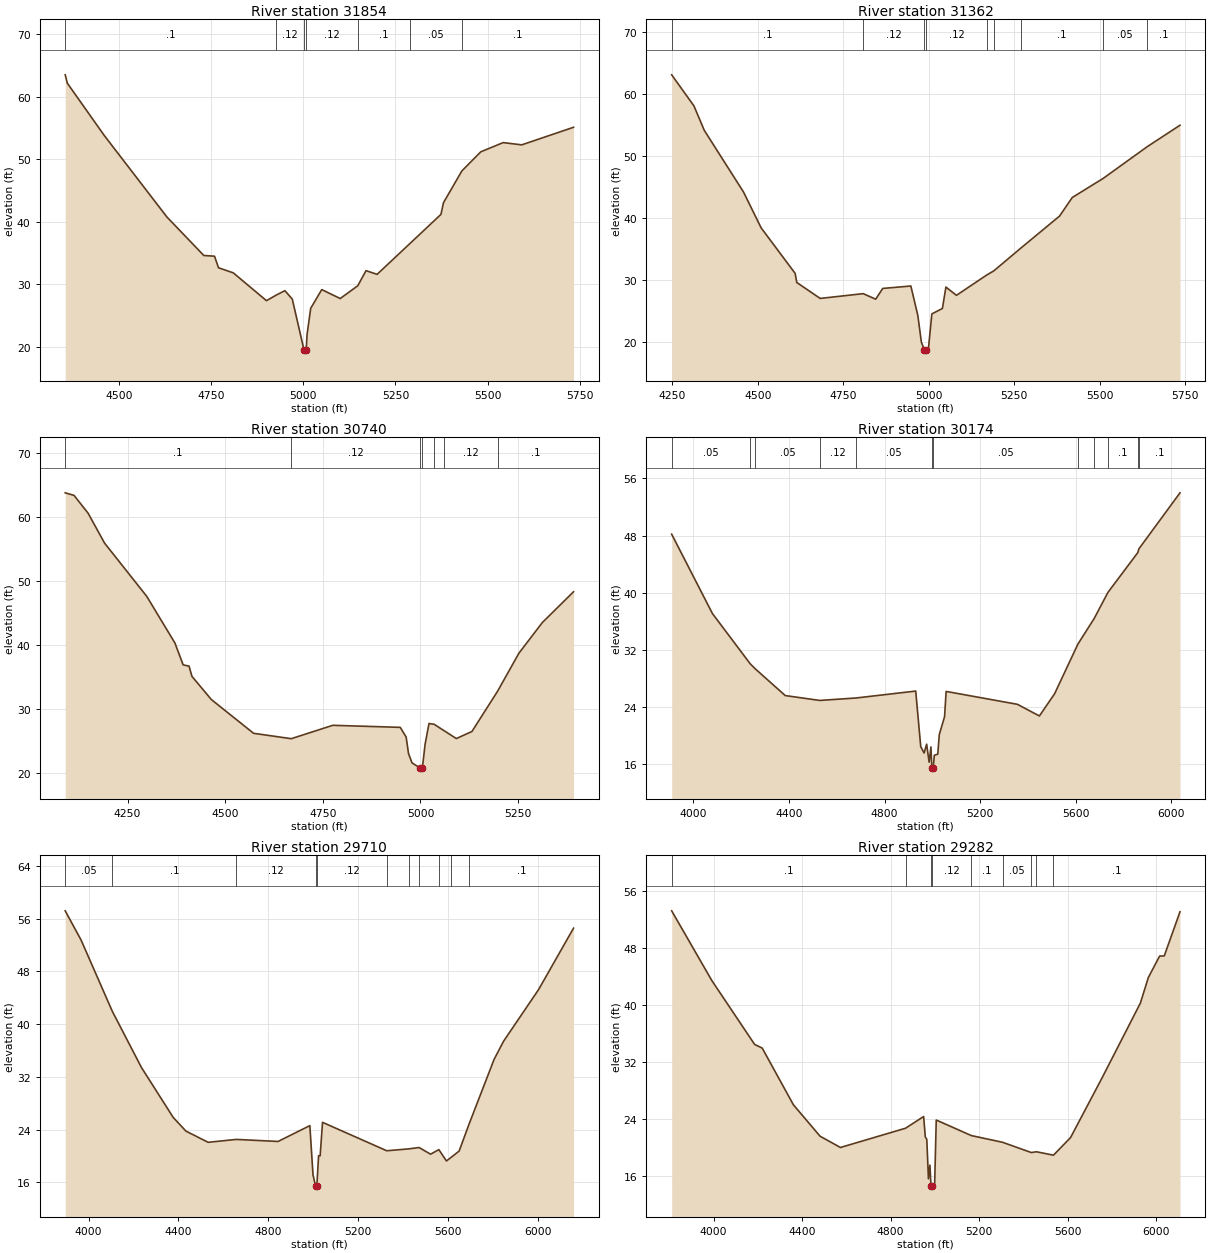
Type RM Length L Ch R = 1 ,31854   ,492,492,492
BEGIN DESCRIPTION:
HONDO CREEK 26.0
END DESCRIPTION:
XS GIS Cut Line= 3
      2400533.56      13163548.8      2399514.49     13163506.59
      2399158.75     13163452.33
#Sta/Elev= 30
  4353.6   63.52  4359.4   62.18  4459.5   53.83  4629.7   40.78  4729.8   34.63
  4758.9   34.51  4769.8   32.66  4809.8   31.85  4899.9    27.4  4925.8   28.27
  4949.9      29    4970   27.65  5001.8   19.51  5004.6   19.01  5007.8   19.51
    5010   21.94    5020   26.18    5050   29.17  5100.1   27.74  5147.9   29.79
  5170.1    32.2  5200.2   31.61  5290.8   36.62  5373.5    41.2  5380.4   43.07
  5430.3   48.15  5481.5    51.2  5542.4   52.68  5592.8   52.32  5733.4   55.13
#Mann= 7 ,-1 , 0
  4353.6      .1       0  4925.8     .12       0  5001.8     .07       0
  5007.8     .12       0  5147.9      .1       0  5290.8     .05       0
  5430.3      .1       0
Bank Sta=5001.8,5007.8
XS Rating Curve= 0 ,0
Exp/Cntr=0.3,0.1

Type RM Length L Ch R = 1 ,31362   ,622,622,622
BEGIN DESCRIPTION:
HONDO CREEK 25.0
END DESCRIPTION:
XS GIS Cut Line= 4
      2400569.75     13163325.68      2400262.22     13163126.69
      2399411.97      13162927.7      2399171.78     13162987.74
#Sta/Elev= 30
  4247.7   63.11  4312.8   58.11  4343.1   54.17  4457.9   44.23  4509.3   38.47
  4608.9   31.13  4613.7   29.66  4682.2   27.09  4807.9   27.86  4844.6   26.97
  4865.1    28.7  4947.4   29.09  4967.8   24.36  4978.1   20.07  4986.9   18.78
  4989.6   18.28  4992.9   18.78  4998.6   18.89  5008.9    24.6  5039.7   25.47
    5050   28.92  5080.8   27.59  5169.6   30.87  5190.3   31.54  5269.7   35.22
  5382.5   40.36  5419.7   43.35  5510.2   46.43  5638.8   51.53  5734.8   54.99
#Mann= 9 ,-1 , 0
  4247.7      .1       0  4807.9     .12       0  4986.9     .07       0
  4992.9     .12       0  5169.6      .1       0  5190.3     .05       0
  5269.7      .1       0  5510.2     .05       0  5638.8      .1       0
Bank Sta=4986.9,4992.9
XS Rating Curve= 0 ,0
Exp/Cntr=0.3,0.1

Type RM Length L Ch R = 1 ,30740   ,566,566,566
BEGIN DESCRIPTION:
HONDO CREEK 24.0
END DESCRIPTION:
XS GIS Cut Line= 3
      2400637.74     13163246.88      2400137.72     13162496.85
      2399737.74     13162496.85
#Sta/Elev= 30
  4090.4   63.84    4113   63.44    4149   60.66  4191.1   55.99  4299.2   47.66
  4371.4   40.36  4392.4   36.95  4407.4   36.76  4414.9   35.16  4464.5   31.54
  4572.7   26.26  4669.2   25.42  4775.5   27.51  4948.2   27.19  4963.3   25.67
  4969.3   23.11  4978.3   21.64  4998.8   20.85  5001.6   20.35  5004.8   20.85
  5011.8   24.56  5021.8   27.79  5034.9   27.67  5059.1   26.72  5091.8   25.44
  5131.8   26.55  5197.6   32.86  5251.8   38.76  5311.8   43.56  5391.8   48.38
#Mann= 7 ,-1 , 0
  4090.4      .1       0  4669.2     .12       0  4998.8     .07       0
  5004.8     .12       0  5034.9     .07       0  5059.1     .12       0
  5197.6      .1       0
Bank Sta=4998.8,5004.8
XS Rating Curve= 0 ,0
Exp/Cntr=0.3,0.1

Type RM Length L Ch R = 1 ,30174   ,464,464,464
BEGIN DESCRIPTION:
HONDO CREEK 23.0
END DESCRIPTION:
XS GIS Cut Line= 3
      2401037.74     13162796.88      2400337.72     13161996.85
      2399537.69     13161296.83
#Sta/Elev= 30
  3909.6   48.19    4080    37.1  4238.4   30.06  4259.9   29.35  4384.7   25.63
  4529.4   24.95  4682.6    25.3  4930.4   26.26  4951.3   18.49  4965.5    17.6
    4976   18.84  4986.4   16.32    4994   18.45  4997.6   15.57  5000.4   15.07
  5003.6   15.57  5008.2   17.29  5022.5   17.44  5029.1    20.2    5051   22.68
  5057.6   26.21  5355.6   24.41  5447.7   22.78  5511.3   25.89  5608.8   32.83
  5676.9   36.41  5734.3   40.05  5859.5   45.63  5863.4   46.12  6035.7   53.97
#Mann= 12 ,-1 , 0
  3909.6     .05       0  4238.4      .1       0  4259.9     .05       0
  4529.4     .12       0  4682.6     .05       0  4997.6    .035       0
  5003.6     .05       0  5608.8      .1       0  5676.9     .05       0
  5734.3      .1       0  5859.5     .05       0  5863.4      .1       0
Bank Sta=4997.6,5003.6
XS Rating Curve= 0 ,0
Exp/Cntr=0.3,0.1

Type RM Length L Ch R = 1 ,29710   ,428,428,428
BEGIN DESCRIPTION:
HONDO CREEK 22.0
END DESCRIPTION:
XS GIS Cut Line= 3
      2401437.75     13162446.88      2400637.72     13161646.85
      2399837.71     13160846.84
#Sta/Elev= 30
  3895.9   57.17  3966.6   52.74  4105.5   41.94  4235.3   33.41  4376.8   25.83
  4433.3   23.76  4532.3   22.06  4657.6    22.5  4843.5   22.19  4984.9   24.59
    4999   17.13  5010.2   15.46  5012.9   14.96  5016.2   15.46  5023.8   20.02
  5030.8   20.02  5041.4   25.09  5327.2   20.78  5424.4   21.06  5471.2   21.27
  5522.3   20.26  5559.2   20.95    5593   19.23  5615.1   19.81  5649.6   20.74
  5694.1   24.86  5805.1   34.64  5847.6   37.41  6003.1   45.22  6158.7   54.54
#Mann= 11 ,-1 , 0
  3895.9     .05       0  4105.5      .1       0  4657.6     .12       0
  5010.2     .07       0  5016.2     .12       0  5327.2     .05       0
  5424.4     .12       0  5471.2     .05       0  5559.2     .12       0
  5615.1     .05       0  5694.1      .1       0
Bank Sta=5010.2,5016.2
XS Rating Curve= 0 ,0
Exp/Cntr=0.3,0.1

Type RM Length L Ch R = 1 ,29282   ,610,610,610
BEGIN DESCRIPTION:
HONDO CREEK 21.0
END DESCRIPTION:
XS GIS Cut Line= 4
      2401637.08     13162240.23      2401401.92     13161781.97
      2400630.06     13161100.56        2400009.     13160678.47
#Sta/Elev= 30
    3811   53.23  3992.4   43.45  4185.7   34.49  4219.9   33.98  4360.7   26.03
  4481.2   21.62  4573.2   20.04    4867   22.74  4948.9   24.38  4956.4   21.52
  4963.1   21.19  4970.6   15.64  4977.3   17.57  4981.9    14.7  4984.6    14.2
  4987.9    14.7  4998.6   14.86  5005.8   23.89  5164.3   21.71  5305.2   20.77
  5435.2   19.33  5458.3   19.44  5535.1   18.96  5612.4   21.43    5757   29.94
  5927.8    40.3  5963.7   43.88  6014.5   46.88  6035.6   46.91  6106.6    53.1
#Mann= 9 ,-1 , 0
    3811      .1       0    4867     .12       0  4981.9     .07       0
  4987.9     .12       0  5164.3      .1       0  5305.2     .05       0
  5435.2      .1       0  5458.3     .05       0  5535.1      .1       0
Bank Sta=4981.9,4987.9
XS Rating Curve= 0 ,0
Exp/Cntr=0.3,0.1

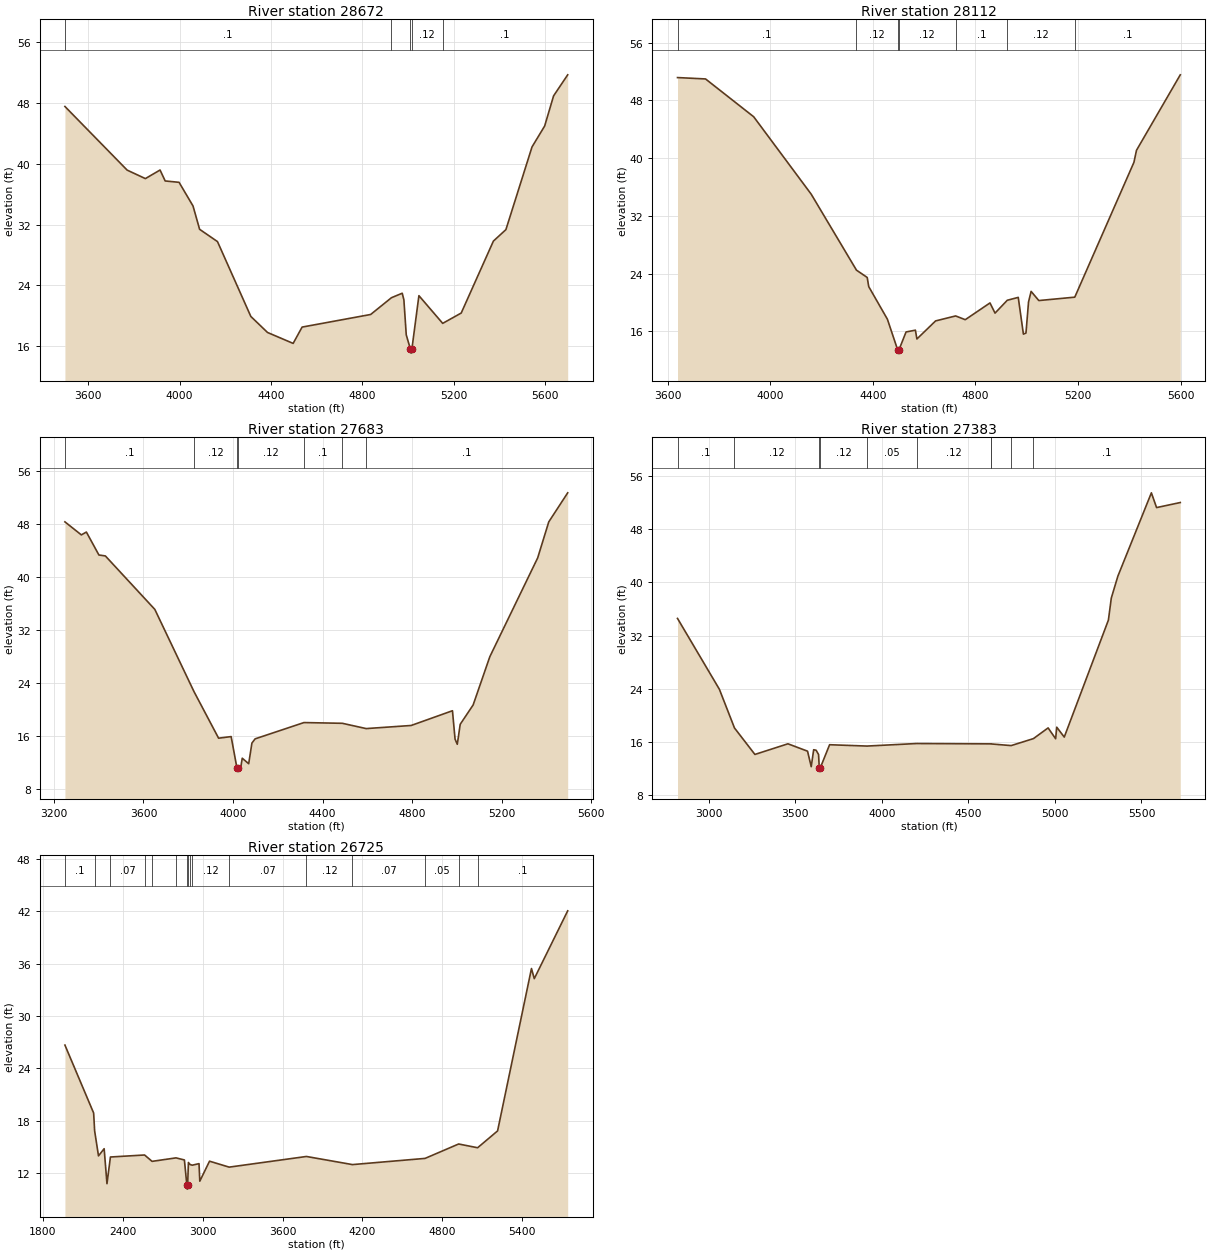
Type RM Length L Ch R = 1 ,28672   ,560,560,560
BEGIN DESCRIPTION:
HONDO CREEK 20.0
END DESCRIPTION:
XS GIS Cut Line= 3
      2402155.68     13161281.46      2401727.55      13161028.2
      2400087.34     13160563.87
#Sta/Elev= 30
    3498   47.56  3770.4   39.18  3850.4   38.06  3914.7   39.19  3937.1   37.75
  3997.9   37.57  4059.1   34.45  4087.9   31.38  4166.2   29.76  4312.3    19.9
  4385.4   17.79  4497.6   16.35  4536.8    18.5  4837.1   20.16  4928.1   22.37
  4975.3   22.96  4982.6   22.09    4993   17.47  5011.5   15.57  5014.2   15.07
  5017.5   15.57  5048.4   22.64  5152.6   18.99  5233.7   20.35  5374.7   29.83
  5429.5   31.34  5543.8   42.23  5599.2   44.99  5638.3   48.96  5700.1   51.73
#Mann= 5 ,-1 , 0
    3498      .1       0  4928.1     .12       0  5011.5     .07       0
  5017.5     .12       0  5152.6      .1       0
Bank Sta=5011.5,5017.5
XS Rating Curve= 0 ,0
Exp/Cntr=0.3,0.1

Type RM Length L Ch R = 1 ,28112   ,429,429,429
BEGIN DESCRIPTION:
Mapping XS e9d0468e
END DESCRIPTION:
XS GIS Cut Line= 3
      2401963.42     13160841.57      2400984.26     13160216.57
      2400187.38     13160268.65
#Sta/Elev= 30
  3638.2   51.15  3747.5   50.96  3935.3   45.72  4159.5      35    4336   24.48
  4377.8   23.47  4383.8    22.2  4456.5   17.69  4496.1   13.49  4498.9   12.99
  4502.1   13.49  4529.3   15.92  4565.7   16.17  4571.6   14.95  4644.4   17.45
  4722.6   18.14  4760.1   17.62  4856.5   19.94  4876.2   18.53  4923.9   20.31
  4966.7   20.71  4986.8   15.62  4996.8   15.77  5006.8   20.07  5016.8   21.54
  5046.9   20.27  5187.1   20.74  5417.7   39.41  5427.7   41.08  5598.4   51.53
#Mann= 7 ,-1 , 0
  3638.2      .1       0    4336     .12       0  4496.1     .07       0
  4502.1     .12       0  4722.6      .1       0  4923.9     .12       0
  5187.1      .1       0
Bank Sta=4496.1,4502.1
XS Rating Curve= 0 ,0
Exp/Cntr=0.3,0.1

Type RM Length L Ch R = 1 ,27683   ,300,300,300
BEGIN DESCRIPTION:
Mapping XS c5de878c
END DESCRIPTION:
XS GIS Cut Line= 3
      2401953.04     13160685.34      2400838.42     13159789.49
      2400131.36     13160195.01
#Sta/Elev= 30
  3249.5   48.38  3322.9   46.41  3345.3   46.84  3401.3   43.37  3430.1   43.23
  3650.9   35.15    3826   22.71  3935.7   15.68  3991.7   15.92  4017.5    11.2
  4020.2    10.7  4023.5    11.2  4034.9   11.31  4041.3   12.65  4070.1   11.82
  4084.5   14.94  4098.9   15.58  4316.9   18.04  4488.1   17.93  4594.8   17.13
  4795.6    17.6    4980   19.83  4991.6   15.54  5001.6   14.76  5014.6   17.78
  5072.3    20.7  5146.9      28  5360.5   42.93  5410.1   48.38  5494.6   52.77
#Mann= 7 ,-1 , 0
  3249.5      .1       0    3826     .12       0  4017.5     .07       0
  4023.5     .12       0  4316.9      .1       0  4488.1     .05       0
  4594.8      .1       0
Bank Sta=4017.5,4023.5
XS Rating Curve= 0 ,0
Exp/Cntr=0.3,0.1

Type RM Length L Ch R = 1 ,27383   ,658,658,658
BEGIN DESCRIPTION:
Mapping XS 9f20ca51
END DESCRIPTION:
XS GIS Cut Line= 4
      2401916.54     13160430.11      2400848.84     13159372.82
      2400130.09     13159930.11      2399952.99     13160388.48
#Sta/Elev= 30
  2820.7   34.58  3062.6   23.92  3149.8    18.1  3267.7   14.12  3458.6   15.72
  3571.7   14.61    3593   12.28  3607.1   14.83  3621.2   14.75  3635.3   14.11
  3639.4   12.11  3642.2   11.61  3645.4   12.11    3699   15.58  3915.1   15.38
  4201.2   15.76  4631.7   15.71  4631.9    15.7  4747.6   15.45  4876.2    16.5
    4961   18.11  5004.4   16.48  5010.8   18.22  5054.2   16.73  5309.2   34.33
  5325.8   37.63  5363.8   40.93  5557.4   53.47  5587.3   51.25  5724.2   52.01
#Mann= 10 ,-1 , 0
  2820.7      .1       0  3149.8     .12       0  3639.4     .07       0
  3645.4     .12       0  3915.1     .05       0  4201.2     .12       0
  4631.7     .05       0  4631.9      .1       0  4747.6     .05       0
  4876.2      .1       0
Bank Sta=3639.4,3645.4
XS Rating Curve= 0 ,0
Exp/Cntr=0.3,0.1

Type RM Length L Ch R = 1 ,26725   ,0,0,0
BEGIN DESCRIPTION:
HONDO CREEK 1.0
END DESCRIPTION:
XS GIS Cut Line= 4
      2402057.17     13160284.28      2401281.13     13159039.49
      2400286.34     13159081.15      2399343.67     13159997.79
#Sta/Elev= 30
    1965   26.66  2180.7   18.88  2188.2   16.83  2217.2   13.97  2259.7   14.79
  2280.9   10.78  2306.8   13.84  2563.4   14.07  2619.8   13.34  2799.4   13.74
  2862.6    13.5  2880.9   10.66  2883.6   10.16  2886.9   10.66  2892.9   13.21
  2905.3   12.98  2921.2    12.9  2972.4   13.08  2978.3   11.07  3051.4   13.36
  3198.9   12.68  3779.3    13.9  4125.3   12.97  4670.8   13.68  4923.1   15.33
  5065.7    14.9  5215.6   16.83  5470.2   35.43  5491.3   34.27  5742.4   42.04
#Mann= 16 ,-1 , 0
    1965      .1       0  2188.2     .12       0  2306.8     .07       0
  2563.4     .12       0  2619.8     .07       0  2799.4     .12       0
  2880.9     .07       0  2886.9     .12       0  2905.3     .07       0
  2921.2     .12       0  3198.9     .07       0  3779.3     .12       0
  4125.3     .07       0  4670.8     .05       0  4923.1     .07       0
  5065.7      .1       0
Bank Sta=2880.9,2886.9
XS Rating Curve= 0 ,0
Exp/Cntr=0.3,0.1