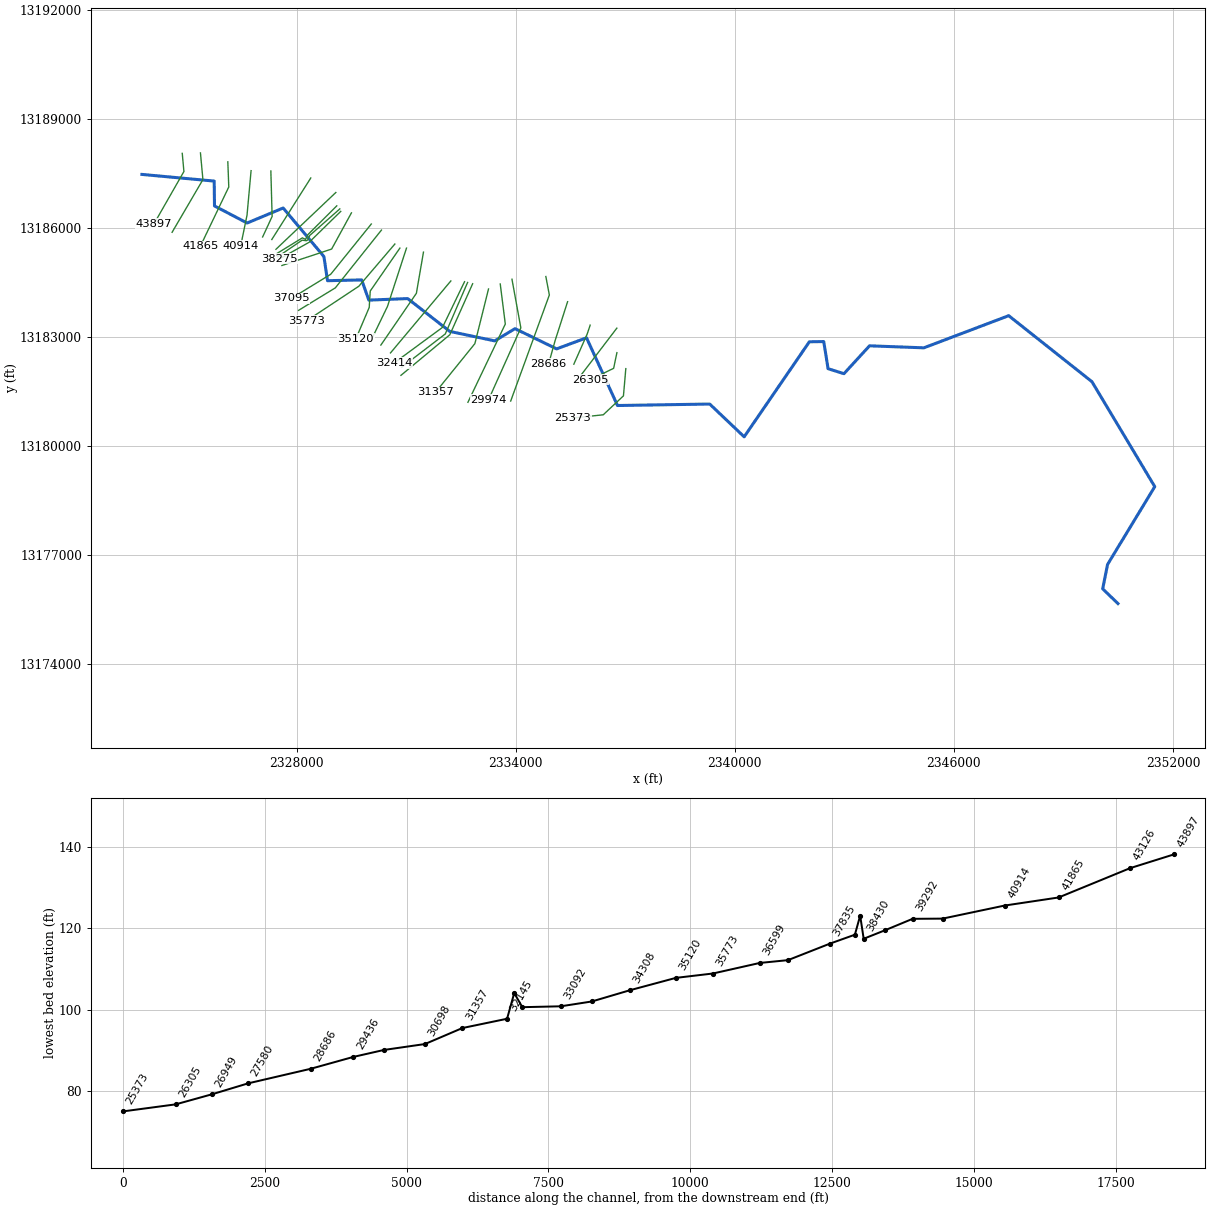
--- JAVELIN CREEK.prj (project) ---

Proj Title=JAVELIN CREEK Base Level Engineering
Current Plan=p01
Default Exp/Contr=0.3,0.1
English Units
Geom File=g01
Flow File=f01
Plan File=p01
Y Axis Title=Elevation
X Axis Title(PF)=Main Channel Distance
X Axis Title(XS)=Station
BEGIN DESCRIPTION:
JAVELIN CREEK
END DESCRIPTION:
DSS Export Rating Curves= 0
DSS Export Rating Curve Sorted= 0
DSS Export Volume Flow Curves= 0
DXF OffsetX= 0
DXF OffsetY= 0
DXF ScaleX= 1
DXF ScaleY= 10

--- JAVELIN CREEK.p01 (plan) ---

Plan Title=Multiple Run
Short Identifier=Multiple
Geom File=g01
Flow File=f01
Subcritical Flow
K Sum by GR= 0
Std Step Tol= 0.01
Critical Tol= 0.01
Num of Std Step Trials= 20
Max Error Tol= 0.3
Flow Tol Ratio= 0.001
Split Flow NTrial= 30
Split Flow Tol= 0.02
Split Flow Ratio= 0.02
Log Output Level= 0
Friction Slope Method= 1
Unsteady Friction Slope Method= 2
Unsteady Bridges Friction Slope Method= 1
Parabolic Critical Depth
Global Vel Dist=  1 , 1 , 1
Global Log Level= 0
CheckData=True
Encroach Param= -1, 0, 0, 0
BEGIN DESCRIPTION:
Multiple Run
END DESCRIPTION:

--- JAVELIN CREEK.f01 (steady flow) ---

Flow Title=Multiple
Program Version=4.10
Number of Profiles= 7
Profile Names=10-year,25-year,50-year,1pct_min,100-year,1pct_plu,500-year
River Rch & RM=JAVELIN CREEK,Reach-1         ,43897
     641     900    1114    1007    1362    1842    2044
River Rch & RM=JAVELIN CREEK,Reach-1         ,37095
     706     997    1241    1127    1524    2061    2315
River Rch & RM=JAVELIN CREEK,Reach-1         ,35120
     821    1168    1461    1334    1804    2440    2772
River Rch & RM=JAVELIN CREEK,Reach-1         ,32271
     883    1259    1578    1443    1951    2639    3008
River Rch & RM=JAVELIN CREEK,Reach-1         ,24361
     935    1339    1681    1540    2083    2817    3226
River Rch & RM=JAVELIN CREEK,Reach-1         ,21253
    1035    1489    1877    1726    2334    3157    3643
River Rch & RM=JAVELIN CREEK,Reach-1         ,19652
    1742    2555    3262    3032    4100    5545    6529
River Rch & RM=JAVELIN CREEK,Reach-1         ,15255
    1742    2552    3256    3023    4088    5529    6499
River Rch & RM=JAVELIN CREEK,Reach-1         ,12044
    2643    3930    5062    4741    6411    8670   10357
Boundary for River Rch & Prof#=JAVELIN CREEK,Reach-1         , 1
Up Type= 0
Dn Type= 3
Dn Slope=0.0035
Boundary for River Rch & Prof#=JAVELIN CREEK,Reach-1         , 2
Up Type= 0
Dn Type= 3
Dn Slope=0.0035
Boundary for River Rch & Prof#=JAVELIN CREEK,Reach-1         , 3
Up Type= 0
Dn Type= 3
Dn Slope=0.0035
Boundary for River Rch & Prof#=JAVELIN CREEK,Reach-1         , 4
Up Type= 0
Dn Type= 3
Dn Slope=0.0035
Boundary for River Rch & Prof#=JAVELIN CREEK,Reach-1         , 5
Up Type= 0
Dn Type= 3
Dn Slope=0.0035
Boundary for River Rch & Prof#=JAVELIN CREEK,Reach-1         , 6
Up Type= 0
Dn Type= 3
Dn Slope=0.0035
Boundary for River Rch & Prof#=JAVELIN CREEK,Reach-1         , 7
Up Type= 0
Dn Type= 3
Dn Slope=0.0035
DSS Import GetInterval= 0
DSS Import GetPeak= 0
DSS Import FillOption= 0

--- JAVELIN CREEK.g01 (geometry) ---

Geom Title=Existing Conditions
Program Version=4.10

River Reach=JAVELIN CREEK   ,Reach-1
Reach XY= 30
      2323757.73     13187466.82      2325736.98     13187283.48
      2325745.52     13186600.03      2326638.95     13186130.42
      2327626.46     13186543.41       2328742.1     13185209.24
      2328841.51       13184544.      2329777.12     13184565.72
      2329972.72     13184009.95      2331037.97     13184052.36
      2332190.86     13183149.61      2333422.04     13182889.22
      2333977.18      13183225.6      2335117.93     13182668.94
      2335936.36      13182973.6      2336784.91      13181111.6
      2339310.98     13181152.17      2340254.82     13180250.92
      2342040.27     13182863.95      2342434.75     13182870.56
      2342553.13     13182124.22      2342988.29     13181987.09
        2343689.     13182753.44      2345177.71     13182697.96
        2347501.     13183582.01      2349780.98     13181767.27
      2351502.64     13178880.31      2350209.24     13176740.55
      2350075.78     13176069.98      2350494.62     13175665.34

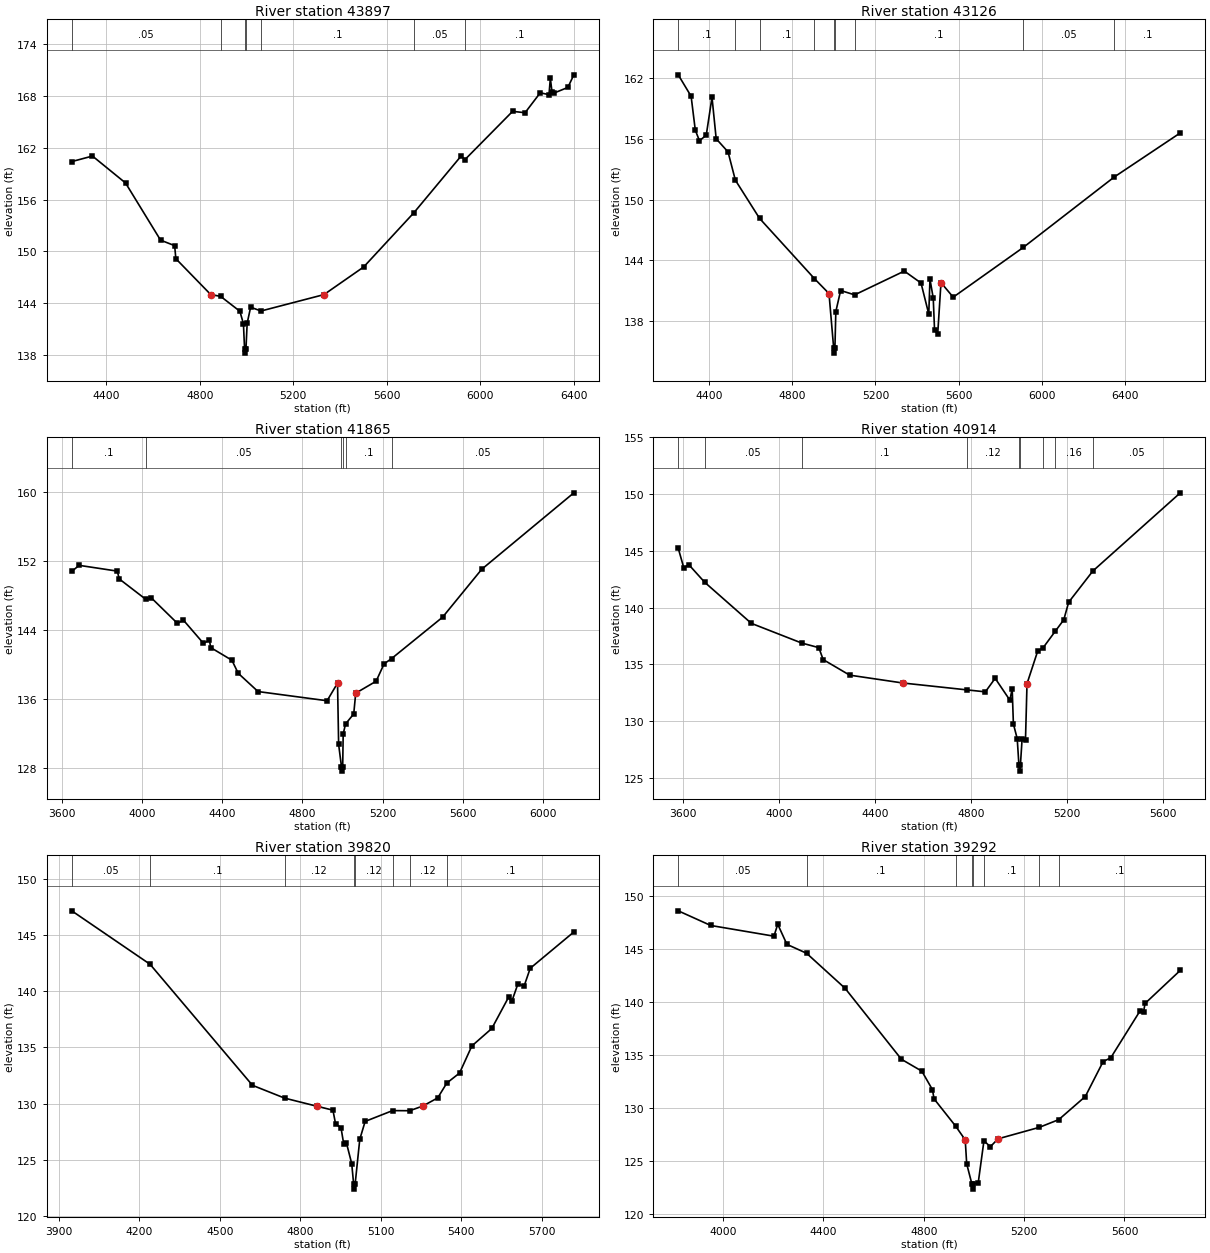
Type RM Length L Ch R = 1 ,43897   ,771,771,771
BEGIN DESCRIPTION:
JAVELIN CREEK 3.0
END DESCRIPTION:
XS GIS Cut Line= 3
      2324862.13     13188045.02      2324907.72     13187547.22
      2324092.24     13186115.79
#Sta/Elev= 30
  4252.3   160.4  4340.8  161.04  4482.3  157.92    4632   151.3  4692.3  150.66
  4697.4  149.15  4846.8  144.99  4888.8  144.79  4971.3  143.06  4986.5  141.61
  4991.3  138.71    4994  138.21  4997.3  138.71  5002.4  141.67  5017.3  143.53
  5061.6  143.09  5330.9  144.99  5500.7  148.19    5716  154.49  5917.3  161.04
  5934.3  160.64  6137.7  166.22    6191  166.06  6255.9  168.37  6293.3  168.15
  6299.1  170.04  6306.3  168.44  6314.9  168.34    6374  168.99  6399.6  170.45
#Mann= 7 ,-1 , 0
  4252.3     .05       0  4888.8     .12       0  4991.3     .07       0
  4997.3     .12       0  5061.6      .1       0    5716     .05       0
  5934.3      .1       0
Bank Sta=4846.8,5330.9
XS Rating Curve= 0 ,0
Exp/Cntr=0.3,0.1

Type RM Length L Ch R = 1 ,43126   ,1261,1261,1261
BEGIN DESCRIPTION:
Mapping XS 47144c26
END DESCRIPTION:
XS GIS Cut Line= 3
      2325360.58     13188058.48      2325428.29     13187324.13
      2324584.53      13185876.2
#Sta/Elev= 30
  4252.3  162.34  4314.2  160.22  4334.3  156.87  4354.4  155.82    4387  156.38
  4414.6  160.12  4434.7  156.02  4491.7  154.72  4526.8  151.93  4643.2  148.15
  4907.1  142.19    4977  140.72  4999.4  135.33  5002.2  134.83  5005.4  135.33
  5009.8  138.94  5032.9  141.02  5100.3  140.59    5339  142.94  5419.3  141.76
  5456.5  138.69  5462.3  142.14    5478  140.27  5484.3  137.11  5499.5  136.73
  5515.2   141.8    5574  140.36  5910.9  145.28  6348.1  152.24  6665.6   156.6
#Mann= 9 ,-1 , 0
  4252.3      .1       0  4526.8     .05       0  4643.2      .1       0
  4907.1     .12       0  4999.4     .07       0  5005.4     .12       0
  5100.3      .1       0  5910.9     .05       0  6348.1      .1       0
Bank Sta=4977,5515.2
XS Rating Curve= 0 ,0
Exp/Cntr=0.3,0.1

Type RM Length L Ch R = 1 ,41865   ,951,951,951
BEGIN DESCRIPTION:
Mapping XS 722f43d8
END DESCRIPTION:
XS GIS Cut Line= 3
      2326110.58     13187813.71      2326136.62       13187121.
      2325355.39     13185485.62
#Sta/Elev= 30
  3648.8  150.82  3685.7  151.52  3875.8  150.85  3885.8  149.94  4018.8  147.56
  4045.9  147.74    4176  144.78    4206  145.15  4306.1  142.45  4336.1  142.83
  4341.6  141.97  4447.9  140.49  4479.6  138.97  4578.4  136.85  4922.9  135.78
  4975.1  137.83  4980.6   130.7  4994.8   128.1  4997.5   127.6  5000.8   128.1
  5003.3  131.91    5015  133.08  5055.9  134.25  5065.8  136.66  5167.6  138.05
  5207.4  140.07  5244.7  140.68  5499.2  145.49  5694.9  151.07  6154.4  159.95
#Mann= 6 ,-1 , 0
  3648.8      .1       0  4018.8     .05       0  4994.8     .07       0
  5000.8     .05       0    5015      .1       0  5244.7     .05       0
Bank Sta=4975.1,5065.8
XS Rating Curve= 0 ,0
Exp/Cntr=0.3,0.1

Type RM Length L Ch R = 1 ,40914   ,1094,1094,1094
BEGIN DESCRIPTION:
Mapping XS 63772288
END DESCRIPTION:
XS GIS Cut Line= 3
      2326747.64     13187570.12      2326636.53      13186347.9
      2326463.03     13185501.25
#Sta/Elev= 30
  3580.8  145.23  3604.2  143.49  3624.2   143.8  3690.8  142.24  3885.3  138.62
  4094.5  136.89  4166.5  136.48  4184.5  135.43  4294.9  134.06  4515.8  133.37
  4784.5  132.76  4860.2  132.59    4901  133.78  4962.2  131.86  4971.9  132.86
    4977  129.76  4992.9  128.47  5000.1  126.11  5002.8  125.61  5006.1  126.11
  5013.3  128.46  5027.4  128.39  5033.7  133.31  5077.9  136.16  5101.4  136.49
  5151.2  137.92  5186.8  138.93  5207.2  140.48  5308.1  143.23  5672.3  150.11
#Mann= 9 ,-1 , 0
  3580.8      .1       0  3690.8     .05       0  4094.5      .1       0
  4784.5     .12       0  5000.1     .07       0  5006.1     .12       0
  5101.4      .1       0  5151.2     .16       0  5308.1     .05       0
Bank Sta=4515.8,5033.7
XS Rating Curve= 0 ,0
Exp/Cntr=0.3,0.1

Type RM Length L Ch R = 1 ,39820   ,528,528,528
BEGIN DESCRIPTION:
Mapping XS 25162266
END DESCRIPTION:
XS GIS Cut Line= 3
       2327289.4     13187560.19      2327324.12     13186310.24
      2327063.69     13185745.97
#Sta/Elev= 30
  3947.7  147.13  4239.5  142.38  4621.3  131.62  4741.3  130.48  4861.4  129.76
  4921.4  129.41  4931.4  128.17  4951.4  127.86  4961.4  126.43  4971.4  126.53
  4991.4  124.66  4998.4  122.89  5001.2  122.39  5004.4  122.89  5021.5  126.82
  5041.5  128.41  5143.8  129.37  5207.5  129.36  5256.9  129.78    5312   130.5
    5346  131.82  5393.5  132.71  5439.4  135.12  5513.7  136.67  5576.3  139.45
  5588.1  139.07    5611  140.63    5634  140.43  5656.9  142.02  5819.6  145.25
#Mann= 8 ,-1 , 0
  3947.7     .05       0  4239.5      .1       0  4741.3     .12       0
  4998.4     .07       0  5004.4     .12       0  5143.8      .1       0
  5207.5     .12       0    5346      .1       0
Bank Sta=4861.4,5256.9
XS Rating Curve= 0 ,0
Exp/Cntr=0.3,0.1

Type RM Length L Ch R = 1 ,39292   ,483,483,483
BEGIN DESCRIPTION:
Mapping XS f656a872
END DESCRIPTION:
XS GIS Cut Line= 2
      2328383.17      13187369.3      2327315.42     13185676.52
#Sta/Elev= 30
  3821.1  148.57  3950.6  147.19  4202.5  146.18  4217.8   147.3  4254.3  145.41
  4332.7  144.57  4486.1  141.27  4710.7  134.58  4792.1  133.46  4834.5  131.71
  4840.8  130.85  4926.8  128.28  4965.1  126.98    4971  124.72  4991.5  122.84
  4994.2  122.34  4997.5  122.84  5016.9  122.93  5039.7  126.89  5065.4  126.34
  5095.8  127.08  5260.1  128.16  5337.9  128.89  5443.8  131.07  5514.8  134.36
  5545.3  134.72  5660.7  139.09    5676  139.06  5681.9  139.84  5822.5  142.96
#Mann= 8 ,-1 , 0
  3821.1     .05       0  4332.7      .1       0  4926.8     .12       0
  4991.5     .07       0  4997.5     .12       0  5039.7      .1       0
  5260.1     .12       0  5337.9      .1       0
Bank Sta=4965.1,5095.8
XS Rating Curve= 0 ,0
Exp/Cntr=0.3,0.1

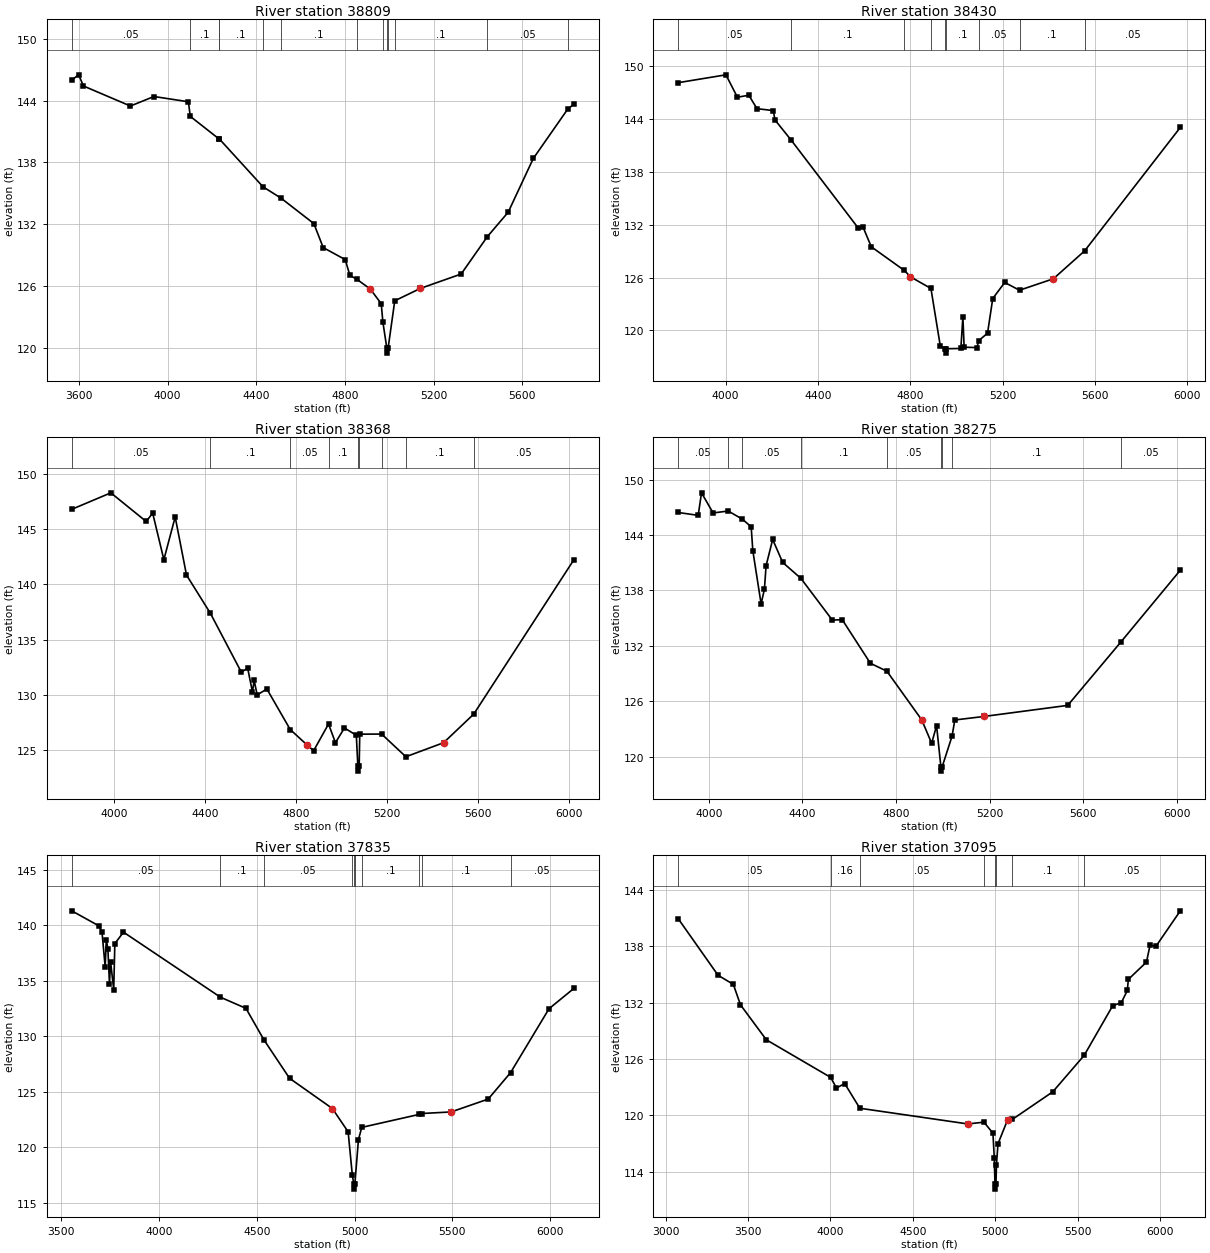
Type RM Length L Ch R = 1 ,38809   ,379,379,379
BEGIN DESCRIPTION:
Mapping XS c052d1e4
END DESCRIPTION:
XS GIS Cut Line= 2
      2329068.91     13186969.96      2327428.31     13185407.48
#Sta/Elev= 30
  3567.5  145.99  3598.7  146.49  3620.1  145.41  3832.1  143.47  3938.4  144.39
  4093.9  143.88  4102.1  142.47  4232.1  140.28  4233.9  140.27  4430.3  135.65
  4512.3  134.54    4660  132.08  4702.1  129.76  4801.2   128.6  4822.6  127.07
    4854  126.69  4914.4  125.75  4963.9  124.33  4971.5  122.53  4989.1  120.04
  4991.8  119.54  4995.1  120.04    5025  124.61  5140.9  125.81  5324.6   127.2
  5442.8  130.82  5536.9  133.19  5650.1  138.39  5805.5  143.17  5833.1  143.65
#Mann= 13 ,-1 , 0
  3567.5     .05       0  4102.1      .1       0  4232.1     .05       0
  4233.9      .1       0  4430.3     .05       0  4512.3      .1       0
    4854     .12       0  4971.5     .05       0  4989.1    .035       0
  4995.1     .05       0    5025      .1       0  5442.8     .05       0
  5805.5      .1       0
Bank Sta=4914.4,5140.9
XS Rating Curve= 0 ,0
Exp/Cntr=0.3,0.1

Type RM Length L Ch R = 1 ,38430   ,62,62,62
BEGIN DESCRIPTION:
Mapping XS 5f412f8c
END DESCRIPTION:
XS GIS Cut Line= 5
      2329094.93     13186601.88      2328298.08     13185805.03
      2328240.79     13185680.03      2328152.25      13185721.7
      2327461.12     13185295.59
#Sta/Elev= 30
  3794.7  148.13  4001.3  149.02  4050.8  146.48  4100.3   146.7  4135.7  145.18
  4206.4  144.96  4213.5   143.9    4284   141.6  4574.1  131.63  4595.3  131.72
  4630.7   129.5  4774.1  126.81  4800.4  126.09    4889  124.77  4929.8  118.19
  4949.6  117.93  4952.4  117.43  4955.6  117.93  5018.6  117.96  5027.3  121.54
  5032.8   118.1  5088.5  118.06  5095.8  118.85  5134.1  119.69  5156.7  123.63
  5208.6  125.45  5272.6  124.57  5419.2  125.87  5554.7  129.04  5968.9  143.05
#Mann= 9 ,-1 , 0
  3794.7     .05       0    4284      .1       0  4774.1     .05       0
    4889      .1       0  4949.6     .07       0  4955.6      .1       0
  5095.8     .05       0  5272.6      .1       0  5554.7     .05       0
Bank Sta=4800.4,5419.2
XS Rating Curve= 0 ,0
Exp/Cntr=0.3,0.1

Type RM Length L Ch R = 1 ,38368   ,93,93,93
BEGIN DESCRIPTION:
Mapping XS ec314eb5
END DESCRIPTION:
XS GIS Cut Line= 6
       2329178.3     13186518.58      2328355.37     13185789.41
      2328303.29     13185664.41      2328256.41     13185643.57
      2328147.04      13185659.2      2327475.92     13185201.38
#Sta/Elev= 30
  3813.9  146.79  3985.8  148.28  4141.4  145.69  4169.8  146.45  4219.1  142.24
  4268.9   146.1  4318.7  140.85  4423.9  137.39  4559.5  132.09    4588  132.42
  4608.9  130.28  4616.3  131.33  4629.8  130.02  4672.4  130.55  4775.1  126.89
  4849.8  125.48  4878.2  124.98  4943.7  127.39    4974   125.7  5013.7  127.03
  5065.9  126.37  5072.5  123.63  5075.3  123.13  5078.5  123.63    5081  126.47
  5177.2  126.48  5283.9  124.43  5450.1   125.7  5582.8  128.29    6023  142.23
#Mann= 9 ,-1 , 0
  3813.9     .05       0  4423.9      .1       0  4775.1     .05       0
  4943.7      .1       0  5072.5     .07       0  5078.5      .1       0
  5177.2     .05       0  5283.9      .1       0  5582.8     .05       0
Bank Sta=4849.8,5450.1
XS Rating Curve= 0 ,0
Exp/Cntr=0.3,0.1

Type RM Length L Ch R = 1 ,38275   ,440,440,440
BEGIN DESCRIPTION:
Mapping XS 63c3457f
END DESCRIPTION:
XS GIS Cut Line= 3
      2329204.32     13186450.86      2328339.75     13185601.91
      2327527.21     13185143.55
#Sta/Elev= 30
  3869.8  146.44  3955.1  146.13  3969.2  148.57  4018.8  146.39  4083.2   146.6
  4143.6  145.72  4181.4  144.89  4188.4   142.3  4223.8  136.54    4238  138.15
    4245  140.67  4273.2  143.52  4315.7  141.04  4393.9   139.3  4527.8  134.79
  4570.3  134.83  4690.6  130.11  4761.1  129.25  4909.7  123.99  4952.2  121.45
  4973.3  123.35  4991.6  118.93  4994.3  118.43  4997.6  118.93  5039.4  122.22
  5051.2  123.97  5175.7  124.35  5533.4  125.55  5760.4  132.41  6014.4  140.19
#Mann= 9 ,-1 , 0
  3869.8     .05       0  4083.2      .1       0  4143.6     .05       0
  4393.9      .1       0  4761.1     .05       0  4991.6    .035       0
  4997.6     .05       0  5039.4      .1       0  5760.4     .05       0
Bank Sta=4909.7,5175.7
XS Rating Curve= 0 ,0
Exp/Cntr=0.3,0.1

Type RM Length L Ch R = 1 ,37835   ,740,740,740
BEGIN DESCRIPTION:
Mapping XS 62f72f17
END DESCRIPTION:
XS GIS Cut Line= 3
      2329495.99     13186409.18      2328954.33     13185414.41
      2327592.06     13184962.05
#Sta/Elev= 30
  3553.8  141.29  3693.1  139.93  3708.6  139.35  3724.7  136.23  3730.4   138.7
  3738.6  137.84  3746.6  134.74  3752.3   136.7  3768.4   134.2  3774.1  138.34
  3818.3  139.37  4314.4  133.51  4444.6  132.51  4536.8  129.67  4667.8  126.21
  4886.7  123.49  4967.4  121.39  4988.7  117.52    4996  116.73  4998.8  116.23
    5002  116.73  5020.1  120.69  5037.1  121.79  5328.7  122.95  5344.3  123.04
  5494.3  123.18  5683.9  124.34  5797.9  126.71  5995.2  132.48  6121.9   134.3
#Mann= 10 ,-1 , 0
  3553.8     .05       0  4314.4      .1       0  4536.8     .05       0
  4988.7     .12       0    4996     .07       0    5002     .12       0
  5037.1      .1       0  5328.7     .16       0  5344.3      .1       0
  5797.9     .05       0
Bank Sta=4886.7,5494.3
XS Rating Curve= 0 ,0
Exp/Cntr=0.3,0.1

Type RM Length L Ch R = 1 ,37095   ,496,496,496
BEGIN DESCRIPTION:
Mapping XS ec59210d
END DESCRIPTION:
XS GIS Cut Line= 3
      2330041.11     13186103.61      2328930.02      13184721.7
       2327846.7     13184055.04
#Sta/Elev= 30
  3076.5  140.91  3317.9   134.9  3410.7  133.93  3453.9  131.76  3610.7  128.04
    4001  124.04  4036.3  122.91    4086  123.39  4177.8  120.76    4833  119.09
  4930.7  119.28  4985.2  118.11  4993.3  115.49  4997.6  112.66  5000.3  112.16
  5003.6  112.66  5006.5  114.75    5016  116.99    5074  119.52  5102.6  119.57
  5348.4  122.51  5538.5  126.38  5711.7  131.66  5763.8  131.99  5800.5  133.28
  5806.4  134.46  5916.5   136.3  5937.7  138.07  5974.4  137.99  6121.7  141.75
#Mann= 8 ,-1 , 0
  3076.5     .05       0    4001     .16       0  4177.8     .05       0
  4930.7     .12       0  4997.6     .07       0  5003.6     .12       0
  5102.6      .1       0  5538.5     .05       0
Bank Sta=4833,5074
XS Rating Curve= 0 ,0
Exp/Cntr=0.3,0.1

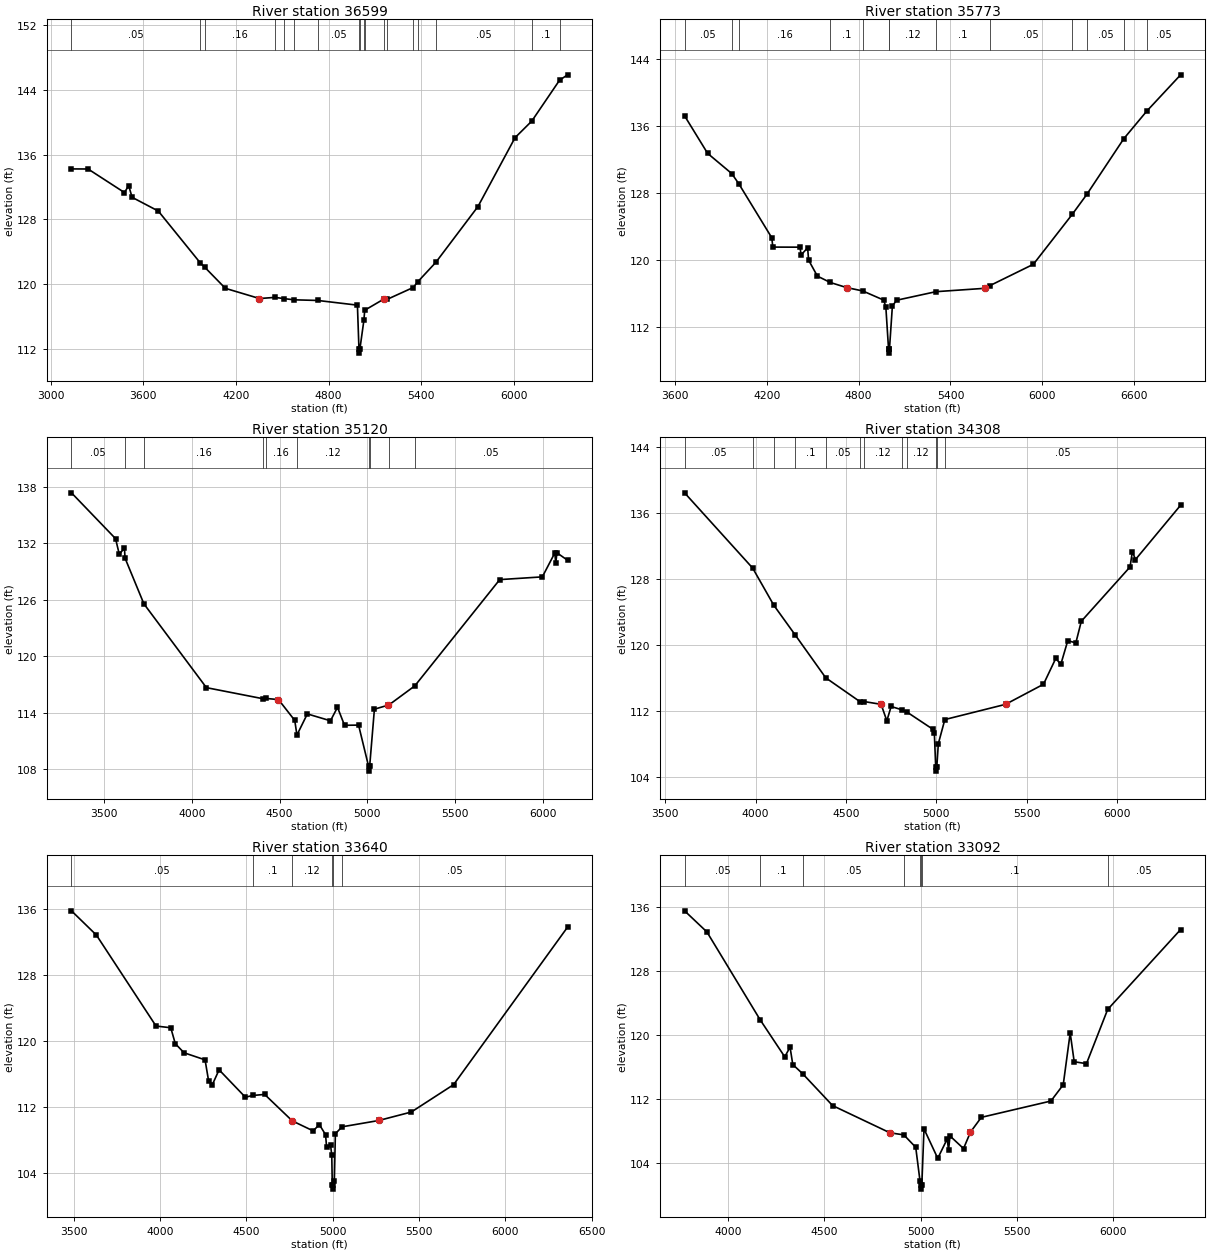
Type RM Length L Ch R = 1 ,36599   ,826,826,826
BEGIN DESCRIPTION:
Mapping XS 8fea4ff4
END DESCRIPTION:
XS GIS Cut Line= 3
      2330318.93     13185936.99      2329055.02      13184346.7
      2328048.05     13183728.63
#Sta/Elev= 30
  3134.1  134.24  3241.7  134.23  3477.2  131.32  3504.7  132.17  3526.8  130.73
  3696.6  129.03  3968.6  122.62  3996.2  122.11  4130.7  119.48  4351.8  118.22
  4453.2  118.36  4513.3   118.2    4577  118.06  4729.2  117.98  4986.2   117.4
  4996.2  111.97    4999  111.47  5002.2  111.97  5028.2  115.54  5033.4  116.77
  5159.7  118.18  5180.4  118.13  5347.4  119.58  5378.6  120.32  5493.6  122.68
    5767  129.59  6007.1   138.1  6115.5  140.15  6295.3   145.2    6347  145.87
#Mann= 18 ,-1 , 0
  3134.1     .05       0  3968.6      .1       0  3996.2     .16       0
  4453.2     .05       0  4513.3      .1       0    4577     .16       0
  4729.2     .05       0  4996.2    .035       0  5002.2     .05       0
  5028.2     .12       0  5033.4     .05       0  5159.7     .16       0
  5180.4      .1       0  5347.4     .05       0  5378.6      .1       0
  5493.6     .05       0  6115.5      .1       0  6295.3     .05       0
Bank Sta=4351.8,5159.7
XS Rating Curve= 0 ,0
Exp/Cntr=0.3,0.1

Type RM Length L Ch R = 1 ,35773   ,653,653,653
BEGIN DESCRIPTION:
Mapping XS 97cf5e91
END DESCRIPTION:
XS GIS Cut Line= 3
      2330685.26     13185551.59      2329699.12     13184391.84
      2328269.62     13183441.15
#Sta/Elev= 30
  3663.7  137.18  3814.3   132.7  3971.8  130.29  4017.6  129.08  4233.3  122.63
  4239.9  121.52  4417.8  121.51  4424.4  120.58  4467.2  121.43  4473.8  119.96
  4530.9  118.06  4614.8   117.3    4722  116.69  4826.9  116.29  4963.6   115.2
  4977.9  114.39  4995.7  109.37  4998.5  108.87  5001.7  109.37  5020.7  114.49
  5048.2  115.18  5304.9   116.2  5622.7   116.6  5654.9   116.9  5941.4  119.47
  6194.9  125.42  6290.5  127.81  6531.8  134.45  6681.8  137.74  6902.8  142.07
#Mann= 13 ,-1 , 0
  3663.7     .05       0  3971.8      .1       0  4017.6     .16       0
  4614.8      .1       0  4826.9     .12       0  4995.7     .07       0
  5001.7     .12       0  5304.9      .1       0  5654.9     .05       0
  6194.9      .1       0  6290.5     .05       0  6531.8      .1       0
  6681.8     .05       0
Bank Sta=4722,5622.7
XS Rating Curve= 0 ,0
Exp/Cntr=0.3,0.1

Type RM Length L Ch R = 1 ,35120   ,812,812,812
BEGIN DESCRIPTION:
Mapping XS 0d8be35a
END DESCRIPTION:
XS GIS Cut Line= 4
       2330824.1     13185440.42      2330011.62     13184259.89
      2329983.84      13183808.5       2329616.1     13182941.19
#Sta/Elev= 30
  3313.6  137.36  3564.9  132.49  3585.8  130.86  3615.6  131.46    3619  130.42
  3726.3  125.57  4082.7  116.66    4406  115.48  4419.9  115.52  4493.6  115.39
  4586.3  113.18  4598.7  111.62    4658  113.87  4789.8  113.14  4829.9  114.57
    4870  112.66  4950.1  112.68  5007.2  108.29    5010  107.79  5013.2  108.29
  5040.3  114.37  5120.4  114.81  5122.8  114.82  5270.7  116.85  5754.7  128.14
  5997.5  128.43  6068.5  130.97    6074  129.86  6080.5  130.99    6141   130.2
#Mann= 10 ,-1 , 0
  3313.6     .05       0    3619      .1       0  3726.3     .16       0
    4406      .1       0  4419.9     .16       0  4598.7     .12       0
  5007.2     .07       0  5013.2     .12       0  5122.8      .1       0
  5270.7     .05       0
Bank Sta=4493.6,5120.4
XS Rating Curve= 0 ,0
Exp/Cntr=0.3,0.1

Type RM Length L Ch R = 1 ,34308   ,668,668,668
BEGIN DESCRIPTION:
Mapping XS c38b5d9c
END DESCRIPTION:
XS GIS Cut Line= 3
      2331004.69     13185440.49      2330483.84     13183836.28
       2330025.5     13182884.87
#Sta/Elev= 30
  3607.8  138.41  3984.5   129.3  4101.5   124.8    4219  121.23  4388.4  116.03
  4577.4  113.15  4599.9  113.16  4694.5  112.82  4726.1  110.83    4750  112.56
  4808.1  112.17  4837.2  111.89    4979  109.83  4988.9  109.31  4996.4  105.24
  4999.2  104.74  5002.4  105.24  5010.9  108.06  5046.9  110.98  5382.6  112.82
  5592.3  115.25  5660.1  118.37  5688.3  117.67  5726.7  120.53  5771.1  120.25
  5801.4  122.87  6070.8  129.44  6083.9   131.3    6101  130.34  6350.5  136.91
#Mann= 12 ,-1 , 0
  3607.8     .05       0  3984.5      .1       0  4101.5     .16       0
    4219      .1       0  4388.4     .05       0  4577.4      .1       0
  4599.9     .12       0  4808.1      .1       0  4837.2     .12       0
  4996.4     .07       0  5002.4     .12       0  5046.9     .05       0
Bank Sta=4694.5,5382.6
XS Rating Curve= 0 ,0
Exp/Cntr=0.3,0.1

Type RM Length L Ch R = 1 ,33640   ,548,548,548
BEGIN DESCRIPTION:
Mapping XS db71f537
END DESCRIPTION:
XS GIS Cut Line= 3
      2331469.95     13185329.29      2331275.51     13184197.39
      2330303.28     13182773.77
#Sta/Elev= 30
  3486.8   135.8  3631.3  132.85  3976.3   121.8  4061.8  121.59  4087.9  119.66
  4138.6  118.55  4260.4  117.69  4280.7  115.15  4301.7  114.63  4341.6  116.48
  4493.8  113.15  4535.9  113.36  4605.4  113.49  4765.6  110.27  4886.3  109.06
  4922.2  109.82  4958.1   108.6  4964.2  107.08  4987.1   107.3    4994  106.16
  4997.1  102.48  4999.8  101.98  5003.1  102.48  5008.9  102.94    5015  108.71
  5053.2  109.55  5266.3  110.32  5454.6  111.35  5699.8  114.68  6359.2  133.81
#Mann= 6 ,-1 , 0
  3486.8     .05       0  4535.9      .1       0  4765.6     .12       0
  4997.1     .07       0  5003.1     .12       0  5053.2     .05       0
Bank Sta=4765.6,5266.3
XS Rating Curve= 0 ,0
Exp/Cntr=0.3,0.1

Type RM Length L Ch R = 1 ,33092   ,678,678,678
BEGIN DESCRIPTION:
Mapping XS ae494996
END DESCRIPTION:
XS GIS Cut Line= 2
      2332219.98     13184537.71      2330567.16     13182558.48
#Sta/Elev= 30
  3773.5  135.57  3889.7  132.93  4166.2  121.96  4294.4  117.32  4321.8  118.54
  4336.1  116.36  4388.3  115.19    4543  111.23  4841.1  107.83  4913.3  107.57
  4975.1  106.02  4997.5  101.79  5000.8  101.29  5003.5  100.79  5006.8  101.29
  5018.1  108.32  5089.6  104.64  5139.1  107.07  5145.6  105.66  5153.4  107.43
  5223.7  105.86  5259.8  107.92  5316.1  109.76  5677.9   111.8  5741.9  113.83
  5778.1  120.31  5798.9  116.71  5862.7  116.47  5972.8  123.24  6352.1  133.23
#Mann= 8 ,-1 , 0
  3773.5     .05       0  4166.2      .1       0  4388.3     .05       0
  4913.3     .12       0  4997.5      .1       0  5000.8     .07       0
  5006.8      .1       0  5972.8     .05       0
Bank Sta=4841.1,5259.8
XS Rating Curve= 0 ,0
Exp/Cntr=0.3,0.1

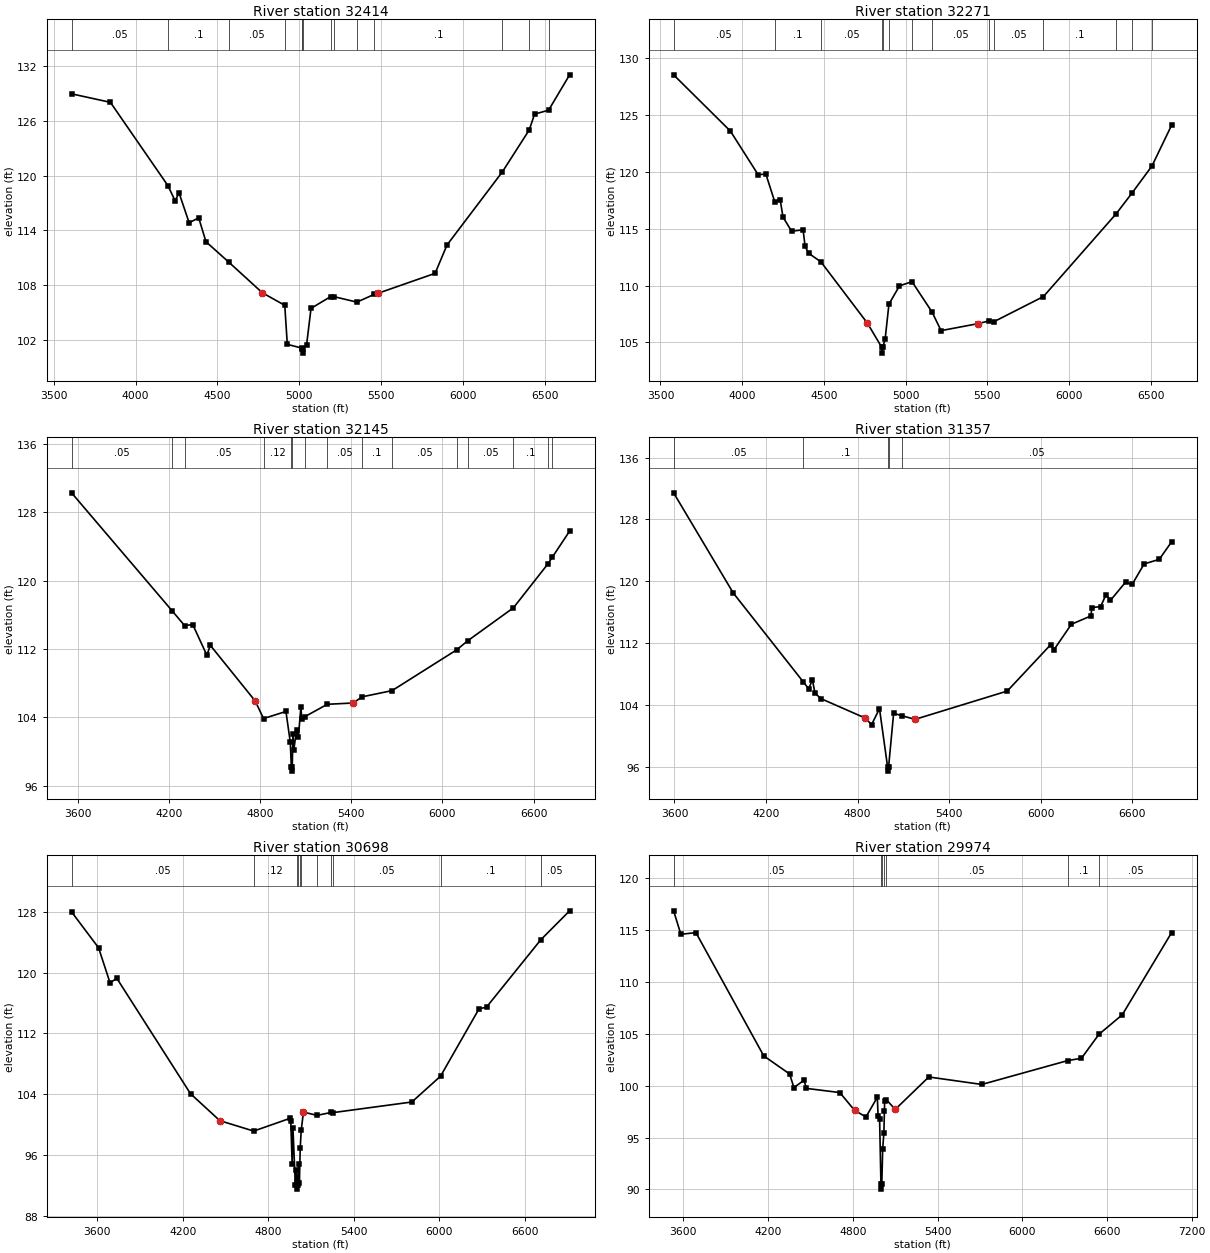
Type RM Length L Ch R = 1 ,32414   ,143,143,143
BEGIN DESCRIPTION:
Mapping XS fe2612c5
END DESCRIPTION:
XS GIS Cut Line= 3
      2332594.94     13184516.81      2331990.79     13183259.89
      2330665.15     13182281.28
#Sta/Elev= 30
  3609.1  128.94  3846.3  128.01  4198.2  118.88  4242.2  117.21  4264.9  118.14
  4327.2  114.84  4385.7  115.37  4430.1  112.76  4567.9  110.55    4774  107.18
  4911.4   105.8  4926.9  101.53    5018  101.11  5018.7  101.07  5021.4  100.57
  5024.7  101.07  5044.7  101.48  5071.8  105.47  5191.3  106.75  5209.7  106.76
  5351.7  106.15  5457.9     107  5479.8  107.11  5829.7   109.3  5902.4   112.4
  6240.9  120.41  6404.7  124.99  6437.3  126.72    6523  127.15  6651.4  131.02
#Mann= 14 ,-1 , 0
  3609.1     .05       0  4198.2      .1       0  4567.9     .05       0
  4911.4     .12       0    5018      .1       0  5018.7     .07       0
  5024.7      .1       0  5191.3     .05       0  5209.7      .1       0
  5351.7     .05       0  5457.9      .1       0  6240.9     .05       0
  6404.7      .1       0    6523     .05       0
Bank Sta=4774,5479.8
XS Rating Curve= 0 ,0
Exp/Cntr=0.3,0.1

Type RM Length L Ch R = 1 ,32271   ,126,126,126
BEGIN DESCRIPTION:
Mapping XS 63b1f4a7
END DESCRIPTION:
XS GIS Cut Line= 3
      2332678.27     13184495.97      2332067.18     13183079.34
       2330872.7     13182162.65
#Sta/Elev= 30
  3580.3  128.54  3927.9  123.59  4097.9  119.75    4145  119.81  4199.9  117.34
  4232.8  117.53  4249.9  116.02  4302.4  114.78  4372.9   114.9  4385.2  113.44
  4407.3  112.83  4481.6  112.09  4766.4  106.69  4854.8  104.55  4857.6  104.05
  4860.8  104.55  4875.3  105.32  4898.3  108.36  4962.8  109.97  5039.5  110.34
  5162.4  107.66  5217.3  106.03  5445.7  106.65    5509  106.88  5538.7   106.8
  5844.2  109.03    6289  116.31  6387.4  118.16  6508.4  120.52  6628.8  124.12
#Mann= 14 ,-1 , 0
  3580.3     .05       0  4199.9      .1       0  4481.6     .05       0
  4854.8     .07       0  4860.8     .05       0  4898.3     .12       0
  5039.5      .1       0  5162.4     .05       0    5509      .1       0
  5538.7     .05       0  5844.2      .1       0    6289     .05       0
  6387.4      .1       0  6508.4     .05       0
Bank Sta=4766.4,5445.7
XS Rating Curve= 0 ,0
Exp/Cntr=0.3,0.1

Type RM Length L Ch R = 1 ,32145   ,788,788,788
BEGIN DESCRIPTION:
Mapping XS faabbe30
END DESCRIPTION:
XS GIS Cut Line= 3
      2332817.16     13184461.24      2332192.18      13183058.5
      2330853.17     13181941.51
#Sta/Elev= 30
  3558.2  130.28    4222  116.44  4302.3  114.75    4356  114.87    4449  111.28
  4471.7  112.44  4767.2  105.93  4822.2  103.87  4969.7   104.7  4998.4   101.1
  5005.1   98.22  5007.8   97.72  5011.1   98.22  5016.2  102.05  5021.7  100.24
  5039.4  102.52  5051.9  101.72  5068.1  105.22  5073.8  103.87  5092.2  104.07
  5241.7  105.54  5411.1  105.69    5473  106.42  5668.8  107.14  6093.1   111.9
  6168.2  112.99  6467.6  116.83  6693.6  121.94  6724.8  122.78  6837.6   125.8
#Mann= 15 ,-1 , 0
  3558.2     .05       0    4222      .1       0  4302.3     .05       0
  4822.2     .12       0  5005.1     .07       0  5011.1     .12       0
  5092.2      .1       0  5241.7     .05       0    5473      .1       0
  5668.8     .05       0  6093.1      .1       0  6168.2     .05       0
  6467.6      .1       0  6693.6     .05       0  6724.8      .1       0
Bank Sta=4767.2,5411.1
XS Rating Curve= 0 ,0
Exp/Cntr=0.3,0.1

Type RM Length L Ch R = 1 ,31357   ,659,659,659
BEGIN DESCRIPTION:
Mapping XS a62bf103
END DESCRIPTION:
XS GIS Cut Line= 3
      2333251.64     13184315.87      2332878.37     13182814.15
      2331802.37     13181477.82
#Sta/Elev= 30
  3594.3  131.44  3984.8  118.49  4442.9     107  4479.5  106.08  4503.5  107.26
  4520.7   105.5  4561.9  104.79  4850.4  102.29  4891.6  101.45  4943.1  103.52
  4996.6   95.93  4999.3   95.43  5002.6   95.93  5035.8  102.91  5089.4   102.6
  5176.5  102.13  5780.2  105.79  6064.3  111.78  6086.7  111.15  6200.3  114.43
  6328.2  115.51  6334.7  116.59  6392.2  116.72  6427.4  118.28  6456.2  117.52
  6555.4  119.88  6598.6  119.59    6677  122.24  6776.1  122.83  6857.4  125.11
#Mann= 5 ,-1 , 0
  3594.3     .05       0  4442.9      .1       0  4996.6     .07       0
  5002.6      .1       0  5089.4     .05       0
Bank Sta=4850.4,5176.5
XS Rating Curve= 0 ,0
Exp/Cntr=0.3,0.1

Type RM Length L Ch R = 1 ,30698   ,724,724,724
BEGIN DESCRIPTION:
Mapping XS a0c4e488
END DESCRIPTION:
XS GIS Cut Line= 3
      2333572.82     13184454.77      2333711.71     13183352.34
      2332687.96     13181200.72
#Sta/Elev= 30
    3420  128.02  3609.4  123.29    3690  118.67  3737.3  119.27  4254.5  104.06
  4460.2  100.51  4697.5   99.14  4950.1   100.8    4958  100.42  4967.3   94.82
  4972.8   99.57    4990   92.03  4995.5   94.06  4999.3   91.99  5002.1   91.49
  5005.3   91.99  5012.7   94.77  5018.3   92.32    5024   96.91  5031.2   99.28
  5046.6  101.64  5142.2  101.21  5239.2  101.59  5253.2  101.57  5807.1  102.97
  6008.3  106.37  6277.9  115.23  6331.2  115.48  6711.9  124.35  6913.9  128.16
#Mann= 11 ,-1 , 0
    3420     .05       0  4697.5     .12       0  4999.3     .07       0
  5005.3     .12       0    5024     .05       0  5031.2     .12       0
  5142.2     .05       0  5239.2      .1       0  5253.2     .05       0
  6008.3      .1       0  6711.9     .05       0
Bank Sta=4460.2,5046.6
XS Rating Curve= 0 ,0
Exp/Cntr=0.3,0.1

Type RM Length L Ch R = 1 ,29974   ,538,538,538
BEGIN DESCRIPTION:
Mapping XS b2abf315
END DESCRIPTION:
XS GIS Cut Line= 3
        2333894.     13184584.97      2334137.06     13183248.17
      2333251.64     13181269.01
#Sta/Elev= 30
    3531  116.83  3582.4  114.57  3689.1  114.73  4169.4  102.86  4352.4  101.12
  4382.9   99.81    4454  100.51  4471.7   99.73  4708.1   99.33  4812.2   97.62
  4893.2   96.98  4973.6   98.88    4979   97.09  4989.8   96.76  4999.2   90.53
    5002   90.03  5005.2   90.53  5011.7   93.94    5020   95.42  5023.7   97.52
  5025.4   98.48  5038.5   98.62  5100.5   97.71    5338  100.83  5713.3  100.11
  6322.4  102.41    6419  102.63  6543.2  104.94  6708.3  106.82  7057.9  114.74
#Mann= 7 ,-1 , 0
    3531     .05       0  4999.2    .035       0  5005.2     .05       0
  5023.7      .1       0  5038.5     .05       0  6322.4      .1       0
  6543.2     .05       0
Bank Sta=4812.2,5100.5
XS Rating Curve= 0 ,0
Exp/Cntr=0.3,0.1

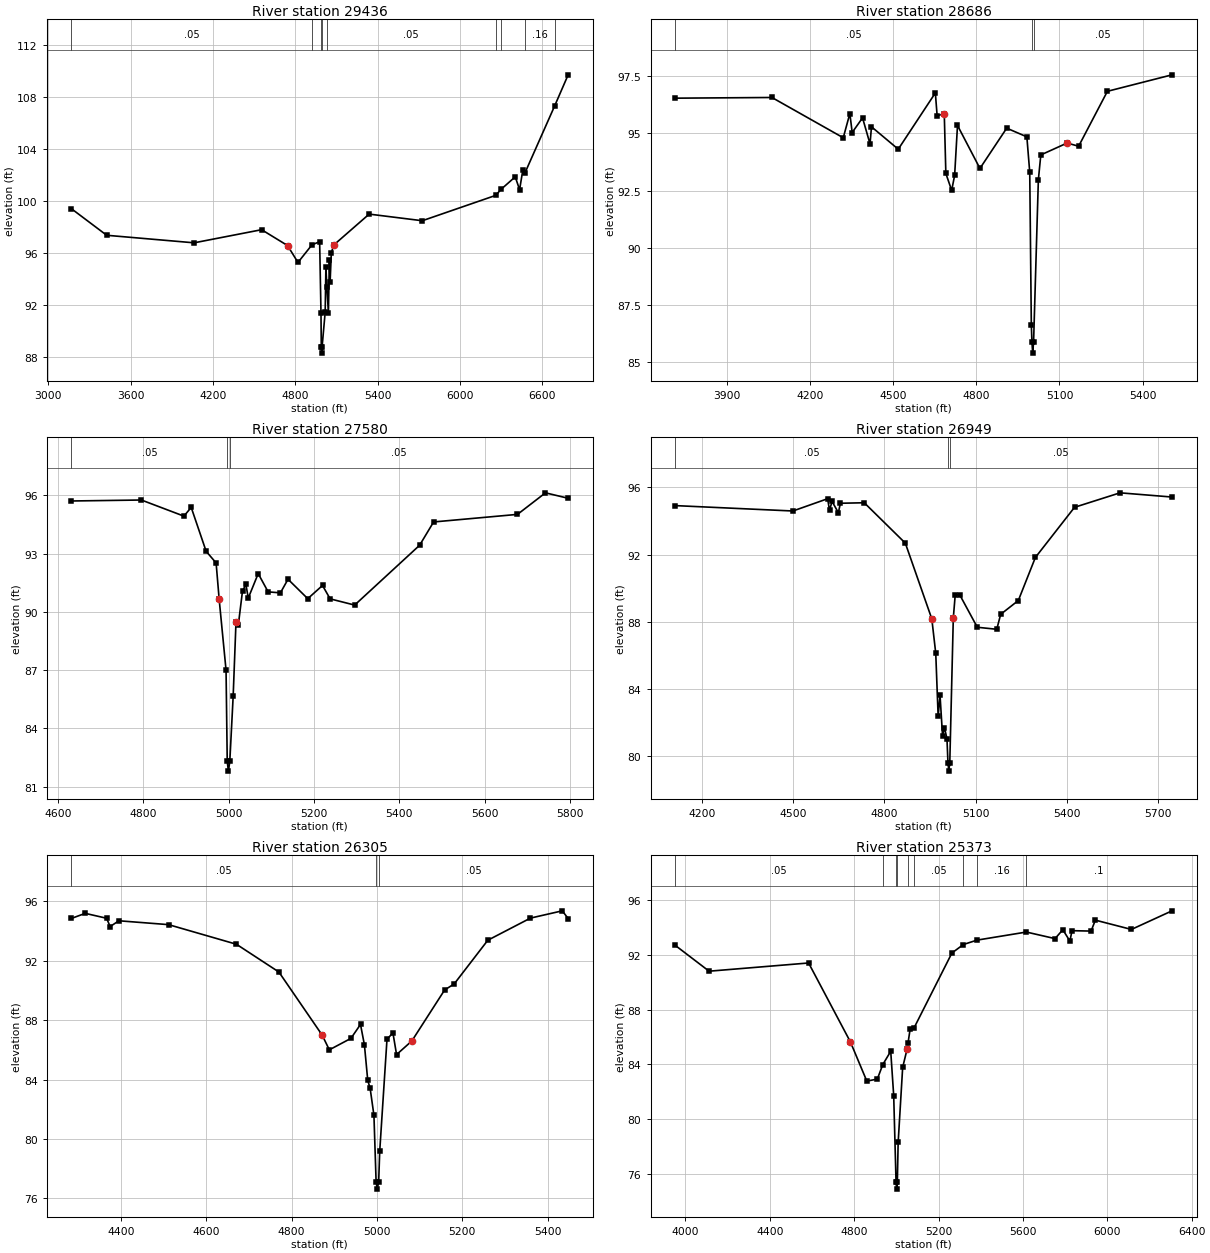
Type RM Length L Ch R = 1 ,29436   ,750,750,750
BEGIN DESCRIPTION:
Mapping XS e21fd761
END DESCRIPTION:
XS GIS Cut Line= 3
      2334822.04     13184659.09      2334918.31     13184150.95
      2333859.26     13181234.25
#Sta/Elev= 30
  3169.3   99.43    3426   97.39  4063.2   96.81  4555.2   97.82  4744.1    96.6
  4820.1    95.3  4921.8   96.65  4978.1    96.9  4987.8   91.44  4990.1   88.82
  4992.8   88.32  4996.1   88.82  5018.4   91.47  5023.7   94.96  5030.7   93.41
    5042   91.42    5049   95.51  5054.3   93.78  5063.2   96.02  5079.6   96.63
  5339.1   99.02  5726.4   98.51  6261.2  100.46  6300.8  100.93  6403.8  101.89
  6435.6   100.9  6459.7  102.45  6473.8  102.17  6692.1  107.37  6789.5  109.74
#Mann= 9 ,-1 , 0
  3169.3     .05       0  4921.8     .12       0  4990.1     .07       0
  4996.1     .12       0  5030.7     .05       0  6261.2     .16       0
  6300.8     .05       0  6473.8     .16       0  6692.1      .1       0
Bank Sta=4744.1,5079.6
XS Rating Curve= 0 ,0
Exp/Cntr=0.3,0.1

Type RM Length L Ch R = 1 ,28686   ,1106,1106,1106
BEGIN DESCRIPTION:
Mapping XS 015c72aa
END DESCRIPTION:
XS GIS Cut Line= 3
      2335417.78     13183966.59      2335076.03      13182896.5
      2334896.75     13182252.22
#Sta/Elev= 30
    3714   96.54  4062.4   96.57  4319.8   94.81  4343.6   95.87    4352   95.04
  4389.4   95.68  4416.4   94.54  4421.6   95.29  4518.2   94.31  4652.1   96.77
  4658.5   95.78  4684.3   95.85    4690   93.25    4711   92.51  4721.7   93.17
    4732   95.35    4813   93.47  4909.6   95.23  4982.3   94.85  4992.7    93.3
  4998.4   86.65  5000.6    85.9  5003.3    85.4  5006.6    85.9  5023.8   92.97
  5032.6   94.06  5127.6   94.58  5169.1   94.44  5272.9   96.84  5506.1   97.56
#Mann= 3 ,-1 , 0
    3714     .05       0  5000.6    .035       0  5006.6     .05       0
Bank Sta=4684.3,5127.6
XS Rating Curve= 0 ,0
Exp/Cntr=0.3,0.1

Type RM Length L Ch R = 1 ,27580   ,631,631,631
BEGIN DESCRIPTION:
Mapping XS efd805e3
END DESCRIPTION:
XS GIS Cut Line= 3
      2336036.37     13183322.38        2335955.     13183078.27
      2335588.78     13182248.18
#Sta/Elev= 30
  4631.5   95.71  4795.4   95.76  4895.1   94.93  4912.2   95.38  4947.2   93.12
  4970.6   92.52  4977.8   90.64  4993.9      87  4996.7    82.3  4999.4    81.8
  5002.7    82.3  5010.6   85.66  5017.2   89.46  5022.7   89.33  5032.5   91.08
  5040.5   91.41    5046   90.71  5069.3   91.97  5092.6   91.03  5121.4   90.98
  5139.2   91.68  5185.5   90.68  5220.1   91.36    5238   90.67  5295.5   90.35
  5447.8   93.43  5480.6   94.63  5677.3   95.02  5742.9   96.13  5796.1   95.85
#Mann= 3 ,-1 , 0
  4631.5     .05       0  4996.7    .035       0  5002.7     .05       0
Bank Sta=4977.8,5017.2
XS Rating Curve= 0 ,0
Exp/Cntr=0.3,0.1

Type RM Length L Ch R = 1 ,26949   ,644,644,644
BEGIN DESCRIPTION:
Mapping XS 67dd7b2a
END DESCRIPTION:
XS GIS Cut Line= 2
      2336767.24     13183239.46      2335777.69     13181937.42
#Sta/Elev= 30
  4111.6   94.91  4498.6   94.59  4612.9   95.32  4619.2   94.63  4627.5   95.16
  4648.3   94.49    4655   95.05  4733.6   95.08  4868.8   92.68    4956   88.18
    4969   86.13  4976.9   82.38  4983.1   83.63  4991.4   81.23  4997.7   81.71
  5005.9   81.06  5009.2   79.63    5012   79.13  5015.2   79.63  5026.8   88.23
    5033   89.58  5047.6   89.62  5105.8   87.68  5169.9   87.56  5182.8   88.45
  5240.9   89.27  5297.1   91.83    5426   94.81  5575.8   95.67    5747   95.42
#Mann= 3 ,-1 , 0
  4111.6     .05       0  5009.2    .035       0  5015.2     .05       0
Bank Sta=4956,5026.8
XS Rating Curve= 0 ,0
Exp/Cntr=0.3,0.1

Type RM Length L Ch R = 1 ,26305   ,932,932,932
BEGIN DESCRIPTION:
Mapping XS b5cbe7fe
END DESCRIPTION:
XS GIS Cut Line= 3
       2336768.8      13182565.6      2336679.28     13182134.25
      2336028.26     13181816.88
#Sta/Elev= 30
  4283.6   94.86  4315.8    95.2  4365.9   94.87  4374.2   94.31  4394.7    94.7
  4511.2   94.44  4670.4   93.12    4770   91.25  4871.3   87.01  4888.3   86.01
  4938.9   86.78  4961.4   87.72  4970.6   86.34  4978.4   83.95    4984   83.42
  4992.9    81.6    4998   77.13  5000.7   76.63    5004   77.13  5006.5   79.19
  5023.5   86.71  5037.4   87.16    5046   85.69  5081.9   86.61  5158.7   90.04
  5181.2   90.45    5260   93.39    5360   94.88  5434.7   95.37  5448.4   94.85
#Mann= 3 ,-1 , 0
  4283.6     .05       0    4998    .035       0    5004     .05       0
Bank Sta=4871.3,5081.9
XS Rating Curve= 0 ,0
Exp/Cntr=0.3,0.1

Type RM Length L Ch R = 1 ,25373   ,1012,1012,1012
BEGIN DESCRIPTION:
Mapping XS eca41f23
END DESCRIPTION:
XS GIS Cut Line= 4
      2337012.94     13182126.11      2336947.83     13181377.42
      2336394.45     13180856.59      2335556.27     13180767.07
#Sta/Elev= 30
  3952.5   92.69  4112.4   90.81  4584.1   91.41  4782.4   85.64  4860.1   82.78
  4909.9   82.93  4935.8   83.99  4973.4   84.96  4987.5   81.72  4998.7   75.39
  5001.4   74.89  5004.7   75.39  5008.6    78.3    5030   83.78    5051   85.12
  5055.7   85.59  5065.2   86.56  5084.7   86.69  5263.5   92.14    5318   92.76
  5382.4   93.08  5616.4   93.67  5752.3   93.19  5789.3   93.84  5822.7   93.01
  5832.8   93.77  5923.3   93.74  5943.4   94.54  6114.4   93.86  6306.9   95.22
#Mann= 9 ,-1 , 0
  3952.5     .05       0  4935.8     .16       0  4998.7     .07       0
  5004.7     .16       0  5055.7      .1       0  5084.7     .05       0
    5318      .1       0  5382.4     .16       0  5616.4      .1       0
Bank Sta=4782.4,5051
XS Rating Curve= 0 ,0
Exp/Cntr=0.3,0.1