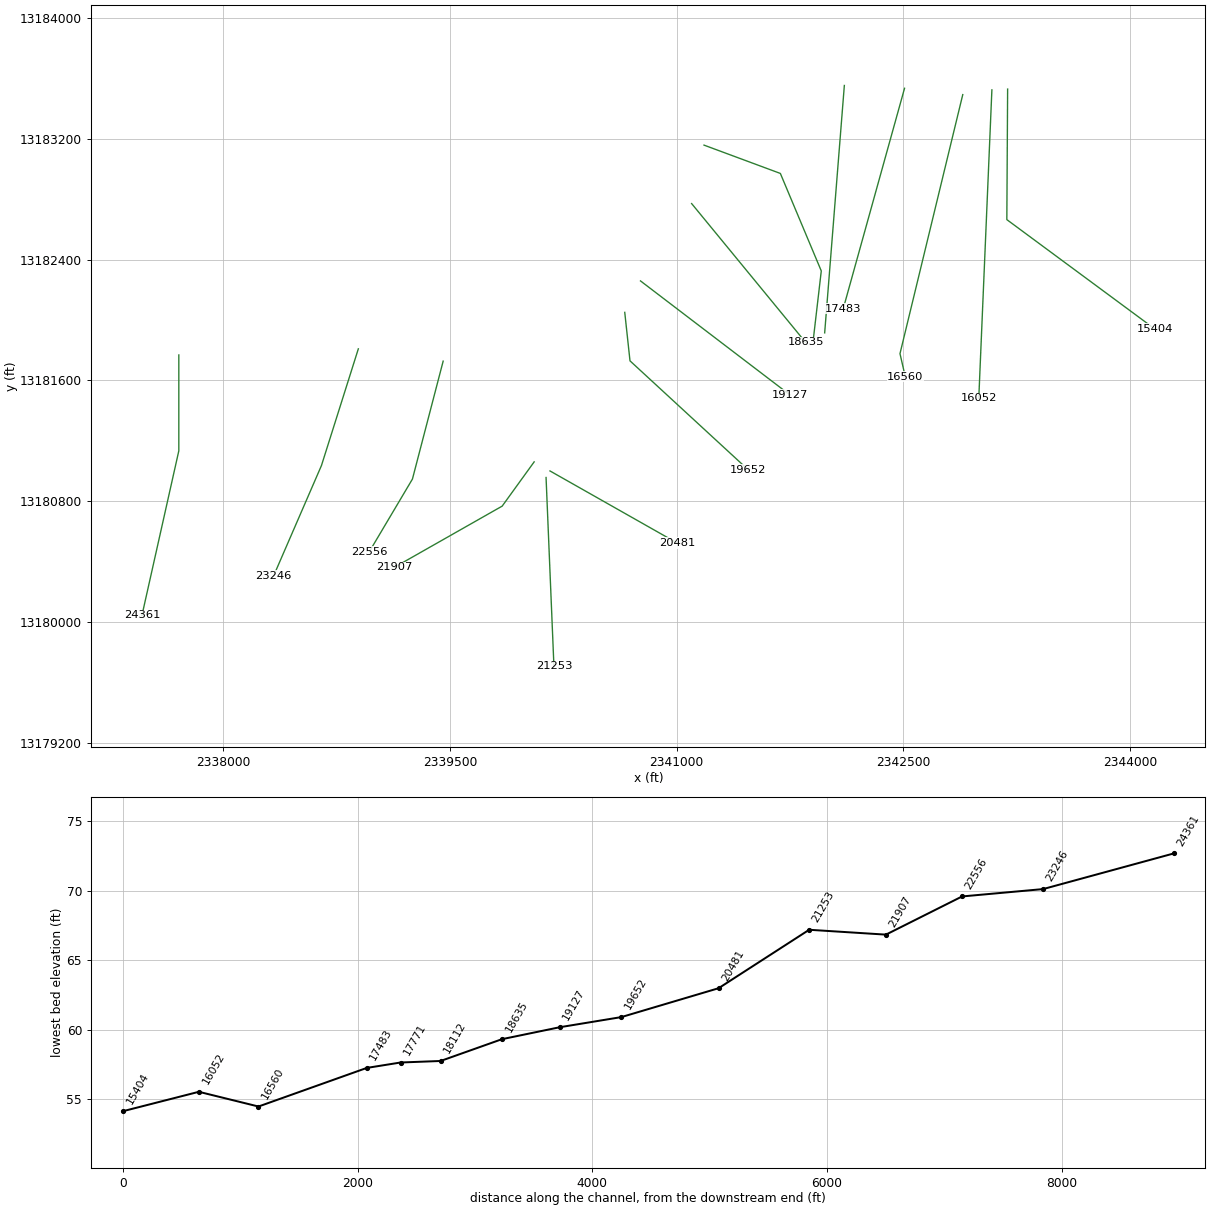
HEC-RAS study JAVELIN CREEK.prj: JAVELIN CREEK Base Level Engineering

--- JAVELIN CREEK.g01 (geometry) --- (continued)

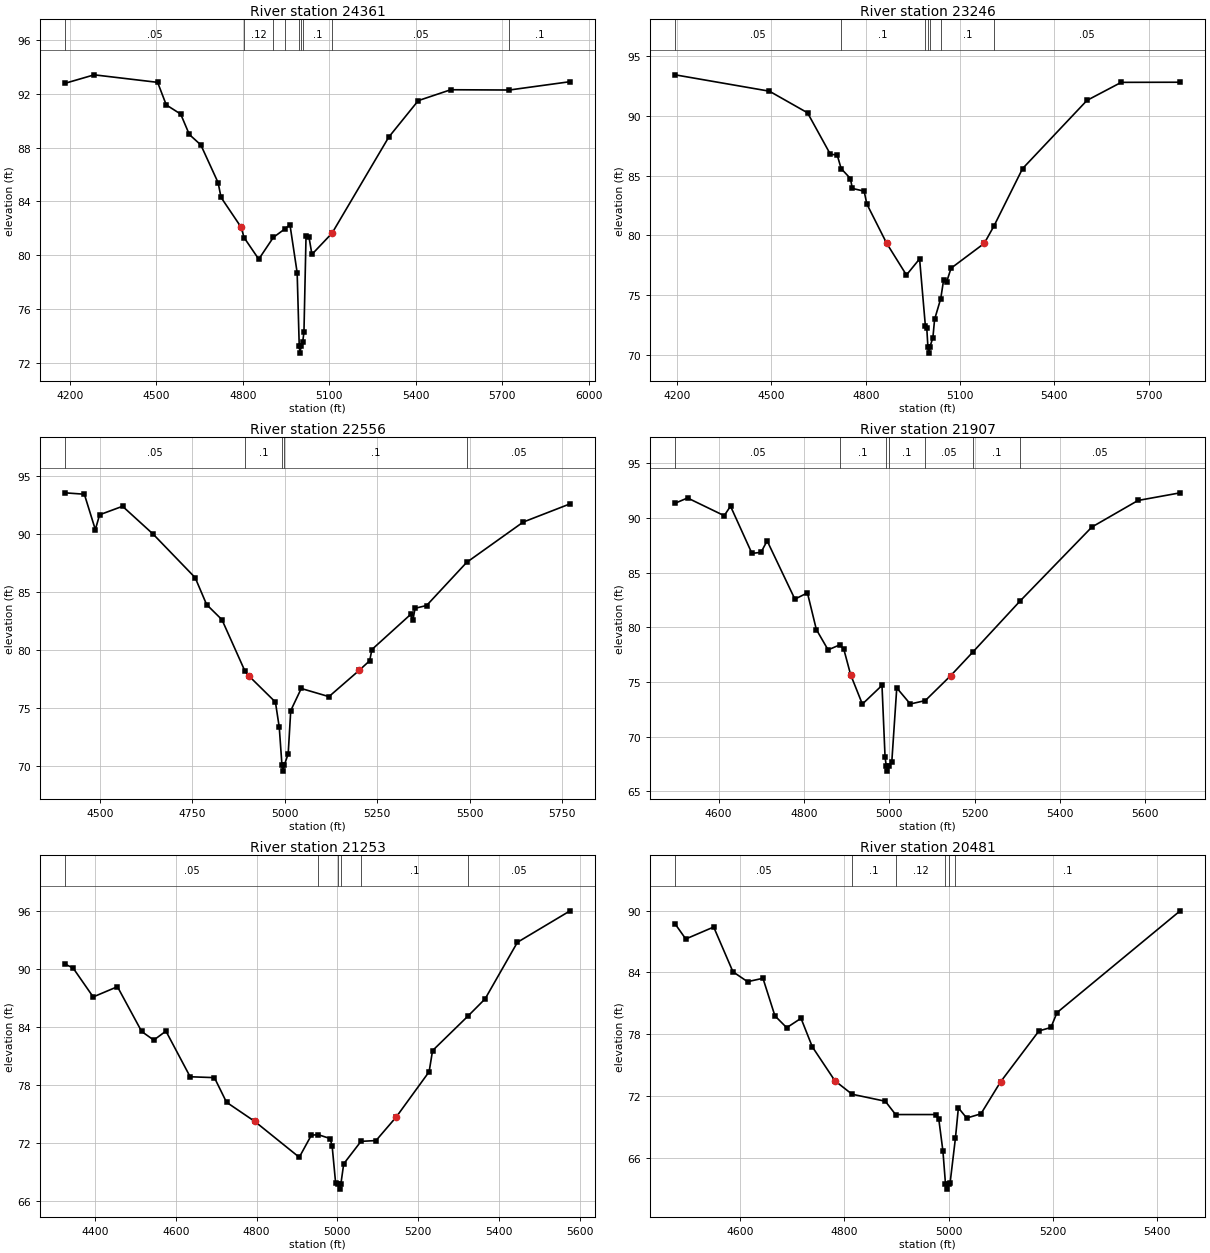
Type RM Length L Ch R = 1 ,24361   ,1115,1115,1115
BEGIN DESCRIPTION:
Mapping XS e2ea8d22
END DESCRIPTION:
XS GIS Cut Line= 3
      2337704.67     13181768.07      2337704.67     13181133.28
      2337460.53     13180042.77
#Sta/Elev= 30
  4182.8   92.78    4284   93.41    4504   92.85    4534   91.17    4584   90.49
    4614   88.97    4654   88.19    4714   85.38    4724   84.29    4794   82.06
  4803.9    81.3  4854.9   79.69  4905.4   81.31  4945.3   81.94  4963.2   82.25
  4988.1   78.69  4995.4    73.2  4998.1    72.7  5001.4    73.2  5007.3   73.53
  5011.7   74.25  5018.9   81.38  5029.1   81.34  5039.4   80.05  5109.3   81.63
  5305.8   88.77  5408.3   91.49    5521    92.3  5724.3   92.28  5935.1    92.9
#Mann= 9 ,-1 , 0
  4182.8     .05       0  4803.9     .12       0  4905.4      .1       0
  4945.3     .12       0  4995.4     .07       0  5001.4     .12       0
  5007.3      .1       0  5109.3     .05       0  5724.3      .1       0
Bank Sta=4794,5109.3
XS Rating Curve= 0 ,0
Exp/Cntr=0.3,0.1

Type RM Length L Ch R = 1 ,23246   ,690,690,690
BEGIN DESCRIPTION:
Mapping XS 002ddac2
END DESCRIPTION:
XS GIS Cut Line= 3
      2338892.82     13181808.72      2338648.68     13181035.62
        2338332.     13180304.81
#Sta/Elev= 30
  4193.3   93.43  4493.3   92.06  4614.7   90.25  4687.3   86.78  4709.1   86.72
  4721.6   85.58  4751.1   84.75  4757.2   83.92  4794.8   83.69  4803.5   82.61
  4866.4   79.33  4929.4   76.67  4971.3   78.02  4989.6   72.43  4994.1   72.25
  4997.8   70.63  5000.5   70.13  5003.8   70.63  5013.6   71.42    5019   72.95
  5038.6    74.7  5047.9   76.28  5057.2   76.08  5071.4   77.24  5177.1   79.32
  5208.3   80.79    5299   85.58    5504   91.29    5613    92.8  5800.5   92.81
#Mann= 7 ,-1 , 0
  4193.3     .05       0  4721.6      .1       0  4989.6     .12       0
  4997.8     .07       0  5003.8     .12       0  5038.6      .1       0
  5208.3     .05       0
Bank Sta=4866.4,5177.1
XS Rating Curve= 0 ,0
Exp/Cntr=0.3,0.1

Type RM Length L Ch R = 1 ,22556   ,649,649,649
BEGIN DESCRIPTION:
Mapping XS 4cf676cc
END DESCRIPTION:
XS GIS Cut Line= 3
      2339454.34     13181727.32      2339250.89      13180946.1
      2338966.09       13180466.
#Sta/Elev= 30
  4406.1   93.58  4458.3   93.46    4488   90.41  4499.6   91.69  4561.6   92.42
  4644.3   90.02  4757.9   86.27  4788.9   83.95  4830.3   82.65  4892.9   78.19
  4902.6   77.82  4974.9   75.55  4985.3   73.37  4992.6    70.1  4995.3    69.6
  4998.6    70.1  5009.4   71.08  5016.3   74.81  5044.7   76.72  5119.6   76.02
  5201.6   78.29  5229.7   79.11  5235.8   80.08  5340.4    83.1  5346.6    82.6
  5352.4   83.63  5383.6   83.87  5492.1   87.59  5644.8   91.06  5771.6   92.63
#Mann= 5 ,-1 , 0
  4406.1     .05       0  4892.9      .1       0  4992.6     .07       0
  4998.6      .1       0  5492.1     .05       0
Bank Sta=4902.6,5201.6
XS Rating Curve= 0 ,0
Exp/Cntr=0.3,0.1

Type RM Length L Ch R = 1 ,21907   ,654,654,654
BEGIN DESCRIPTION:
Mapping XS ad8d80f8
END DESCRIPTION:
XS GIS Cut Line= 3
      2340056.54     13181060.02      2339844.97     13180767.07
      2339130.33     13180361.02
#Sta/Elev= 30
  4498.3   91.35  4527.5   91.83  4613.3   90.21  4628.1   91.08  4678.3   86.76
  4699.6   86.86  4713.9   87.91  4778.9   82.58  4808.3   83.15  4829.2    79.8
  4856.7   77.94  4884.4    78.4  4893.6   77.99  4909.5   75.67    4937   72.98
    4983   74.69  4990.2   68.12    4993   67.35  4995.7   66.85    4999   67.35
    5006   67.71  5017.6   74.46  5049.3   72.99  5084.4    73.3    5144   75.58
  5195.4   77.72  5306.4    82.4  5474.7   89.17  5582.8    91.6  5681.6    92.3
#Mann= 7 ,-1 , 0
  4498.3     .05       0  4884.4      .1       0    4993     .07       0
    4999      .1       0  5084.4     .05       0  5195.4      .1       0
  5306.4     .05       0
Bank Sta=4909.5,5144
XS Rating Curve= 0 ,0
Exp/Cntr=0.3,0.1

Type RM Length L Ch R = 1 ,21253   ,772,772,772
BEGIN DESCRIPTION:
Mapping XS 6aa6faf9
END DESCRIPTION:
XS GIS Cut Line= 2
      2340135.32     13180956.51       2340187.4      13179706.5
#Sta/Elev= 30
  4325.4    90.5  4345.1   90.12  4395.1   87.11  4455.2   88.17  4515.2   83.53
  4545.2   82.64  4575.3   83.57  4635.3   78.84  4695.4   78.75  4725.4    76.2
  4795.5   74.21  4905.6    70.5  4935.6   72.79  4952.6   72.84  4982.1   72.44
  4987.1   71.64  4995.6   67.87  5002.6    67.7  5005.4    67.2  5008.6    67.7
  5015.7   69.82  5058.5   72.15  5095.7   72.23  5145.8   74.67  5227.3   79.36
  5235.8   81.55  5324.6   85.17    5366   86.91    5446   92.77  5576.5   96.03
#Mann= 6 ,-1 , 0
  4325.4     .05       0  4952.6     .12       0  5002.6     .07       0
  5008.6     .12       0  5058.5      .1       0  5324.6     .05       0
Bank Sta=4795.5,5145.8
XS Rating Curve= 0 ,0
Exp/Cntr=0.3,0.1

Type RM Length L Ch R = 1 ,20481   ,829,829,829
BEGIN DESCRIPTION:
Mapping XS fc824d96
END DESCRIPTION:
XS GIS Cut Line= 2
      2340161.35     13180999.91      2341003.06     13180522.66
#Sta/Elev= 30
  4476.1    88.7  4496.5   87.24    4550    88.4  4586.9   84.06  4614.9    83.1
  4644.4   83.43  4667.3   79.79  4689.9   78.64  4717.3   79.55  4738.9   76.79
  4782.3   73.49  4815.1   72.19  4878.8   71.51  4898.5   70.22  4975.5   70.22
  4981.2    69.8  4989.2   66.67  4994.1   63.49  4996.9   62.99  5000.1   63.49
  5002.9   63.58  5013.2   67.96  5018.8   70.87  5034.7   69.88    5062   70.29
  5099.5   73.38  5173.2   78.33  5196.1   78.66  5207.7    80.1  5443.7   89.97
#Mann= 6 ,-1 , 0
  4476.1     .05       0  4815.1      .1       0  4898.5     .12       0
  4994.1     .07       0  5000.1     .12       0  5013.2      .1       0
Bank Sta=4782.3,5099.5
XS Rating Curve= 0 ,0
Exp/Cntr=0.3,0.1

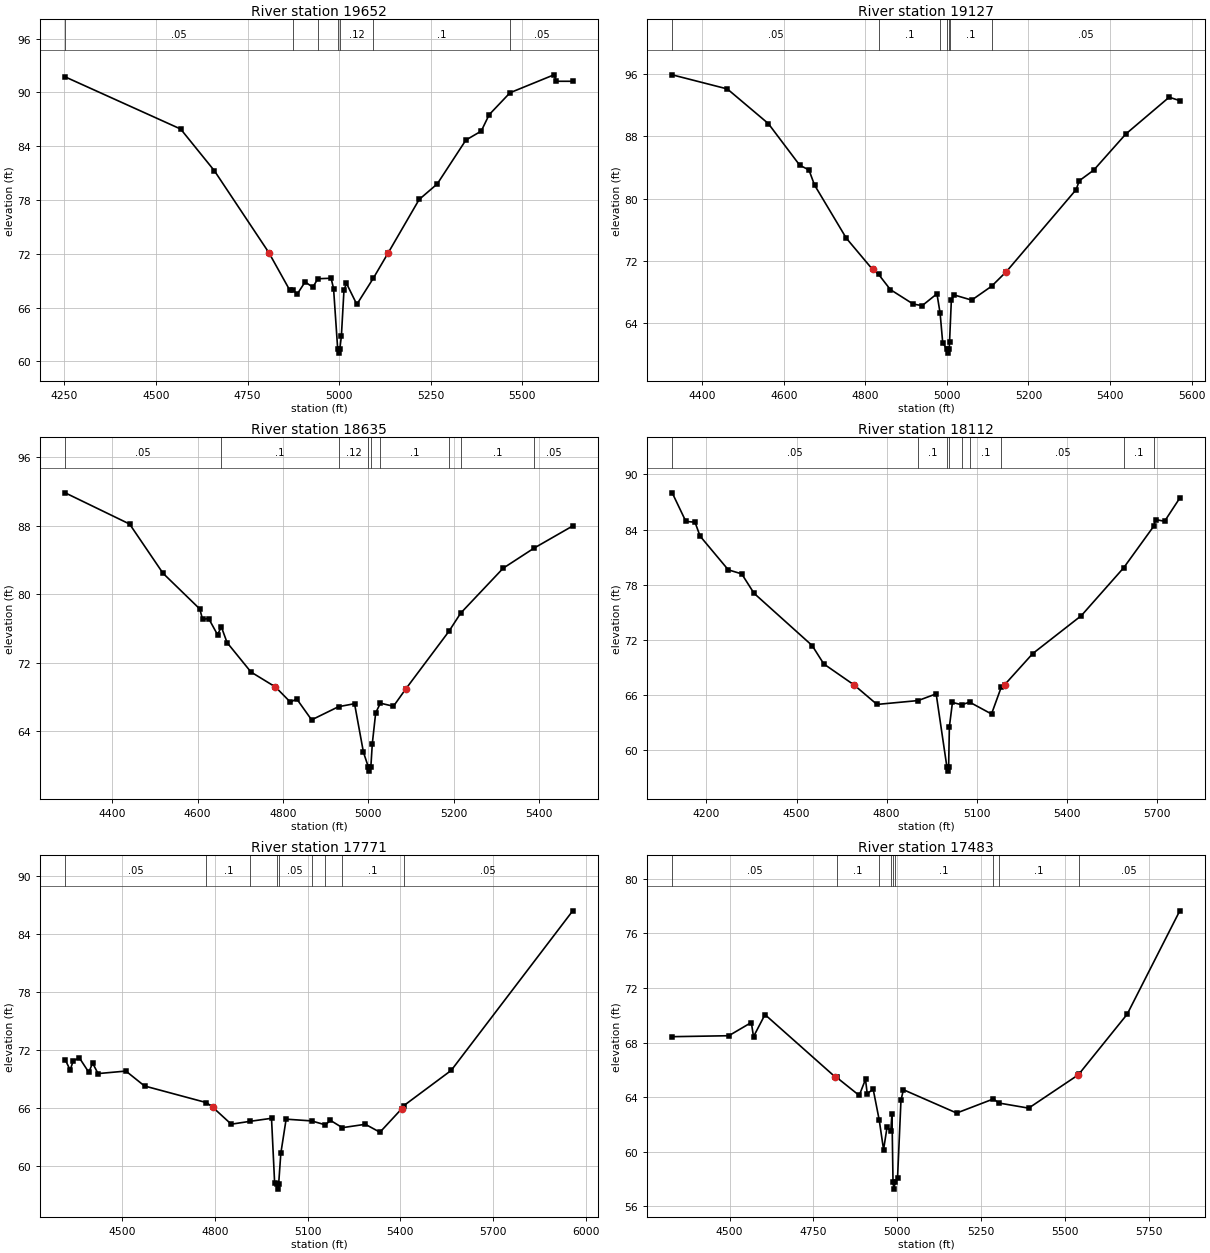
Type RM Length L Ch R = 1 ,19652   ,525,525,525
BEGIN DESCRIPTION:
Mapping XS bfb6b510
END DESCRIPTION:
XS GIS Cut Line= 3
      2340656.15     13182050.28      2340690.87     13181729.08
       2341472.1     13181008.61
#Sta/Elev= 30
    4252   91.74  4567.3   85.92  4659.3   81.27  4807.9   72.14  4864.6   67.98
  4874.2   67.93  4885.6    67.5  4907.2   68.86  4928.1   68.26  4941.9   69.21
    4978   69.27  4984.8   68.12    4996   61.41  4998.8   60.91    5002   61.41
  5006.1   62.78  5013.2   67.92    5020    68.7  5048.3   66.35  5093.2   69.26
  5133.4   72.06  5218.5   78.06  5267.8   79.79  5346.1   84.69    5388   85.69
  5409.6   87.52  5466.6   89.97  5586.5   91.97  5593.3   91.25  5637.8   91.25
#Mann= 7 ,-1 , 0
    4252     .05       0  4874.2      .1       0  4941.9     .12       0
    4996     .07       0    5002     .12       0  5093.2      .1       0
  5466.6     .05       0
Bank Sta=4807.9,5133.4
XS Rating Curve= 0 ,0
Exp/Cntr=0.3,0.1

Type RM Length L Ch R = 1 ,19127   ,492,492,492
BEGIN DESCRIPTION:
Mapping XS 32271301
END DESCRIPTION:
XS GIS Cut Line= 2
      2340760.32     13182258.59      2341749.87      13181503.4
#Sta/Elev= 30
  4326.2   95.87  4461.3   94.06  4561.9   89.62  4638.9   84.28  4661.6   83.67
  4675.2   81.74  4753.2   74.92  4817.6   70.91  4832.2   70.29  4861.2   68.33
  4917.3   66.47  4939.3   66.27  4975.5   67.79  4983.3   65.28  4989.6   61.52
  4999.6   60.68  5002.3   60.18  5005.6   60.68  5006.4   61.65  5010.8   66.96
  5017.1   67.65  5060.7   66.98  5109.5   68.76  5145.9   70.64  5316.7   81.14
  5324.6   82.29    5360   83.65  5438.9   88.29    5545      93    5571   92.56
#Mann= 7 ,-1 , 0
  4326.2     .05       0  4832.2      .1       0  4983.3     .12       0
  4999.6     .07       0  5005.6     .12       0  5006.4      .1       0
  5109.5     .05       0
Bank Sta=4817.6,5145.9
XS Rating Curve= 0 ,0
Exp/Cntr=0.3,0.1

Type RM Length L Ch R = 1 ,18635   ,523,523,523
BEGIN DESCRIPTION:
Mapping XS 338c877e
END DESCRIPTION:
XS GIS Cut Line= 2
      2341098.84     13182770.76      2341852.86     13181852.07
#Sta/Elev= 30
    4290   91.84  4440.9   88.19  4519.1   82.44  4605.2   78.27  4611.7   77.06
    4626   77.15  4646.8   75.26  4655.7   76.18  4669.1   74.34  4725.1    70.9
  4782.5   69.15  4817.6   67.37    4832   67.77  4867.1   65.31  4930.1   66.85
  4967.6    67.2  4988.4   61.53  4999.8   59.82  5002.5   59.32  5005.8   59.82
  5009.2   62.54  5017.1   66.13  5028.1   67.26  5058.7    66.9  5087.4   68.91
  5188.5   75.65  5216.1   77.78  5315.6   83.03    5388   85.38  5478.5   87.97
#Mann= 9 ,-1 , 0
    4290     .05       0  4655.7      .1       0  4930.1     .12       0
  4999.8     .07       0  5005.8     .12       0  5028.1      .1       0
  5188.5     .05       0  5216.1      .1       0    5388     .05       0
Bank Sta=4782.5,5087.4
XS Rating Curve= 0 ,0
Exp/Cntr=0.3,0.1

Type RM Length L Ch R = 1 ,18112   ,341,341,341
BEGIN DESCRIPTION:
Mapping XS 9d9e30a6
END DESCRIPTION:
XS GIS Cut Line= 4
      2341180.82     13183157.97      2341686.07     13182970.45
       2341956.9     13182324.62      2341904.82     13181876.68
#Sta/Elev= 30
    4086      88  4131.5   84.89  4161.9   84.81  4178.7    83.3  4272.7   79.63
  4317.4   79.19  4358.5   77.08    4552    71.4  4590.8    69.4  4691.1   67.13
  4767.9      65  4905.1   65.42    4965   66.15  5000.5   58.25  5003.3   57.75
  5006.5   58.25    5009   62.57  5019.2   65.22    5050   64.96  5076.3   65.25
  5149.3   63.96  5182.1   66.91  5192.7   67.13  5286.7   70.53  5448.4   74.65
  5589.6   79.86  5689.5   84.37  5695.5   85.09  5725.7   84.91  5776.2   87.43
#Mann= 9 ,-1 , 0
    4086     .05       0  4905.1      .1       0  5000.5     .07       0
  5006.5      .1       0    5050     .12       0  5076.3      .1       0
  5182.1     .05       0  5589.6      .1       0  5689.5     .05       0
Bank Sta=4691.1,5192.7
XS Rating Curve= 0 ,0
Exp/Cntr=0.3,0.1

Type RM Length L Ch R = 1 ,17771   ,288,288,288
BEGIN DESCRIPTION:
Mapping XS 02c9c9d6
END DESCRIPTION:
XS GIS Cut Line= 2
      2342109.57     13183552.98      2341979.36     13181914.55
#Sta/Elev= 30
  4314.4   71.03  4330.6   69.94  4340.6   70.92  4360.7   71.19  4390.8   69.72
  4403.3   70.66  4420.9   69.58  4511.1   69.84  4571.3    68.3  4771.9   66.58
    4792   66.11  4852.2   64.35  4913.8   64.65  4982.6   64.96  4992.7   58.26
  4999.7   58.14  5002.4   57.64  5005.7   58.14  5012.7   61.33  5029.9   64.87
  5112.5   64.69  5157.1   64.28  5173.2   64.75  5211.9   63.99  5286.5   64.34
  5333.7   63.52    5404   65.94  5410.7   66.26  5564.5   69.91    5958    86.4
#Mann= 9 ,-1 , 0
  4314.4     .05       0  4771.9      .1       0  4913.8     .05       0
  4999.7     .03       0  5005.7     .05       0  5112.5      .1       0
  5157.1     .05       0  5211.9      .1       0  5410.7     .05       0
Bank Sta=4792,5404
XS Rating Curve= 0 ,0
Exp/Cntr=0.3,0.1

Type RM Length L Ch R = 1 ,17483   ,923,923,923
BEGIN DESCRIPTION:
Mapping XS 1f8b95ea
END DESCRIPTION:
XS GIS Cut Line= 2
      2342507.99     13183534.26      2342102.55     13182075.77
#Sta/Elev= 30
  4328.9   68.43  4497.7    68.5  4564.9   69.47  4571.4   68.43  4605.6   70.05
    4814    65.5  4819.6   65.44  4886.7   64.12  4905.4    65.3  4910.6   64.24
  4928.2   64.59  4946.3   62.32  4959.3   60.14  4969.7    61.8  4980.8   61.49
  4984.3   62.76  4987.5   57.75  4990.2   57.25  4993.5   57.75  5000.9   58.03
  5011.2   63.77  5018.5   64.54  5177.3   62.83  5286.5   63.86  5304.2   63.56
    5392   63.19  5539.4   65.62  5541.4   65.67  5685.9   70.08  5842.7   77.66
#Mann= 9 ,-1 , 0
  4328.9     .05       0  4819.6      .1       0  4946.3     .05       0
  4980.8      .1       0  4987.5     .07       0  4993.5      .1       0
  5286.5     .05       0  5304.2      .1       0  5541.4     .05       0
Bank Sta=4814,5539.4
XS Rating Curve= 0 ,0
Exp/Cntr=0.3,0.1

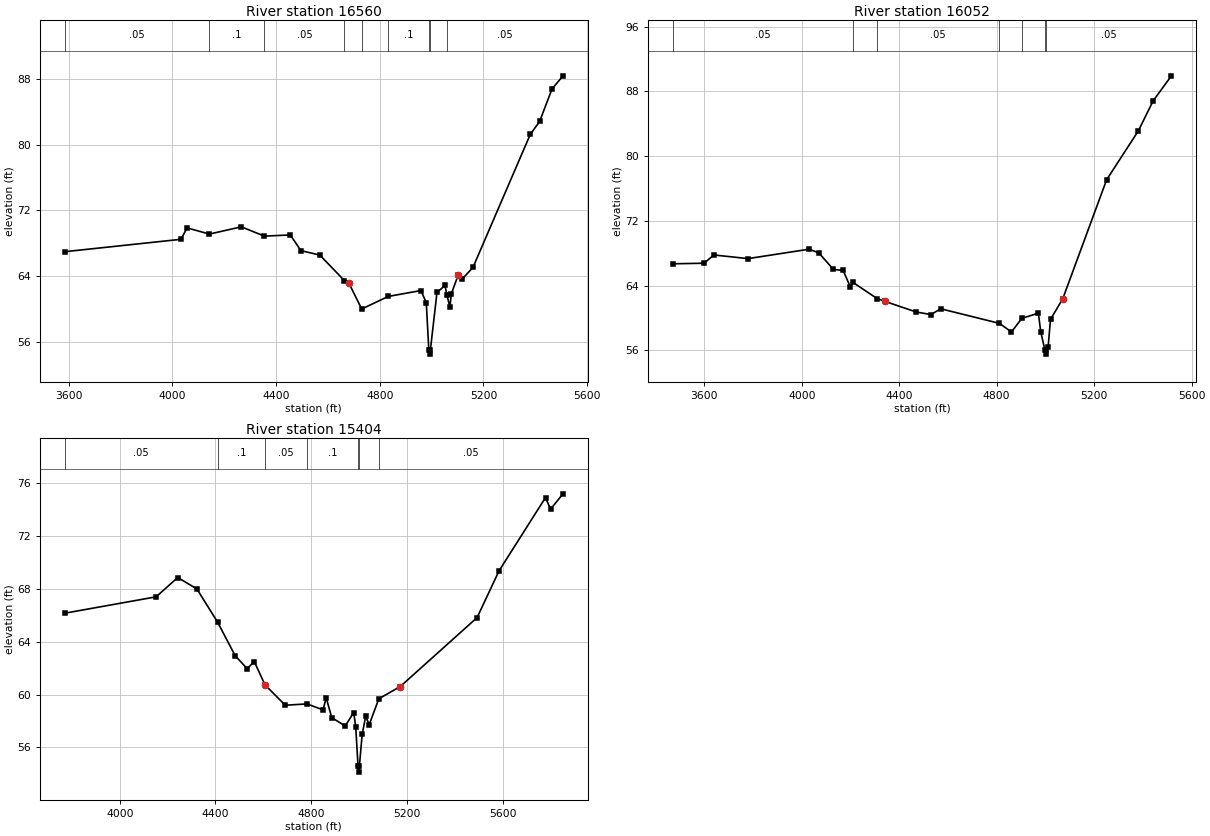
Type RM Length L Ch R = 1 ,16560   ,508,508,508
BEGIN DESCRIPTION:
Mapping XS b748205b
END DESCRIPTION:
XS GIS Cut Line= 3
       2342893.4     13183492.59      2342477.82     13181776.73
      2342512.95     13181623.89
#Sta/Elev= 30
  3584.6   66.95  4032.9   68.46  4056.7   69.85  4142.8    69.1  4265.8   69.98
    4355   68.85  4454.8   68.99  4495.9   67.08  4568.8   66.54  4663.5   63.43
  4681.2    63.1  4730.4   59.97  4832.8    61.5    4959   62.22  4979.5   60.72
  4989.2   54.97  4991.9   54.47  4995.2   54.97  5020.7   61.98  5051.6   62.84
  5058.9   61.66  5070.7    60.2  5075.8    61.8    5103   64.14  5117.6   63.61
  5159.5   65.03  5380.7   81.25  5416.6   82.82  5464.6   86.79  5506.9   88.38
#Mann= 9 ,-1 , 0
  3584.6     .05       0  4142.8      .1       0    4355     .05       0
  4663.5      .1       0  4730.4     .05       0  4832.8      .1       0
  4989.2     .07       0  4995.2      .1       0  5058.9     .05       0
Bank Sta=4681.2,5103
XS Rating Curve= 0 ,0
Exp/Cntr=0.3,0.1

Type RM Length L Ch R = 1 ,16052   ,648,648,648
BEGIN DESCRIPTION:
Mapping XS 2012a092
END DESCRIPTION:
XS GIS Cut Line= 2
      2343086.11     13183523.83      2342999.36     13181481.17
#Sta/Elev= 30
  3472.5   66.69  3599.6   66.76  3639.6   67.78  3779.8   67.33    4030   68.49
    4070   68.05  4130.1   65.99  4170.1   65.87  4200.1   63.79  4209.9    64.4
    4309    62.4  4340.3   62.06  4470.4   60.73  4530.4   60.42  4570.5   61.13
  4811.3   59.33  4860.7   58.27  4903.3   59.95  4971.1   60.59  4980.8   58.29
  4997.9   56.03  5000.6   55.53  5003.9   56.03  5010.9   56.38  5020.9   59.83
  5070.9   62.35  5251.1   77.07  5381.2   83.11    5442   86.82    5517   89.91
#Mann= 7 ,-1 , 0
  3472.5     .05       0  4209.9      .1       0    4309     .05       0
  4811.3      .1       0  4903.3     .12       0  4997.9     .07       0
  5003.9     .05       0
Bank Sta=4340.3,5070.9
XS Rating Curve= 0 ,0
Exp/Cntr=0.3,0.1

Type RM Length L Ch R = 1 ,15404   ,149,149,149
BEGIN DESCRIPTION:
Mapping XS 9bcf021d
END DESCRIPTION:
XS GIS Cut Line= 3
      2343190.28     13183529.08      2343185.07     13182664.49
      2344164.21     13181940.55
#Sta/Elev= 30
  3770.2   66.15  4152.4   67.39  4242.4   68.85  4322.4   67.99  4409.5   65.46
  4482.4   62.94  4532.4   61.96  4562.4   62.49  4607.2   60.73  4691.9   59.19
  4782.5   59.29  4849.5   58.84    4863   59.75  4886.1   58.25  4942.4   57.62
  4977.9   58.64  4986.3   57.55  4995.8   54.63  4998.5   54.13  5001.8   54.63
  5013.3      57    5028   58.35  5042.6   57.72  5082.9   59.68  5172.1    60.6
  5493.5   65.82  5585.3   69.36  5779.5    74.9  5800.4   74.02  5852.5   75.18
#Mann= 7 ,-1 , 0
  3770.2     .05       0  4409.5      .1       0  4607.2     .05       0
  4782.5      .1       0  4995.8     .07       0  5001.8      .1       0
  5082.9     .05       0
Bank Sta=4607.2,5172.1
XS Rating Curve= 0 ,0
Exp/Cntr=0.3,0.1