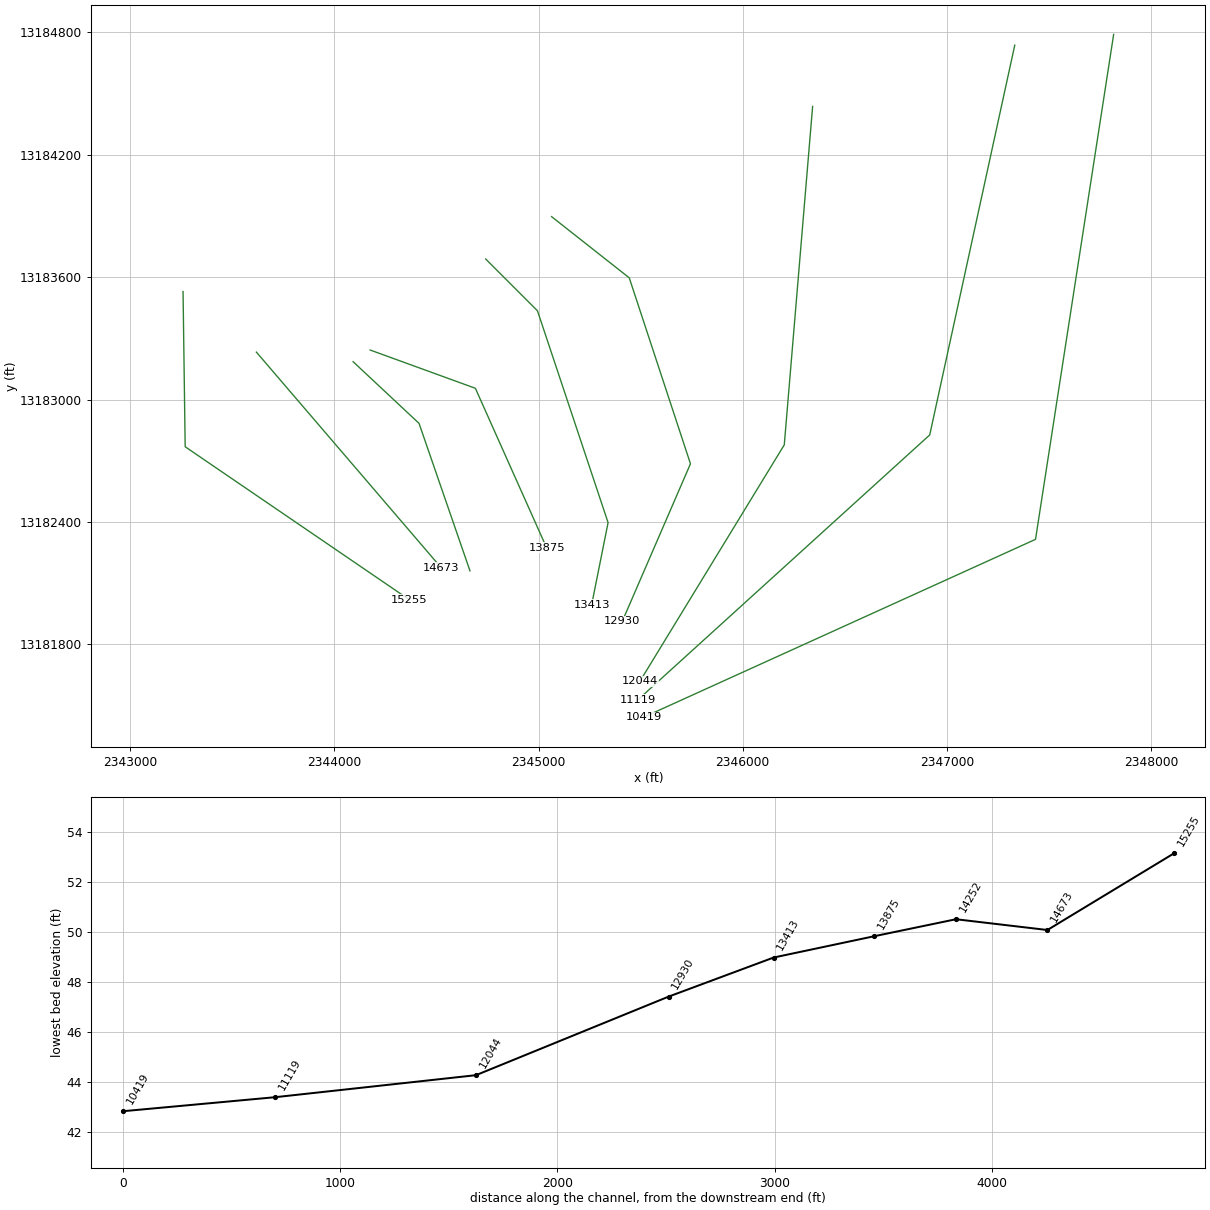
HEC-RAS study JAVELIN CREEK.prj: JAVELIN CREEK Base Level Engineering

--- JAVELIN CREEK.g01 (geometry) --- (continued)

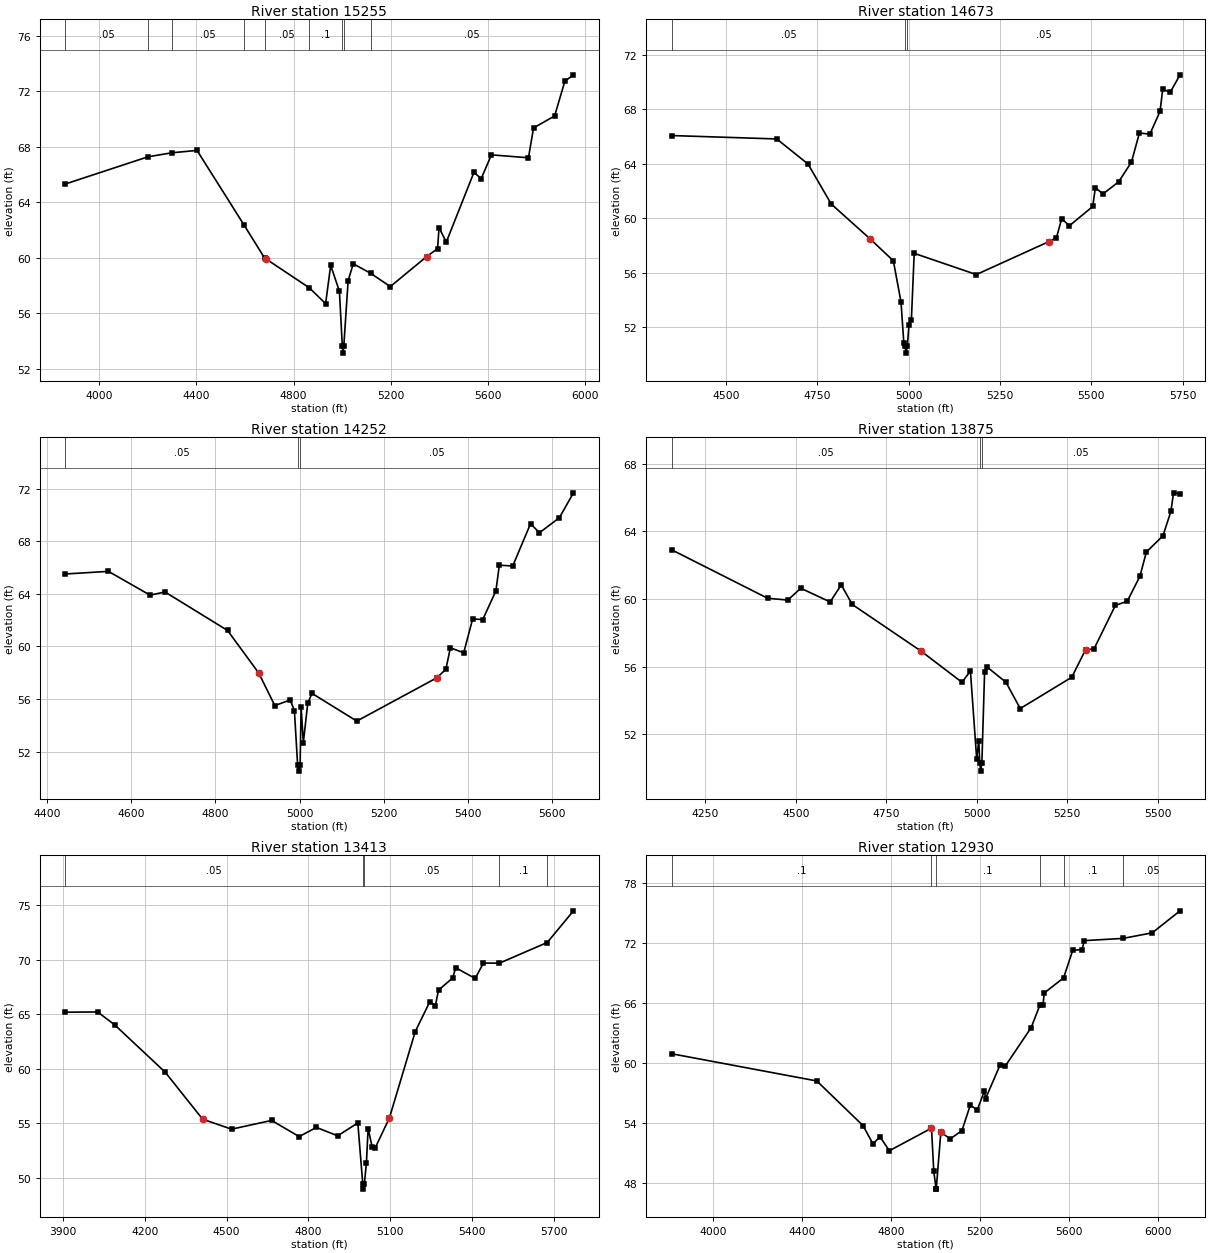
Type RM Length L Ch R = 1 ,15255   ,582,582,582
BEGIN DESCRIPTION:
Mapping XS 5b931839
END DESCRIPTION:
XS GIS Cut Line= 3
      2343257.99     13183529.07      2343268.41     13182768.65
      2344367.38     13182018.64
#Sta/Elev= 30
  3860.6   65.31  4201.2   67.27    4300   67.56  4402.9   67.73  4596.4   62.36
  4680.9   59.98  4686.6   59.92    4865   57.84  4931.9    56.7  4952.8   59.46
  4988.7   57.59  5000.7   53.64  5003.4   53.14  5006.7   53.64  5024.6   58.36
  5045.6   59.57  5116.8   58.89  5198.1   57.93  5347.7   60.09  5392.5   60.66
  5398.6   62.17  5428.4   61.13  5542.2   66.15    5572    65.7    5614   67.41
  5766.4    67.2  5787.4   69.35  5874.1   70.21  5916.1   72.71  5951.6   73.17
#Mann= 9 ,-1 , 0
  3860.6     .05       0  4201.2      .1       0    4300     .05       0
  4596.4      .1       0  4680.9     .05       0    4865      .1       0
  5000.7     .07       0  5006.7      .1       0  5116.8     .05       0
Bank Sta=4686.6,5347.7
XS Rating Curve= 0 ,0
Exp/Cntr=0.3,0.1

Type RM Length L Ch R = 1 ,14673   ,421,421,421
BEGIN DESCRIPTION:
Mapping XS 9a55db8c
END DESCRIPTION:
XS GIS Cut Line= 2
      2343617.34     13183232.22      2344523.18     13182175.41
#Sta/Elev= 30
  4351.2   66.06  4638.7   65.81  4724.4   63.97    4788   61.03  4894.5   58.47
  4958.1   56.86    4979   53.85  4986.7   50.84  4990.3   50.58    4993   50.08
  4996.3   50.58  5000.9   52.17  5007.5   52.54  5015.2   57.41  5185.3   55.85
    5384   58.27  5404.8   58.56  5419.1   59.96    5440   59.43  5504.1   60.85
  5511.3   62.23  5532.2   61.77    5575   62.66  5610.1   64.11    5632   66.25
  5660.6   66.16  5688.5   67.84  5695.7   69.45  5716.6   69.25  5743.1   70.52
#Mann= 3 ,-1 , 0
  4351.2     .05       0  4990.3     .03       0  4996.3     .05       0
Bank Sta=4894.5,5384
XS Rating Curve= 0 ,0
Exp/Cntr=0.3,0.1

Type RM Length L Ch R = 1 ,14252   ,377,377,377
BEGIN DESCRIPTION:
Mapping XS 1f923f96
END DESCRIPTION:
XS GIS Cut Line= 3
      2344091.31     13183185.34      2344414.24     13182883.24
      2344663.81     13182160.53
#Sta/Elev= 30
  4443.4   65.52  4546.1   65.72  4644.8   63.91  4680.4   64.15  4828.9   61.22
  4902.9   57.98  4941.1    55.5  4977.6   55.93  4987.6   55.12  4995.2   51.01
  4997.9   50.51  5001.2   51.01  5003.5   55.39  5008.8   52.68  5019.3   55.68
  5029.4   56.43  5135.7   54.32  5326.1   57.62  5347.3   58.27  5357.9    59.9
  5389.6   59.52  5410.8    62.1  5434.8   62.05    5466   64.23  5474.2   66.19
    5506   66.13  5548.3   69.35  5569.4   68.66  5616.6    69.8  5650.2    71.7
#Mann= 3 ,-1 , 0
  4443.4     .05       0  4995.2     .03       0  5001.2     .05       0
Bank Sta=4902.9,5326.1
XS Rating Curve= 0 ,0
Exp/Cntr=0.3,0.1

Type RM Length L Ch R = 1 ,13875   ,462,462,462
BEGIN DESCRIPTION:
Mapping XS b6acd688
END DESCRIPTION:
XS GIS Cut Line= 3
      2344174.66     13183242.61      2344690.28     13183055.11
      2345039.24     13182273.86
#Sta/Elev= 30
  4157.3   62.91  4422.1   60.05  4477.9   59.94  4513.8   60.64    4595   59.83
  4625.6   60.84  4656.1   59.68  4846.4   56.92  4959.3   55.08  4982.5   55.75
  4999.8   50.56  5005.7   51.63  5008.2   50.33  5010.9   49.83  5014.2   50.33
  5021.7   55.68  5028.9   55.98  5080.8   55.08  5120.2   53.53  5262.6   55.38
  5300.7   57.01  5323.9   57.05  5383.1   59.63  5415.9   59.87  5450.9   61.35
  5468.6   62.78  5514.5   63.74  5536.4   65.18  5543.7   66.28  5561.6   66.23
#Mann= 3 ,-1 , 0
  4157.3     .05       0  5008.2     .03       0  5014.2     .05       0
Bank Sta=4846.4,5300.7
XS Rating Curve= 0 ,0
Exp/Cntr=0.3,0.1

Type RM Length L Ch R = 1 ,13413   ,483,483,483
BEGIN DESCRIPTION:
Mapping XS ce97bcf4
END DESCRIPTION:
XS GIS Cut Line= 4
      2344740.83     13183688.48      2344994.52     13183434.79
      2345340.51     13182396.84      2345259.78     13181993.21
#Sta/Elev= 30
  3908.1   65.18  4027.3    65.2  4090.9   63.99  4275.2   59.68  4412.3   55.38
  4518.6   54.47  4665.3   55.27  4766.3   53.79  4829.5   54.63  4907.7   53.86
  4981.5   55.04  4999.6   49.48  5002.3   48.98  5005.6   49.48  5013.1   51.39
  5019.3   54.53  5034.2   52.83  5044.7   52.72  5097.4    55.5  5192.3   63.41
  5245.9   66.15  5266.1   65.78  5277.5    67.2  5329.3   68.31  5340.8   69.25
  5411.9   68.27  5442.5   69.68    5501   69.67  5676.4   71.56  5772.6   74.46
#Mann= 5 ,-1 , 0
  3908.1     .05       0  4999.6     .03       0  5005.6     .05       0
    5501      .1       0  5676.4     .05       0
Bank Sta=4412.3,5097.4
XS Rating Curve= 0 ,0
Exp/Cntr=0.3,0.1

Type RM Length L Ch R = 1 ,12930   ,887,887,887
BEGIN DESCRIPTION:
Mapping XS ef03be9c
END DESCRIPTION:
XS GIS Cut Line= 4
      2345063.75     13183896.07       2345444.3     13183596.25
      2345744.15     13182685.16       2345409.7     13181912.46
#Sta/Elev= 30
  3814.2   60.96  4466.5   58.24  4674.6   53.77  4719.1   51.95  4750.7   52.66
  4792.8   51.26  4982.3   53.52  4992.5    49.2  5003.1   47.42  5003.6   47.42
  5024.3   53.11  5066.6   52.45  5119.2   53.27  5156.7   55.82  5188.4   55.35
  5220.2   57.24  5225.5   56.48  5290.4   59.82  5313.8   59.72  5430.3   63.57
  5470.1   65.85  5483.7   65.83  5489.1   67.04  5576.2   68.55  5617.4   71.31
    5659   71.38    5670   72.28  5842.8    72.5  5975.2   73.06  6099.8   75.26
#Mann= 6 ,-1 , 0
  3814.2      .1       0  4982.3     .05       0  5003.6      .1       0
  5470.1     .05       0  5576.2      .1       0  5842.8     .05       0
Bank Sta=4982.3,5024.3
XS Rating Curve= 0 ,0
Exp/Cntr=0.3,0.1

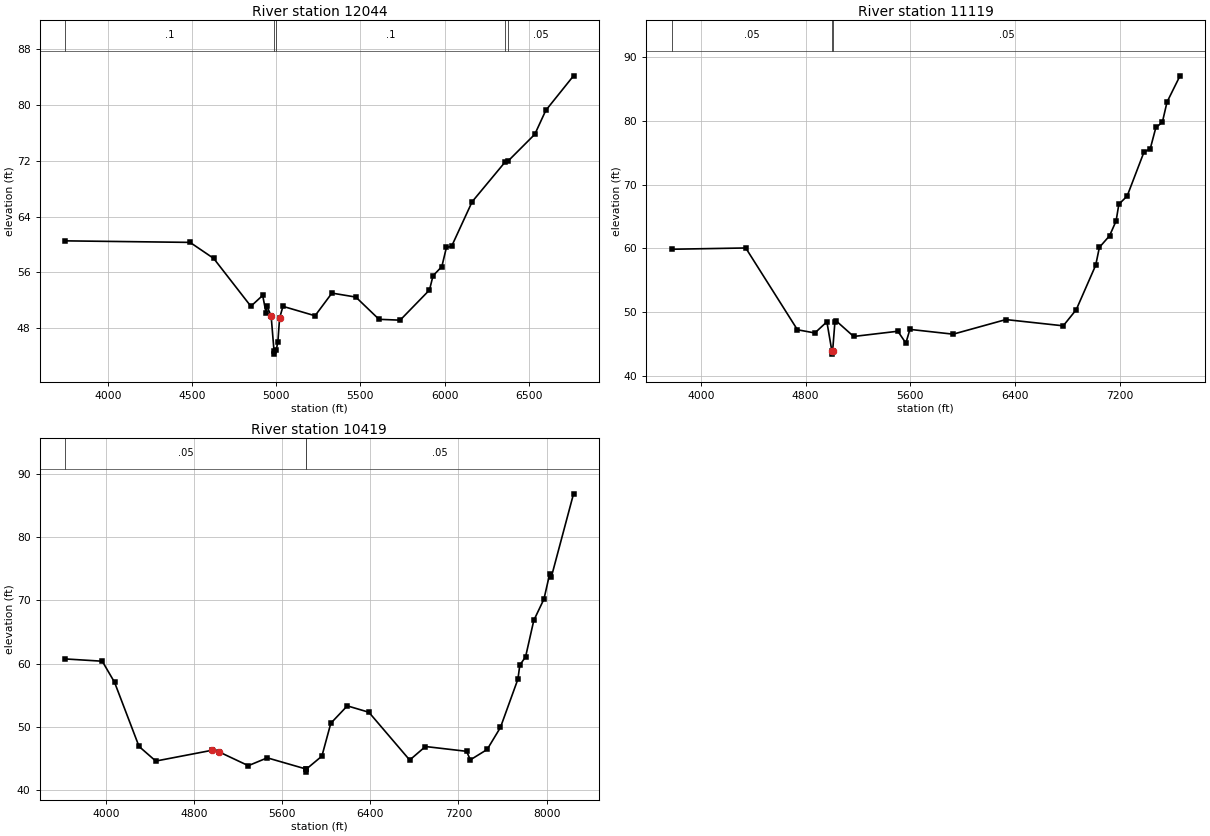
Type RM Length L Ch R = 1 ,12044   ,925,925,925
BEGIN DESCRIPTION:
Mapping XS 7ec4e017
END DESCRIPTION:
XS GIS Cut Line= 3
      2346342.71     13184435.96      2346203.83     13182778.01
      2345497.19     13181620.52
#Sta/Elev= 30
  3746.5   60.52  4488.2    60.3  4628.7      58  4849.5   51.14  4919.7    52.7
  4939.5   50.21  4944.6   51.18  4969.9   49.74  4986.9   44.78  4989.7   44.28
    5000   44.88    5010   46.05  5020.1   49.44  5040.1   51.13  5230.8   49.78
  5331.1   53.03    5473   52.46  5610.8   49.27  5736.2   49.15  5910.5   53.47
  5931.8   55.52    5984   56.83  6011.2   59.57  6042.1   59.74  6164.1   66.13
  6358.8   71.79  6375.4   71.91  6536.4    75.8  6601.5   79.22  6766.4   84.18
#Mann= 5 ,-1 , 0
  3746.5      .1       0  4986.9     .05       0    5000      .1       0
  6358.8      .1       0  6375.4     .05       0
#XS Ineff= 2 , 0
                            5530           51.08
Permanent Ineff=
       F       F
Bank Sta=4969.9,5020.1
XS Rating Curve= 0 ,0
Exp/Cntr=0.3,0.1

Type RM Length L Ch R = 1 ,11119   ,700,700,700
BEGIN DESCRIPTION:
Mapping XS c0092d94
END DESCRIPTION:
XS GIS Cut Line= 3
      2347333.17     13184736.35       2346916.5     13182826.62
      2345485.96     13181528.02
#Sta/Elev= 30
  3775.4   59.85  4341.7   60.05    4737   47.22  4870.1   46.72  4962.2   48.47
  5000.1    43.9  5002.9    43.4  5006.1    43.9  5023.6   48.46  5033.8    48.6
  5166.9   46.17  5504.6   46.99  5566.1   45.13  5596.8   47.28  5927.4   46.53
  6330.8   48.82  6769.4   47.84  6868.8   50.37  7017.4   57.34  7045.8   60.15
  7123.5   61.96  7173.5   64.29  7194.5   66.91    7258   68.19  7385.7   75.04
  7435.1   75.65  7477.6   78.95    7527   79.75  7562.8   82.93  7662.1   87.05
#Mann= 3 ,-1 , 0
  3775.4     .05       0  5000.1    .035       0  5006.1     .05       0
Bank Sta=5000.1,5006.1
XS Rating Curve= 0 ,0
Exp/Cntr=0.3,0.1

Type RM Length L Ch R = 1 ,10419   ,0,0,0
BEGIN DESCRIPTION:
JAVELIN CREEK 1.0
END DESCRIPTION:
XS GIS Cut Line= 3
      2347817.67     13184789.01      2347434.86     13182314.93
      2345513.79       13181443.
#Sta/Elev= 30
  3631.2   60.74  3967.3   60.38  4078.6   57.06  4301.2    46.9  4453.2   44.59
  4967.8   46.31  5029.8   46.02  5292.9   43.86  5464.9    45.1  5814.9   43.34
  5817.6   42.84  5820.9   43.34  5960.7   45.37  6041.7   50.57  6191.3   53.32
  6386.9   52.31  6757.5   44.75  6900.3   46.89  7273.7   46.13  7307.8   44.78
  7460.4   46.42  7581.2   49.91  7739.7   57.55  7756.9   59.77    7809   61.06
  7883.7   66.83    7976   70.21  8027.7   74.17  8042.4   73.66  8244.4   86.85
#Mann= 3 ,-1 , 0
  3631.2     .05       0  5814.9    .035       0  5820.9     .05       0
Bank Sta=4967.8,5029.8
XS Rating Curve= 0 ,0
Exp/Cntr=0.3,0.1

Chan Stop Cuts=-1
Use User Specified Reach Order=0
Composite Channel Slope=5