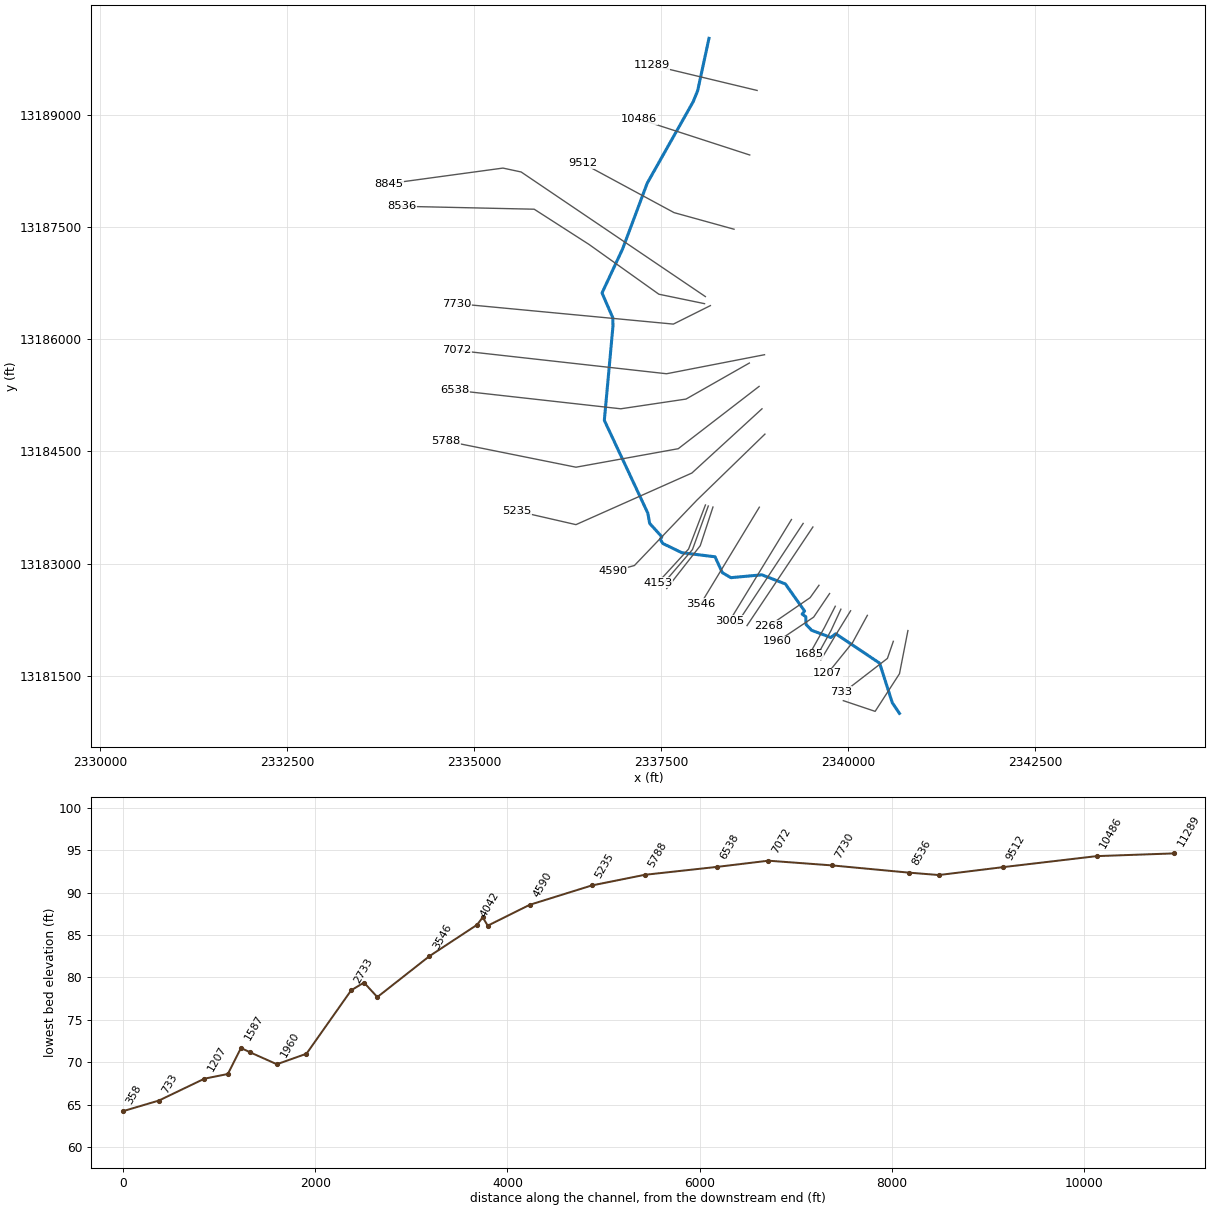
--- LAIN CREEK.prj (project) ---

Proj Title=LAIN CREEK Base Level Engineering
Current Plan=p01
Default Exp/Contr=0.3,0.1
English Units
Geom File=g01
Flow File=f01
Plan File=p01
Y Axis Title=Elevation
X Axis Title(PF)=Main Channel Distance
X Axis Title(XS)=Station
BEGIN DESCRIPTION:
LAIN CREEK
END DESCRIPTION:
DSS Export Rating Curves= 0
DSS Export Rating Curve Sorted= 0
DSS Export Volume Flow Curves= 0
DXF OffsetX= 0
DXF OffsetY= 0
DXF ScaleX= 1
DXF ScaleY= 10

--- LAIN CREEK.p01 (plan) ---

Plan Title=Multiple Run
Short Identifier=Multiple
Geom File=g01
Flow File=f01
Subcritical Flow
K Sum by GR= 0
Std Step Tol= 0.01
Critical Tol= 0.01
Num of Std Step Trials= 20
Max Error Tol= 0.3
Flow Tol Ratio= 0.001
Split Flow NTrial= 30
Split Flow Tol= 0.02
Split Flow Ratio= 0.02
Log Output Level= 0
Friction Slope Method= 1
Unsteady Friction Slope Method= 2
Unsteady Bridges Friction Slope Method= 1
Parabolic Critical Depth
Global Vel Dist=  1 , 1 , 1
Global Log Level= 0
CheckData=True
Encroach Param= -1, 0, 0, 0
BEGIN DESCRIPTION:
Multiple Run
END DESCRIPTION:

--- LAIN CREEK.f01 (steady flow) ---

Flow Title=Multiple
Program Version=4.10
Number of Profiles= 7
Profile Names=10-year,25-year,50-year,1pct_min,100-year,1pct_plu,500-year
River Rch & RM=LAIN CREEK,Reach-1         ,11289
     229     295     344     293     396     536     527
River Rch & RM=LAIN CREEK,Reach-1         ,8845
     982    1396    1743    1584    2142    2897    3255
River Rch & RM=LAIN CREEK,Reach-1         ,8536
     982    1396    1743    1584    2142    2897    3255
River Rch & RM=LAIN CREEK,Reach-1         ,3546
    1054    1508    1892    1729    2338    3163    3592
Boundary for River Rch & Prof#=LAIN CREEK,Reach-1         , 1
Up Type= 0
Dn Type= 3
Dn Slope=0.005
Boundary for River Rch & Prof#=LAIN CREEK,Reach-1         , 2
Up Type= 0
Dn Type= 3
Dn Slope=0.005
Boundary for River Rch & Prof#=LAIN CREEK,Reach-1         , 3
Up Type= 0
Dn Type= 3
Dn Slope=0.005
Boundary for River Rch & Prof#=LAIN CREEK,Reach-1         , 4
Up Type= 0
Dn Type= 3
Dn Slope=0.005
Boundary for River Rch & Prof#=LAIN CREEK,Reach-1         , 5
Up Type= 0
Dn Type= 3
Dn Slope=0.005
Boundary for River Rch & Prof#=LAIN CREEK,Reach-1         , 6
Up Type= 0
Dn Type= 3
Dn Slope=0.005
Boundary for River Rch & Prof#=LAIN CREEK,Reach-1         , 7
Up Type= 0
Dn Type= 3
Dn Slope=0.005
DSS Import GetInterval= 0
DSS Import GetPeak= 0
DSS Import FillOption= 0

--- LAIN CREEK.g01 (geometry) ---

Geom Title=Existing Conditions
Program Version=4.10

River Reach=LAIN CREEK      ,Reach-1
Reach XY= 30
      2338141.48     13190026.13      2337990.44     13189327.24
      2337930.25     13189178.52      2337315.67     13188088.24
      2336986.97     13187209.77      2336711.79     13186620.07
      2336855.17     13186289.94      2336858.41     13186182.53
      2336742.67     13184916.33       2337323.8     13183675.24
      2337348.42     13183538.39      2337510.46     13183359.43
      2337491.82     13183321.68      2337524.69     13183269.36
      2337778.78     13183145.96       2338222.3     13183091.33
      2338320.04     13182878.99      2338434.43     13182811.99
      2338848.23     13182850.14      2339162.12     13182728.37
      2339419.52      13182365.4      2339387.12      13182324.2
      2339435.73     13182289.48      2339438.61     13182186.54
      2339513.97       13182108.      2339769.99     13182012.16
      2339835.17     13182061.95      2340422.39     13181668.46
      2340591.79     13181138.48      2340687.72     13180996.86

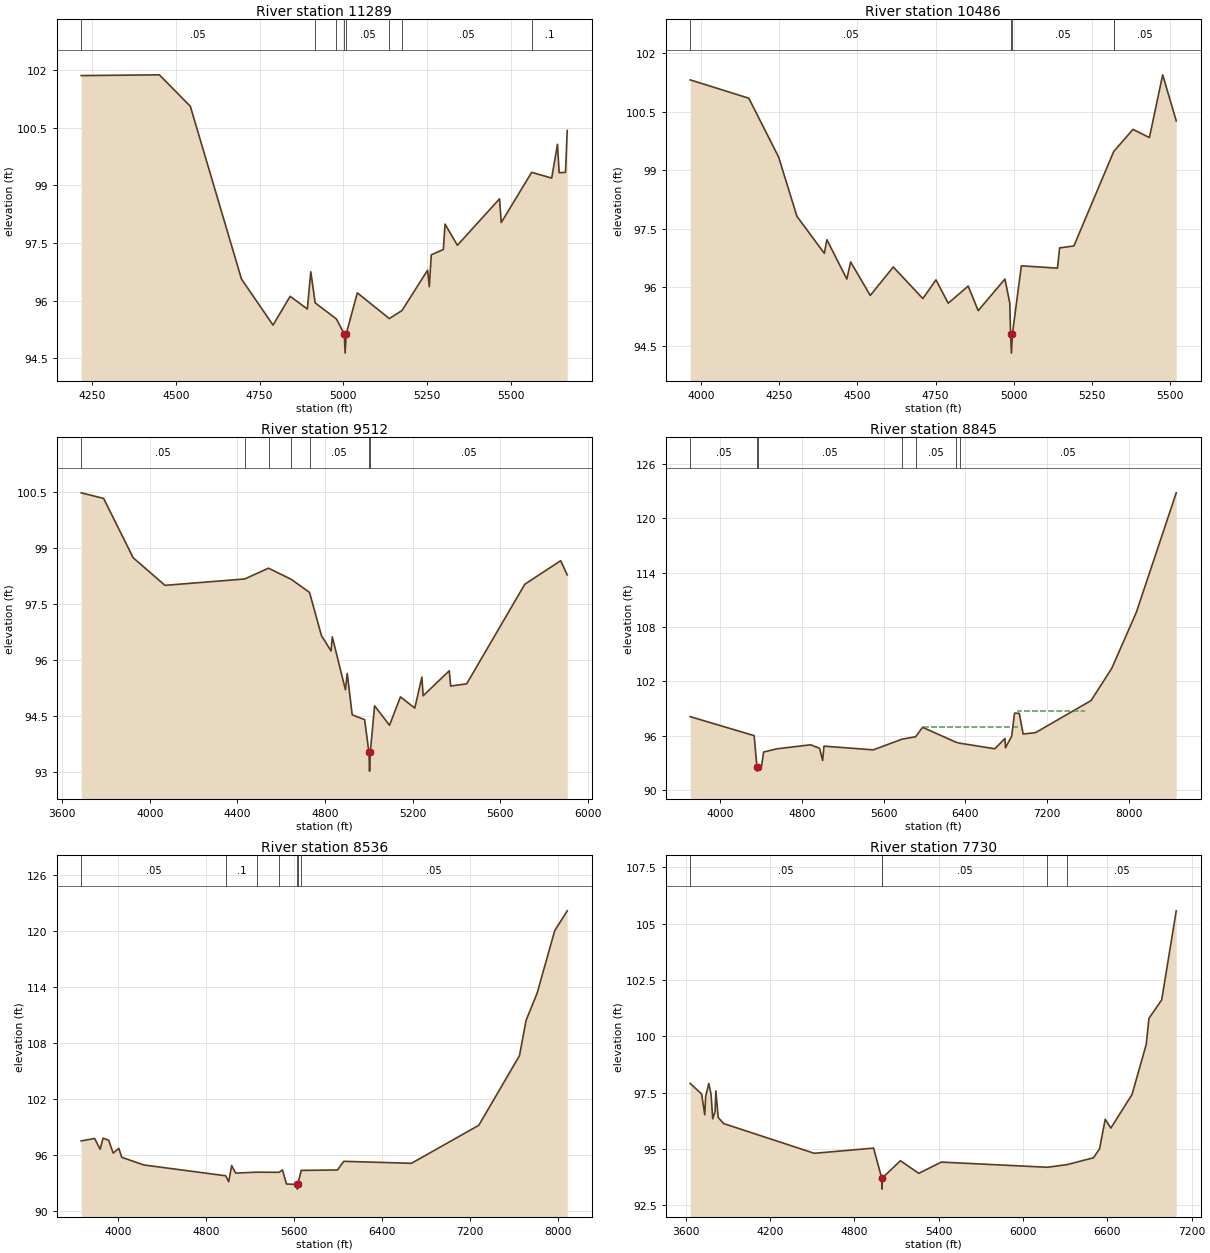
Type RM Length L Ch R = 1 ,11289   ,803,803,803
BEGIN DESCRIPTION:
LAIN CREEK 16.0
END DESCRIPTION:
XS GIS Cut Line= 2
      2338784.77     13189329.13      2337372.63     13189668.29
#Sta/Elev= 30
  4217.2  101.86  4450.7  101.88  4543.3  101.06  4696.1   96.56  4790.4   95.36
  4841.5   96.11  4892.9   95.78  4903.2   96.75  4916.3   95.94  4979.8   95.52
  5003.1   95.13  5005.8   94.63  5009.1   95.13  5042.3    96.2  5137.9   95.53
  5175.8   95.74  5252.2   96.79  5257.3   96.36  5263.2   97.19  5299.3   97.33
  5304.4   97.99  5341.3   97.44  5467.2   98.65  5472.3   98.03  5563.2   99.34
  5623.1   99.19  5640.3  100.07  5645.4   99.33  5664.3   99.34  5669.5  100.43
#Mann= 8 ,-1 , 0
  4217.2     .05       0  4916.3     .12       0  4979.8     .05       0
  5003.1     .03       0  5009.1     .05       0  5137.9      .1       0
  5175.8     .05       0  5563.2      .1       0
Bank Sta=5003.1,5009.1
XS Rating Curve= 0 ,0
Exp/Cntr=0.3,0.1

Type RM Length L Ch R = 1 ,10486   ,974,974,974
BEGIN DESCRIPTION:
Mapping XS 2eac6fda
END DESCRIPTION:
XS GIS Cut Line= 2
      2338686.13      13188465.7      2337206.04     13188946.73
#Sta/Elev= 30
  3964.4  101.32    4152  100.85  4247.5   99.34  4306.1   97.82  4393.8   96.87
    4402   97.22  4465.9   96.21    4478   96.65    4541   95.79  4614.6   96.52
  4709.3   95.71  4751.3   96.19  4790.6   95.59  4854.5   96.03  4886.5    95.4
  4972.2   96.21  4987.6    95.6  4990.2   94.81  4992.9   94.31  4996.2   94.81
  5024.8   96.55  5140.4   96.49  5147.3   97.01    5193   97.06  5320.4   99.48
  5321.2   99.49  5382.2  100.05  5434.8   99.84  5477.3  101.45  5520.7  100.27
#Mann= 5 ,-1 , 0
  3964.4     .05       0  4990.2     .03       0  4996.2     .05       0
  5320.4      .1       0  5321.2     .05       0
Bank Sta=4990.2,4996.2
XS Rating Curve= 0 ,0
Exp/Cntr=0.3,0.1

Type RM Length L Ch R = 1 ,9512    ,667,667,667
BEGIN DESCRIPTION:
Mapping XS a1469f28
END DESCRIPTION:
XS GIS Cut Line= 3
      2338476.44     13187472.77       2337674.7     13187694.79
      2336453.61     13188354.68
#Sta/Elev= 30
  3686.5  100.47  3788.9  100.32  3923.8   98.73  4069.1   97.99    4433   98.16
    4542   98.45  4646.2   98.15  4729.4    97.8  4783.9   96.64  4827.7   96.23
  4833.3   96.61  4893.3   95.19  4901.5   95.63  4924.2   94.52    4981   94.39
  5000.8   93.51  5003.5   93.01  5006.8   93.51  5026.5   94.76  5094.7   94.24
  5144.5      95  5210.2    94.7  5242.5   95.53  5248.3   95.03  5367.5    95.7
  5373.9   95.29  5447.1   95.35  5712.7   98.02  5876.4   98.65  5906.4   98.27
#Mann= 7 ,-1 , 0
  3686.5     .05       0    4433      .1       0    4542     .05       0
  4646.2      .1       0  4729.4     .05       0  5000.8     .03       0
  5006.8     .05       0
Bank Sta=5000.8,5006.8
XS Rating Curve= 0 ,0
Exp/Cntr=0.3,0.1

Type RM Length L Ch R = 1 ,8845    ,309,309,309
BEGIN DESCRIPTION:
LAIN CREEK 15.0
END DESCRIPTION:
XS GIS Cut Line= 4
      2338093.25     13186571.85       2335630.4     13188238.63
      2335387.34     13188290.71      2333861.19      13188082.6
#Sta/Elev= 30
  3704.7    98.1  4331.2      96  4358.1   92.58  4360.9   92.08  4364.1   92.58
  4403.1   92.61  4424.1   94.19  4555.9   94.55  4885.5   94.99  4972.3    94.6
  5002.3   93.25  5015.5   94.84  5498.5   94.43  5779.9   95.61  5913.9   95.88
  5981.4   96.92  6308.2   95.28  6344.8   95.17  6690.2   94.55    6789   95.69
  6794.2   94.66  6855.1   95.95  6882.8   98.49  6929.5   98.46  6967.1   96.18
  7088.2   96.33  7633.2   99.88  7835.1  103.43  8077.3  109.65  8467.4  122.83
#Mann= 7 ,-1 , 0
  3704.7     .05       0  4358.1    .035       0  4364.1     .05       0
  5779.9      .1       0  5913.9     .05       0  6308.2      .1       0
  6344.8     .05       0
#XS Ineff= 2 ,-1
 5981.35 6917.04   96.93 6917.05 7571.59   98.72
Permanent Ineff=
       F       F
Bank Sta=4358.1,4364.1
XS Rating Curve= 0 ,0
Exp/Cntr=0.3,0.1

Type RM Length L Ch R = 1 ,8536    ,806,806,806
BEGIN DESCRIPTION:
Mapping XS 08dd8ca3
END DESCRIPTION:
XS GIS Cut Line= 5
      2338082.09     13186477.18      2337471.67     13186603.34
       2336537.1     13187269.96      2335805.13     13187740.51
      2334034.01     13187779.73
#Sta/Elev= 30
  3667.1   97.53    3789   97.79  3839.2   96.63  3865.6   97.83  3916.6   97.59
  3957.5   96.22  4008.5   96.73  4035.1   95.77    4236   94.95  4979.6   93.79
  5006.3   93.15  5033.4   94.89  5069.1   94.08  5267.6   94.18  5462.7   94.16
  5494.2   94.42  5530.6   92.91  5627.3   92.86  5630.1   92.36  5633.3   92.86
  5664.8   94.37  5993.5   94.41    6051   95.34    6666   95.13    7277    99.2
  7646.3  106.66  7706.3  110.44  7806.3  113.35  7966.4  120.06  8080.1  122.19
#Mann= 7 ,-1 , 0
  3667.1     .05       0  4979.6      .1       0  5267.6     .05       0
  5462.7      .1       0  5627.3     .07       0  5633.3      .1       0
  5664.8     .05       0
Bank Sta=5627.3,5633.3
XS Rating Curve= 0 ,0
Exp/Cntr=0.3,0.1

Type RM Length L Ch R = 1 ,7730    ,658,658,658
BEGIN DESCRIPTION:
LAIN CREEK 14.0
END DESCRIPTION:
XS GIS Cut Line= 3
      2338160.24     13186451.16      2337665.41     13186203.75
      2334774.75     13186477.19
#Sta/Elev= 30
  3633.2   97.91  3714.3   97.44  3736.6   96.52  3742.8   97.33  3765.2   97.91
  3781.4   97.43  3793.2   96.34  3809.9   96.67  3815.5   97.58  3832.3    96.4
  3870.8   96.13  4515.6   94.81  4937.5   95.04  4994.7   93.72  4997.5   93.22
  5000.7   93.72  5128.3   94.48  5258.9   93.92  5419.6   94.42  6174.3   94.19
  6314.9   94.31  6500.9   94.61  6544.6   95.01  6584.8   96.32    6625   95.93
  6775.6   97.42  6876.1   99.63  6896.2   100.8  6986.6  101.62    7090  105.57
#Mann= 5 ,-1 , 0
  3633.2     .05       0  4994.7    .035       0  5000.7     .05       0
  6174.3      .1       0  6314.9     .05       0
Bank Sta=4994.7,5000.7
XS Rating Curve= 0 ,0
Exp/Cntr=0.3,0.1

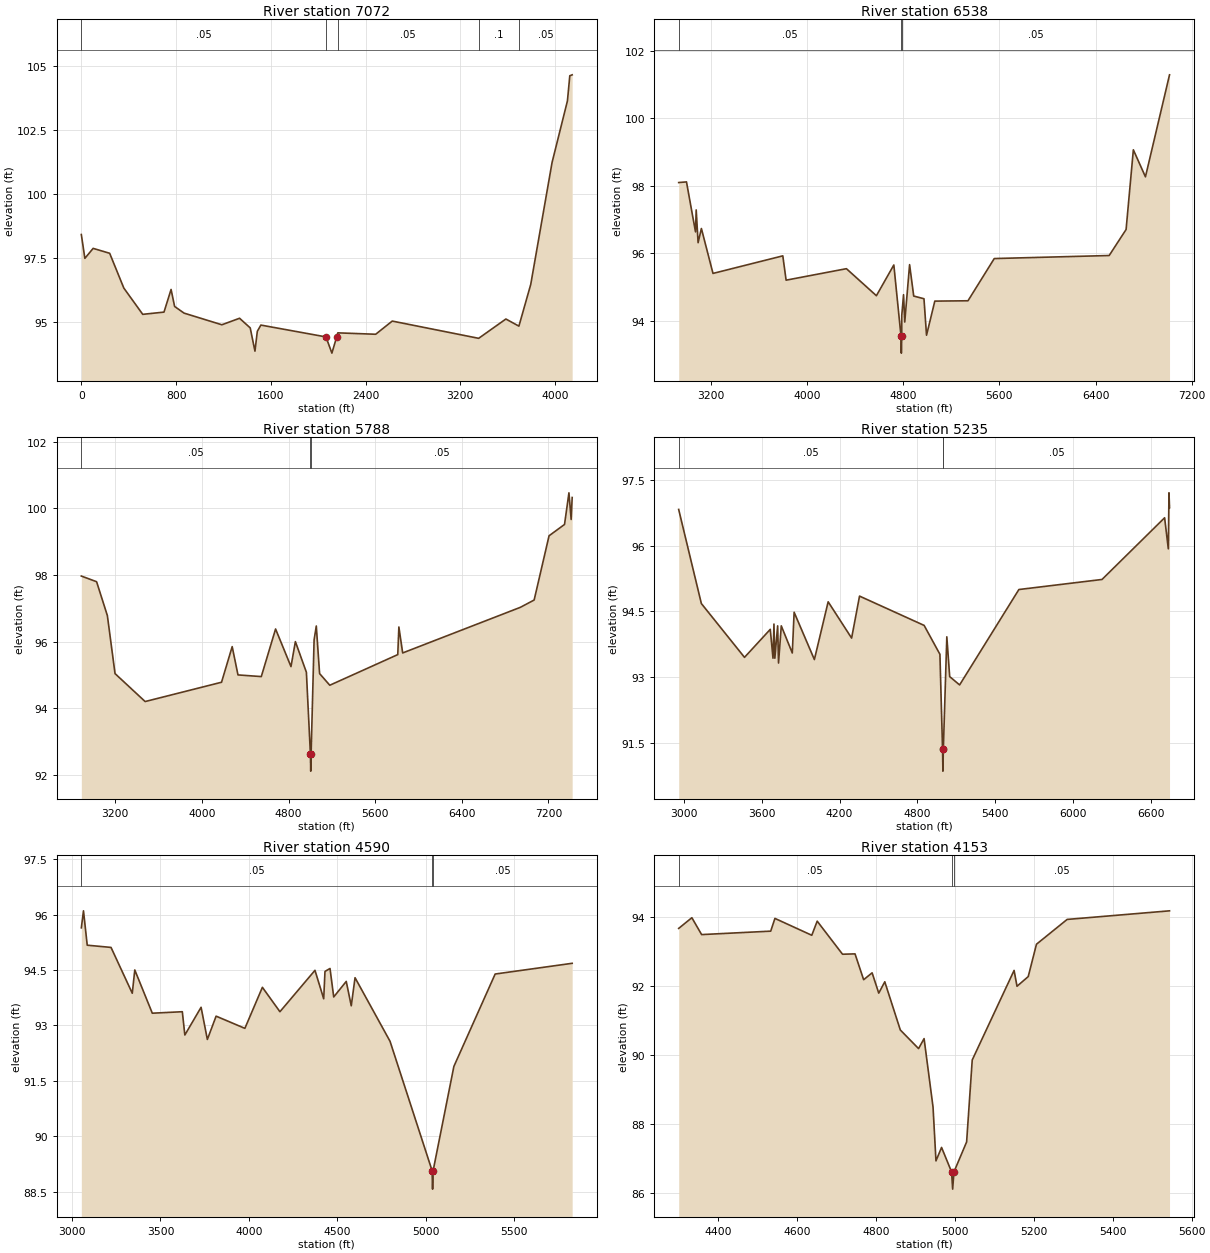
Type RM Length L Ch R = 1 ,7072    ,534,534,534
BEGIN DESCRIPTION:
LAIN CREEK 12.0
END DESCRIPTION:
XS GIS Cut Line= 3
     2338883.948     13185794.29      2337574.26     13185539.68
     2334774.781     13185852.18
#Sta/Elev= 30
       0 98.407129.91263  97.47699.70876 97.8658 239.301 97.6743358.9515 96.3127
518.4855 95.2864697.9613 95.3738757.7866 96.2589787.6992 95.5942867.4662 95.3342
1186.534 94.87821336.097 95.13291426.044 94.75571466.021 93.84641486.009 94.6226
1515.991 94.86622065.666 94.40352115.636 93.76952155.613 94.39452165.607  94.562
2485.417 94.50742625.335 95.02293354.903 94.34823584.767 95.10373694.702 94.8251
3794.643 96.45673974.537101.2216 4104.46103.63514124.448 104.6174144.436104.6531
#Mann= 5 ,-1 , 0
       0     .05       02065.666    .035       02165.607     .05       0
3354.903      .1       03694.702     .05       0
Bank Sta=2065.666,2155.613
XS Rating Curve= 0 ,0
Exp/Cntr=0.3,0.1

Type RM Length L Ch R = 1 ,6538    ,750,750,750
BEGIN DESCRIPTION:
LAIN CREEK 11.0
END DESCRIPTION:
XS GIS Cut Line= 4
      2338681.03     13185682.91      2337834.68     13185201.14
      2336962.28     13185070.93      2334748.69     13185318.33
#Sta/Elev= 30
  2932.1   98.09    2997   98.11    3072   96.63  3077.7   97.28  3093.6   96.31
    3121   96.73  3217.5    95.4  3798.3   95.92  3825.7    95.2  4327.5   95.54
  4576.9   94.74  4721.9   95.65  4781.7   93.54  4784.4   93.04  4787.7   93.54
  4787.8   94.15  4802.7   94.77  4812.7   93.96    4853   95.66  4887.3   94.73
  4972.6   94.65  4993.9   93.57  5062.8   94.58  5338.8   94.59  5557.4   95.84
  6513.3   95.93  6654.1    96.7  6714.5   99.06  6815.1   98.26  7015.4  101.28
#Mann= 3 ,-1 , 0
  2932.1     .05       0  4781.7    .035       0  4787.7     .05       0
Bank Sta=4781.7,4787.7
XS Rating Curve= 0 ,0
Exp/Cntr=0.3,0.1

Type RM Length L Ch R = 1 ,5788    ,553,553,553
BEGIN DESCRIPTION:
LAIN CREEK 10.0
END DESCRIPTION:
XS GIS Cut Line= 4
      2338811.25     13185370.42      2337730.51     13184537.08
      2336363.32     13184289.68      2334618.49     13184641.25
#Sta/Elev= 30
  2885.9   97.97  3026.9    97.8  3126.6   96.78  3197.2   95.04  3475.3    94.2
    4181   94.78  4279.4   95.85  4332.9      95  4548.2   94.95  4680.3   96.38
  4822.5   95.25  4863.2      96  4964.8   95.08  5002.2   92.61    5005   92.11
  5008.2   92.61    5036   96.05  5056.3   96.47  5086.8   95.04  5180.9   94.69
  5808.9   95.61  5819.1   96.44  5854.2   95.66  6941.2   97.03  7068.7   97.25
  7206.5   99.18  7349.3   99.52  7390.1  100.47  7410.5   99.67  7419.9  100.33
#Mann= 3 ,-1 , 0
  2885.9     .05       0  5002.2     .03       0  5008.2     .05       0
Bank Sta=5002.2,5008.2
XS Rating Curve= 0 ,0
Exp/Cntr=0.3,0.1

Type RM Length L Ch R = 1 ,5235    ,645,645,645
BEGIN DESCRIPTION:
LAIN CREEK 9.0
END DESCRIPTION:
XS GIS Cut Line= 4
      2338850.29     13185070.92       2337912.8     13184211.56
      2336363.32     13183521.45       2335570.9     13183703.32
#Sta/Elev= 30
  2960.7   96.83  3135.3   94.68  3467.7   93.45  3666.2   94.09  3687.2   93.43
  3694.6   94.21  3701.4   93.43    3723   94.17  3729.8   93.32    3751   94.17
  3835.8   93.55    3850   94.48    4006    93.4  4112.1   94.72  4292.8   93.89
  4353.8   94.85  4851.4   94.18    4973   93.52  4993.3   91.35    4996   90.85
  4999.3   91.35  5026.2   93.92  5048.2   93.01  5124.7   92.82  5581.3      95
  6221.7   95.23  6703.9   96.64  6732.4   95.93  6737.5   97.21  6741.7   96.87
#Mann= 3 ,-1 , 0
  2960.7     .05       0  4993.3    .035       0  4999.3     .05       0
Bank Sta=4993.3,4999.3
XS Rating Curve= 0 ,0
Exp/Cntr=0.3,0.1

Type RM Length L Ch R = 1 ,4590    ,437,437,437
BEGIN DESCRIPTION:
LAIN CREEK 8.0
END DESCRIPTION:
XS GIS Cut Line= 4
      2338889.34     13184732.37      2337977.91     13183846.98
      2337144.57     13182974.58      2336858.16     13182896.47
#Sta/Elev= 30
  3052.8   95.64    3065    96.1  3086.1   95.17  3220.6   95.11  3340.7   93.87
  3354.9    94.5  3453.9   93.33  3623.6   93.37  3637.8   92.74  3729.6   93.49
  3765.1   92.62  3814.5   93.25  3977.1   92.92  4076.1   94.03  4175.2   93.37
  4373.2   94.49  4422.6   93.72  4429.8   94.46  4458.2   94.54  4479.2   93.77
    4550   94.19  4578.3   93.53  4599.7   94.29  4797.5   92.57  5035.1   89.07
  5037.9   88.57  5041.1   89.07  5158.3   91.89  5391.6   94.39  5826.8   94.68
#Mann= 3 ,-1 , 0
  3052.8     .05       0  5035.1    .035       0  5041.1     .05       0
Bank Sta=5035.1,5041.1
XS Rating Curve= 0 ,0
Exp/Cntr=0.3,0.1

Type RM Length L Ch R = 1 ,4153    ,52,52,52
BEGIN DESCRIPTION:
Mapping XS 95a8b76d
END DESCRIPTION:
XS GIS Cut Line= 3
      2338094.05     13183784.68      2337868.36     13183194.41
      2337455.17     13182743.02
#Sta/Elev= 30
    4300   93.68  4333.4   93.99  4358.1    93.5  4533.2    93.6  4543.9   93.97
  4637.3   93.48    4651   93.89  4715.2   92.93  4746.9   92.94  4768.7   92.19
  4790.2   92.39    4807    91.8  4822.3   92.13  4861.7   90.73  4907.9   90.19
  4921.9   90.48  4944.6   88.49    4952   86.93  4966.2   87.32  4991.6   86.61
  4994.3   86.11  4997.6   86.61  5029.7   87.48  5043.9   89.86    5150   92.46
  5157.4      92  5185.8   92.28  5206.7   93.22  5284.4   93.94  5543.9   94.19
#Mann= 3 ,-1 , 0
    4300     .05       0  4991.6    .035       0  4997.6     .05       0
Bank Sta=4991.6,4997.6
XS Rating Curve= 0 ,0
Exp/Cntr=0.3,0.1

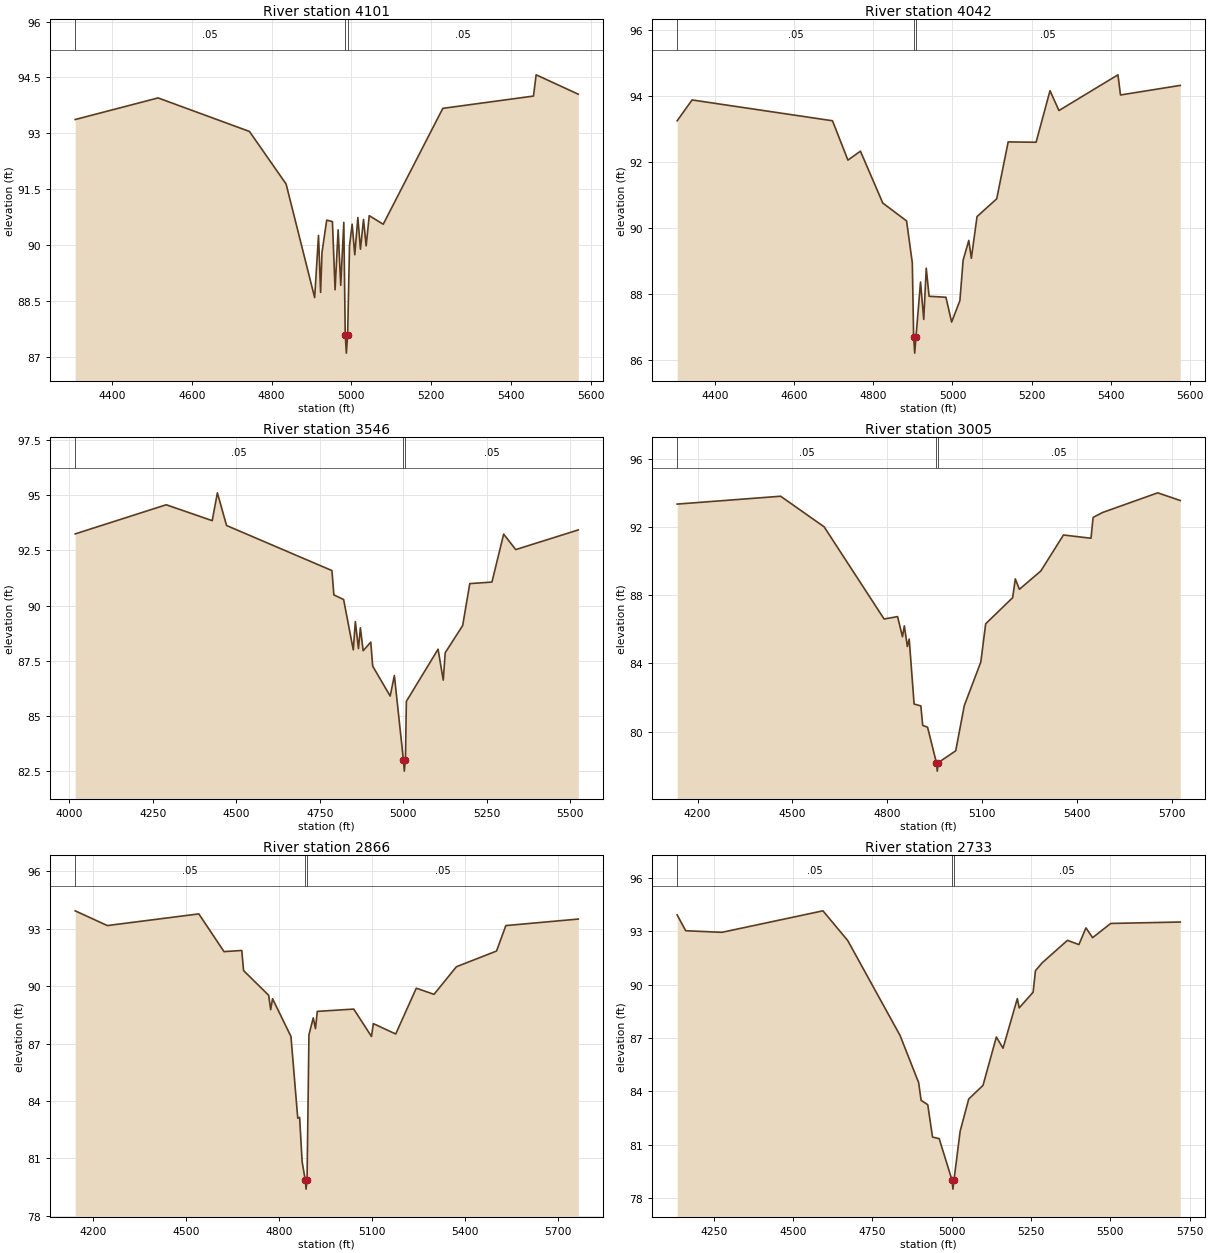
Type RM Length L Ch R = 1 ,4101    ,59,59,59
BEGIN DESCRIPTION:
Mapping XS 7c6d9896
END DESCRIPTION:
XS GIS Cut Line= 3
      2338132.25      13183770.8      2337920.45     13183187.47
        2337504.     13182701.62
#Sta/Elev= 30
  4307.9   93.37  4515.6   93.95  4744.5   93.05  4836.3   91.64  4907.9   88.59
  4917.5   90.26  4922.8   88.73  4926.2    89.8  4938.1   90.67  4952.4   90.63
    4959    88.8  4966.7   90.41  4973.2   88.92  4980.9   90.61  4984.5    87.6
  4987.3    87.1  4990.5    87.6  4995.2   89.98  5001.8   90.56  5008.4   89.74
  5016.1   90.74  5022.6   89.89  5030.3   90.69  5036.9   89.98  5044.6   90.79
  5079.7   90.56    5229   93.67  5456.1      94  5462.8   94.57  5568.4   94.05
#Mann= 3 ,-1 , 0
  4307.9     .05       0  4984.5    .035       0  4990.5     .05       0
Bank Sta=4984.5,4990.5
XS Rating Curve= 0 ,0
Exp/Cntr=0.3,0.1

Type RM Length L Ch R = 1 ,4042    ,496,496,496
BEGIN DESCRIPTION:
Mapping XS fb96e4ba
END DESCRIPTION:
XS GIS Cut Line= 3
      2338194.76     13183756.94      2338024.61     13183239.55
      2337576.68     13182666.61
#Sta/Elev= 30
    4304   93.24  4341.7   93.87  4696.7   93.24  4735.7   92.05  4767.3   92.32
  4823.9   90.75    4884   90.21  4898.5   88.94  4901.8   86.71  4904.6   86.21
  4907.8   86.71  4919.3   88.36  4927.4   87.23  4933.7   88.78  4940.9   87.93
  4983.5    87.9  4997.9   87.15  5018.8    87.8  5026.9   89.02  5041.3   89.62
  5047.7   89.08  5062.1   90.34  5111.9   90.88  5140.8    92.6  5211.4   92.59
  5246.6   94.15  5269.2   93.55  5418.4   94.63  5424.8   94.02  5575.9   94.31
#Mann= 3 ,-1 , 0
    4304     .05       0  4901.8    .035       0  4907.8     .05       0
Bank Sta=4901.8,4907.8
XS Rating Curve= 0 ,0
Exp/Cntr=0.3,0.1

Type RM Length L Ch R = 1 ,3546    ,541,541,541
BEGIN DESCRIPTION:
Mapping XS a70cd6d2
END DESCRIPTION:
XS GIS Cut Line= 2
       2338814.4     13183754.65      2338033.17     13182465.61
#Sta/Elev= 30
  4017.2   93.25    4290   94.57  4427.7   93.85  4443.2   95.11  4470.7   93.63
  4786.4   91.59  4792.2   90.49  4821.4   90.28  4850.4      88  4856.5   89.28
  4865.9   88.06  4871.7      89  4879.9   87.96  4902.7   88.35  4908.6   87.26
  4960.9   85.91  4973.5   86.84  5000.6   83.01  5003.3   82.51  5006.6   83.01
  5009.4   85.67  5104.4   88.03  5119.9   86.63  5125.8   87.87  5178.1    89.1
  5199.4      91  5265.8   91.07  5300.9   93.24  5337.1   92.54  5524.5   93.43
#Mann= 3 ,-1 , 0
  4017.2     .05       0  5000.6    .035       0  5006.6     .05       0
Bank Sta=5000.6,5006.6
XS Rating Curve= 0 ,0
Exp/Cntr=0.3,0.1

Type RM Length L Ch R = 1 ,3005    ,139,139,139
BEGIN DESCRIPTION:
LAIN CREEK 7.0
END DESCRIPTION:
XS GIS Cut Line= 2
      2339244.14     13183589.79      2338415.28     13182231.51
#Sta/Elev= 30
  4135.3   93.33  4462.6   93.79  4600.1      92  4789.8    86.6  4832.4   86.74
  4847.9   85.56  4853.8    86.2  4863.4   84.99  4869.2   85.43  4884.7   81.62
    4906   81.51  4911.9   80.37  4927.3   80.26  4955.2   78.19    4958   77.69
  4961.2   78.19  5016.3   78.88  5043.5   81.53  5095.7   84.08  5111.1   86.32
  5196.4   87.85  5204.8   88.95  5217.7   88.34  5285.4   89.41  5357.1   91.52
  5444.2   91.33  5450.8   92.55    5481   92.84  5655.2   93.99  5726.5   93.54
#Mann= 3 ,-1 , 0
  4135.3     .05       0  4955.2    .035       0  4961.2     .05       0
Bank Sta=4955.2,4961.2
XS Rating Curve= 0 ,0
Exp/Cntr=0.3,0.1

Type RM Length L Ch R = 1 ,2866    ,133,133,133
BEGIN DESCRIPTION:
LAIN CREEK 6.0
END DESCRIPTION:
XS GIS Cut Line= 2
      2339400.39     13183537.71      2338506.24     13182183.46
#Sta/Elev= 30
  4141.7   93.93  4245.5   93.16  4540.5   93.77  4621.8    91.8    4679   91.86
  4684.9   90.81  4765.8   89.52  4772.3   88.77  4778.3   89.34  4837.7   87.37
  4859.6    83.1  4865.6   83.15  4873.7   80.83  4883.6    79.9  4886.4    79.4
  4889.6    79.9  4895.7   87.46  4909.6   88.34  4916.8   87.78  4922.7   88.68
  5040.2    88.8  5097.4   87.37  5103.4   88.04  5175.6    87.5  5241.9   89.89
  5299.1   89.57  5371.3   91.01  5500.7   91.83  5530.9   93.16  5764.5    93.5
#Mann= 3 ,-1 , 0
  4141.7     .05       0  4883.6    .035       0  4889.6     .05       0
Bank Sta=4883.6,4889.6
XS Rating Curve= 0 ,0
Exp/Cntr=0.3,0.1

Type RM Length L Ch R = 1 ,2733    ,465,465,465
BEGIN DESCRIPTION:
Mapping XS ed1f5df6
END DESCRIPTION:
XS GIS Cut Line= 2
      2339530.58     13183489.93      2338649.93     13182171.13
#Sta/Elev= 30
  4134.4   93.92  4161.3   93.03  4275.5   92.94  4593.9   94.15    4672   92.48
  4837.2   87.13  4895.6   84.48  4903.3   83.49  4924.3   83.24  4939.3   81.42
  4960.3   81.33  5000.9   78.99  5003.6   78.49  5006.9   78.99  5026.4   81.75
  5053.4   83.56  5098.5   84.33  5140.5   87.05  5161.6   86.42  5206.6   89.21
  5212.6   88.69  5256.4   89.57  5263.7   90.78  5284.7   91.22  5364.6   92.49
  5400.7   92.25  5422.9   93.19  5443.9   92.64    5501   93.44  5720.2   93.52
#Mann= 3 ,-1 , 0
  4134.4     .05       0  5000.9    .035       0  5006.9     .05       0
Bank Sta=5000.9,5006.9
XS Rating Curve= 0 ,0
Exp/Cntr=0.3,0.1

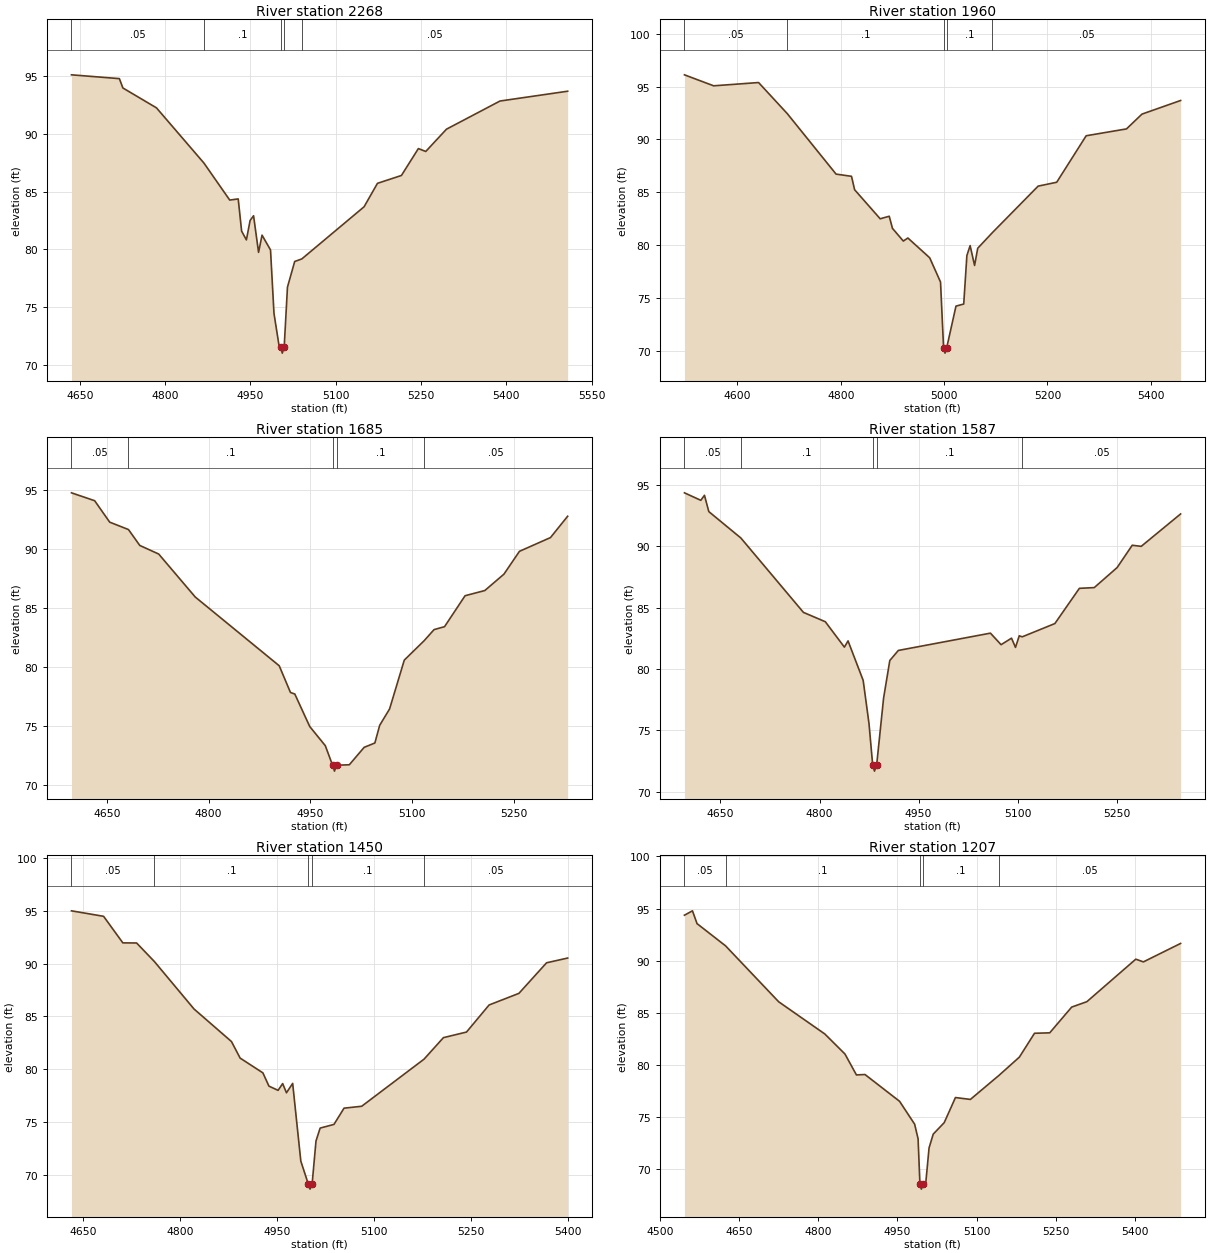
Type RM Length L Ch R = 1 ,2268    ,308,308,308
BEGIN DESCRIPTION:
LAIN CREEK 5.0
END DESCRIPTION:
XS GIS Cut Line= 3
      2339611.79     13182710.23      2339493.45     13182544.55
      2338942.03     13182166.44
#Sta/Elev= 30
  4635.5   95.12  4719.7   94.79  4725.9   93.98  4784.9   92.26  4868.3   87.48
  4913.7   84.27  4928.6   84.37  4934.6   81.58    4943   80.82  4949.5    82.5
  4955.6   82.91  4964.4   79.74  4970.5   81.23  4985.4   79.95  4991.5   74.45
  5000.3   71.69  5003.4   71.51  5006.1   71.01  5009.4   71.51  5015.2   76.73
  5027.9   78.95  5040.4   79.17  5149.9   83.69  5173.4   85.72  5215.5    86.4
  5245.3   88.73  5258.3   88.48  5294.7   90.41  5388.8   92.85  5507.7    93.7
#Mann= 5 ,-1 , 0
  4635.5     .05       0  4868.3      .1       0  5003.4     .07       0
  5009.4      .1       0  5040.4     .05       0
Bank Sta=5003.4,5009.4
XS Rating Curve= 0 ,0
Exp/Cntr=0.3,0.1

Type RM Length L Ch R = 1 ,1960    ,275,275,275
BEGIN DESCRIPTION:
Mapping XS 03ab767b
END DESCRIPTION:
XS GIS Cut Line= 3
      2339753.74     13182599.77      2339540.77     13182284.26
      2339059.62     13181960.86
#Sta/Elev= 30
  4497.4   96.12    4554   95.08  4640.9   95.39  4696.4   92.45  4790.9   86.72
  4820.8   86.51  4826.8   85.24  4876.3   82.49  4893.8   82.73  4900.1   81.58
  4921.1   80.38  4929.9   80.67  4972.1    78.8  4993.1    76.5    4999   70.27
  5001.8   69.77    5005   70.27    5023   74.22    5038   74.42  5044.1   79.01
  5050.4   79.95    5059   78.07  5065.1    79.7  5093.1   81.16    5182   85.58
    5218   85.95    5275   90.35  5353.1      91    5383    92.4  5457.8   93.69
#Mann= 5 ,-1 , 0
  4497.4     .05       0  4696.4      .1       0    4999     .07       0
    5005      .1       0  5093.1     .05       0
Bank Sta=4999,5005
XS Rating Curve= 0 ,0
Exp/Cntr=0.3,0.1

Type RM Length L Ch R = 1 ,1685    ,98,98,98
BEGIN DESCRIPTION:
LAIN CREEK 4.0
END DESCRIPTION:
XS GIS Cut Line= 3
      2339829.68     13182429.49      2339682.06     13182140.28
      2339483.24     13181784.81
#Sta/Elev= 30
  4597.8    94.8    4632   94.13  4654.2   92.31  4681.9   91.68  4698.6   90.33
  4726.5    89.6  4780.4   85.95  4904.3   80.11  4920.9   77.84  4927.3   77.71
  4949.3   74.95  4972.3   73.32    4983   71.66  4985.8   71.16    4989   71.66
  5007.7    71.7  5029.6   73.18  5045.4   73.55  5052.5   75.05  5067.1   76.44
  5088.8   80.59  5118.3   82.25  5132.7   83.18  5148.2   83.43  5178.5   86.06
  5207.6    86.5  5235.8   87.89  5258.7   89.83  5304.5      91  5329.8   92.81
#Mann= 5 ,-1 , 0
  4597.8     .05       0  4681.9      .1       0    4983     .07       0
    4989      .1       0  5118.3     .05       0
Bank Sta=4983,4989
XS Rating Curve= 0 ,0
Exp/Cntr=0.3,0.1

Type RM Length L Ch R = 1 ,1587    ,137,137,137
BEGIN DESCRIPTION:
Mapping XS 084d2173
END DESCRIPTION:
XS GIS Cut Line= 3
      2339904.99     13182390.32      2339772.44     13182104.13
      2339562.22     13181722.73
#Sta/Elev= 30
  4595.6   94.36  4620.4   93.75  4625.9   94.16  4632.5   92.83    4681   90.68
  4775.7   84.62  4808.8   83.86  4837.7   81.79  4843.2    82.3  4866.1   79.08
  4874.9   75.57  4880.5   72.19  4883.2   71.69  4886.5   72.19    4897   77.64
  4906.4    80.7  4919.3   81.52  5058.7   82.93  5074.8   81.99  5090.6   82.52
  5096.6   81.77  5102.3   82.71  5106.8   82.63  5156.2   83.71  5193.3   86.58
  5215.8   86.64  5250.4   88.27  5273.3   90.09  5286.9      90  5346.5   92.64
#Mann= 5 ,-1 , 0
  4595.6     .05       0    4681      .1       0  4880.5     .07       0
  4886.5      .1       0  5106.8     .05       0
Bank Sta=4880.5,4886.5
XS Rating Curve= 0 ,0
Exp/Cntr=0.3,0.1

Type RM Length L Ch R = 1 ,1450    ,243,243,243
BEGIN DESCRIPTION:
LAIN CREEK 3.0
END DESCRIPTION:
XS GIS Cut Line= 3
      2340034.54     13182369.24      2339832.69     13182040.86
      2339636.86     13181712.47
#Sta/Elev= 30
  4631.7   95.02  4681.4    94.5  4711.2   91.98  4732.5   91.97    4760   90.21
  4821.3   85.71  4879.3   82.62  4892.7   81.05  4927.9   79.65  4937.3   78.39
  4951.4   77.99  4958.5   78.63  4964.4   77.76    4974   78.65  4986.6   71.28
  4998.1   69.12  5000.9   68.62  5004.1   69.12  5010.1   73.19  5016.5   74.41
  5037.9   74.76  5053.5    76.3  5080.8   76.48  5177.3   80.95  5207.3   82.99
    5243   83.52    5278   86.09  5324.1   87.19  5366.9   90.09  5399.5   90.54
#Mann= 5 ,-1 , 0
  4631.7     .05       0    4760      .1       0  4998.1     .07       0
  5004.1      .1       0  5177.3     .05       0
Bank Sta=4998.1,5004.1
XS Rating Curve= 0 ,0
Exp/Cntr=0.3,0.1

Type RM Length L Ch R = 1 ,1207    ,474,474,474
BEGIN DESCRIPTION:
Mapping XS 6de8283d
END DESCRIPTION:
XS GIS Cut Line= 3
      2340258.52     13182307.88      2340061.36     13181945.09
       2339730.1     13181534.96
#Sta/Elev= 30
  4546.6   94.36  4561.8   94.78  4570.5   93.55  4624.5   91.42  4725.2   86.05
  4812.6   82.96  4850.7   81.04  4872.5   79.03  4888.7   79.07  4954.2    76.5
  4982.8    74.3  4989.3    72.9  4992.8   68.57  4995.5   68.07  4998.8   68.57
  5003.7   68.58  5010.1   72.03    5018   73.35  5038.8   74.45  5060.1   76.86
  5088.4   76.68  5142.4   78.98  5181.2   80.74  5209.9   83.03  5238.7   83.07
  5280.3   85.54  5309.1   86.06  5401.8   90.14  5416.2   89.88  5486.7   91.65
#Mann= 5 ,-1 , 0
  4546.6     .05       0  4624.5      .1       0  4992.8     .07       0
  4998.8      .1       0  5142.4     .05       0
Bank Sta=4992.8,4998.8
XS Rating Curve= 0 ,0
Exp/Cntr=0.3,0.1

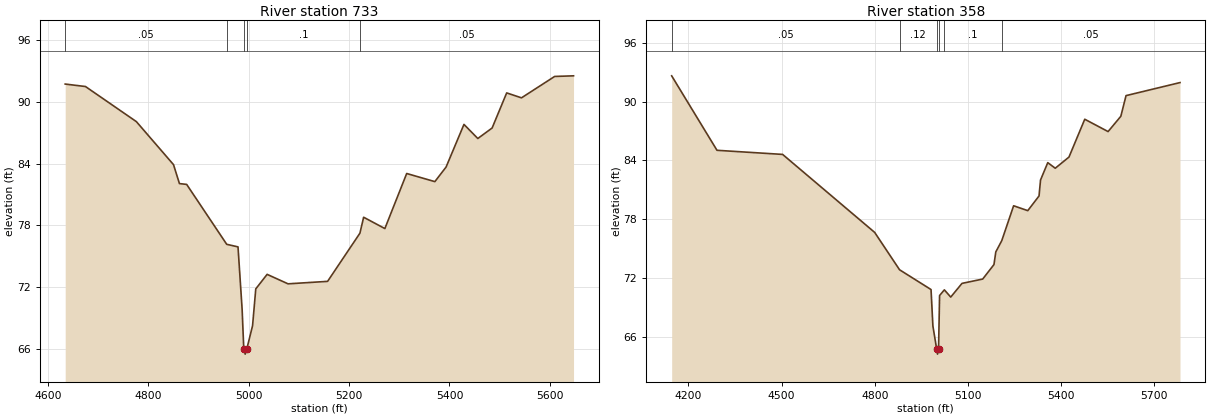
Type RM Length L Ch R = 1 ,733     ,375,375,375
BEGIN DESCRIPTION:
LAIN CREEK 2.0
END DESCRIPTION:
XS GIS Cut Line= 4
      2340605.61     13181960.88      2340526.72     13181732.12
      2340006.14     13181329.86      2339903.61     13181282.53
#Sta/Elev= 30
  4634.4   91.73  4674.8   91.49  4776.2   88.08  4850.2    83.9    4862   82.06
  4876.4   81.98  4956.2   76.16  4978.7   75.91  4986.9   69.84  4990.2   65.99
    4993   65.49  4996.2   65.99  5007.7   68.25  5014.1   71.83  5036.7   73.24
  5078.4   72.32  5157.2   72.56  5221.6   77.24    5229   78.79  5271.3   77.69
  5314.8   83.04  5370.9   82.25  5393.3   83.67  5428.9   87.81  5456.5   86.44
    5485   87.46    5514   90.87  5543.5   90.39  5609.6   92.47  5647.2   92.53
#Mann= 5 ,-1 , 0
  4634.4     .05       0  4956.2      .1       0  4990.2     .07       0
  4996.2      .1       0  5221.6     .05       0
Bank Sta=4990.2,4996.2
XS Rating Curve= 0 ,0
Exp/Cntr=0.3,0.1

Type RM Length L Ch R = 1 ,358     ,0,0,0
BEGIN DESCRIPTION:
LAIN CREEK 1.0
END DESCRIPTION:
XS GIS Cut Line= 4
      2340800.83     13182104.52      2340687.98     13181527.25
      2340362.46     13181023.78      2339937.15       13181167.
#Sta/Elev= 30
  4146.4   92.63  4292.3   85.03  4503.6   84.61    4800   76.65    4880   72.84
  4981.4   70.82  4987.4    67.1  4999.6   64.73  5002.3   64.23  5005.6   64.73
  5008.9   70.21  5024.3   70.79  5044.8   70.05  5081.1   71.45  5147.7   71.89
    5184   73.37  5189.9   74.66  5209.1   75.81  5247.3   79.37  5292.8   78.87
  5329.1   80.37  5333.9      82  5357.2   83.77  5381.3    83.2  5425.5   84.34
  5476.3    88.2  5551.4   86.94  5592.4    88.5  5609.2   90.61  5782.9   91.94
#Mann= 6 ,-1 , 0
  4146.4     .05       0    4880     .12       0  4999.6     .07       0
  5005.6     .12       0  5024.3      .1       0  5209.1     .05       0
Bank Sta=4999.6,5005.6
XS Rating Curve= 0 ,0
Exp/Cntr=0.3,0.1

Chan Stop Cuts=-1
Use User Specified Reach Order=0
Composite Channel Slope=5