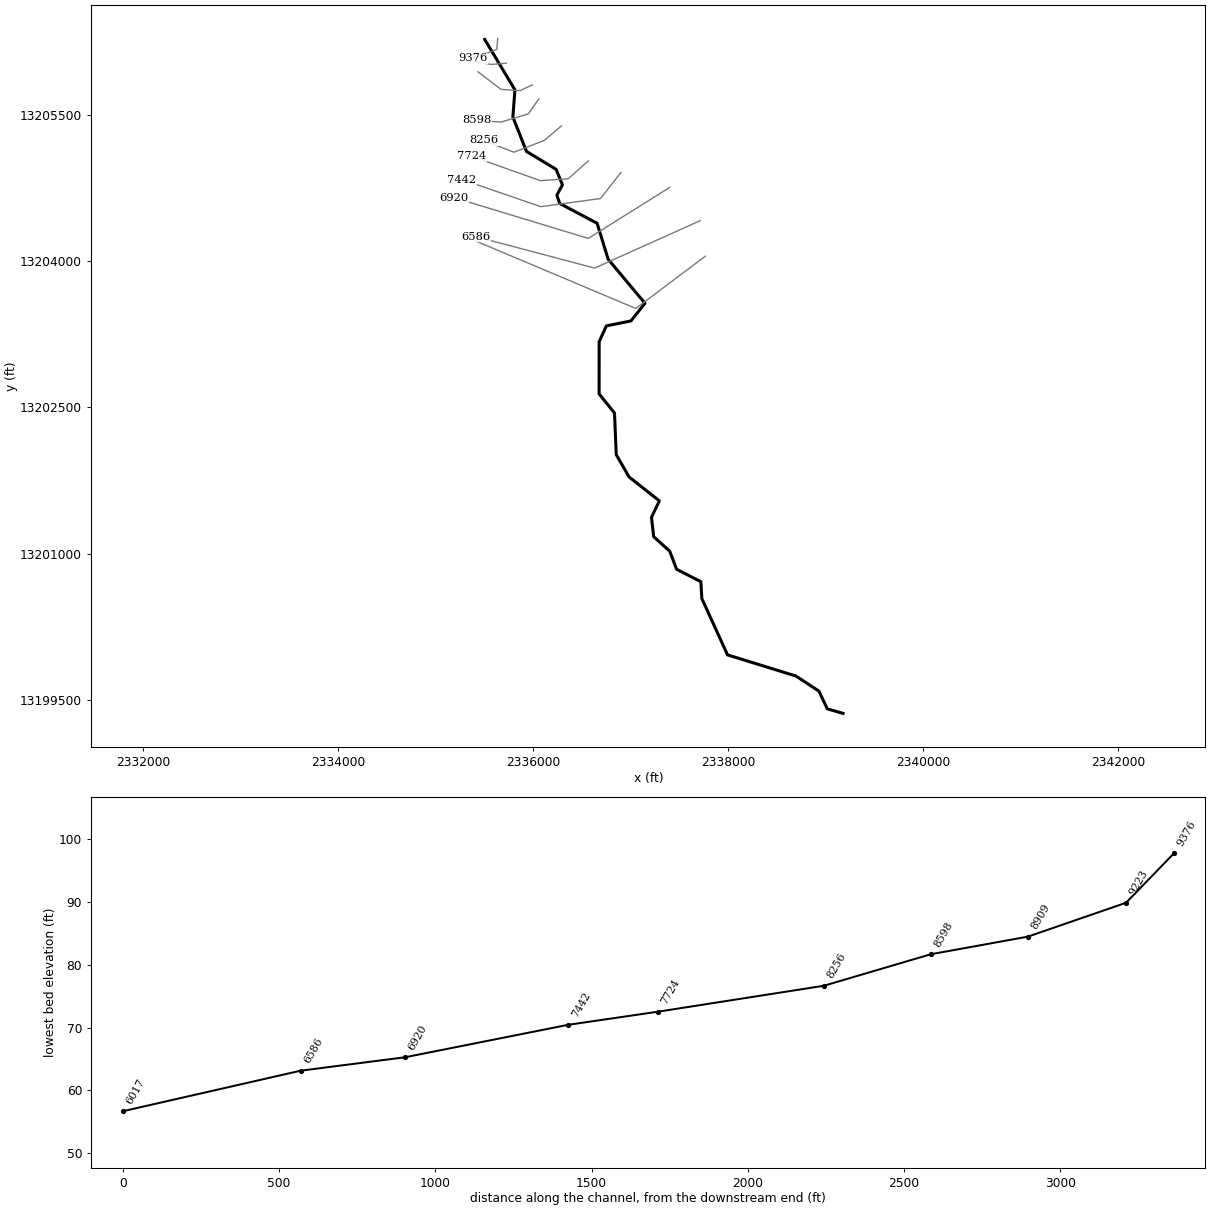
--- NUECES RIVER TRIB 1.prj (project) ---

Proj Title=NUECES RIVER TRIB 1 Base Level Engineering
Current Plan=p01
Default Exp/Contr=0.3,0.1
English Units
Geom File=g01
Flow File=f01
Plan File=p01
Y Axis Title=Elevation
X Axis Title(PF)=Main Channel Distance
X Axis Title(XS)=Station
BEGIN DESCRIPTION:
NUECES RIVER TRIB 1
END DESCRIPTION:
DSS Export Rating Curves= 0
DSS Export Rating Curve Sorted= 0
DSS Export Volume Flow Curves= 0
DXF OffsetX= 0
DXF OffsetY= 0
DXF ScaleX= 1
DXF ScaleY= 10

--- NUECES RIVER TRIB 1.p01 (plan) ---

Plan Title=Multiple Run
Short Identifier=Multiple
Geom File=g01
Flow File=f01
Subcritical Flow
K Sum by GR= 0
Std Step Tol= 0.01
Critical Tol= 0.01
Num of Std Step Trials= 20
Max Error Tol= 0.3
Flow Tol Ratio= 0.001
Split Flow NTrial= 30
Split Flow Tol= 0.02
Split Flow Ratio= 0.02
Log Output Level= 0
Friction Slope Method= 1
Unsteady Friction Slope Method= 2
Unsteady Bridges Friction Slope Method= 1
Parabolic Critical Depth
Global Vel Dist=  1 , 1 , 1
Global Log Level= 0
CheckData=True
Encroach Param= -1, 0, 0, 0
BEGIN DESCRIPTION:
Multiple Run
END DESCRIPTION:

--- NUECES RIVER TRIB 1.f01 (steady flow) ---

Flow Title=Multiple
Number of Profiles=7
Profile Names=10-year,25-year,50-year,1pct_min,100-year,1pct_plu,500-year
River Rch & RM= NUECES RIVER TRI,Reach-1,9376
     487     674     826     739    1000    1352    1471
Boundary for River Rch & Prof#=NUECES RIVER TRI,Reach-1,1
Up Type=0
Dn Type=3
Dn Slope=0.005
Boundary for River Rch & Prof#=NUECES RIVER TRI,Reach-1,2
Up Type=0
Dn Type=3
Dn Slope=0.005
Boundary for River Rch & Prof#=NUECES RIVER TRI,Reach-1,3
Up Type=0
Dn Type=3
Dn Slope=0.005
Boundary for River Rch & Prof#=NUECES RIVER TRI,Reach-1,4
Up Type=0
Dn Type=3
Dn Slope=0.005
Boundary for River Rch & Prof#=NUECES RIVER TRI,Reach-1,5
Up Type=0
Dn Type=3
Dn Slope=0.005
Boundary for River Rch & Prof#=NUECES RIVER TRI,Reach-1,6
Up Type=0
Dn Type=3
Dn Slope=0.005
Boundary for River Rch & Prof#=NUECES RIVER TRI,Reach-1,7
Up Type=0
Dn Type=3
Dn Slope=0.005

--- NUECES RIVER TRIB 1.g01 (geometry) ---

Geom Title=Existing Conditions
Program Version=4.10

River Reach=NUECES RIVER TRI,Reach-1
Reach XY= 30
       2335504.1     13206272.26      2335814.37     13205755.31
      2335793.29     13205476.61      2335932.68     13205123.88
      2336236.67     13204940.01      2336301.76     13204780.61
      2336244.26     13204675.79       2336273.6     13204590.21
      2336657.33     13204386.76      2336770.32     13204017.93
       2337148.1     13203566.38      2337003.84     13203385.39
      2336751.88     13203334.55      2336678.04     13203171.72
      2336677.72     13202636.86       2336835.5     13202440.93
      2336853.31     13202014.29       2336984.7     13201785.52
      2337295.48     13201540.46      2337214.87     13201371.12
       2337237.1     13201173.35      2337401.73     13201023.91
      2337472.04     13200839.02      2337721.11     13200711.11
      2337731.21      13200538.3      2337994.66     13199960.63
      2338696.18     13199743.63      2338932.44     13199588.44
      2339017.56      13199407.4      2339178.98     13199360.77

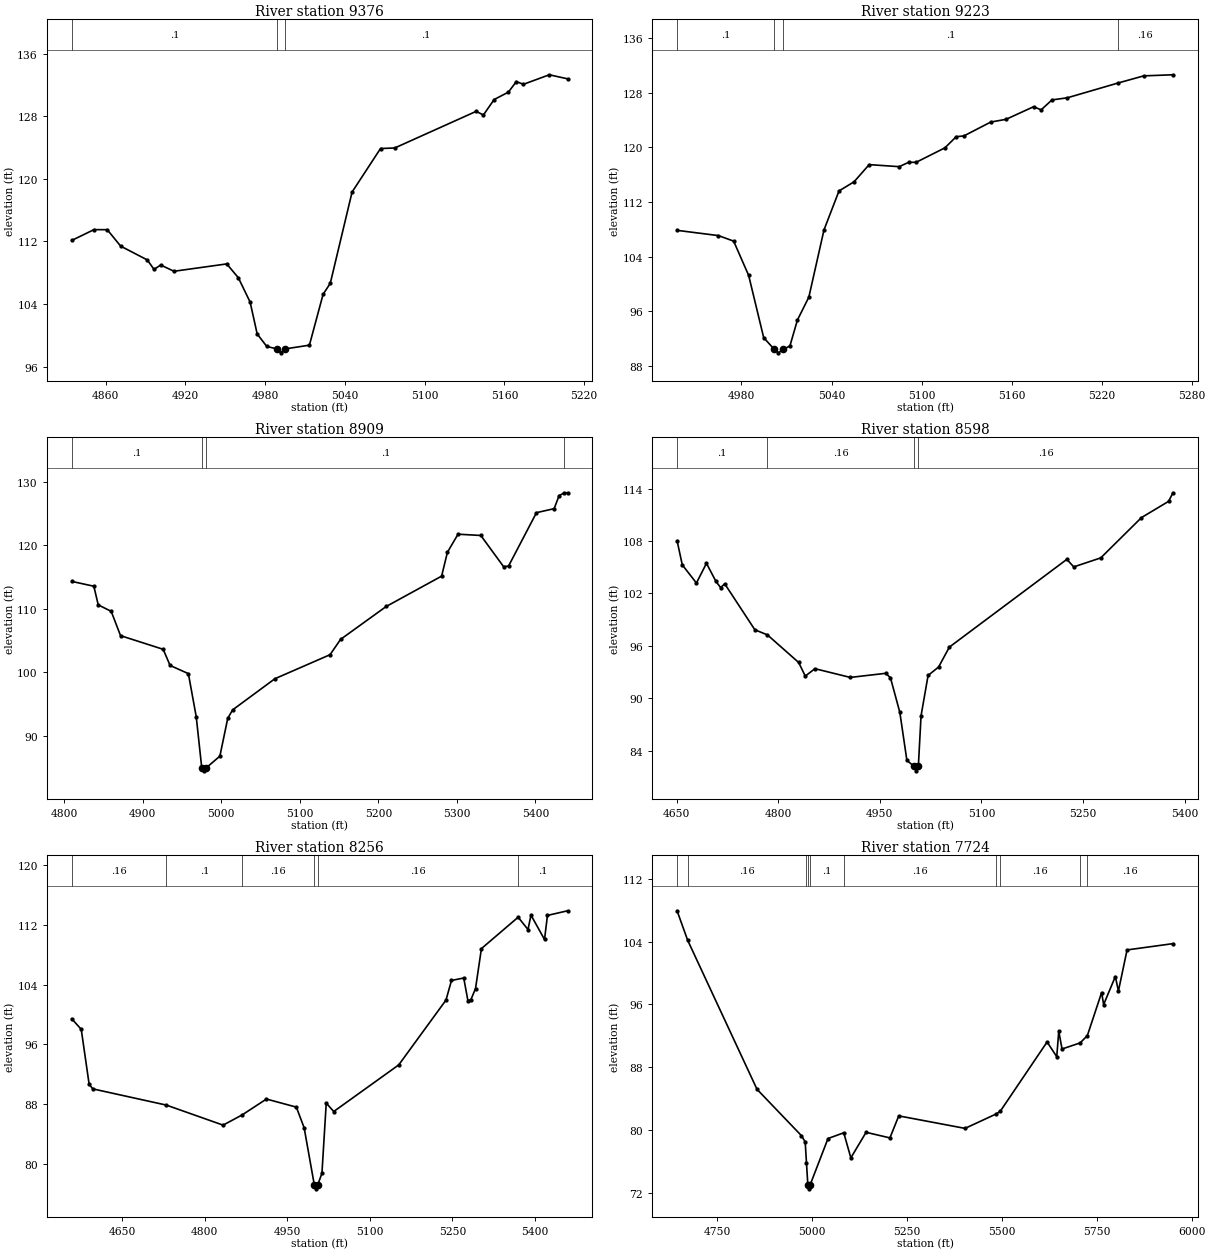
Type RM Length L Ch R = 1 ,9376    ,153,153,153
BEGIN DESCRIPTION:
NUECES RIVER TRIB 1 17.0
END DESCRIPTION:
XS GIS Cut Line= 3
      2335637.29     13206283.51      2335628.92     13206170.49
      2335386.04     13206078.37
#Sta/Elev= 30
  4834.5  112.13  4851.2  113.51  4861.2   113.5  4871.3   111.4  4891.3  109.64
  4896.4  108.43  4901.4  108.99  4911.4  108.19  4951.1  109.13  4959.8  107.37
  4968.7  104.25    4974  100.18  4981.2   98.59  4988.9   98.27  4991.6   97.77
  4994.9   98.27  5013.3   98.75  5023.6  105.25    5029  106.65  5045.4  118.31
  5066.8  123.87  5077.5  123.94  5138.8  128.62  5144.2  128.15  5152.3  130.13
    5163  131.07    5169  132.42  5174.3  132.07  5193.8  133.29  5207.6  132.77
#Mann= 3 ,-1 , 0
  4834.5      .1       0  4988.9     .07       0  4994.9      .1       0
Bank Sta=4988.9,4994.9
XS Rating Curve= 0 ,0
Exp/Cntr=0.3,0.1

Type RM Length L Ch R = 1 ,9223    ,314,314,314
BEGIN DESCRIPTION:
Mapping XS a912587c
END DESCRIPTION:
XS GIS Cut Line= 3
      2335725.26     13206028.12       2335570.3     13206015.56
      2335398.61     13206049.06
#Sta/Elev= 30
  4937.1  107.84  4964.7  107.07  4974.8  106.26  4984.8  101.24  4994.8   92.14
  5001.9   90.41  5004.6   89.91  5007.9   90.41  5012.3   90.93  5017.3   94.72
  5024.9   98.06    5035  107.91    5045  113.61    5055  114.94  5065.1  117.46
  5085.1  117.16  5091.4   117.8  5096.4   117.8  5115.6  119.92  5123.1  121.55
  5128.2  121.66  5146.1  123.69  5156.3  124.09  5174.6  125.93  5179.7  125.48
  5186.9  126.93  5197.1  127.24  5230.7  129.39    5248  130.45  5267.5  130.61
#Mann= 4 ,-1 , 0
  4937.1      .1       0  5001.9     .07       0  5007.9      .1       0
  5230.7     .16       0
Bank Sta=5001.9,5007.9
XS Rating Curve= 0 ,0
Exp/Cntr=0.3,0.1

Type RM Length L Ch R = 1 ,8909    ,311,311,311
BEGIN DESCRIPTION:
Mapping XS 7427d0f1
END DESCRIPTION:
XS GIS Cut Line= 4
       2335993.2     13205806.17      2335867.61     13205747.56
      2335670.79     13205760.12      2335436.27     13205940.21
#Sta/Elev= 30
  4809.5  114.33  4837.6  113.57  4843.2  110.63  4859.7  109.62  4871.6  105.79
  4925.9  103.64  4934.7   101.1    4958   99.81    4968   93.03    4975   85.01
  4977.8   84.51    4981   85.01  4998.1   86.82  5008.1   92.76  5014.3    94.1
  5068.2   99.01  5138.4  102.79  5151.8   105.2  5209.9  110.38  5280.5  115.16
  5287.9  118.92  5301.4  121.76  5330.4  121.56  5359.4  116.65  5365.7  116.74
  5401.3  125.15  5423.8  125.78  5430.1  127.83  5436.8  128.27    5441  128.28
#Mann= 4 ,-1 , 0
  4809.5      .1       0    4975     .07       0    4981      .1       0
  5436.8     .16       0
Bank Sta=4975,4981
XS Rating Curve= 0 ,0
Exp/Cntr=0.3,0.1

Type RM Length L Ch R = 1 ,8598    ,342,342,342
BEGIN DESCRIPTION:
Mapping XS 20c87124
END DESCRIPTION:
XS GIS Cut Line= 4
       2336060.2     13205663.77      2335951.35     13205508.87
      2335674.98     13205425.12      2335421.33     13205441.76
#Sta/Elev= 30
  4650.6  108.04  4658.3  105.27  4679.2  103.19    4694  105.45  4707.9  103.39
  4714.9  102.67    4721   103.1  4765.5   97.84    4784   97.26  4830.2    94.1
  4839.9   92.54  4854.2   93.39  4906.4   92.39  4958.7   92.86  4965.7   92.36
  4979.6   88.38    4990   82.89  5000.9    82.2  5003.6    81.7  5006.9    82.2
  5010.9      88  5021.3   92.62  5036.8   93.58  5052.7   95.86  5226.2   105.9
  5236.4  105.04  5276.3  106.07  5336.4  110.68  5376.5  112.54  5382.9  113.52
#Mann= 4 ,-1 , 0
  4650.6      .1       0    4784     .16       0  5000.9     .07       0
  5006.9     .16       0
Bank Sta=5000.9,5006.9
XS Rating Curve= 0 ,0
Exp/Cntr=0.3,0.1

Type RM Length L Ch R = 1 ,8256    ,532,532,532
BEGIN DESCRIPTION:
NUECES RIVER TRIB 1 16.0
END DESCRIPTION:
XS GIS Cut Line= 4
      2336292.05      13205386.2      2336114.67     13205236.69
      2335804.79     13205115.25      2335491.69     13205236.32
#Sta/Elev= 30
  4558.7   99.42  4575.9   98.01  4590.2   90.68  4596.8   90.05  4730.5   87.88
  4833.5    85.2  4868.4   86.58  4912.2   88.69  4966.5   87.61  4980.7   84.84
  4999.2   77.18    5002   76.68  5005.2   77.18    5013   78.76  5020.8   88.15
  5034.4   87.02  5152.5   93.26  5238.3  101.93  5248.2  104.55  5270.5  104.88
  5278.1  101.84  5283.5  101.98  5291.9  103.47  5302.6  108.81  5369.3  113.01
  5387.2  111.36  5392.6  113.29  5417.2  110.03  5422.5  113.25  5459.2  113.87
#Mann= 6 ,-1 , 0
  4558.7     .16       0  4730.5      .1       0  4868.4     .16       0
  4999.2     .07       0  5005.2     .16       0  5369.3      .1       0
Bank Sta=4999.2,5005.2
XS Rating Curve= 0 ,0
Exp/Cntr=0.3,0.1

Type RM Length L Ch R = 1 ,7724    ,286,286,286
BEGIN DESCRIPTION:
NUECES RIVER TRIB 1 15.0
END DESCRIPTION:
XS GIS Cut Line= 4
      2336565.49     13205025.95      2336361.52     13204843.69
      2336075.07     13204824.15      2335372.38     13205073.57
#Sta/Elev= 30
  4644.5  107.91  4672.3  104.17  4855.1    85.2    4972   79.31    4982   78.51
  4985.4   75.85    4989   73.04  4991.8   72.54    4995   73.04  5042.1   78.94
  5083.6   79.67  5102.3   76.48  5142.4   79.73  5205.2   79.02  5228.5   81.82
  5403.1   80.23  5484.9   82.06  5495.8    82.4  5619.2   91.22  5644.7   89.35
    5650   92.59  5658.6   90.33  5706.3    91.1  5725.3   92.03  5762.9   97.51
  5768.2   95.98    5799   99.54  5807.2   97.71  5829.9  102.93  5950.8  103.73
#Mann= 10 ,-1 , 0
  4644.5      .1       0  4672.3     .16       0  4985.4      .1       0
    4989     .07       0    4995      .1       0  5083.6     .16       0
  5484.9      .1       0  5495.8     .16       0  5706.3      .1       0
  5725.3     .16       0
Bank Sta=4989,4995
XS Rating Curve= 0 ,0
Exp/Cntr=0.3,0.1

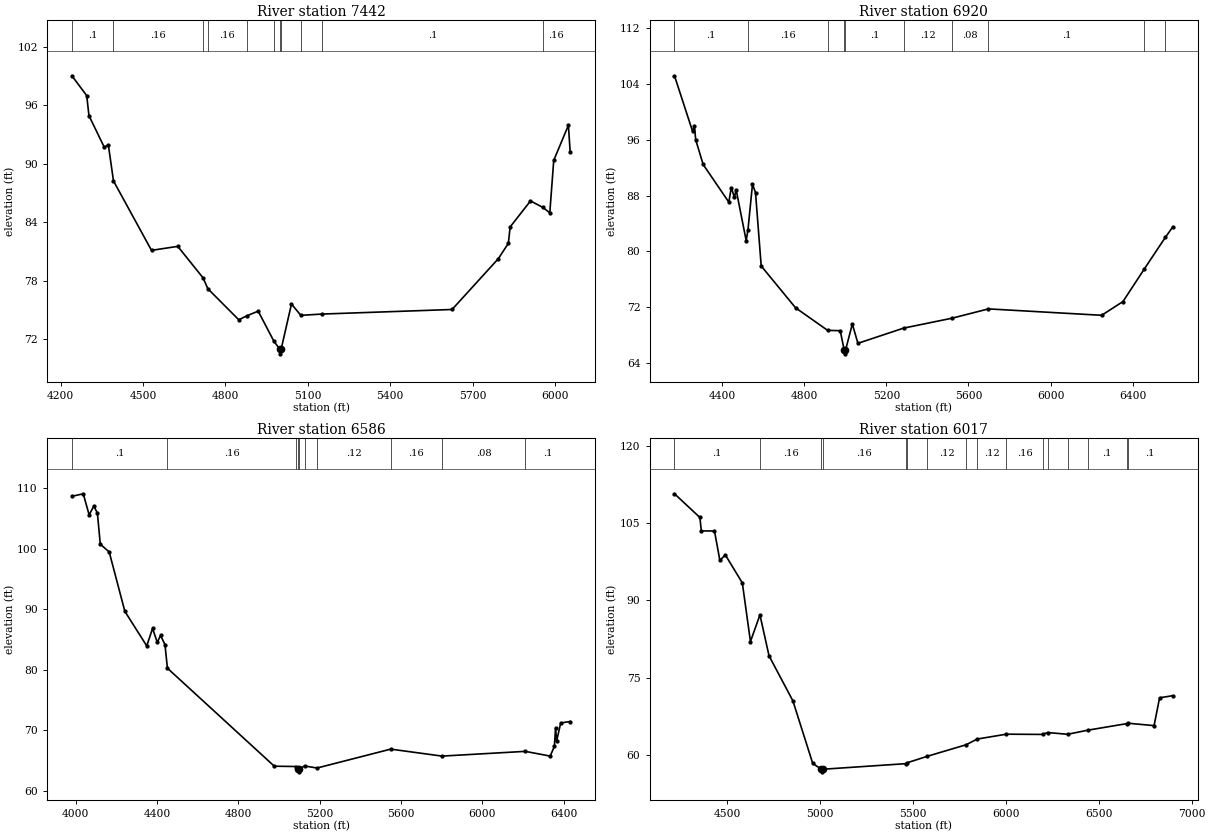
Type RM Length L Ch R = 1 ,7442    ,522,522,522
BEGIN DESCRIPTION:
Mapping XS 8feed51e
END DESCRIPTION:
XS GIS Cut Line= 4
      2336902.47     13204908.89      2336691.56     13204640.69
      2336079.58     13204557.35      2335271.21     13204835.47
#Sta/Elev= 30
    4241   99.05    4295   97.01  4303.1   94.95  4359.1   91.69  4373.6   91.96
  4392.4   88.24  4530.8    81.1  4626.4   81.51  4718.5   78.27    4736   77.15
  4848.5   73.96  4877.1   74.36  4919.1   74.85  4975.7   71.79  4996.9   70.96
  4999.6   70.46  5002.9   70.96  5040.2   75.58  5074.4   74.42  5152.1   74.55
  5624.8   75.02  5793.2   80.24  5829.7   81.82  5836.3   83.51  5910.3   86.18
  5954.5   85.53  5980.6   84.96  5994.9   90.35  6048.3   93.96  6054.7   91.24
#Mann= 11 ,-1 , 0
    4241      .1       0  4392.4     .16       0  4718.5      .1       0
    4736     .16       0  4877.1     .12       0  4975.7     .16       0
  4996.9     .07       0  5002.9     .16       0  5074.4     .08       0
  5152.1      .1       0  5954.5     .16       0
Bank Sta=4996.9,5002.9
XS Rating Curve= 0 ,0
Exp/Cntr=0.3,0.1

Type RM Length L Ch R = 1 ,6920    ,334,334,334
BEGIN DESCRIPTION:
Mapping XS ba2f2337
END DESCRIPTION:
XS GIS Cut Line= 3
      2337402.48     13204755.26      2336566.56     13204231.83
      2335186.32     13204651.11
#Sta/Elev= 30
  4166.9  105.19  4255.1   97.22  4264.3   98.01  4270.2   96.02  4306.7   92.46
  4431.7   87.06  4443.9   89.15  4458.8   87.76  4467.5   88.83  4516.5   81.53
  4525.2   83.11  4547.2   89.64  4561.9   88.42  4589.6    77.9    4757    71.9
  4913.3   68.66  4974.8   68.61  4994.5   65.79  4997.2   65.29  5000.5   65.79
  5033.8   69.57  5061.1    66.8  5283.8   68.98  5519.3    70.4  5697.4   71.74
  6249.2   70.82    6353   72.79  6456.5   77.44    6560   82.02  6595.7    83.5
#Mann= 10 ,-1 , 0
  4166.9      .1       0  4525.2     .16       0  4913.3      .1       0
  4994.5     .07       0  5000.5      .1       0  5283.8     .12       0
  5519.3     .08       0  5697.4      .1       0  6456.5     .08       0
    6560      .1       0
Bank Sta=4994.5,5000.5
XS Rating Curve= 0 ,0
Exp/Cntr=0.3,0.1

Type RM Length L Ch R = 1 ,6586    ,569,569,569
BEGIN DESCRIPTION:
Mapping XS a5c8dde7
END DESCRIPTION:
XS GIS Cut Line= 3
        2337715.     13204414.13      2336631.66     13203927.14
      2335412.88     13204250.07
#Sta/Elev= 30
  3982.2  108.64    4038  109.06  4066.9  105.58  4089.8  107.02  4107.5  105.89
  4121.7  100.74  4165.6   99.45  4242.4   89.65  4350.1   83.94  4378.7   86.83
  4401.9   84.52  4417.8   85.67  4439.7   84.15  4451.6   80.26  4976.9   64.08
  5081.4   64.03  5094.5   63.65  5097.3   63.15  5100.5   63.65  5125.4   64.12
    5187   63.78    5549    66.9  5800.9   65.75  6210.2   66.53  6332.7   65.75
  6353.4   67.36  6359.1   70.43  6364.3   68.24  6384.4   71.22  6430.8   71.46
#Mann= 10 ,-1 , 0
  3982.2      .1       0  4451.6     .16       0  5081.4     .12       0
  5094.5     .07       0  5100.5     .12       0  5125.4     .16       0
    5187     .12       0    5549     .16       0  5800.9     .08       0
  6210.2      .1       0
Bank Sta=5094.5,5100.5
XS Rating Curve= 0 ,0
Exp/Cntr=0.3,0.1

Type RM Length L Ch R = 1 ,6017    ,0,0,0
BEGIN DESCRIPTION:
NUECES RIVER TRIB 1 1.0
END DESCRIPTION:
XS GIS Cut Line= 3
      2337767.04     13204049.51      2337053.53     13203513.08
      2335405.14     13204208.38
#Sta/Elev= 30
  4216.5  110.66  4353.3  106.06    4361  103.45  4431.8  103.44  4460.9   97.71
  4490.1    98.8  4581.7   93.36  4625.4   81.98  4676.5   87.15  4725.4   79.21
  4853.7   70.48  4960.7   58.31  5007.7   57.19  5010.5   56.69  5013.7   57.19
    5463   58.28  5469.6   58.46  5577.4   59.71  5785.5   61.94  5846.7   63.06
  6002.9      64  6198.4   63.95  6224.5   64.32  6332.3   63.98  6440.2   64.77
  6651.3   66.05  6655.8   66.13  6797.7   65.66  6827.4   71.06  6898.2   71.47
#Mann= 16 ,-1 , 0
  4216.5      .1       0  4676.5     .16       0  5007.7     .07       0
  5013.7     .16       0    5463     .12       0  5469.6     .16       0
  5577.4     .12       0  5785.5      .1       0  5846.7     .12       0
  6002.9     .16       0  6198.4     .08       0  6224.5     .16       0
  6332.3     .08       0  6440.2      .1       0  6651.3     .08       0
  6655.8      .1       0
Bank Sta=5007.7,5013.7
XS Rating Curve= 0 ,0
Exp/Cntr=0.3,0.1

Chan Stop Cuts=-1
Use User Specified Reach Order=0
Composite Channel Slope=5