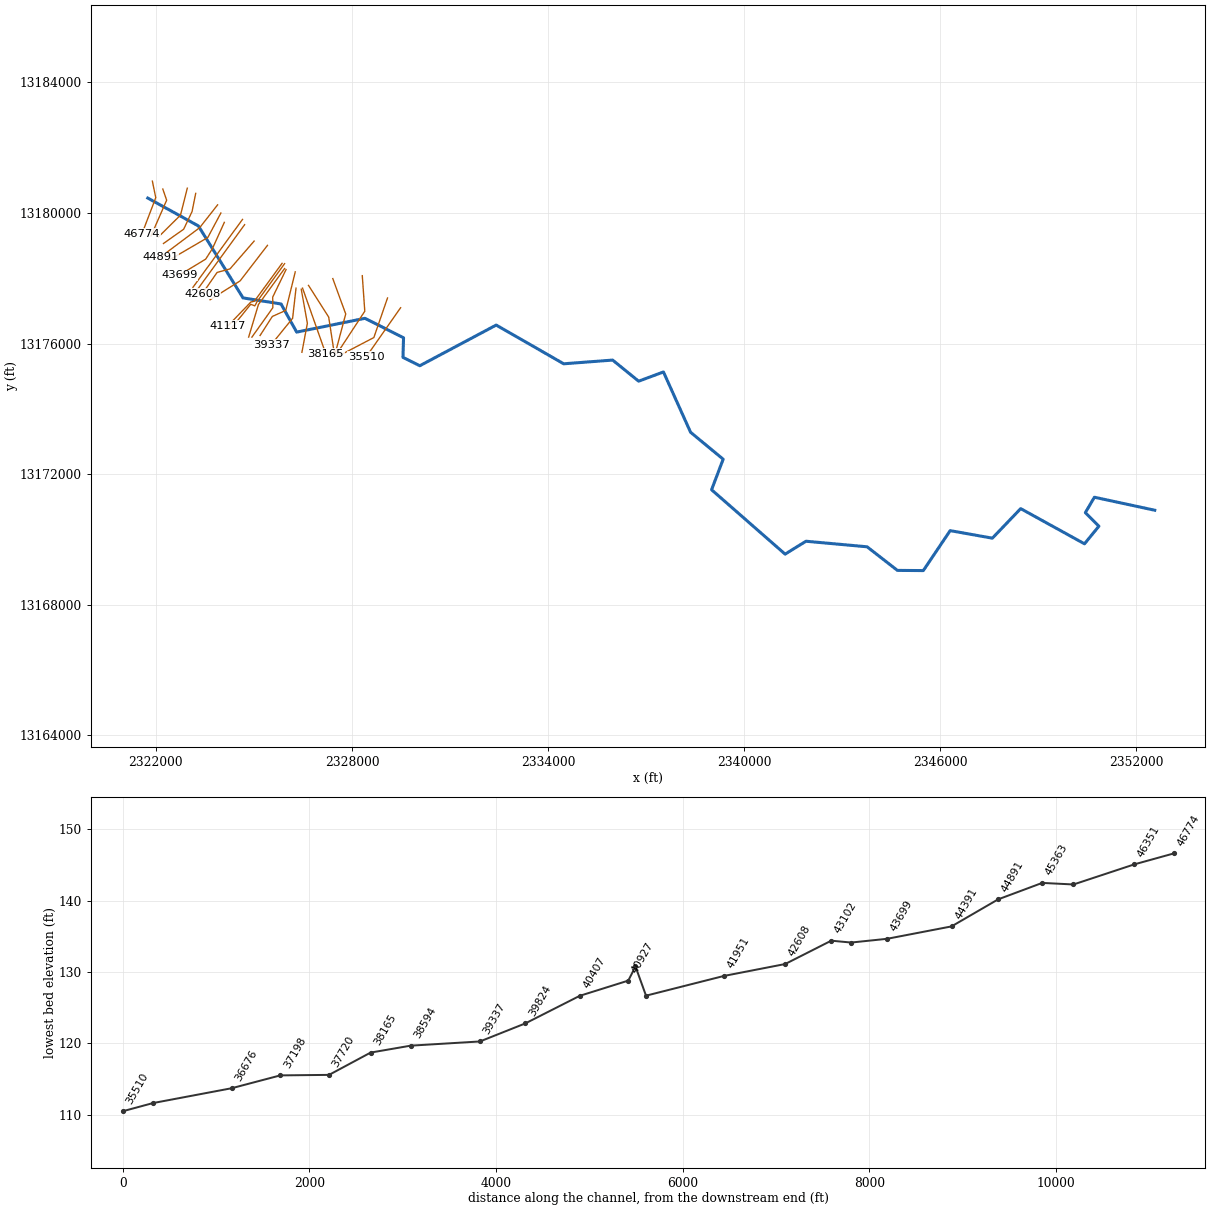
--- SANDY HOLLOW CREEK.prj (project) ---

Proj Title=SANDY HOLLOW CREEK Base Level Engineering
Current Plan=p01
Default Exp/Contr=0.3,0.1
English Units
Geom File=g01
Flow File=f01
Plan File=p01
Y Axis Title=Elevation
X Axis Title(PF)=Main Channel Distance
X Axis Title(XS)=Station
BEGIN DESCRIPTION:
SANDY HOLLOW CREEK
END DESCRIPTION:
DSS Export Rating Curves= 0
DSS Export Rating Curve Sorted= 0
DSS Export Volume Flow Curves= 0
DXF OffsetX= 0
DXF OffsetY= 0
DXF ScaleX= 1
DXF ScaleY= 10

--- SANDY HOLLOW CREEK.p01 (plan) ---

Plan Title=Multiple Run
Short Identifier=Multiple
Geom File=g01
Flow File=f01
Subcritical Flow
K Sum by GR= 0
Std Step Tol= 0.01
Critical Tol= 0.01
Num of Std Step Trials= 20
Max Error Tol= 0.3
Flow Tol Ratio= 0.001
Split Flow NTrial= 30
Split Flow Tol= 0.02
Split Flow Ratio= 0.02
Log Output Level= 0
Friction Slope Method= 1
Unsteady Friction Slope Method= 2
Unsteady Bridges Friction Slope Method= 1
Parabolic Critical Depth
Global Vel Dist=  1 , 1 , 1
Global Log Level= 0
CheckData=True
Encroach Param= -1, 0, 0, 0
BEGIN DESCRIPTION:
Multiple Run
END DESCRIPTION:

--- SANDY HOLLOW CREEK.f01 (steady flow) ---

Flow Title=Multiple
Program Version=4.10
Number of Profiles= 7
Profile Names=10-year,25-year,50-year,1pct_min,100-year,1pct_plu,500-year
River Rch & RM=SANDY HOLLOW CRE,Reach-1         ,46774
     267     361     436     388     524     709     763
River Rch & RM=SANDY HOLLOW CRE,Reach-1         ,45698
     329     450     549     491     664     898     981
River Rch & RM=SANDY HOLLOW CRE,Reach-1         ,43102
     401     553     679     609     824    1115    1228
River Rch & RM=SANDY HOLLOW CRE,Reach-1         ,38594
     473     659     812     733     992    1341    1493
River Rch & RM=SANDY HOLLOW CRE,Reach-1         ,34905
     534     747     924     837    1132    1531    1716
River Rch & RM=SANDY HOLLOW CRE,Reach-1         ,32967
     645     911    1135    1033    1397    1890    2141
River Rch & RM=SANDY HOLLOW CRE,Reach-1         ,28260
     744    1055    1318    1203    1627    2200    2505
River Rch & RM=SANDY HOLLOW CRE,Reach-1         ,24391
     761    1080    1349    1231    1665    2252    2563
River Rch & RM=SANDY HOLLOW CRE,Reach-1         ,19193
     898    1286    1615    1482    2004    2710    3118
River Rch & RM=SANDY HOLLOW CRE,Reach-1         ,16625
     898    1284    1611    1477    1997    2700    3101
River Rch & RM=SANDY HOLLOW CRE,Reach-1         ,14679
    1138    1643    2075    1914    2588    3500    4068
River Rch & RM=SANDY HOLLOW CRE,Reach-1         ,14123
    1138    1643    2075    1914    2588    3500    4068
River Rch & RM=SANDY HOLLOW CRE,Reach-1         ,13377
    1189    1716    2168    1998    2703    3655    4245
River Rch & RM=SANDY HOLLOW CRE,Reach-1         ,5641
    1266    1833    2319    2142    2897    3918    4566
Boundary for River Rch & Prof#=SANDY HOLLOW CRE,Reach-1         , 1
Up Type= 0
Dn Type= 3
Dn Slope=0.0023
Boundary for River Rch & Prof#=SANDY HOLLOW CRE,Reach-1         , 2
Up Type= 0
Dn Type= 3
Dn Slope=0.0023
Boundary for River Rch & Prof#=SANDY HOLLOW CRE,Reach-1         , 3
Up Type= 0
Dn Type= 3
Dn Slope=0.0023
Boundary for River Rch & Prof#=SANDY HOLLOW CRE,Reach-1         , 4
Up Type= 0
Dn Type= 3
Dn Slope=0.0023
Boundary for River Rch & Prof#=SANDY HOLLOW CRE,Reach-1         , 5
Up Type= 0
Dn Type= 3
Dn Slope=0.0023
Boundary for River Rch & Prof#=SANDY HOLLOW CRE,Reach-1         , 6
Up Type= 0
Dn Type= 3
Dn Slope=0.0023
Boundary for River Rch & Prof#=SANDY HOLLOW CRE,Reach-1         , 7
Up Type= 0
Dn Type= 3
Dn Slope=0.0023
DSS Import GetInterval= 0
DSS Import GetPeak= 0
DSS Import FillOption= 0

--- SANDY HOLLOW CREEK.g01 (geometry) ---

Geom Title=Existing Conditions
Program Version=4.10

River Reach=SANDY HOLLOW CRE,Reach-1
Reach XY= 30
      2321750.42     13180455.44      2323300.47     13179601.54
      2324665.51     13177398.07      2325830.54     13177211.42
      2326307.17     13176350.53      2328396.47     13176772.76
      2329577.72     13176176.85      2329560.14     13175577.09
      2330075.51     13175320.76      2332413.22     13176566.16
      2334479.06     13175380.08       2335976.5     13175493.82
      2336772.34     13174847.48      2337531.36     13175130.57
      2338361.22     13173283.34      2339358.38     13172458.34
      2339004.32      13171522.6       2341254.2     13169551.11
      2341892.87     13169946.28      2343762.45     13169776.07
      2344690.91     13169053.18      2345482.63     13169047.21
      2346305.23     13170270.88      2347596.43     13170039.82
       2348462.8     13170944.79      2350415.68     13169867.21
      2350856.77     13170406.77      2350441.74     13170821.99
      2350719.02     13171293.71      2352566.15     13170895.21

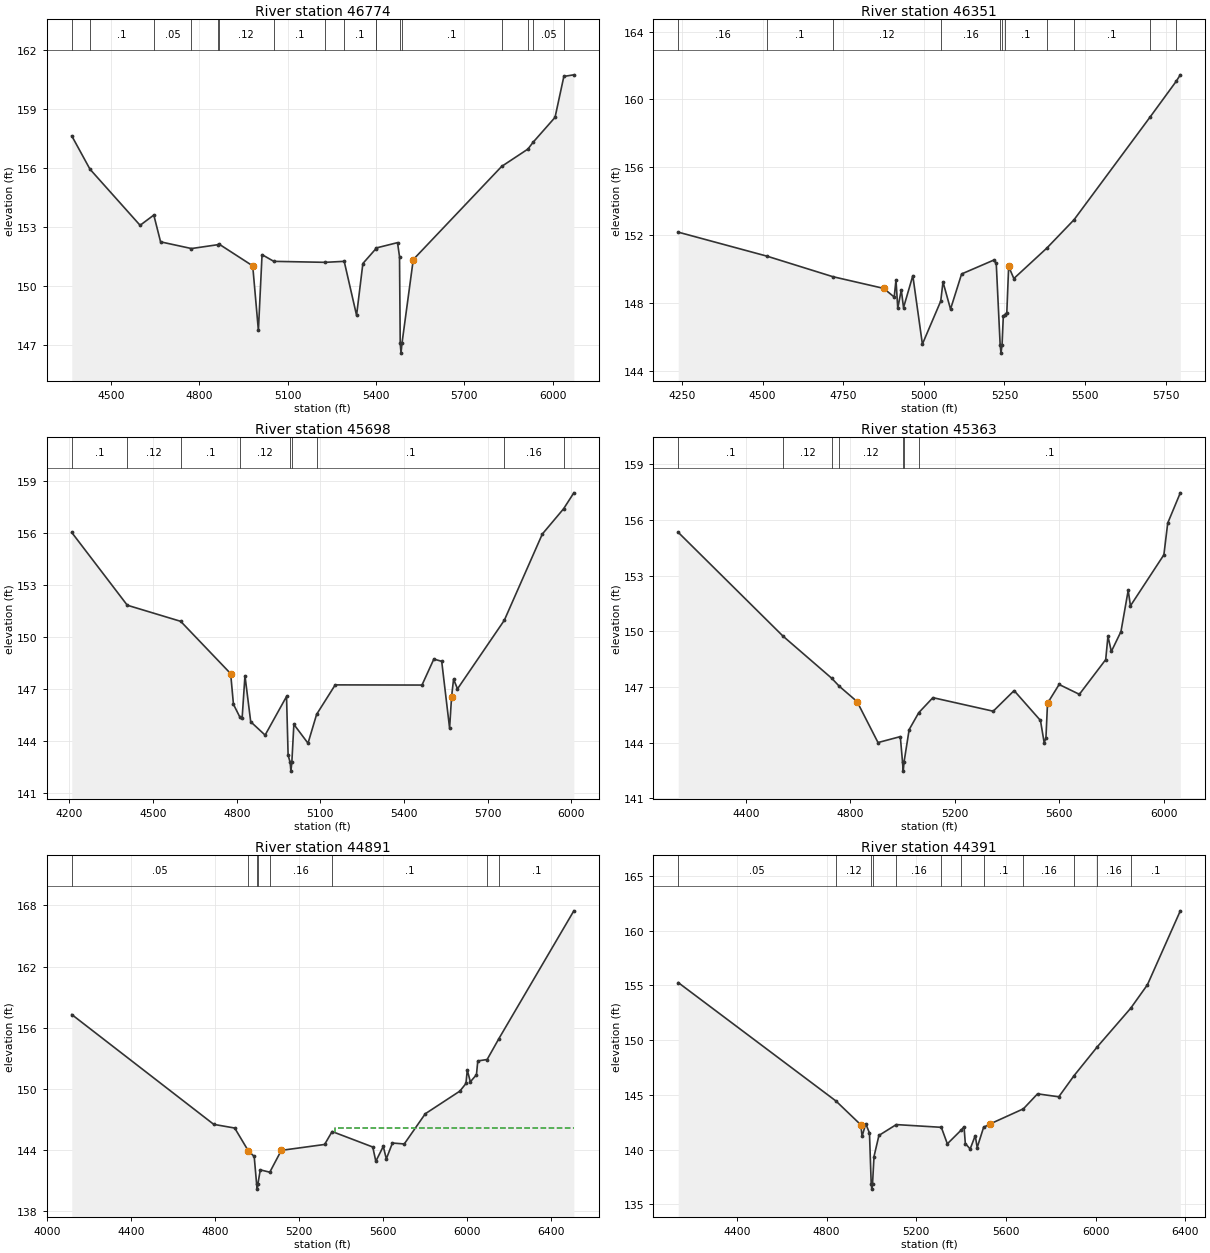
Type RM Length L Ch R = 1 ,46774   ,423,423,423
BEGIN DESCRIPTION:
SANDY HOLLOW CREEK 78.0
END DESCRIPTION:
XS GIS Cut Line= 3
      2321891.35     13180974.24      2321995.52     13180467.26
       2321572.3     13179357.17
#Sta/Elev= 30
  4366.1  157.63  4427.9  155.94  4598.2  153.09  4644.8  153.61  4667.8  152.25
  4772.7  151.91  4864.3  152.11  4864.9  152.15  4980.8  151.03  5000.1  147.75
  5012.5   151.6  5052.4  151.26  5226.7  151.21  5291.6  151.26  5333.6  148.52
    5355  151.15  5398.6  151.89  5400.6  151.94  5472.7  152.21  5479.5   151.5
  5481.9   147.1  5484.6   146.6  5487.9   147.1  5526.2  151.35  5826.5  156.08
  5915.6  156.96  5933.5  157.31  6007.8  158.57  6037.8  160.65  6071.7  160.73
#Mann= 17 ,-1 , 0
  4366.1     .05       0  4427.9      .1       0  4644.8     .05       0
  4772.7     .12       0  4864.3     .16       0  4864.9     .12       0
  5052.4      .1       0  5226.7     .16       0  5291.6      .1       0
  5398.6     .16       0  5400.6      .1       0  5481.9     .07       0
  5487.9      .1       0  5826.5     .05       0  5915.6      .1       0
  5933.5     .05       0  6037.8      .1       0
Bank Sta=4980.8,5526.2
XS Rating Curve= 0 ,0
Exp/Cntr=0.3,0.1

Type RM Length L Ch R = 1 ,46351   ,653,653,653
BEGIN DESCRIPTION:
SANDY HOLLOW CREEK 77.0
END DESCRIPTION:
XS GIS Cut Line= 3
       2322210.8     13180731.16      2322328.86     13180390.87
      2321849.68     13179293.62
#Sta/Elev= 30
  4238.1  152.19  4512.9  150.78  4717.6  149.57  4875.5  148.88  4908.1  148.37
  4913.6  149.38  4919.1  147.71    4930  148.79    4937  147.75  4965.8  149.63
  4995.5   145.6  5052.4  148.13  5059.4  149.26  5082.8  147.66  5117.2  149.73
  5216.2  150.54  5224.6  150.36  5236.7  145.57  5239.4  145.07  5242.7  145.57
  5246.5  147.24  5251.5  147.34  5257.4  147.46  5263.1  150.17  5279.2  149.46
  5381.4  151.25  5465.9  152.92  5702.8  158.99  5782.9  161.07  5795.6  161.45
#Mann= 11 ,-1 , 0
  4238.1     .16       0  4512.9      .1       0  4717.6     .12       0
  5052.4     .16       0  5236.7     .07       0  5242.7     .16       0
  5251.5      .1       0  5381.4     .16       0  5465.9      .1       0
  5702.8     .05       0  5782.9      .1       0
Bank Sta=4875.5,5263.1
XS Rating Curve= 0 ,0
Exp/Cntr=0.3,0.1

Type RM Length L Ch R = 1 ,45698   ,335,335,335
BEGIN DESCRIPTION:
SANDY HOLLOW CREEK 76.0
END DESCRIPTION:
XS GIS Cut Line= 3
      2322960.79     13180758.88      2322752.47     13179932.54
      2322078.88     13179265.89
#Sta/Elev= 30
  4208.7  156.03  4407.7  151.83  4599.1   150.9  4778.3  147.88  4788.3  146.11
  4811.6  145.36  4819.4   145.3  4829.6  147.76  4850.2   145.1  4901.8  144.33
  4978.6  146.56  4984.3  143.17  4991.6  142.75  4994.3  142.25  4997.6  142.75
  5004.9  144.95  5055.6  143.86  5086.5  145.53  5153.1  147.23  5464.2  147.22
  5506.7  148.72  5534.9  148.59  5563.2  144.73  5570.3  146.55  5577.4  147.56
  5591.5     147  5759.3  150.96  5895.6  155.94  5971.9   157.4  6008.6  158.32
#Mann= 9 ,-1 , 0
  4208.7      .1       0  4407.7     .12       0  4599.1      .1       0
  4811.6     .12       0  4991.6     .07       0  4997.6     .12       0
  5086.5      .1       0  5759.3     .16       0  5971.9      .1       0
Bank Sta=4778.3,5570.3
XS Rating Curve= 0 ,0
Exp/Cntr=0.3,0.1

Type RM Length L Ch R = 1 ,45363   ,472,472,472
BEGIN DESCRIPTION:
SANDY HOLLOW CREEK 75.0
END DESCRIPTION:
XS GIS Cut Line= 4
      2323217.74     13180599.19      2323106.63     13180043.65
      2322849.69     13179501.98       2322232.2     13179064.89
#Sta/Elev= 30
  4140.7  155.34  4542.4  149.74  4728.9  147.47    4757  147.05  4825.4  146.22
  4905.7  144.01  4991.1  144.33  4999.5  142.97  5002.3  142.47  5005.5  142.97
    5025  144.71  5061.7  145.62  5115.9  146.43  5346.8   145.7  5426.9  146.81
  5527.8   145.2    5542     144  5548.7  144.25  5554.8  146.13  5599.2  147.14
  5676.7  146.61  5777.6  148.48  5786.2  149.74  5799.2  148.92    5836  149.99
  5863.7  152.21  5872.4  151.38  6000.4  154.13  6015.1  155.84  6063.3  157.47
#Mann= 7 ,-1 , 0
  4140.7      .1       0  4542.4     .12       0  4728.9      .1       0
    4757     .12       0  4999.5     .07       0  5005.5     .12       0
  5061.7      .1       0
Bank Sta=4825.4,5554.8
XS Rating Curve= 0 ,0
Exp/Cntr=0.3,0.1

Type RM Length L Ch R = 1 ,44891   ,500,500,500
BEGIN DESCRIPTION:
SANDY HOLLOW CREEK 74.0
END DESCRIPTION:
XS GIS Cut Line= 3
       2323887.7     13180246.83      2323337.72     13179546.85
      2322137.71     13178646.85
#Sta/Elev= 30
  4116.5  157.29  4792.5  146.52  4892.2  146.16  4955.9  143.96  4956.1  143.95
    4985  143.37  4996.5  140.67  4999.2  140.17  5002.5  140.67    5014  142.06
  5059.2  141.83    5114  143.97  5320.2  144.55  5355.9  145.82  5549.4   144.3
    5564   142.9  5599.4  144.36    5614  143.14  5643.1  144.69  5699.4   144.6
  5799.4  147.56    5964  149.78  5993.1  150.53  5999.4  151.85    6014  150.69
  6043.1  151.39  6049.4  152.74  6093.9  152.88  6150.2  154.94  6506.7  167.46
#Mann= 8 ,-1 , 0
  4116.5     .05       0  4955.9     .12       0  4996.5     .07       0
  5002.5     .12       0  5059.2     .16       0  5355.9      .1       0
  6093.9     .16       0  6150.2      .1       0
#XS Ineff= 2 , 0
                         5368.75          146.12
Permanent Ineff=
       F       F
Bank Sta=4956.1,5114
XS Rating Curve= 0 ,0
Exp/Cntr=0.3,0.1

Type RM Length L Ch R = 1 ,44391   ,692,692,692
BEGIN DESCRIPTION:
SANDY HOLLOW CREEK 73.0
END DESCRIPTION:
XS GIS Cut Line= 3
      2323987.72     13179996.85      2323587.72     13179246.85
      2322387.75     13178546.87
#Sta/Elev= 30
  4138.1  155.26  4841.3  144.44  4952.3  142.26    4958   141.2  4974.3  142.36
    4991  141.51  4998.7  136.88  5001.5  136.38  5004.7  136.88  5011.2  139.36
  5033.2  141.29  5110.6  142.28  5311.5  142.03  5338.3  140.52  5399.1  141.76
  5412.7  142.08  5418.5  140.55    5440  140.05  5462.7  141.27  5471.4  140.18
    5500  142.03  5530.1  142.35  5677.4  143.72  5740.6  145.09  5835.3  144.82
  5903.3  146.75  6007.1  149.39  6156.2  152.92  6230.6  155.06  6377.3  161.82
#Mann= 12 ,-1 , 0
  4138.1     .05       0  4841.3     .12       0  4998.7     .07       0
  5004.7     .12       0  5110.6     .16       0  5311.5      .1       0
  5399.1     .16       0    5500      .1       0  5677.4     .16       0
  5903.3      .1       0  6007.1     .16       0  6156.2      .1       0
Bank Sta=4952.3,5530.1
XS Rating Curve= 0 ,0
Exp/Cntr=0.3,0.1

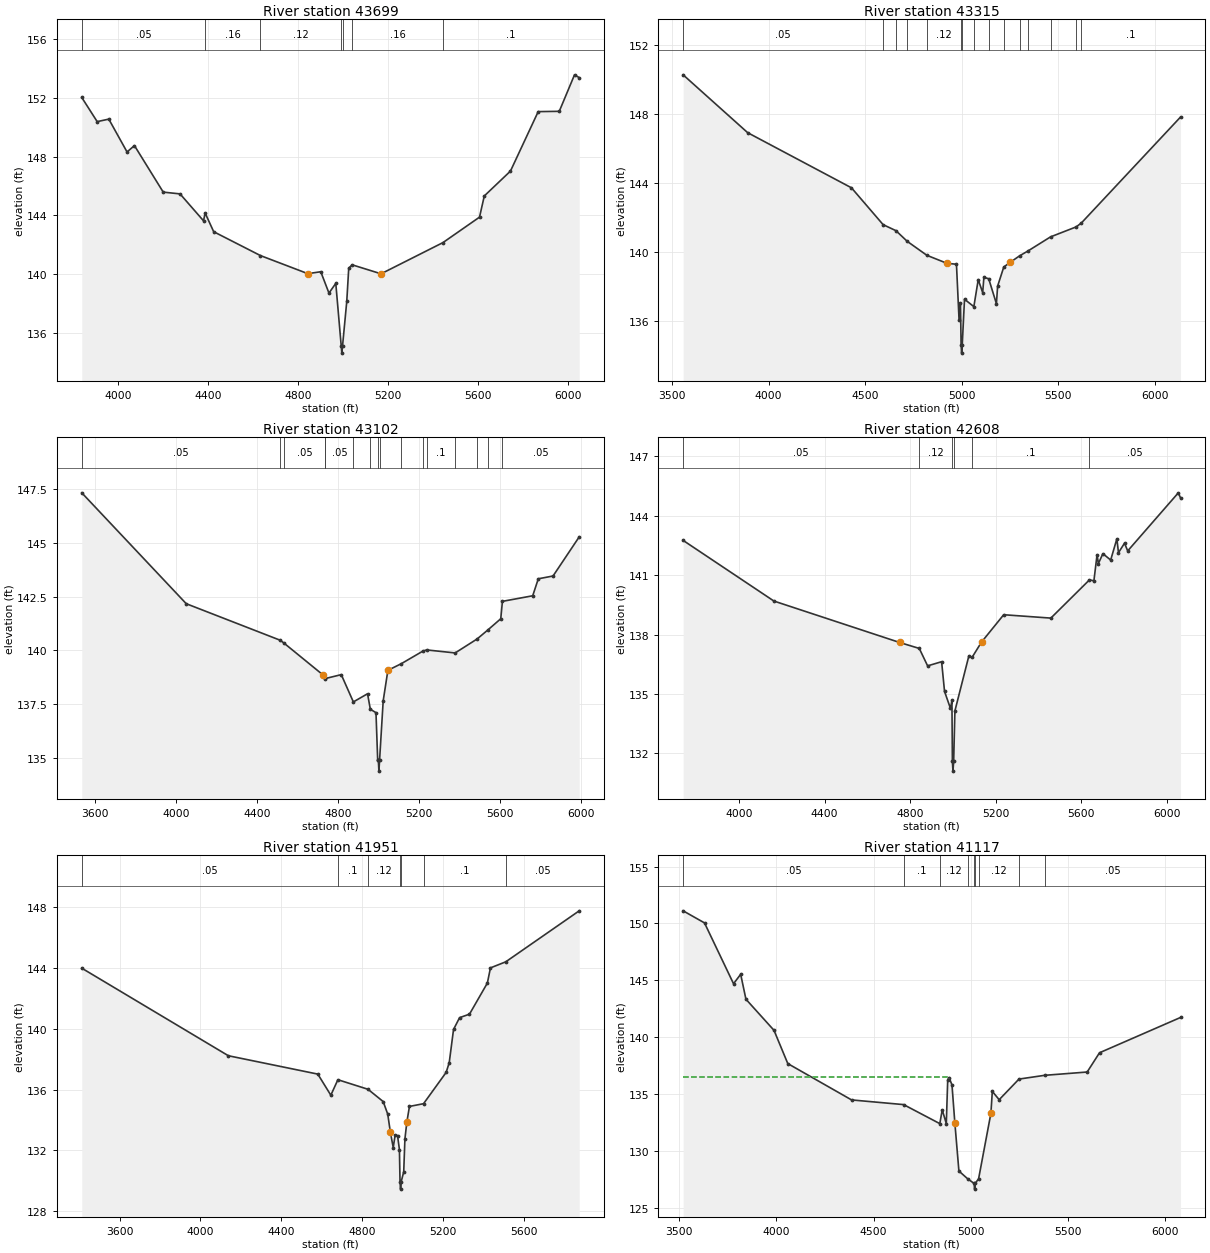
Type RM Length L Ch R = 1 ,43699   ,384,384,384
BEGIN DESCRIPTION:
Mapping XS 0b9f4a46
END DESCRIPTION:
XS GIS Cut Line= 4
      2324092.74     13179710.31      2323731.63     13178911.71
       2323523.3     13178585.32      2322711.79     13178092.86
#Sta/Elev= 30
  3837.5  152.01    3906  150.37  3957.7  150.54  4038.8  148.31  4071.8  148.74
  4199.8  145.58  4274.6  145.46  4379.1  143.63  4386.2  144.16  4424.3  142.89
  4632.1  141.27  4843.2  140.04  4900.7  140.17  4937.1  138.72  4967.5  139.38
  4991.6  135.14  4994.4  134.64  4997.6  135.14  5016.3  138.15  5025.1  140.41
  5040.4  140.64  5168.8  140.03  5444.2  142.15  5606.9  143.88  5628.2  145.32
  5744.6  147.01    5868  151.05  5961.7  151.07  6029.5  153.55  6050.4  153.36
#Mann= 7 ,-1 , 0
  3837.5     .05       0  4386.2     .16       0  4632.1     .12       0
  4991.6     .07       0  4997.6     .12       0  5040.4     .16       0
  5444.2      .1       0
Bank Sta=4843.2,5168.8
XS Rating Curve= 0 ,0
Exp/Cntr=0.3,0.1

Type RM Length L Ch R = 1 ,43315   ,213,213,213
BEGIN DESCRIPTION:
SANDY HOLLOW CREEK 72.0
END DESCRIPTION:
XS GIS Cut Line= 2
      2324649.86     13179801.82      2323131.74     13177719.83
#Sta/Elev= 30
  3557.2  150.28  3891.6  146.92  4429.2  143.72  4593.2  141.58  4659.7  141.23
  4718.2  140.61  4819.9   139.8  4922.8  139.34  4973.1  139.28  4986.6  136.05
  4993.9  137.04  4997.1  134.62  4999.9  134.12  5003.1  134.62  5014.8  137.25
  5063.2  136.82  5085.9  138.39    5109  137.63  5115.2  138.52  5140.1  138.44
  5180.1  136.99  5186.3  138.01  5218.2  139.12  5251.2  139.39  5300.2  139.77
  5343.3  140.05  5460.4  140.87  5593.3  141.45  5620.5  141.68  6133.9  147.83
#Mann= 15 ,-1 , 0
  3557.2     .05       0  4593.2     .08       0  4659.7     .16       0
  4718.2     .05       0  4819.9     .12       0  4997.1     .07       0
  5003.1     .12       0  5063.2     .08       0  5140.1     .16       0
  5218.2      .1       0  5300.2     .16       0  5343.3      .1       0
  5460.4     .16       0  5593.3     .05       0  5620.5      .1       0
Bank Sta=4922.8,5251.2
XS Rating Curve= 0 ,0
Exp/Cntr=0.3,0.1

Type RM Length L Ch R = 1 ,43102   ,494,494,494
BEGIN DESCRIPTION:
SANDY HOLLOW CREEK 71.0
END DESCRIPTION:
XS GIS Cut Line= 2
      2324714.93     13179641.19      2323269.64     13177653.37
#Sta/Elev= 30
  3534.3  147.33  4050.5  142.17  4514.8  140.47    4533  140.34  4724.4  138.87
  4737.5   138.7  4738.4  138.69  4816.4  138.87  4876.1   137.6  4946.2  137.98
    4960  137.26  4987.9   137.1  4996.4  134.88  4999.6  134.88  5002.4  134.38
  5005.6  134.88  5023.5  137.65  5046.7  139.07  5113.1  139.38  5218.7  139.96
    5238  140.02  5379.1  139.88  5487.7  140.53  5539.5  140.94  5604.4  141.47
  5612.6  142.28  5762.3  142.54  5789.9  143.33  5862.8  143.46    5992  145.28
#Mann= 16 ,-1 , 0
  3534.3     .05       0  4514.8     .08       0    4533     .05       0
  4737.5     .08       0  4738.4     .05       0  4876.1     .12       0
    4960     .08       0  4999.6     .07       0  5005.6     .08       0
  5113.1      .1       0  5218.7     .08       0    5238      .1       0
  5379.1     .08       0  5487.7      .1       0  5539.5     .08       0
  5612.6     .05       0
Bank Sta=4724.4,5046.7
XS Rating Curve= 0 ,0
Exp/Cntr=0.3,0.1

Type RM Length L Ch R = 1 ,42608   ,657,657,657
BEGIN DESCRIPTION:
SANDY HOLLOW CREEK 70.0
END DESCRIPTION:
XS GIS Cut Line= 4
      2325005.72     13179137.71      2324267.89     13178287.03
      2323872.93     13178178.53       2323422.1      13177528.3
#Sta/Elev= 30
  3738.1  142.75  4162.8  139.69  4750.9   137.6  4842.8   137.3  4881.8  136.42
  4947.3  136.63    4961  135.13  4988.8  134.27  4995.5  134.68  4997.7  131.61
  5000.4  131.11  5003.7  131.61  5009.5  134.15  5074.7  136.92  5089.8  136.85
    5134  137.62  5237.7     139  5458.3  138.83    5639  140.76  5659.7  140.71
  5674.5  142.03  5680.6  141.58  5701.7  142.08  5738.2  141.76  5767.1  142.83
  5774.7  142.13  5802.9  142.61  5817.8  142.22  6054.6  145.15    6065  144.89
#Mann= 6 ,-1 , 0
  3738.1     .05       0  4842.8     .12       0  4997.7     .07       0
  5003.7     .12       0  5089.8      .1       0    5639     .05       0
Bank Sta=4750.9,5134
XS Rating Curve= 0 ,0
Exp/Cntr=0.3,0.1

Type RM Length L Ch R = 1 ,41951   ,834,834,834
BEGIN DESCRIPTION:
SANDY HOLLOW CREEK 69.0
END DESCRIPTION:
XS GIS Cut Line= 3
      2325413.71     13179007.49      2324576.05     13177918.11
       2323656.7     13177341.34
#Sta/Elev= 30
  3413.1     144  4137.9  138.23  4580.1  137.02  4644.5  135.63  4679.4  136.65
  4828.3  136.02  4903.4  135.21  4925.9  134.38  4938.8   133.2  4953.1  132.18
  4962.4     133  4974.3  132.97  4983.7  132.05  4986.6  129.94  4989.3  129.44
  4992.6  129.94  5004.9  130.58  5010.8  132.74  5020.2  133.84  5033.2  134.89
  5102.9  135.07  5214.6  137.13  5229.9  137.77  5251.2  139.96  5281.1  140.74
  5330.1  140.97  5418.5  143.02  5433.8  144.02  5509.5  144.42  5872.6  147.78
#Mann= 7 ,-1 , 0
  3413.1     .05       0  4679.4      .1       0  4828.3     .12       0
  4986.6     .07       0  4992.6     .12       0  5102.9      .1       0
  5509.5     .05       0
Bank Sta=4938.8,5020.2
XS Rating Curve= 0 ,0
Exp/Cntr=0.3,0.1

Type RM Length L Ch R = 1 ,41117   ,113,113,113
BEGIN DESCRIPTION:
Mapping XS 15fa5c60
END DESCRIPTION:
XS GIS Cut Line= 4
      2325860.78     13178456.31      2325014.42     13177297.45
      2324905.91     13177271.41      2324202.76     13176542.21
#Sta/Elev= 30
  3519.8  151.11  3629.8  150.05  3779.2  144.71  3815.9  145.54    3843  143.35
  3987.4  140.62  4058.4   137.7  4386.7  134.51  4654.4   134.1  4840.6  132.43
  4853.1  133.64    4874  132.44  4881.3  136.25  4888.7  136.47  4903.3  135.82
    4918   132.5  4938.9  128.27  4983.8  127.59    5017  127.18  5019.7  126.68
    5023  127.18  5040.4   127.6  5103.6  133.34  5110.8  135.26  5146.1  134.53
    5248  136.34  5379.9  136.67  5598.9  136.96  5662.4  138.65  6079.4  141.75
#Mann= 9 ,-1 , 0
  3519.8     .05       0  4654.4      .1       0  4840.6     .12       0
  4983.8      .1       0    5017     .07       0    5023      .1       0
  5040.4     .12       0    5248      .1       0  5379.9     .05       0
#XS Ineff= 2 , 0
          4885.8  136.53
Permanent Ineff=
       F       F
Bank Sta=4918,5103.6
XS Rating Curve= 0 ,0
Exp/Cntr=0.3,0.1

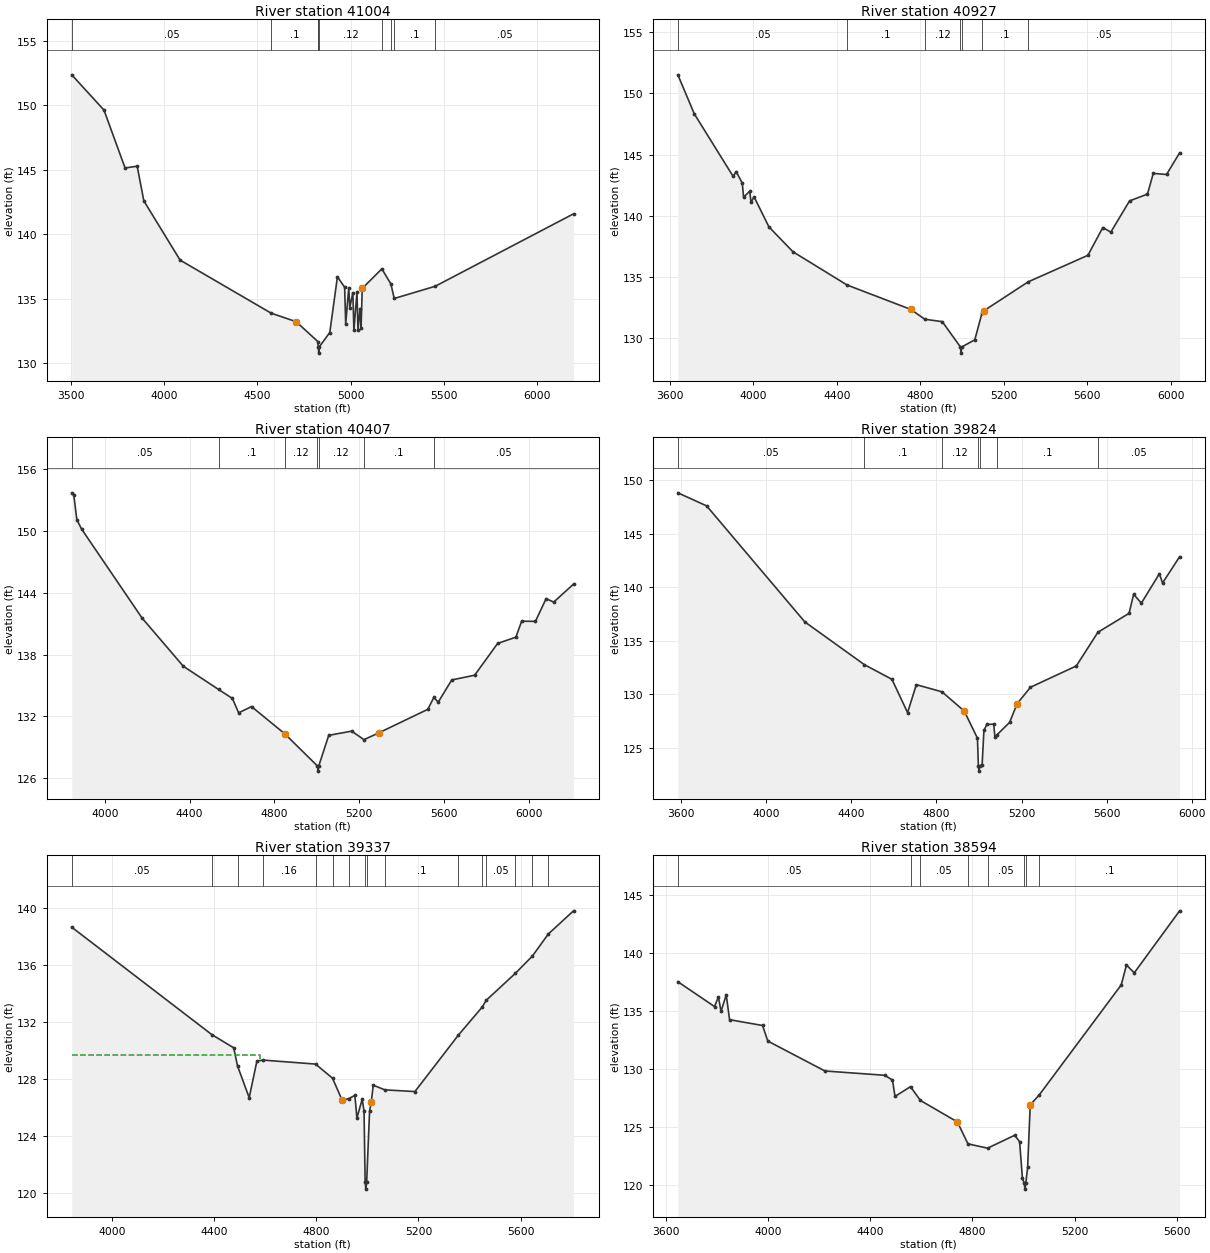
Type RM Length L Ch R = 1 ,41004   ,77,77,77
BEGIN DESCRIPTION:
SANDY HOLLOW CREEK 68.0
END DESCRIPTION:
XS GIS Cut Line= 5
      2325937.75     13178446.89      2325101.23     13177293.11
      2325027.44     13177154.22      2324901.57     13177201.96
      2324289.56     13176446.72
#Sta/Elev= 30
    3506  152.37  3678.9  149.63  3791.7  145.14  3856.7  145.28  3892.2  142.59
  4086.6  137.99  4574.9  133.87  4708.7  133.21  4824.8  131.67  4827.1  131.27
  4829.9  130.77  4833.1  131.27  4888.9  132.37  4929.9   136.7  4968.5  135.88
  4974.2  133.03  4990.5  135.85  4996.2  134.31  5012.5  135.46  5018.2  132.54
  5034.5  135.51  5040.1   132.6  5050.8  134.23  5056.5  132.72  5062.8  135.79
  5167.8  137.31  5216.5  136.14  5234.2  135.01    5454  135.96  6195.1  141.58
#Mann= 9 ,-1 , 0
    3506     .05       0  4574.9      .1       0  4824.8     .12       0
  4827.1     .07       0  4833.1     .12       0  5167.8      .1       0
  5216.5     .12       0  5234.2      .1       0    5454     .05       0
Bank Sta=4708.7,5062.8
XS Rating Curve= 0 ,0
Exp/Cntr=0.3,0.1

Type RM Length L Ch R = 1 ,40927   ,520,520,520
BEGIN DESCRIPTION:
SANDY HOLLOW CREEK 67.0
END DESCRIPTION:
XS GIS Cut Line= 3
      2325937.73     13178296.87      2325137.72     13177196.85
      2324837.72     13176196.85
#Sta/Elev= 30
  3638.6  151.52  3717.1  148.34  3903.3  143.23    3918  143.62  3947.4  142.67
  3953.5  141.53  3982.9  142.01  3989.1  141.11  4003.8  141.55  4074.9   139.1
    4190  137.07  4449.7  134.35  4754.9  132.36  4821.5  131.56  4905.6  131.36
  4992.7  129.29  4995.4  128.79  4998.7  129.29  5061.4  129.88  5096.4  132.09
  5103.2  132.23    5317  134.61  5603.4  136.78  5674.8  139.05  5713.1  138.67
  5802.7  141.22  5888.8  141.78  5916.6  143.47  5980.2  143.38  6042.8  145.15
#Mann= 7 ,-1 , 0
  3638.6     .05       0  4449.7      .1       0  4821.5     .12       0
  4992.7     .07       0  4998.7     .12       0  5096.4      .1       0
    5317     .05       0
Bank Sta=4754.9,5103.2
XS Rating Curve= 0 ,0
Exp/Cntr=0.3,0.1

Type RM Length L Ch R = 1 ,40407   ,583,583,583
BEGIN DESCRIPTION:
SANDY HOLLOW CREEK 66.0
END DESCRIPTION:
XS GIS Cut Line= 4
      2325982.31     13178265.34      2325574.32     13177423.32
      2325578.66      13177097.8      2324937.71     13176196.84
#Sta/Elev= 30
  3843.8  153.73  3853.2  153.54  3867.8  151.12  3890.4   150.2  4175.5  141.55
  4370.1  136.86  4536.7   134.6  4601.5  133.73  4631.1  132.33  4691.8  132.94
  4848.6  130.29  5002.9  127.16  5005.7  126.66  5008.9  127.16    5056  130.14
  5164.2  130.55  5222.1  129.72  5292.1  130.38  5523.3  132.67  5551.9  133.83
  5572.5  133.37  5636.4  135.53  5744.3  135.99  5852.8  139.08  5938.9  139.69
    5966  141.24  6031.1  141.23  6081.6  143.44  6117.2   143.1  6210.7  144.85
#Mann= 7 ,-1 , 0
  3843.8     .05       0  4536.7      .1       0  4848.6     .12       0
  5002.9     .07       0  5008.9     .12       0  5222.1      .1       0
  5551.9     .05       0
Bank Sta=4848.6,5292.1
XS Rating Curve= 0 ,0
Exp/Cntr=0.3,0.1

Type RM Length L Ch R = 1 ,39824   ,487,487,487
BEGIN DESCRIPTION:
SANDY HOLLOW CREEK 65.0
END DESCRIPTION:
XS GIS Cut Line= 4
      2326264.43     13178195.91      2325973.62     13177015.33
       2325561.3      13176828.7      2325187.73     13176246.87
#Sta/Elev= 30
  3583.6  148.81  3718.9  147.59  4180.6  136.75  4460.9  132.75  4590.5  131.38
    4664  128.27  4705.2  130.88  4826.1  130.21  4930.7  128.41  4992.6  125.88
    4997   123.3  4999.7   122.8    5003   123.3  5014.5  123.38  5023.1   126.6
  5036.5  127.16  5069.3  127.19  5074.8  125.96  5084.3  126.19  5144.1  127.36
  5179.2   129.1    5242  130.64  5457.6  132.63  5559.3  135.78  5705.8  137.55
  5727.2  139.33  5763.5   138.5  5848.4  141.25  5863.2  140.38  5943.5  142.84
#Mann= 7 ,-1 , 0
  3583.6     .05       0  4460.9      .1       0  4826.1     .12       0
    4997     .07       0    5003     .12       0  5084.3      .1       0
  5559.3     .05       0
#XS Ineff= 2 , 0
         4705.97  130.85
Permanent Ineff=
       F       F
Bank Sta=4930.7,5179.2
XS Rating Curve= 0 ,0
Exp/Cntr=0.3,0.1

Type RM Length L Ch R = 1 ,39337   ,743,743,743
BEGIN DESCRIPTION:
SANDY HOLLOW CREEK 64.0
END DESCRIPTION:
XS GIS Cut Line= 3
      2326287.72     13177696.85       2326183.4     13176774.16
       2325531.7     13175969.93
#Sta/Elev= 30
  3843.4  138.66  4392.3  131.11  4477.4  130.19  4492.1  128.92  4537.8  126.69
    4568  129.26  4591.9  129.33  4797.5  129.05  4863.9  128.06  4901.9   126.5
  4927.8  126.63  4951.5  126.85  4959.4  125.26  4980.2  126.59  4987.3  125.74
  4991.6  120.77  4994.3  120.27  4997.6  120.77    5009  125.76  5015.4  126.36
  5023.3  127.57  5068.7  127.24  5186.4  127.12  5356.8  131.09  5449.2  133.04
  5465.6  133.53  5579.5  135.42    5646  136.63  5708.4  138.18  5807.1  139.81
#Mann= 16 ,-1 , 0
  3843.4     .05       0  4392.3      .1       0  4492.1     .05       0
  4591.9     .16       0  4797.5      .1       0  4863.9     .16       0
  4927.8     .12       0  4991.6     .07       0  4997.6     .12       0
  5068.7      .1       0  5356.8     .05       0  5449.2      .1       0
  5465.6     .05       0  5579.5      .1       0    5646     .05       0
  5708.4      .1       0
#XS Ineff= 2 , 0
         4579.55  129.69
Permanent Ineff=
       F       F
Bank Sta=4901.9,5015.4
XS Rating Curve= 0 ,0
Exp/Cntr=0.3,0.1

Type RM Length L Ch R = 1 ,38594   ,429,429,429
BEGIN DESCRIPTION:
SANDY HOLLOW CREEK 63.0
END DESCRIPTION:
XS GIS Cut Line= 3
      2326447.29     13177663.03      2326634.79     13176621.38
      2326468.12     13175732.46
#Sta/Elev= 30
  3647.8  137.55  3791.3  135.41  3806.5  136.25  3816.6  134.99    3837  136.42
    3850  134.28  3979.2  133.78  3999.5  132.44  4223.1  129.86  4456.8  129.49
  4487.3  129.08  4497.4  127.67  4557.9  128.51  4596.6  127.32  4741.3  125.47
  4782.6  123.58  4859.4  123.21  4965.2  124.32  4984.6  123.77  4995.7  120.62
  5002.8  120.18  5005.6  119.68  5008.8  120.18    5016  121.55  5026.2  126.94
  5061.6   127.8  5382.3  137.28  5402.6  138.99  5433.2  138.32  5610.6  143.66
#Mann= 8 ,-1 , 0
  3647.8     .05       0  4557.9      .1       0  4596.6     .05       0
  4782.6      .1       0  4859.4     .05       0  5002.8     .04       0
  5008.8     .05       0  5061.6      .1       0
Bank Sta=4741.3,5026.2
XS Rating Curve= 0 ,0
Exp/Cntr=0.3,0.1

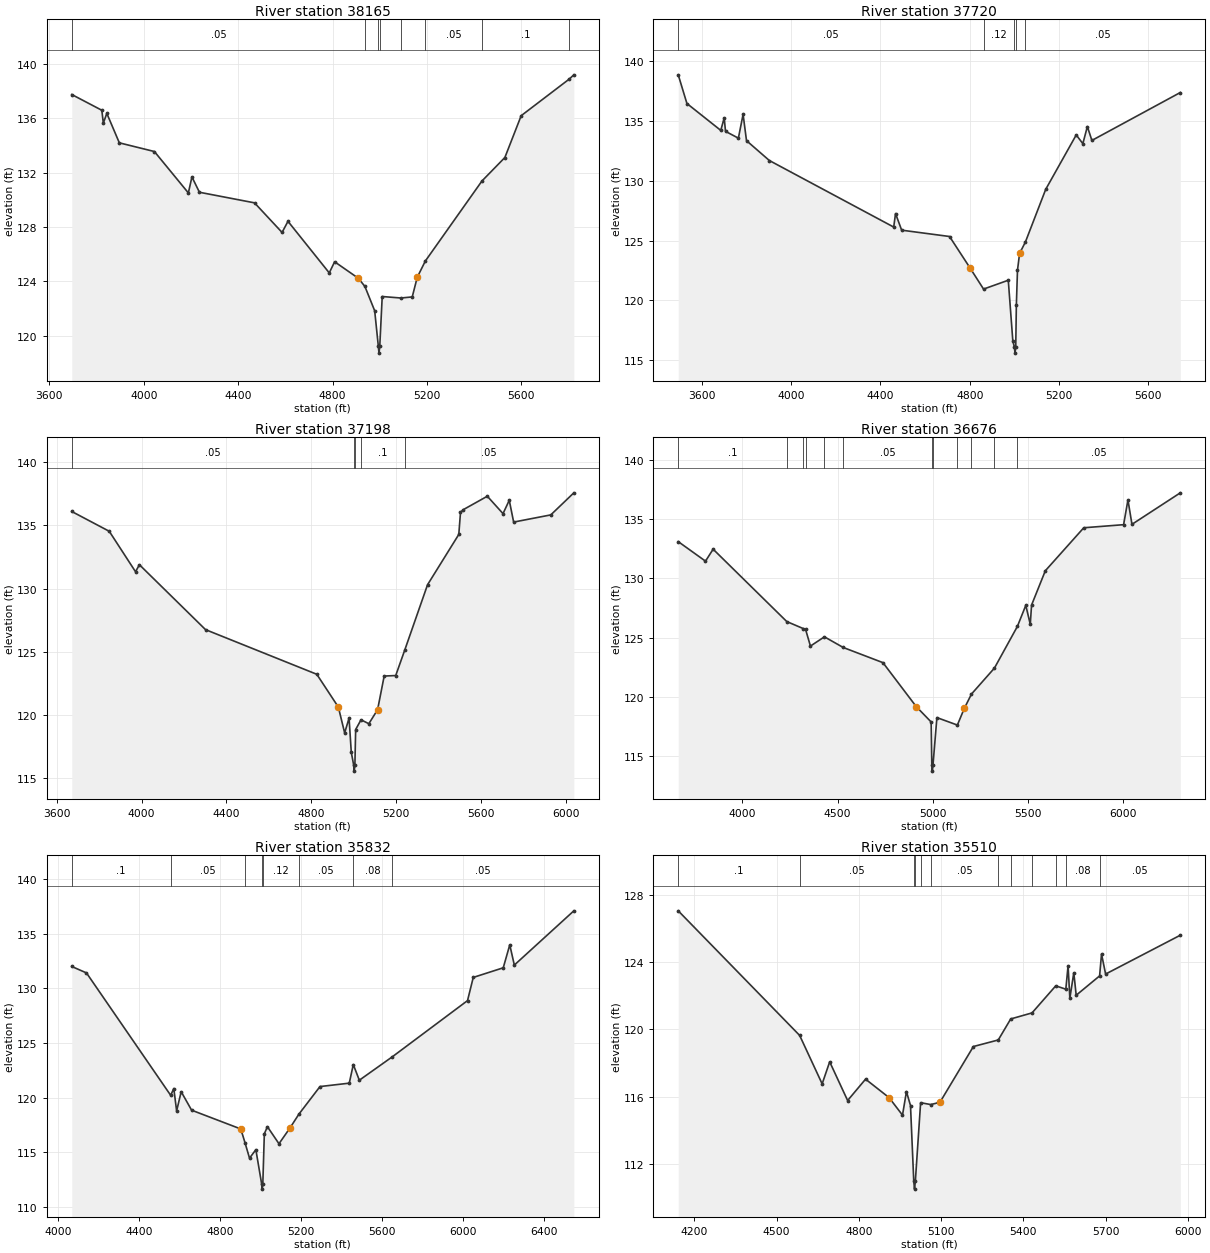
Type RM Length L Ch R = 1 ,38165   ,445,445,445
BEGIN DESCRIPTION:
SANDY HOLLOW CREEK 62.0
END DESCRIPTION:
XS GIS Cut Line= 2
      2326487.73     13177696.82      2327197.09     13175691.38
#Sta/Elev= 30
    3695  137.76  3822.3   136.6  3828.7  135.65  3843.5  136.37  3896.5   134.2
  4045.1  133.56    4189  130.51  4204.1  131.69  4235.9  130.56  4469.3  129.78
    4586   127.6    4611  128.42  4785.9  124.62  4808.7  125.44  4909.5  124.22
    4937  123.62  4978.4  121.83  4993.9  119.21  4996.6  118.71  4999.9  119.21
  5010.3  122.88  5089.5  122.77  5137.5  122.85  5158.8   124.3  5193.2   125.5
  5432.9  131.39    5530  133.12  5599.1   136.2  5802.2  138.89  5822.2  139.21
#Mann= 8 ,-1 , 0
    3695     .05       0    4937     .12       0  4993.9     .07       0
  4999.9     .12       0  5089.5     .16       0  5193.2     .05       0
  5432.9      .1       0  5802.2     .05       0
Bank Sta=4909.5,5158.8
XS Rating Curve= 0 ,0
Exp/Cntr=0.3,0.1

Type RM Length L Ch R = 1 ,37720   ,522,522,522
BEGIN DESCRIPTION:
SANDY HOLLOW CREEK 61.0
END DESCRIPTION:
XS GIS Cut Line= 3
      2326669.53     13177781.08      2327287.57     13176808.88
      2327454.24     13175725.54
#Sta/Elev= 30
  3494.8  138.88  3533.7  136.48  3685.3  134.23  3700.6  135.28  3706.5  134.15
  3764.1  133.58  3785.2  135.57  3800.5  133.37  3902.7  131.71  4459.6  126.14
  4467.8  127.27  4495.2  125.88  4709.6  125.35  4800.6  122.74  4861.9  120.95
  4972.6  121.69  4992.9  116.63    5000  116.09  5002.7  115.59    5006  116.09
  5008.8  119.62  5013.8  122.52  5023.2  123.93  5049.3  124.89  5140.3   129.3
  5276.9  133.85  5306.5  133.12  5326.7  134.55    5347  133.39  5742.9   137.4
#Mann= 5 ,-1 , 0
  3494.8     .05       0  4861.9     .12       0    5000     .07       0
    5006     .12       0  5049.3     .05       0
Bank Sta=4800.6,5023.2
XS Rating Curve= 0 ,0
Exp/Cntr=0.3,0.1

Type RM Length L Ch R = 1 ,37198   ,522,522,522
BEGIN DESCRIPTION:
SANDY HOLLOW CREEK 60.0
END DESCRIPTION:
XS GIS Cut Line= 3
      2327412.57     13177989.43       2327808.4      13176906.1
       2327495.9     13175732.48
#Sta/Elev= 30
  3670.7  136.11  3847.5  134.54  3971.5  131.33  3989.6  131.89  4301.6  126.74
  4826.3   123.2  4927.9   120.6  4957.7  118.55  4978.5  119.73  4988.9  117.02
    5000  116.02  5002.8  115.52    5006  116.02  5009.6  118.82  5034.9  119.59
  5071.7  119.28    5113  120.39  5144.1  123.06  5198.5   123.1  5241.1  125.12
  5348.6   130.3    5496  134.29    5504  136.03  5516.6  136.25  5630.5  137.32
  5704.6  135.94    5734     137  5754.7  135.27  5929.9  135.84  6038.6  137.59
#Mann= 5 ,-1 , 0
  3670.7     .05       0    5000     .03       0    5006     .05       0
  5034.9      .1       0  5241.1     .05       0
Bank Sta=4927.9,5113
XS Rating Curve= 0 ,0
Exp/Cntr=0.3,0.1

Type RM Length L Ch R = 1 ,36676   ,844,844,844
BEGIN DESCRIPTION:
SANDY HOLLOW CREEK 59.0
END DESCRIPTION:
XS GIS Cut Line= 3
      2328315.35     13178079.66      2328391.74     13176989.44
      2327544.53     13175697.79
#Sta/Elev= 30
  3663.3   133.1  3806.5  131.45  3846.6  132.46  4233.5  126.35  4321.2  125.75
  4332.4  125.68  4357.8  124.28  4431.3  125.06  4530.2  124.16  4738.7  122.88
  4913.6  119.17    4992  117.87  4995.5  114.22  4998.2  113.72  5001.5  114.22
  5022.2  118.24  5129.7  117.61  5165.9  119.01  5203.9  120.23  5324.4  122.42
    5445  125.94  5489.2  127.72  5512.7  126.11  5519.4  127.74  5591.8  130.64
  5793.7  134.27    6003  134.53  6025.8  136.62  6046.9  134.56  6300.9  137.22
#Mann= 12 ,-1 , 0
  3663.3      .1       0  4233.5     .05       0  4321.2      .1       0
  4332.4     .05       0  4431.3      .1       0  4530.2     .05       0
  4995.5     .03       0  5001.5     .05       0  5129.7      .1       0
  5203.9     .05       0  5324.4      .1       0    5445     .05       0
Bank Sta=4913.6,5165.9
XS Rating Curve= 0 ,0
Exp/Cntr=0.3,0.1

Type RM Length L Ch R = 1 ,35832   ,322,322,322
BEGIN DESCRIPTION:
SANDY HOLLOW CREEK 58.0
END DESCRIPTION:
XS GIS Cut Line= 3
      2329087.74      13177396.9      2328669.51     13176183.88
      2327606.99     13175628.31
#Sta/Elev= 30
  4066.8     132  4139.6  131.41  4555.7  120.22  4571.2  120.84  4585.2  118.79
  4607.7  120.55  4659.2  118.86  4902.5  117.14  4923.6  115.86  4945.6  114.47
  4976.9  115.25  5005.3  112.14    5008  111.64  5011.3  112.14  5018.8   116.7
    5034  117.35  5091.1  115.79  5145.8  117.24  5189.4  118.49  5293.9  121.02
  5438.6  121.33  5458.6  123.03  5488.4   121.6  5652.1  123.75  6023.3  128.88
  6051.6     131  6199.9  131.88  6232.1  133.98  6254.7  132.13  6548.9  137.09
#Mann= 8 ,-1 , 0
  4066.8      .1       0  4555.7     .05       0  4923.6     .12       0
  5005.3     .07       0  5011.3     .12       0  5189.4     .05       0
  5458.6     .08       0  5652.1     .05       0
Bank Sta=4902.5,5145.8
XS Rating Curve= 0 ,0
Exp/Cntr=0.3,0.1

Type RM Length L Ch R = 1 ,35510   ,68,68,68
BEGIN DESCRIPTION:
SANDY HOLLOW CREEK 57.0
END DESCRIPTION:
XS GIS Cut Line= 2
      2329487.69     13177096.82      2328437.74     13175596.89
#Sta/Elev= 30
  4141.2  127.05    4584  119.64    4666  116.76  4693.5  118.07  4758.9  115.77
  4824.3  117.04  4910.2  115.94    4959   114.9  4973.4   116.3  4988.2  115.47
    5000     111  5002.8   110.5    5006     111  5025.1  115.64  5061.8  115.53
  5095.4  115.66  5217.5  118.98  5308.2  119.37  5353.6  120.62  5431.4  120.98
  5517.9  122.59  5554.6  122.39  5562.8  123.79  5569.3  121.85  5583.7  123.37
  5592.4  122.03  5677.8  123.18  5684.8  124.48  5699.7  123.29  5972.1   125.6
#Mann= 12 ,-1 , 0
  4141.2      .1       0    4584     .05       0    5000     .04       0
    5006     .05       0  5025.1     .16       0  5061.8     .05       0
  5308.2     .08       0  5353.6     .05       0  5431.4     .08       0
  5517.9     .05       0  5554.6     .08       0  5677.8     .05       0
Bank Sta=4910.2,5095.4
XS Rating Curve= 0 ,0
Exp/Cntr=0.3,0.1