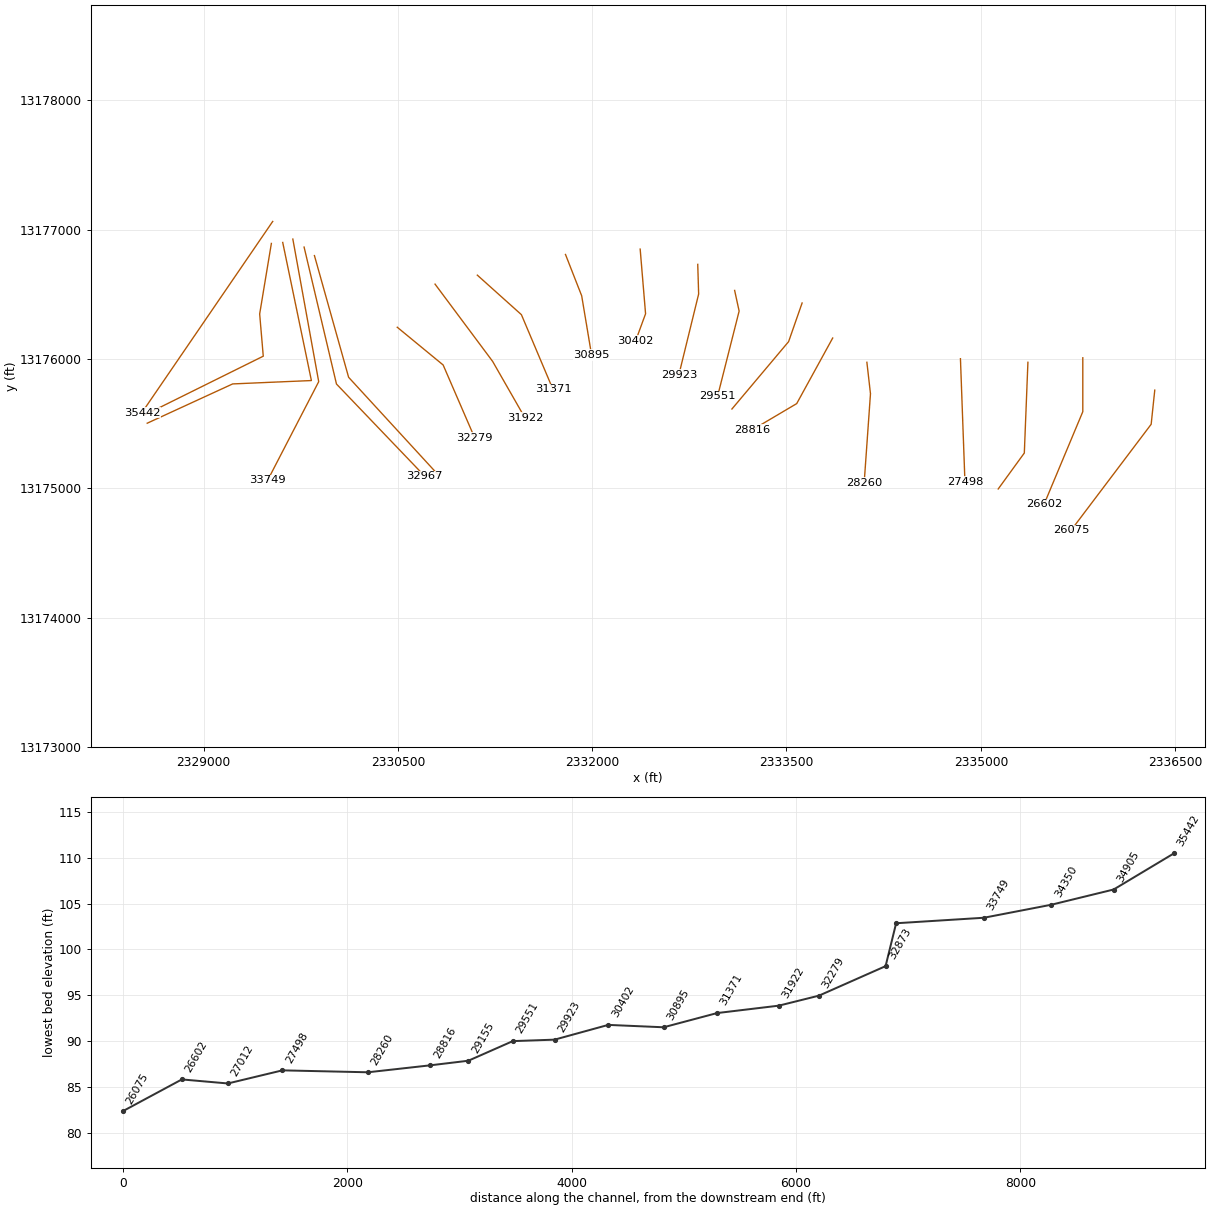
HEC-RAS study SANDY HOLLOW CREEK.prj: SANDY HOLLOW CREEK Base Level Engineering

--- SANDY HOLLOW CREEK.g01 (geometry) --- (continued)

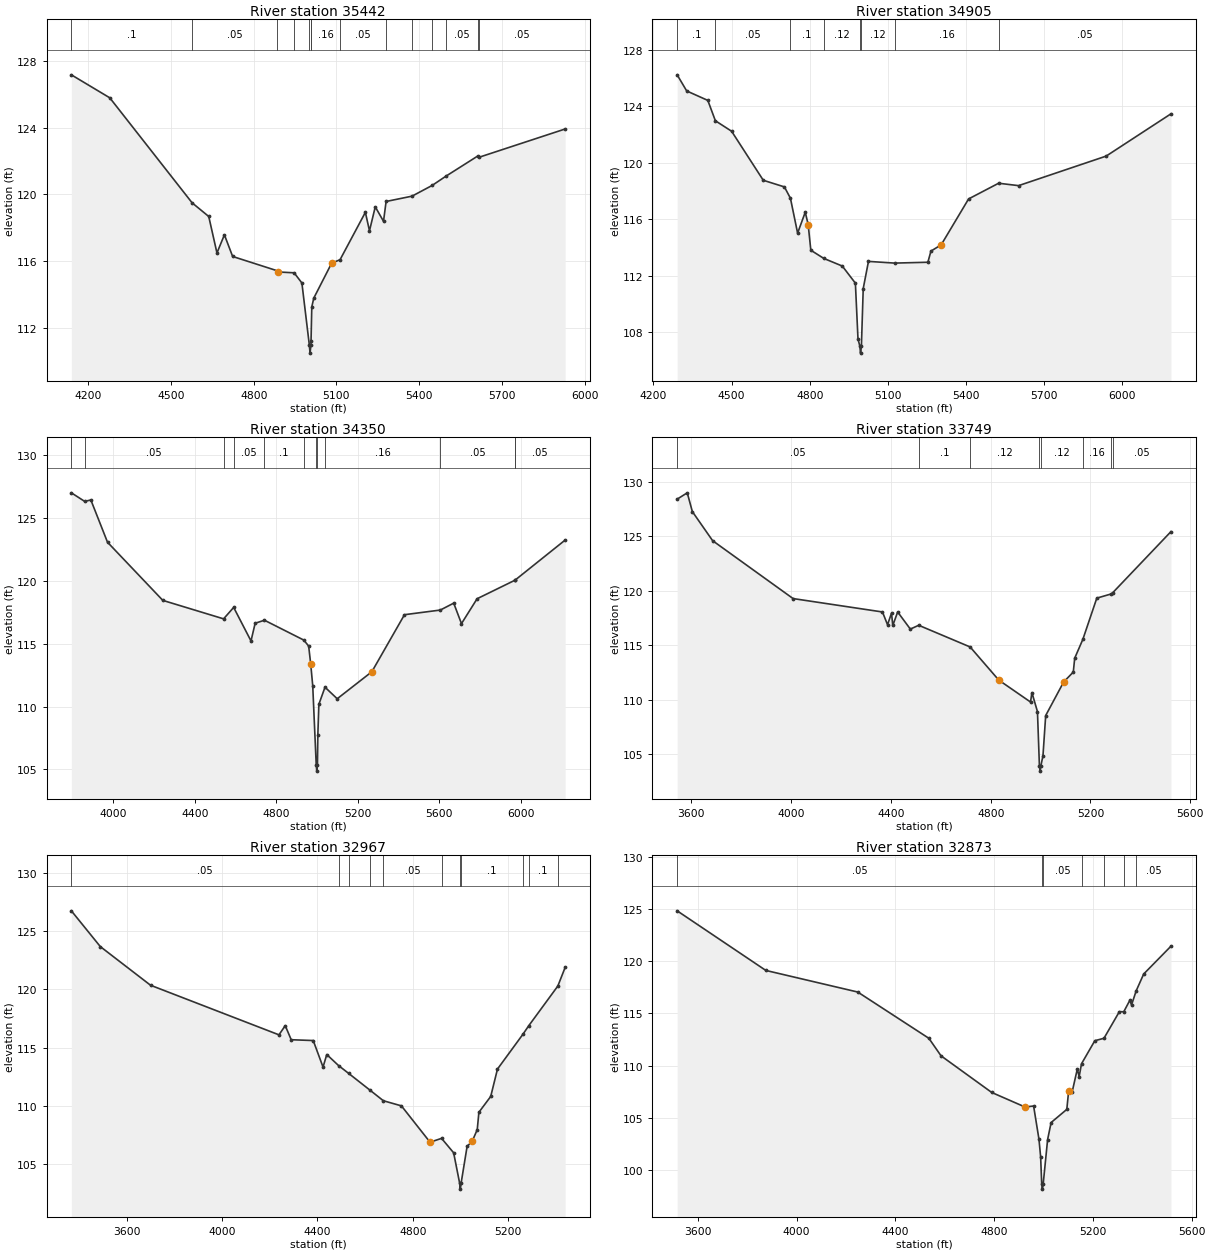
Type RM Length L Ch R = 1 ,35442   ,537,537,537
BEGIN DESCRIPTION:
SANDY HOLLOW CREEK 56.0
END DESCRIPTION:
XS GIS Cut Line= 2
      2329534.08     13177063.01      2328523.68     13175583.87
#Sta/Elev= 30
  4138.4  127.17  4277.8  125.79  4576.4  119.49  4636.8  118.67  4666.6  116.48
  4693.6  117.57  4723.5  116.27  4885.7  115.41    4888  115.34  4946.5  115.29
  4974.7  114.68  5001.6  110.97  5004.3  110.47  5007.6  110.97  5007.9   111.2
  5010.6  113.24  5017.8  113.77  5082.4  115.86  5113.3  116.08    5205  118.92
  5219.9  117.81  5240.9  119.25  5270.8  118.38  5280.2  119.57  5374.3  119.89
    5447  120.53  5496.5  121.08  5613.8  122.31  5618.7  122.23  5929.7  123.92
#Mann= 14 ,-1 , 0
  4138.4      .1       0  4576.4     .05       0  4885.7     .12       0
  4946.5     .05       0  5001.6     .04       0  5007.6     .05       0
  5007.9     .16       0  5113.3     .05       0  5280.2     .08       0
  5374.3     .05       0    5447     .08       0  5496.5     .05       0
  5613.8     .08       0  5618.7     .05       0
Bank Sta=4888,5082.4
XS Rating Curve= 0 ,0
Exp/Cntr=0.3,0.1

Type RM Length L Ch R = 1 ,34905   ,555,555,555
BEGIN DESCRIPTION:
Mapping XS 6e8b8a7e
END DESCRIPTION:
XS GIS Cut Line= 4
      2329523.69     13176892.94       2329433.4     13176347.76
      2329461.18     13176021.37      2328552.11     13175570.31
#Sta/Elev= 30
  4291.1  126.22  4327.7  125.08  4408.8  124.41  4437.8  122.97    4500  122.23
  4621.6  118.76  4702.7  118.29  4725.8  117.49  4753.4  115.02  4782.7   116.5
  4793.9  115.63  4804.1  113.81    4854  113.23  4924.9  112.69  4975.1  111.48
  4985.1  107.53  4992.2  107.03  4994.9  106.53  4998.2  107.03  5005.2   111.1
  5025.3  113.02  5125.9   112.9  5253.3  112.96  5265.1  113.75  5304.3  114.19
  5409.6  117.44  5524.8  118.55  5601.3  118.38  5937.5  120.47  6186.1  123.46
#Mann= 8 ,-1 , 0
  4291.1      .1       0  4437.8     .05       0  4725.8      .1       0
    4854     .12       0  4992.2     .07       0  4998.2     .12       0
  5125.9     .16       0  5524.8     .05       0
Bank Sta=4793.9,5304.3
XS Rating Curve= 0 ,0
Exp/Cntr=0.3,0.1

Type RM Length L Ch R = 1 ,34350   ,601,601,601
BEGIN DESCRIPTION:
Mapping XS 4364c25f
END DESCRIPTION:
XS GIS Cut Line= 4
      2329611.36     13176900.67      2329832.71       13175833.
      2329225.07     13175806.96      2328565.34     13175503.14
#Sta/Elev= 30
  3793.8  127.02  3859.1  126.34  3889.6  126.45  3971.3  123.09  4242.9  118.46
  4541.4  116.99  4590.9   117.9    4676  115.23  4696.4  116.64  4742.1  116.88
  4935.3   115.3  4959.2  114.82  4969.2   113.4  4979.2  111.66  4996.3  105.37
    4999  104.87  5002.3  105.37  5004.3  107.78  5009.3  110.19  5039.4  111.55
  5099.4  110.63  5269.5  112.78  5429.7  117.32  5605.6  117.69  5671.5  118.24
  5709.6  116.61  5786.3  118.59  5972.9  120.07  5973.5  120.08  6218.7  123.26
#Mann= 12 ,-1 , 0
  3793.8      .1       0  3859.1     .05       0  4541.4      .1       0
  4590.9     .05       0  4742.1      .1       0  4935.3     .12       0
  4996.3     .07       0  5002.3     .12       0  5039.4     .16       0
  5605.6     .05       0  5972.9      .1       0  5973.5     .05       0
Bank Sta=4969.2,5269.5
XS Rating Curve= 0 ,0
Exp/Cntr=0.3,0.1

Type RM Length L Ch R = 1 ,33749   ,782,782,782
BEGIN DESCRIPTION:
SANDY HOLLOW CREEK 55.0
END DESCRIPTION:
XS GIS Cut Line= 3
      2329689.48     13176926.74      2329889.13     13175824.32
      2329494.54     13175061.15
#Sta/Elev= 30
    3543   128.4  3583.5  128.98  3603.9  127.26  3685.2  124.59  4007.7  119.28
  4366.1  118.05  4386.4  116.88  4402.3  117.94  4407.4  116.81    4427  118.05
  4477.8  116.48  4511.4  116.83  4717.5  114.84  4832.4   111.8  4959.6  109.79
  4965.2  110.65  4987.4  108.91  4995.2  103.95    4998  103.45  5001.2  103.95
  5009.5  104.86  5020.4  108.55  5092.5  111.63  5131.1  112.54  5136.7  113.81
  5169.4  115.54  5225.3  119.32  5282.4   119.7  5288.9  119.81  5522.5  125.42
#Mann= 8 ,-1 , 0
    3543     .05       0  4511.4      .1       0  4717.5     .12       0
  4995.2     .07       0  5001.2     .12       0  5169.4     .16       0
  5282.4      .1       0  5288.9     .05       0
Bank Sta=4832.4,5092.5
XS Rating Curve= 0 ,0
Exp/Cntr=0.3,0.1

Type RM Length L Ch R = 1 ,32967   ,94,94,94
BEGIN DESCRIPTION:
Mapping XS 1070ede4
END DESCRIPTION:
XS GIS Cut Line= 3
      2329776.28     13176865.14      2330026.28     13175806.09
      2330706.87     13175094.25
#Sta/Elev= 30
  3366.7  126.75  3488.2  123.68  3699.1  120.36  4238.3   116.1  4264.6  116.89
  4289.7  115.68  4382.2  115.61  4423.3  113.33    4439  114.41  4488.6  113.46
  4530.2   112.8  4621.6  111.33  4676.6  110.44  4752.4     110  4872.6  106.88
  4920.9  107.21  4971.6  105.97  4996.9  103.35  4999.7  102.85  5002.9  103.35
  5028.2  106.53  5049.3  106.95  5070.7  107.96  5077.6  109.45  5127.3  110.81
  5155.6  113.16  5262.5  116.15  5286.5  116.87    5409  120.29  5439.7  121.89
#Mann= 11 ,-1 , 0
  3366.7     .05       0  4488.6     .12       0  4530.2     .05       0
  4621.6      .1       0  4676.6     .05       0  4920.9      .1       0
  4996.9     .07       0  5002.9      .1       0  5262.5     .05       0
  5286.5      .1       0    5409     .05       0
Bank Sta=4872.6,5049.3
XS Rating Curve= 0 ,0
Exp/Cntr=0.3,0.1

Type RM Length L Ch R = 1 ,32873   ,594,594,594
BEGIN DESCRIPTION:
SANDY HOLLOW CREEK 54.0
END DESCRIPTION:
XS GIS Cut Line= 3
      2329856.15     13176799.12      2330120.03     13175858.18
      2330811.02     13175104.69
#Sta/Elev= 30
  3516.5  124.83  3875.6  119.12  4247.8  117.05  4535.8  112.62  4585.1  110.94
  4790.4  107.43  4924.9  106.04    4960  106.13  4981.6  102.96  4988.4  101.27
  4992.8   98.67  4995.5   98.17  4998.8   98.67  5016.7  102.92  5030.9  104.55
  5094.4  105.81  5101.8  107.55    5116  107.47    5137  109.68  5144.4  108.95
    5154  110.18  5207.9  112.39  5244.9  112.62  5307.2  115.17    5325  115.16
  5349.7  116.26  5356.5  115.81  5375.4  117.17  5405.8  118.78  5516.1  121.44
#Mann= 7 ,-1 , 0
  3516.5     .05       0  4992.8     .04       0  4998.8     .05       0
    5154      .1       0  5244.9     .05       0    5325      .1       0
  5375.4     .05       0
Bank Sta=4924.9,5101.8
XS Rating Curve= 0 ,0
Exp/Cntr=0.3,0.1

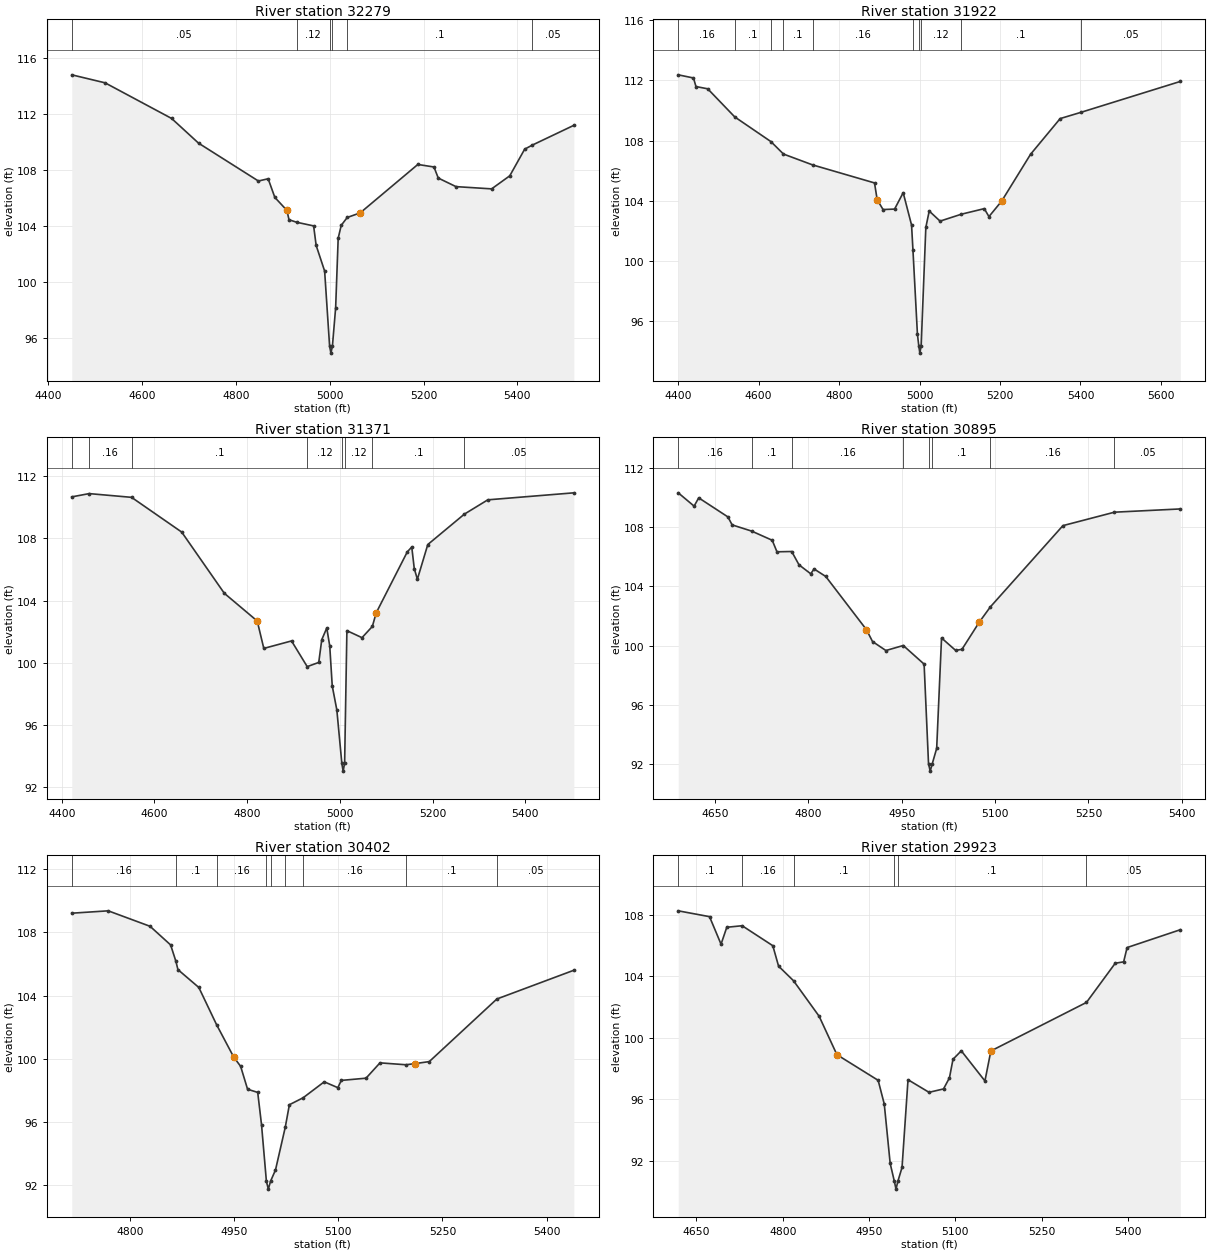
Type RM Length L Ch R = 1 ,32279   ,357,357,357
BEGIN DESCRIPTION:
SANDY HOLLOW CREEK 53.0
END DESCRIPTION:
XS GIS Cut Line= 3
      2330495.55     13176245.02      2330849.69     13175953.37
      2331092.53     13175391.37
#Sta/Elev= 30
  4449.7  114.79  4520.7  114.22  4662.7  111.68  4720.1  109.92  4847.8  107.22
  4868.6  107.38  4882.9  106.05  4908.5  105.13  4913.1  104.46  4929.4  104.28
  4965.6  104.02    4971  102.63  4989.1   100.8  4999.7   95.45  5002.5   94.95
  5005.7   95.45  5012.6   98.19    5018  103.14  5024.5  104.06  5037.3  104.62
    5065  104.95  5187.9   108.4  5222.3  108.22  5231.5  107.43  5269.3  106.82
  5345.3  106.66    5384  107.59  5415.8  109.49  5432.1  109.78  5520.7  111.19
#Mann= 6 ,-1 , 0
  4449.7     .05       0  4929.4     .12       0  4999.7     .07       0
  5005.7     .12       0  5037.3      .1       0  5432.1     .05       0
Bank Sta=4908.5,5065
XS Rating Curve= 0 ,0
Exp/Cntr=0.3,0.1

Type RM Length L Ch R = 1 ,31922   ,551,551,551
BEGIN DESCRIPTION:
SANDY HOLLOW CREEK 52.0
END DESCRIPTION:
XS GIS Cut Line= 3
       2330787.2     13176578.36      2331231.63     13175981.15
      2331481.62     13175543.67
#Sta/Elev= 30
    4400  112.37  4437.9  112.16  4444.1  111.59  4473.3  111.44  4540.5  109.57
  4630.4  107.93  4661.7   107.1    4734  106.38    4888  105.18  4894.6  104.07
  4909.2  103.41  4937.9  103.44  4959.3  104.53  4980.1  102.38  4983.5  100.75
  4994.7   95.12    4998   94.36  5000.7   93.86    5004   94.36  5015.6  102.22
    5024  103.31    5051  102.64    5104   103.1  5160.9  103.47  5172.5  102.94
  5204.1  103.97  5276.1  107.09  5349.6  109.46  5400.6  109.87  5648.3  111.93
#Mann= 10 ,-1 , 0
    4400     .16       0  4540.5      .1       0  4630.4     .16       0
  4661.7      .1       0    4734     .16       0  4983.5     .12       0
    4998     .07       0    5004     .12       0    5104      .1       0
  5400.6     .05       0
Bank Sta=4894.6,5204.1
XS Rating Curve= 0 ,0
Exp/Cntr=0.3,0.1

Type RM Length L Ch R = 1 ,31371   ,476,476,476
BEGIN DESCRIPTION:
SANDY HOLLOW CREEK 51.0
END DESCRIPTION:
XS GIS Cut Line= 3
      2331113.59     13176647.81      2331453.86     13176342.26
      2331696.93     13175765.83
#Sta/Elev= 30
  4421.6  110.66  4459.1  110.87  4550.6  110.63  4658.7   108.4  4750.6  104.47
  4821.6  102.69  4835.8  100.93  4895.6  101.41  4929.4   99.76  4954.3  100.03
  4960.8  101.49  4971.6  102.24    4978  101.09  4983.4   98.52  4993.3   96.98
  5004.1   93.55  5006.9   93.05  5010.1   93.55    5015  102.07  5047.6  101.62
  5069.9  102.34  5078.3  103.22  5145.3  107.13  5154.9  107.44  5160.3  106.06
    5167  105.37  5189.5   107.6  5268.3  109.55  5318.9  110.47  5504.5  110.92
#Mann= 8 ,-1 , 0
  4421.6      .1       0  4459.1     .16       0  4550.6      .1       0
  4929.4     .12       0  5004.1     .07       0  5010.1     .12       0
  5069.9      .1       0  5268.3     .05       0
Bank Sta=4821.6,5078.3
XS Rating Curve= 0 ,0
Exp/Cntr=0.3,0.1

Type RM Length L Ch R = 1 ,30895   ,493,493,493
BEGIN DESCRIPTION:
SANDY HOLLOW CREEK 50.0
END DESCRIPTION:
XS GIS Cut Line= 3
      2331794.14     13176807.52      2331919.13      13176488.1
      2331995.35     13176030.81
#Sta/Elev= 30
  4590.9  110.33  4616.4  109.43  4623.8  109.99  4670.7   108.7  4677.5  108.16
  4708.9  107.74  4741.9  107.12  4749.5  106.34  4773.2  106.36  4784.9  105.46
  4803.8  104.85  4809.1  105.18  4827.9  104.67  4893.3  101.07    4903  100.27
  4924.5   99.66  4952.4     100  4985.9   98.74    4993      92  4995.7    91.5
    4999      92  5006.1   93.04  5013.9  100.51  5036.5   99.67  5046.7   99.74
  5074.7  101.59  5092.3  102.61  5208.9  108.11  5291.7  109.02  5397.5  109.24
#Mann= 8 ,-1 , 0
  4590.9     .16       0  4708.9      .1       0  4773.2     .16       0
  4952.4      .1       0    4993     .07       0    4999      .1       0
  5092.3     .16       0  5291.7     .05       0
Bank Sta=4893.3,5074.7
XS Rating Curve= 0 ,0
Exp/Cntr=0.3,0.1

Type RM Length L Ch R = 1 ,30402   ,479,479,479
BEGIN DESCRIPTION:
SANDY HOLLOW CREEK 49.0
END DESCRIPTION:
XS GIS Cut Line= 3
      2332370.52     13176849.22      2332412.19     13176349.21
      2332335.99     13176141.38
#Sta/Elev= 30
  4716.1  109.22  4768.6  109.37  4828.9  108.39  4858.5  107.21  4866.1  106.17
    4869  105.65  4899.1  104.52  4924.6  102.17  4949.3  100.12  4959.3   99.53
  4969.3   98.08  4983.9   97.88  4989.4   95.83  4996.4   92.26  4999.2   91.76
  5002.4   92.26  5009.5   92.97  5023.6   95.68  5029.5    97.1  5049.3   97.54
  5079.7   98.55  5099.3   98.18  5104.3   98.64  5139.9   98.78    5160   99.75
  5197.3   99.63  5210.2    99.7    5231   99.83  5328.3  103.79  5439.2  105.61
#Mann= 9 ,-1 , 0
  4716.1     .16       0  4866.1      .1       0  4924.6     .16       0
  4996.4     .07       0  5002.4     .16       0  5023.6      .1       0
  5049.3     .16       0  5197.3      .1       0  5328.3     .05       0
Bank Sta=4949.3,5210.2
XS Rating Curve= 0 ,0
Exp/Cntr=0.3,0.1

Type RM Length L Ch R = 1 ,29923   ,372,372,372
BEGIN DESCRIPTION:
SANDY HOLLOW CREEK 48.0
END DESCRIPTION:
XS GIS Cut Line= 3
      2332814.97     13176731.19      2332821.91     13176501.98
      2332669.14       13175877.
#Sta/Elev= 30
  4618.3  108.26  4672.7  107.88  4692.7  106.09  4702.7  107.19  4729.4  107.29
  4782.7  105.99  4792.7  104.66  4818.7  103.71  4863.2   101.4  4894.1    98.9
  4965.8   97.23  4976.4   95.69  4986.7   91.82    4994   90.65  4996.8   90.15
    5000   90.65  5007.3   91.56  5017.7   97.27  5054.2   96.45  5079.4   96.67
  5089.7   97.39  5095.9    98.6  5110.3   99.15  5151.4   97.19  5161.7   99.14
  5327.9   102.3  5377.9  104.85  5392.5  104.94  5398.5  105.87    5491  107.03
#Mann= 6 ,-1 , 0
  4618.3      .1       0  4729.4     .16       0  4818.7      .1       0
    4994     .07       0    5000      .1       0  5327.9     .05       0
Bank Sta=4894.1,5161.7
XS Rating Curve= 0 ,0
Exp/Cntr=0.3,0.1

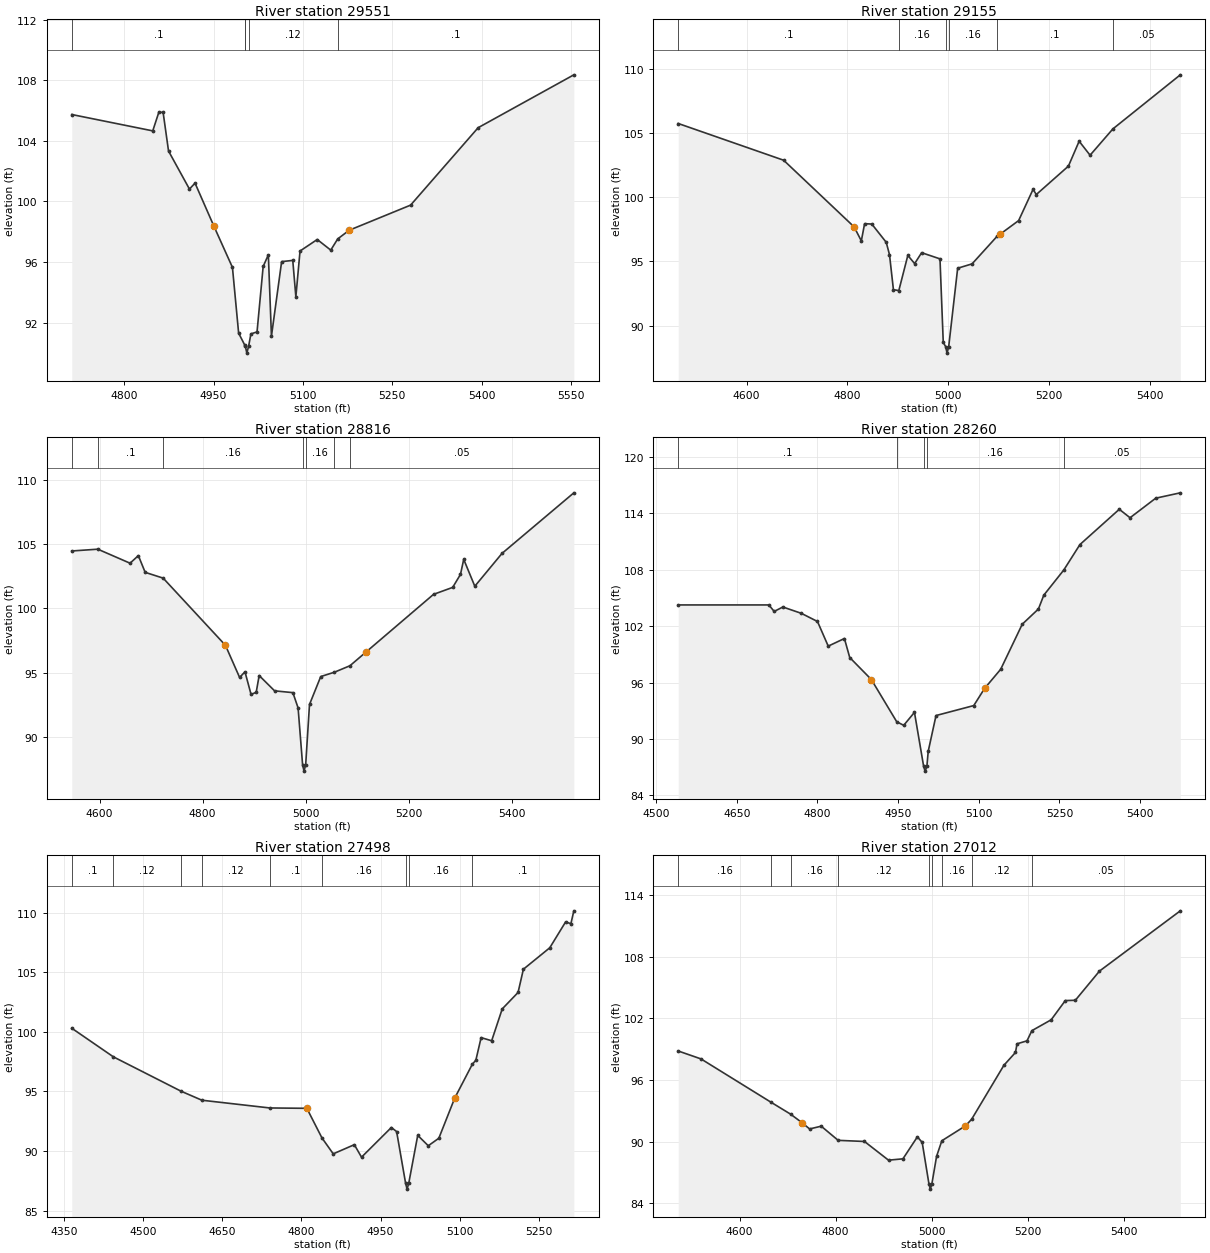
Type RM Length L Ch R = 1 ,29551   ,396,396,396
BEGIN DESCRIPTION:
SANDY HOLLOW CREEK 47.0
END DESCRIPTION:
XS GIS Cut Line= 3
       2333099.7     13176529.72      2333134.41     13176370.04
      2332967.93     13175711.06
#Sta/Elev= 30
  4711.9  105.74  4847.9  104.66  4858.1  105.89  4865.3  105.88  4874.4  103.33
  4909.5  100.82  4918.9  101.21  4950.8   98.35  4981.7   95.65  4992.1   91.31
  5002.5   90.51  5003.1   90.49  5005.9   89.99  5009.1   90.49  5012.7   91.26
    5023   91.39  5033.3   95.71    5042   96.48  5047.2   91.11  5064.3   96.03
    5083   96.11  5088.2   93.71  5095.2   96.73  5124.1   97.49  5146.8   96.79
  5158.5   97.53  5177.7    98.1  5280.9   99.76  5394.3  104.87    5555  108.36
#Mann= 5 ,-1 , 0
  4711.9      .1       0  5002.5     .12       0  5003.1     .07       0
  5009.1     .12       0  5158.5      .1       0
Bank Sta=4950.8,5177.7
XS Rating Curve= 0 ,0
Exp/Cntr=0.3,0.1

Type RM Length L Ch R = 1 ,29155   ,339,339,339
BEGIN DESCRIPTION:
SANDY HOLLOW CREEK 46.0
END DESCRIPTION:
XS GIS Cut Line= 3
      2333620.53     13176432.56      2333516.36     13176133.93
      2333078.84     13175613.08
#Sta/Elev= 30
  4464.4  105.73  4673.6  102.87  4813.5   97.68  4827.8   96.59  4834.3   97.93
  4848.6    97.9  4877.2   96.48  4883.7   95.52  4891.5   92.79  4902.2   92.72
  4920.1   95.46  4933.6   94.82  4947.5   95.67  4983.9   95.19  4990.4   88.69
  4995.2   88.35  4997.9   87.85  5001.2   88.35    5019   94.46  5047.6    94.8
  5097.8   96.97  5103.6   97.12    5140   98.17  5168.6   100.6  5175.1   100.2
  5238.8  102.41  5260.1  104.35  5281.8  103.26  5327.1  105.31  5460.9  109.52
#Mann= 6 ,-1 , 0
  4464.4      .1       0  4902.2     .16       0  4995.2     .07       0
  5001.2     .16       0  5097.8      .1       0  5327.1     .05       0
Bank Sta=4813.5,5103.6
XS Rating Curve= 0 ,0
Exp/Cntr=0.3,0.1

Type RM Length L Ch R = 1 ,28816   ,556,556,556
BEGIN DESCRIPTION:
SANDY HOLLOW CREEK 45.0
END DESCRIPTION:
XS GIS Cut Line= 3
      2333856.61     13176161.67      2333578.86     13175654.76
       2333238.6     13175453.39
#Sta/Elev= 30
  4546.2  104.46  4596.7   104.6  4659.2  103.51  4675.3   104.1  4688.5   102.8
  4723.4  102.35  4844.1   97.13  4871.6   94.63    4882   95.07  4893.8   93.31
  4903.8   93.48  4909.5   94.78  4939.4   93.59  4974.9   93.45    4985   92.26
  4993.7   87.85  4996.5   87.35  4999.7   87.85  5007.1   92.53  5028.9    94.7
  5055.5   95.04  5085.5   95.54  5116.2   96.59  5247.6  101.09  5284.7  101.63
  5299.8  102.64  5306.1  103.81  5327.6  101.72  5380.3  104.27  5519.6  108.98
#Mann= 7 ,-1 , 0
  4546.2     .16       0  4596.7      .1       0  4723.4     .16       0
  4993.7     .07       0  4999.7     .16       0  5055.5      .1       0
  5085.5     .05       0
Bank Sta=4844.1,5116.2
XS Rating Curve= 0 ,0
Exp/Cntr=0.3,0.1

Type RM Length L Ch R = 1 ,28260   ,762,762,762
BEGIN DESCRIPTION:
SANDY HOLLOW CREEK 44.0
END DESCRIPTION:
XS GIS Cut Line= 3
      2334120.52     13175974.23       2334148.3     13175731.15
      2334099.69     13175043.63
#Sta/Elev= 30
    4541  104.26  4709.5  104.26  4719.5  103.57  4735.6  104.04  4769.9  103.37
    4800   102.5    4820   99.88  4850.1  100.69    4860   98.67  4900.2   96.33
  4947.4   91.84  4960.4   91.46  4980.4   92.84  4997.5   87.09  5000.2   86.59
  5003.5   87.09    5006    88.7  5020.5    92.5  5090.7   93.56  5110.8   95.38
  5140.8   97.42  5180.9  102.21    5211  103.83    5221   105.3  5258.1  107.97
  5288.2  110.68  5361.4  114.43  5381.4  113.53  5429.2  115.61  5474.9  116.18
#Mann= 5 ,-1 , 0
    4541      .1       0  4947.4     .16       0  4997.5     .07       0
  5003.5     .16       0  5258.1     .05       0
Bank Sta=4900.2,5110.8
XS Rating Curve= 0 ,0
Exp/Cntr=0.3,0.1

Type RM Length L Ch R = 1 ,27498   ,486,486,486
BEGIN DESCRIPTION:
SANDY HOLLOW CREEK 42.0
END DESCRIPTION:
XS GIS Cut Line= 2
      2334842.75     13176001.94      2334877.44     13175051.27
#Sta/Elev= 30
    4365   100.3  4443.8    97.9  4571.9   95.02  4611.5   94.26  4740.2   93.61
  4810.4   93.58    4839    91.1  4860.4   89.76  4900.4   90.53    4914   89.48
  4970.5   91.97  4980.5   91.63  4997.5    87.3  5000.3    86.8  5003.5    87.3
  5020.5   91.31  5040.5   90.44  5060.5   91.07  5090.6   94.44  5124.1   97.29
  5130.6   97.61  5140.6   99.51  5160.6   99.25  5180.6  101.92  5210.6   103.3
  5220.7  105.25  5270.7  107.05  5300.7  109.22  5310.7  109.07  5316.3  110.15
#Mann= 9 ,-1 , 0
    4365      .1       0  4443.8     .12       0  4571.9     .16       0
  4611.5     .12       0  4740.2      .1       0    4839     .16       0
  4997.5     .07       0  5003.5     .16       0  5124.1      .1       0
Bank Sta=4810.4,5090.6
XS Rating Curve= 0 ,0
Exp/Cntr=0.3,0.1

Type RM Length L Ch R = 1 ,27012   ,410,410,410
BEGIN DESCRIPTION:
SANDY HOLLOW CREEK 41.0
END DESCRIPTION:
XS GIS Cut Line= 3
      2335363.58     13175974.23       2335335.8     13175272.82
      2335134.39     13174995.01
#Sta/Elev= 30
  4472.3   98.82  4519.7   98.05  4665.8   93.82  4706.2   92.67  4729.9   91.84
  4745.8   91.23  4769.9    91.5  4805.2   90.12    4860   90.01    4910   88.19
    4940   88.32  4970.1   90.46  4980.1   89.92  4994.2   85.87    4997   85.37
  5000.2   85.87  5010.1   88.57    5021   90.08  5070.1   91.53    5083   92.17
  5150.2   97.43  5174.3   98.68  5177.5   99.52  5198.3   99.81  5208.4   100.8
  5248.6  101.86    5278  103.73  5298.9  103.76  5349.1   106.6  5517.4  112.47
#Mann= 9 ,-1 , 0
  4472.3     .16       0  4665.8     .12       0  4706.2     .16       0
  4805.2     .12       0  4994.2     .07       0  5000.2     .12       0
    5021     .16       0    5083     .12       0  5208.4     .05       0
Bank Sta=4729.9,5070.1
XS Rating Curve= 0 ,0
Exp/Cntr=0.3,0.1

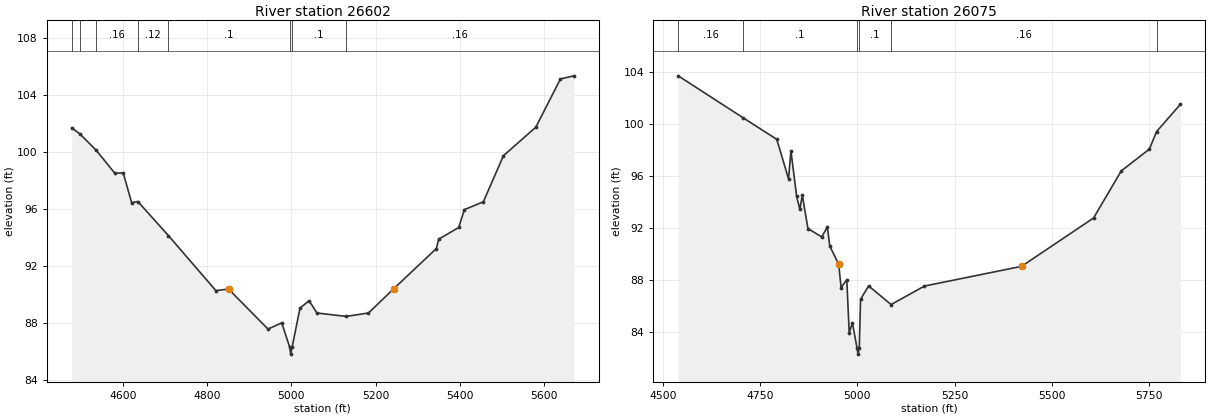
Type RM Length L Ch R = 1 ,26602   ,527,527,527
BEGIN DESCRIPTION:
SANDY HOLLOW CREEK 40.0
END DESCRIPTION:
XS GIS Cut Line= 3
      2335787.19     13176008.97      2335787.19     13175592.26
      2335488.58       13174877.
#Sta/Elev= 30
  4478.7  101.71    4498  101.28  4536.7  100.13  4580.8   98.52  4600.8   98.54
  4620.8   96.45  4635.6   96.53    4708   94.14  4820.8   90.27  4850.8   90.38
  4944.6   87.57  4977.1   88.01  4995.8   86.31  4998.5   85.81  5001.8   86.31
  5020.5   89.05  5042.2   89.56  5060.6    88.7  5130.1   88.46    5183    88.7
  5243.5   90.42  5344.2   93.23  5349.6   93.88  5397.3   94.71  5410.6   95.96
  5455.7   96.51  5503.4   99.75  5580.2  101.75  5638.7  105.14  5670.5  105.36
#Mann= 8 ,-1 , 0
  4478.7     .16       0    4498      .1       0  4536.7     .16       0
  4635.6     .12       0    4708      .1       0  4995.8     .07       0
  5001.8      .1       0  5130.1     .16       0
Bank Sta=4850.8,5243.5
XS Rating Curve= 0 ,0
Exp/Cntr=0.3,0.1

Type RM Length L Ch R = 1 ,26075   ,407,407,407
BEGIN DESCRIPTION:
SANDY HOLLOW CREEK 39.0
END DESCRIPTION:
XS GIS Cut Line= 3
      2336342.75     13175758.94      2336314.97     13175495.04
      2335696.88     13174675.56
#Sta/Elev= 30
    4539  103.68  4706.6  100.45  4792.5   98.81  4822.8   95.78    4829   97.92
  4843.6   94.44  4851.9   93.45  4858.2   94.53  4872.7   91.97  4908.1   91.33
  4922.7   92.08    4929   90.62  4951.8   89.24  4958.1   87.44  4972.7   88.05
  4978.9   83.98  4987.2   84.74  4998.8   82.84  5001.6   82.34  5004.8   82.84
  5008.1   86.55  5028.9   87.57  5086.7   86.14  5172.5   87.56  5422.3   89.07
  5607.6   92.78  5678.9   96.39  5751.2   98.06  5769.9   99.41  5830.8  101.49
#Mann= 6 ,-1 , 0
    4539     .16       0  4706.6      .1       0  4998.8     .07       0
  5004.8      .1       0  5086.7     .16       0  5769.9     .05       0
Bank Sta=4951.8,5422.3
XS Rating Curve= 0 ,0
Exp/Cntr=0.3,0.1