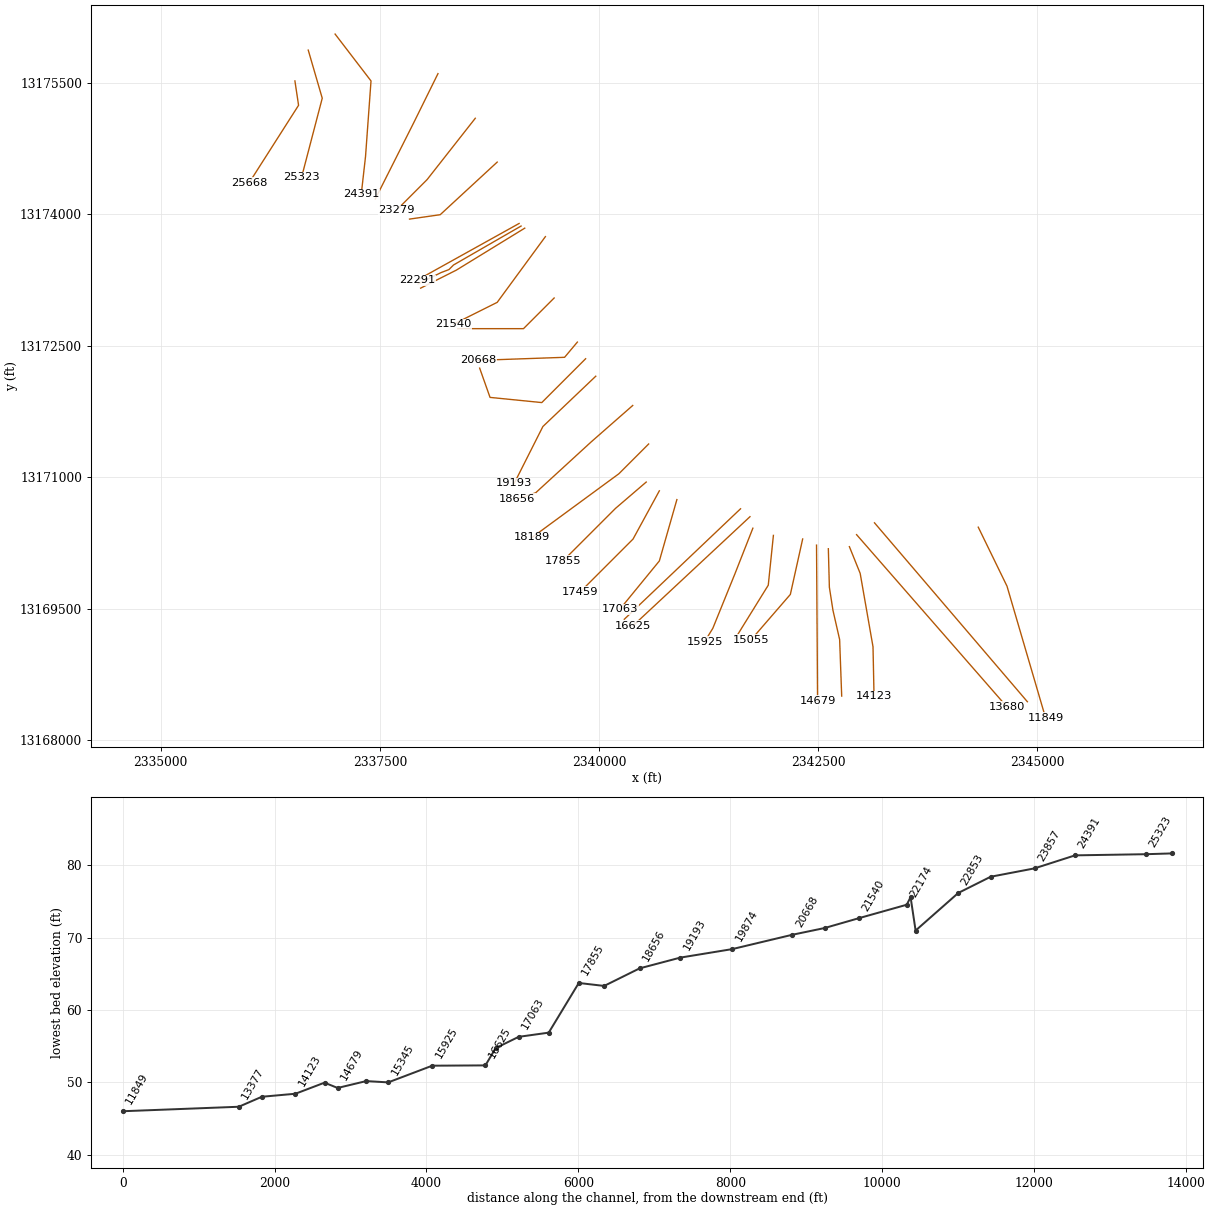
HEC-RAS study SANDY HOLLOW CREEK.prj: SANDY HOLLOW CREEK Base Level Engineering

--- SANDY HOLLOW CREEK.g01 (geometry) --- (continued)

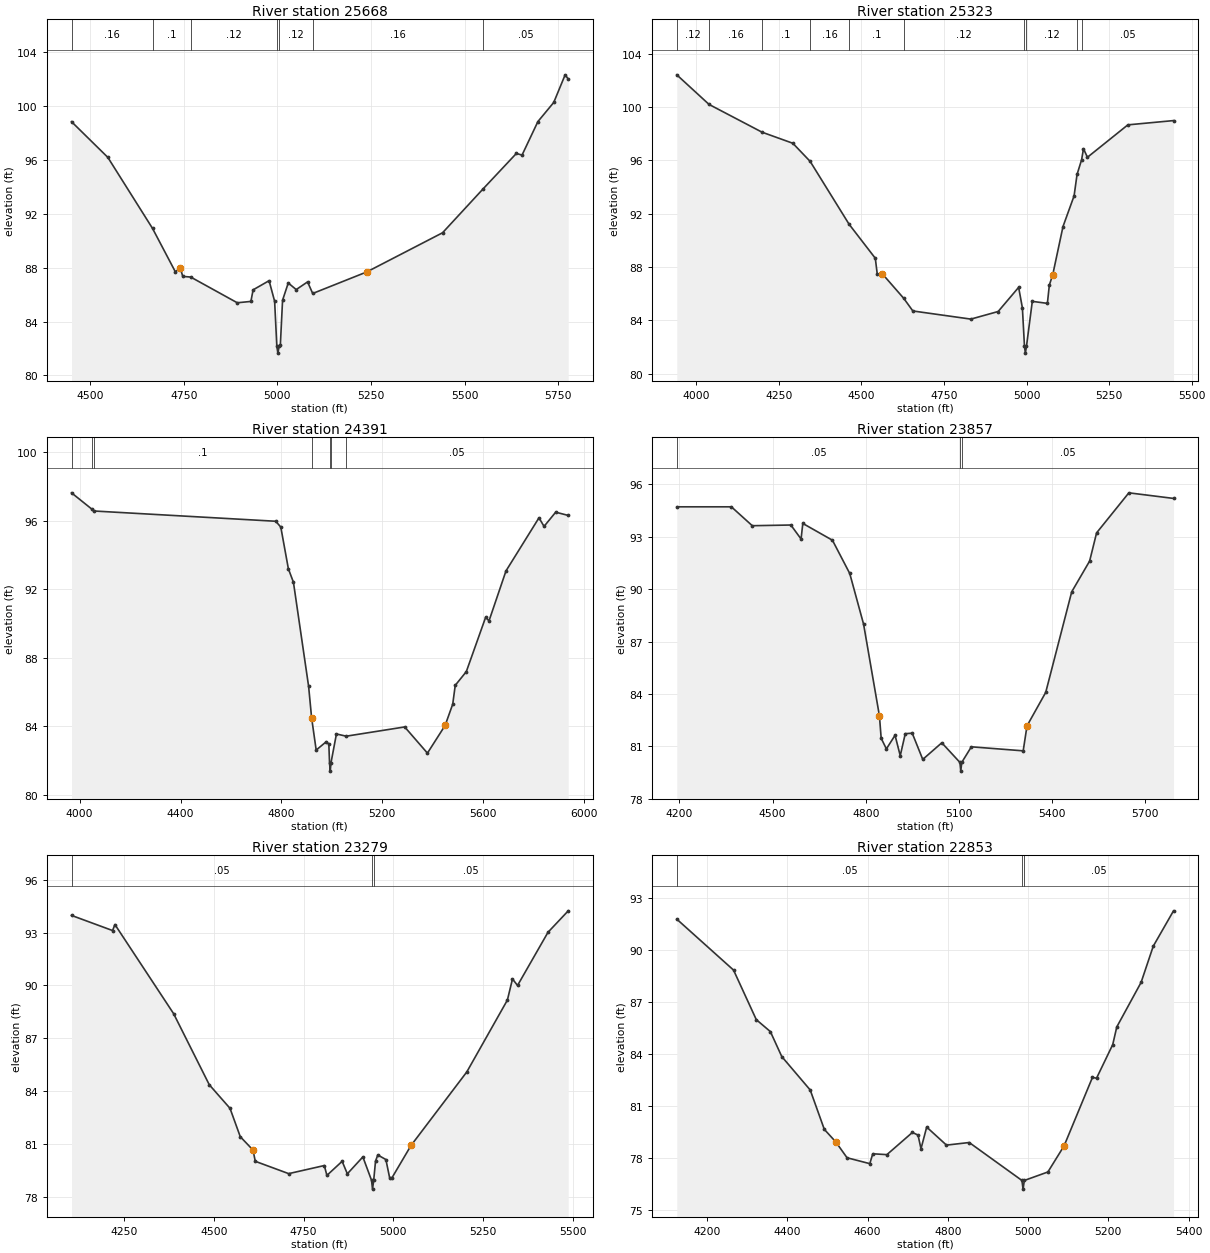
Type RM Length L Ch R = 1 ,25668   ,345,345,345
BEGIN DESCRIPTION:
SANDY HOLLOW CREEK 38.0
END DESCRIPTION:
XS GIS Cut Line= 3
      2336530.25     13175522.79      2336571.91     13175245.04
      2336009.42     13174363.11
#Sta/Elev= 30
  4450.2   98.85  4547.2    96.2  4666.7   90.92  4727.6    87.7  4740.8   87.99
  4747.4   87.36  4768.6   87.31    4893    85.4  4929.4    85.5  4935.3   86.36
    4978   87.04  4992.8   85.51  4998.7   82.16  5001.5   81.66  5004.7   82.16
  5008.1   82.28    5014   85.59  5029.2   86.87  5050.4   86.38  5080.8   86.95
  5094.5   86.09  5238.9   87.69  5441.4    90.6  5548.7   93.83  5638.5   96.49
  5653.7   96.37  5696.1   98.86  5738.4  100.28  5768.8  102.33  5777.1  102.02
#Mann= 7 ,-1 , 0
  4450.2     .16       0  4666.7      .1       0  4768.6     .12       0
  4998.7     .07       0  5004.7     .12       0  5094.5     .16       0
  5548.7     .05       0
Bank Sta=4740.8,5238.9
XS Rating Curve= 0 ,0
Exp/Cntr=0.3,0.1

Type RM Length L Ch R = 1 ,25323   ,932,932,932
BEGIN DESCRIPTION:
SANDY HOLLOW CREEK 37.0
END DESCRIPTION:
XS GIS Cut Line= 3
      2336682.24     13175874.38      2336841.97     13175325.77
      2336605.86     13174423.03
#Sta/Elev= 30
  3940.6  102.41  4038.4  100.19  4198.9   98.11  4292.1   97.28  4344.6   95.92
  4462.5   91.21  4541.9   88.66  4547.8   87.47  4562.6   87.51  4628.2   85.65
  4655.6   84.71  4831.3    84.1    4914   84.67    4976   86.48  4987.4   84.94
  4993.7   82.05  4996.4   81.55  4999.7   82.05  5017.4   85.43  5063.1   85.28
    5069   86.65  5079.4   87.44  5110.4   91.04    5144   93.34  5152.9   94.94
  5166.8   96.05  5172.4   96.87  5184.4   96.23  5306.8   98.66  5445.1   98.98
#Mann= 10 ,-1 , 0
  3940.6     .12       0  4038.4     .16       0  4198.9      .1       0
  4344.6     .16       0  4462.5      .1       0  4628.2     .12       0
  4993.7     .07       0  4999.7     .12       0  5152.9     .16       0
  5166.8     .05       0
Bank Sta=4562.6,5079.4
XS Rating Curve= 0 ,0
Exp/Cntr=0.3,0.1

Type RM Length L Ch R = 1 ,24391   ,534,534,534
BEGIN DESCRIPTION:
SANDY HOLLOW CREEK 36.0
END DESCRIPTION:
XS GIS Cut Line= 4
       2336988.6     13176057.51       2337398.3     13175522.82
       2337335.8     13174661.71      2337287.23     13174231.52
#Sta/Elev= 30
  3967.7   97.64  4049.1   96.68  4055.4   96.58  4777.6   95.98  4797.7   95.64
  4827.8    93.2  4847.8   92.42    4908   86.34  4919.9    84.5    4938   82.62
  4978.2   83.11  4988.2   82.97  4990.9   81.89  4993.7   81.39  4996.9   81.89
  5018.3   83.56  5057.2   83.43    5289   83.97  5379.2   82.44  5449.4   84.06
  5479.5    85.3  5489.5    86.4  5533.4    87.2  5610.2   90.38  5623.3   90.16
  5690.7   93.08  5821.5   96.18  5841.7   95.68  5887.8   96.51  5937.6   96.32
#Mann= 7 ,-1 , 0
  3967.7     .16       0  4049.1     .12       0  4055.4      .1       0
  4919.9     .12       0  4990.9     .07       0  4996.9     .12       0
  5057.2     .05       0
Bank Sta=4919.9,5449.4
XS Rating Curve= 0 ,0
Exp/Cntr=0.3,0.1

Type RM Length L Ch R = 1 ,23857   ,578,578,578
BEGIN DESCRIPTION:
SANDY HOLLOW CREEK 35.0
END DESCRIPTION:
XS GIS Cut Line= 3
      2338162.19     13175606.15      2337884.41     13175043.65
      2337446.92     13174175.62
#Sta/Elev= 30
  4191.5    94.7  4367.3    94.7  4434.6   93.62  4558.8   93.66  4591.7   92.86
  4597.3   93.75  4692.7   92.79  4748.4   90.89    4793   87.99    4844   82.75
  4849.6   81.47  4866.4   80.86  4894.3   81.64    4911   80.47  4927.2   81.73
  4949.6   81.76  4983.5   80.26  5044.8   81.21  5103.1   80.09  5105.9   79.59
  5109.1   80.09    5140   80.98  5306.9   80.75  5319.2   82.18  5379.4   84.09
  5463.1   89.84  5520.8    91.6  5543.2   93.21  5647.1    95.5  5790.9   95.18
#Mann= 3 ,-1 , 0
  4191.5     .05       0  5103.1     .03       0  5109.1     .05       0
Bank Sta=4844,5319.2
XS Rating Curve= 0 ,0
Exp/Cntr=0.3,0.1

Type RM Length L Ch R = 1 ,23279   ,426,426,426
BEGIN DESCRIPTION:
SANDY HOLLOW CREEK 34.0
END DESCRIPTION:
XS GIS Cut Line= 3
      2338587.75     13175096.89      2338037.72     13174396.85
      2337687.75     13174046.88
#Sta/Elev= 30
  4102.7   93.98  4217.2   93.12  4223.8   93.46  4387.4    88.4  4486.9   84.36
  4544.7   83.02  4573.3   81.41  4608.8   80.65  4615.2   80.01  4708.3   79.31
  4807.7   79.77  4814.9   79.21  4857.4   80.01  4871.9    79.3  4915.2   80.26
  4939.4   78.93  4942.1   78.43  4945.4   78.93  4950.5   80.02  4956.8   80.37
  4979.4   80.11  4989.8   79.08  4996.5   79.08  5049.5   80.91  5205.1   85.09
  5318.2   89.17  5332.4   90.37  5346.5      90  5431.4   93.02  5487.9   94.24
#Mann= 3 ,-1 , 0
  4102.7     .05       0  4939.4    .035       0  4945.4     .05       0
Bank Sta=4608.8,5049.5
XS Rating Curve= 0 ,0
Exp/Cntr=0.3,0.1

Type RM Length L Ch R = 1 ,22853   ,562,562,562
BEGIN DESCRIPTION:
SANDY HOLLOW CREEK 33.0
END DESCRIPTION:
XS GIS Cut Line= 3
      2338837.72     13174596.85      2338187.72     13173996.85
      2337837.76     13173946.86
#Sta/Elev= 30
  4124.4   91.77  4265.9   88.83  4322.6   85.97  4357.7   85.28  4386.1   83.84
    4457   81.91  4492.1   79.64  4520.5   78.92  4548.8      78  4605.5   77.66
  4612.9   78.23  4648.1   78.18  4711.6   79.46  4725.7   79.31  4733.1   78.52
  4747.3   79.77  4796.6   78.73  4853.3   78.88  4984.7   76.69  4987.5   76.19
  4990.7   76.69  5049.4   77.18  5089.8   78.69  5160.5   82.64  5170.6   82.59
    5211   84.53  5221.1   85.55  5281.7   88.12    5312   90.21  5362.5   92.25
#Mann= 3 ,-1 , 0
  4124.4     .05       0  4984.7    .035       0  4990.7     .05       0
Bank Sta=4520.5,5089.8
XS Rating Curve= 0 ,0
Exp/Cntr=0.3,0.1

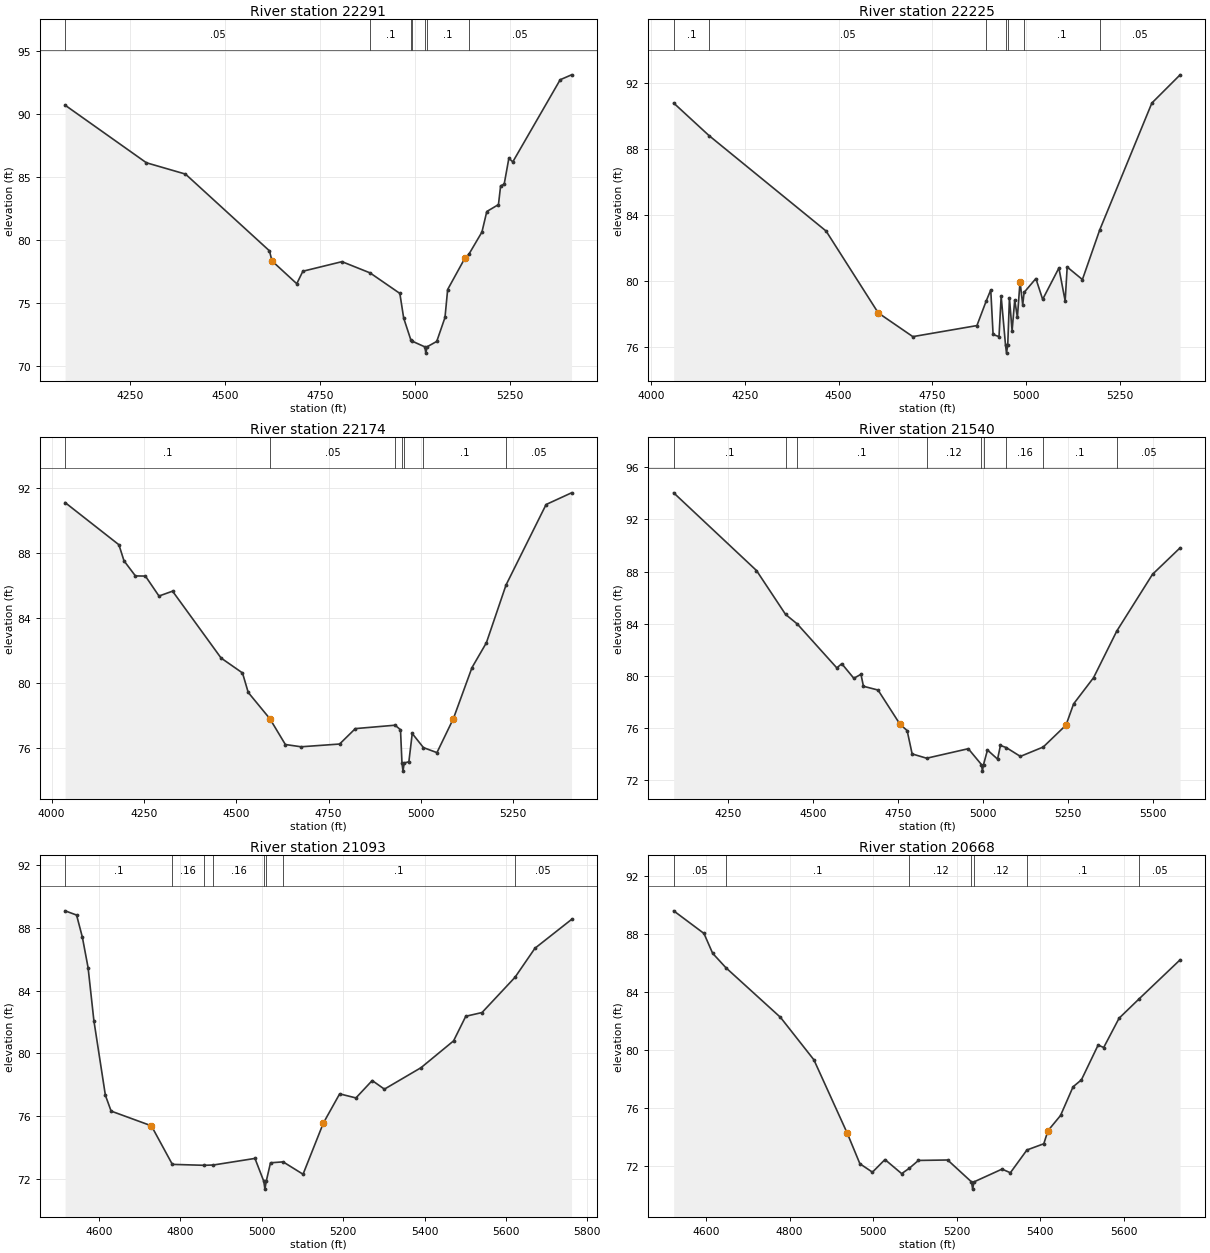
Type RM Length L Ch R = 1 ,22291   ,66,66,66
BEGIN DESCRIPTION:
SANDY HOLLOW CREEK 32.0
END DESCRIPTION:
XS GIS Cut Line= 2
      2339087.68     13173896.83      2337922.77     13173249.47
#Sta/Elev= 30
  4078.6   90.67  4292.5    86.1  4395.4    85.2  4616.3   79.11    4623   78.31
  4688.2    76.5  4704.3   77.49  4807.2   78.25    4881   77.36  4959.5   75.73
  4969.6   73.77  4988.3   72.05  4991.1   71.95  5025.1   71.49  5027.9   70.99
  5031.1   71.49  5056.6   71.92  5078.3   73.82  5085.3   76.04  5131.1   78.55
    5141   78.83  5175.5    80.6  5188.3   82.23    5219   82.78  5224.7   84.27
    5234   84.39  5246.4   86.46  5256.7   86.17  5381.4   92.69  5411.3   93.08
#Mann= 7 ,-1 , 0
  4078.6     .05       0    4881      .1       0  4988.3     .12       0
  4991.1      .1       0  5025.1     .07       0  5031.1      .1       0
    5141     .05       0
Bank Sta=4623,5131.1
XS Rating Curve= 0 ,0
Exp/Cntr=0.3,0.1

Type RM Length L Ch R = 1 ,22225   ,51,51,51
BEGIN DESCRIPTION:
Mapping XS d3b79444
END DESCRIPTION:
XS GIS Cut Line= 5
      2339110.27     13173867.52      2338339.47      13173423.1
      2338287.39     13173371.02      2338197.11      13173336.3
       2337936.7     13173207.83
#Sta/Elev= 30
  4060.4   90.77  4154.5    88.8  4466.9   83.01  4605.9   78.05  4698.2   76.61
  4869.1   77.28  4894.2   78.79    4906   79.44  4912.2   76.74    4928   76.61
  4933.7   79.06  4945.3   76.11    4948   75.61  4951.3   76.11  4955.8   78.95
  4962.9   76.96  4969.9   78.83    4977   77.78  4984.1   79.95  4991.2   78.53
  4994.9   79.29  5026.3   80.13  5044.4   78.87  5087.7   80.77  5104.4   78.77
  5109.8   80.83  5150.4   80.07  5196.6   83.08  5335.6   90.77  5410.9   92.48
#Mann= 7 ,-1 , 0
  4060.4      .1       0  4154.5     .05       0  4894.2     .12       0
  4945.3     .07       0  4951.3     .12       0  4994.9      .1       0
  5196.6     .05       0
Bank Sta=4605.9,4984.1
XS Rating Curve= 0 ,0
Exp/Cntr=0.3,0.1

Type RM Length L Ch R = 1 ,22174   ,634,634,634
BEGIN DESCRIPTION:
SANDY HOLLOW CREEK 31.0
END DESCRIPTION:
XS GIS Cut Line= 3
      2339151.96     13173843.23      2338370.72     13173364.07
      2337964.43     13173159.19
#Sta/Elev= 30
  4036.5   91.11  4182.2   88.51    4196   87.52  4226.9   86.59    4254   86.58
  4290.7   85.35  4327.5   85.65  4458.9   81.53  4516.9   80.61  4532.4   79.41
    4591   77.79    4633    76.2  4675.6   76.06  4779.9   76.23  4822.5   77.18
  4930.2   77.39  4944.8   77.11  4948.8   75.06  4951.6   74.56  4954.8   75.06
  4967.5   75.14  4976.6   76.88  5006.9   76.01  5043.5    75.7  5088.1    77.8
  5138.4   80.94  5177.4   82.47  5230.6   86.03  5339.1   90.99    5408   91.71
#Mann= 7 ,-1 , 0
  4036.5      .1       0    4591     .05       0  4930.2     .12       0
  4948.8     .07       0  4954.8     .12       0  5006.9      .1       0
  5230.6     .05       0
Bank Sta=4591,5088.1
XS Rating Curve= 0 ,0
Exp/Cntr=0.3,0.1

Type RM Length L Ch R = 1 ,21540   ,447,447,447
BEGIN DESCRIPTION:
SANDY HOLLOW CREEK 30.0
END DESCRIPTION:
XS GIS Cut Line= 3
      2339387.71     13173746.84      2338837.72     13172996.85
      2338337.68     13172746.83
#Sta/Elev= 30
    4090   94.04  4333.5   88.08  4419.1   84.71  4453.4   83.98  4569.7   80.61
  4584.3   80.93  4619.8   79.81  4640.7   80.12    4648    79.2  4690.9   78.91
  4755.7   76.28  4776.5    75.8  4791.2   74.01  4833.9   73.68  4956.3   74.41
  4995.1   73.19  4997.8   72.69  5001.1   73.19  5012.7   74.31  5042.4   73.61
  5050.8   74.66  5067.7    74.5  5109.5   73.82  5176.7   74.54  5243.6   76.22
    5266   77.85  5324.7   79.86    5393   83.44    5498   87.79  5579.1   89.82
#Mann= 9 ,-1 , 0
    4090      .1       0  4419.1     .05       0  4453.4      .1       0
  4833.9     .12       0  4995.1     .07       0  5001.1     .12       0
  5067.7     .16       0  5176.7      .1       0    5393     .05       0
Bank Sta=4755.7,5243.6
XS Rating Curve= 0 ,0
Exp/Cntr=0.3,0.1

Type RM Length L Ch R = 1 ,21093   ,425,425,425
BEGIN DESCRIPTION:
SANDY HOLLOW CREEK 29.0
END DESCRIPTION:
XS GIS Cut Line= 3
      2339487.69     13173046.83      2339137.72     13172696.85
      2338387.76     13172696.85
#Sta/Elev= 30
  4516.4    89.1  4544.6   88.83  4558.8   87.42  4572.9   85.47  4587.1    82.1
  4615.4   77.33  4629.5   76.32  4728.5   75.38    4780   72.92  4858.1   72.86
    4881   72.88  4983.1    73.3  5004.8   71.84  5007.6   71.34  5010.8   71.84
  5021.3   73.02  5052.3   73.08  5101.3   72.29  5151.3   75.56  5191.3   77.42
  5231.3   77.16  5271.3   78.27  5301.3   77.72  5391.3   79.09  5471.3    80.8
  5501.3   82.37  5541.3   82.61  5622.4   84.86  5671.3   86.71  5761.3   88.55
#Mann= 8 ,-1 , 0
  4516.4      .1       0    4780     .16       0  4858.1     .12       0
    4881     .16       0  5004.8     .07       0  5010.8     .16       0
  5052.3      .1       0  5622.4     .05       0
Bank Sta=4728.5,5151.3
XS Rating Curve= 0 ,0
Exp/Cntr=0.3,0.1

Type RM Length L Ch R = 1 ,20668   ,794,794,794
BEGIN DESCRIPTION:
SANDY HOLLOW CREEK 28.0
END DESCRIPTION:
XS GIS Cut Line= 3
      2339752.46     13172543.64      2339606.63     13172370.04
      2338621.67     13172335.36
#Sta/Elev= 30
  4522.7   89.61  4595.2   88.05    4616   86.68  4647.9   85.68  4778.4   82.26
  4858.4   79.33  4938.5   74.25  4968.5   72.16  4998.5   71.58  5028.5   72.45
  5068.5   71.48  5086.8   71.85  5108.6   72.39  5178.6   72.42  5235.6   70.91
  5238.4   70.41  5241.6   70.91  5308.7   71.79  5328.7   71.54  5368.3   73.11
  5408.7   73.54  5418.7   74.44  5448.8   75.49  5478.8   77.47  5498.8   77.95
  5538.8   80.35  5552.1   80.18  5588.9    82.2    5637   83.54    5735   86.23
#Mann= 7 ,-1 , 0
  4522.7     .05       0  4647.9      .1       0  5086.8     .12       0
  5235.6     .07       0  5241.6     .12       0  5368.3      .1       0
    5637     .05       0
Bank Sta=4938.5,5418.7
XS Rating Curve= 0 ,0
Exp/Cntr=0.3,0.1

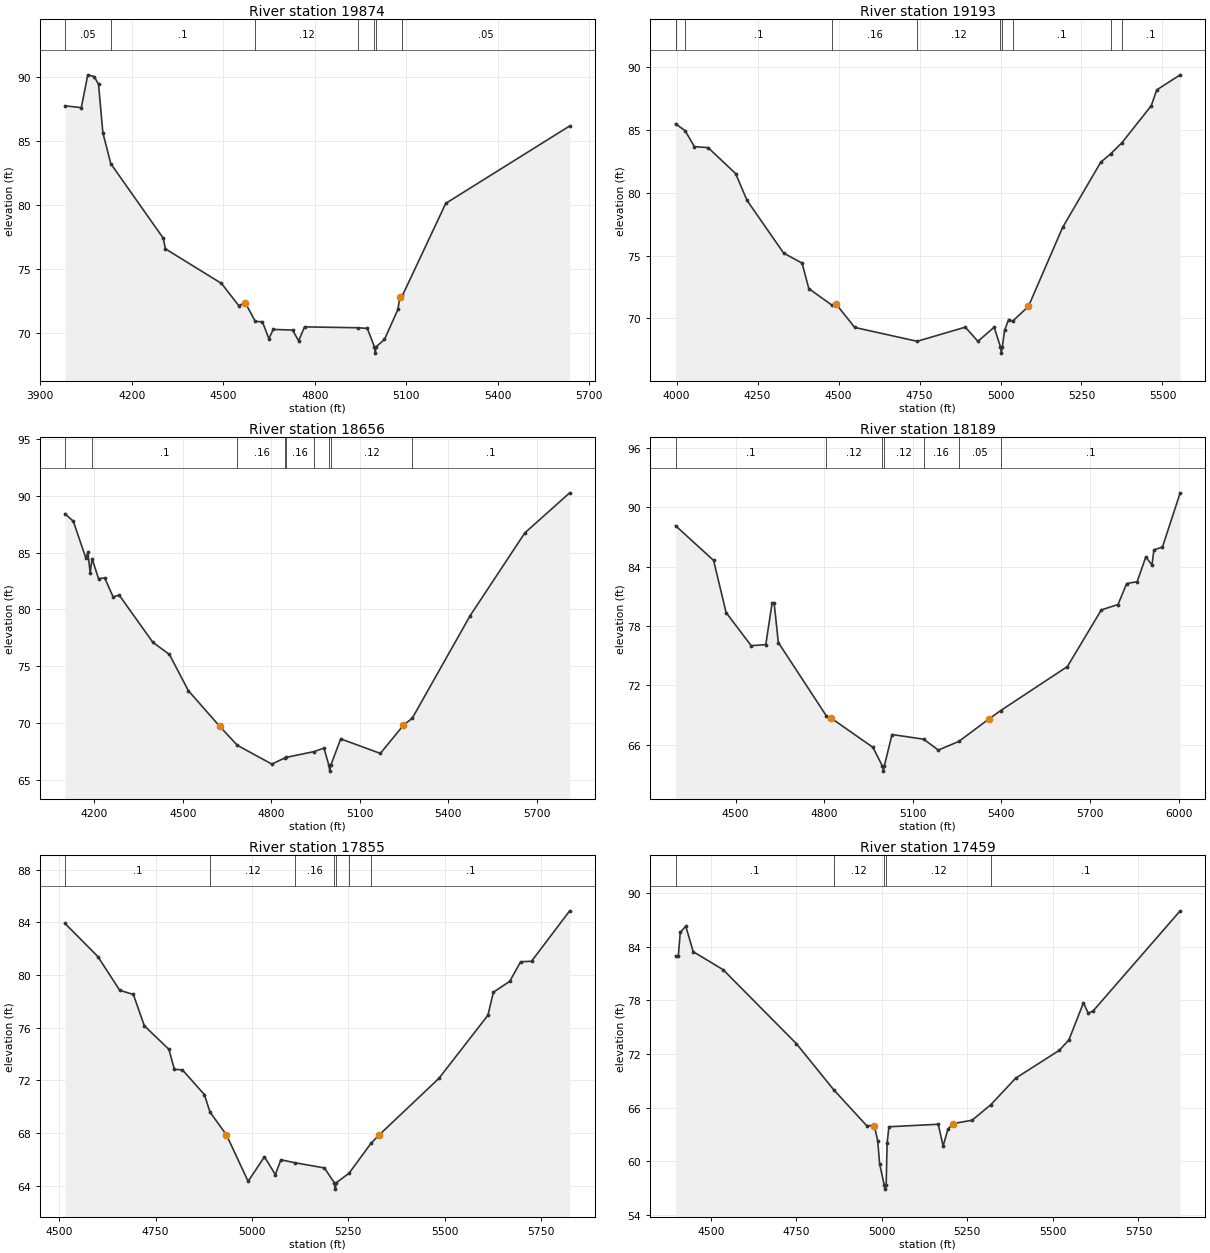
Type RM Length L Ch R = 1 ,19874   ,681,681,681
BEGIN DESCRIPTION:
SANDY HOLLOW CREEK 27.0
END DESCRIPTION:
XS GIS Cut Line= 4
       2339846.4     13172353.64      2339346.42     13171853.66
      2338756.14     13171912.68      2338637.73     13172246.83
#Sta/Elev= 30
  3981.1   87.72  4034.5   87.58  4055.7   90.14  4076.9      90    4091    89.4
  4105.2   85.62  4131.1   83.21  4303.2   77.39  4310.2   76.56  4494.1   73.86
  4550.6   72.13  4571.9   72.36  4605.1   70.89  4628.4   70.87  4649.6   69.54
  4663.8   70.27  4727.1   70.22  4747.2   69.38  4766.4   70.47  4941.3    70.4
  4972.4   70.35  4995.4   68.92  4998.2   68.42  5001.4   68.92  5028.6   69.49
  5072.9   71.84  5078.8   72.82  5087.6   72.92  5229.6   80.11  5635.9   86.15
#Mann= 7 ,-1 , 0
  3981.1     .05       0  4131.1      .1       0  4605.1     .12       0
  4941.3      .1       0  4995.4     .07       0  5001.4      .1       0
  5087.6     .05       0
Bank Sta=4571.9,5078.8
XS Rating Curve= 0 ,0
Exp/Cntr=0.3,0.1

Type RM Length L Ch R = 1 ,19193   ,537,537,537
BEGIN DESCRIPTION:
SANDY HOLLOW CREEK 26.0
END DESCRIPTION:
XS GIS Cut Line= 3
      2339962.25     13172154.33      2339358.98     13171580.34
      2339032.29     13170932.79
#Sta/Elev= 30
  3996.7   85.46  4026.2   84.92  4054.8   83.65  4097.3   83.57  4182.2   81.51
  4217.4   79.38  4330.6   75.19  4387.3    74.4  4408.3   72.37  4480.2   71.05
  4493.3   71.12  4549.9   69.29  4742.5   68.19  4891.3   69.31  4930.3   68.19
  4980.5   69.31  4999.8   67.75  5002.6   67.25  5005.8   67.75  5012.5   69.06
  5025.1   69.92  5037.5   69.79  5086.4   70.97  5191.7   77.23  5309.4   82.41
  5340.8   83.09  5374.9   83.96  5465.5    86.9  5482.2   88.15  5554.7   89.35
#Mann= 9 ,-1 , 0
  3996.7     .05       0  4026.2      .1       0  4480.2     .16       0
  4742.5     .12       0  4999.8     .07       0  5005.8     .12       0
  5037.5      .1       0  5340.8     .05       0  5374.9      .1       0
Bank Sta=4493.3,5086.4
XS Rating Curve= 0 ,0
Exp/Cntr=0.3,0.1

Type RM Length L Ch R = 1 ,18656   ,467,467,467
BEGIN DESCRIPTION:
SANDY HOLLOW CREEK 25.0
END DESCRIPTION:
XS GIS Cut Line= 4
      2340383.96     13171820.46      2339909.55     13171404.63
      2339276.98     13170824.77      2339066.17      13170754.5
#Sta/Elev= 30
  4100.7   88.42  4128.9   87.75  4171.6    84.5  4178.3   85.04  4185.9   83.21
  4192.4   84.46  4214.3   82.71  4235.2   82.77  4263.7    81.1  4284.6   81.25
  4398.5    77.1  4454.7   76.03    4519   72.84  4625.3    69.7  4685.2   68.03
  4801.9   66.38  4848.1   66.95  4848.7   66.96  4945.4   67.48  4978.7   67.79
  4995.6   66.26  4998.3   65.76  5001.6   66.26  5035.5    68.6  5169.9   67.32
  5248.2    69.8  5278.1   70.42  5474.5   79.45  5659.8   86.73  5811.9   90.26
#Mann= 9 ,-1 , 0
  4100.7     .05       0  4192.4      .1       0  4685.2     .16       0
  4848.1     .12       0  4848.7     .16       0  4945.4     .12       0
  4995.6     .07       0  5001.6     .12       0  5278.1      .1       0
Bank Sta=4625.3,5248.2
XS Rating Curve= 0 ,0
Exp/Cntr=0.3,0.1

Type RM Length L Ch R = 1 ,18189   ,334,334,334
BEGIN DESCRIPTION:
SANDY HOLLOW CREEK 24.0
END DESCRIPTION:
XS GIS Cut Line= 3
      2340565.52     13171381.16      2340225.84     13171041.48
      2339235.99      13170315.2
#Sta/Elev= 30
    4297   88.14  4425.8   84.63  4468.2   79.36    4553   76.01  4602.5   76.12
  4623.8   80.31  4630.8   80.31    4645   76.33  4806.7   68.95    4823    68.7
    4965   65.74  4997.5   63.83  5000.3   63.33  5003.5   63.83  5029.8   67.03
  5136.6   66.56  5186.5   65.46  5255.7   66.33    5358   68.61  5397.5   69.45
  5623.3    73.9  5738.3   79.63  5794.7   80.17    5824   82.29  5859.5   82.48
  5888.8   84.99  5909.6   84.16  5916.1   85.69  5945.1   85.98  6005.1   91.46
#Mann= 7 ,-1 , 0
    4297      .1       0  4806.7     .12       0  4997.5     .07       0
  5003.5     .12       0  5136.6     .16       0  5255.7     .05       0
  5397.5      .1       0
Bank Sta=4823,5358
XS Rating Curve= 0 ,0
Exp/Cntr=0.3,0.1

Type RM Length L Ch R = 1 ,17855   ,396,396,396
BEGIN DESCRIPTION:
SANDY HOLLOW CREEK 23.0
END DESCRIPTION:
XS GIS Cut Line= 3
      2340537.72     13170946.86      2340187.72     13170646.85
      2339587.73     13170046.86
#Sta/Elev= 30
  4514.9   83.92    4600   81.41    4657   78.84  4692.2   78.53  4720.7   76.15
  4784.4   74.36  4798.6   72.84  4819.5    72.8  4876.6   70.92  4891.1   69.59
  4933.6   67.87    4990   64.33  5032.4    66.2  5060.7   64.84  5074.9   65.97
  5112.4   65.74    5188   65.35  5213.3   64.24    5216   63.74  5219.3   64.24
    5252   64.95  5309.3   67.24  5329.4   67.84    5485   72.15  5612.3   76.95
  5626.4    78.7  5668.8   79.52  5697.1   81.01  5725.4   81.05  5824.4   84.88
#Mann= 7 ,-1 , 0
  4514.9      .1       0  4891.1     .12       0  5112.4     .16       0
  5213.3     .07       0  5219.3     .16       0    5252     .12       0
  5309.3      .1       0
Bank Sta=4933.6,5329.4
XS Rating Curve= 0 ,0
Exp/Cntr=0.3,0.1

Type RM Length L Ch R = 1 ,17459   ,396,396,396
BEGIN DESCRIPTION:
SANDY HOLLOW CREEK 22.0
END DESCRIPTION:
XS GIS Cut Line= 3
      2340687.72     13170846.86      2340387.72     13170296.85
      2339787.74     13169696.88
#Sta/Elev= 30
    4397   82.99  4405.1   82.97  4410.8    85.6  4426.9    86.3  4448.7   83.45
  4536.1   81.43  4750.1   73.16  4859.4   67.99  4955.6   63.98  4977.9   63.98
  4987.9    62.3  4993.6   59.69  5006.7   57.37  5009.5   56.87  5012.7   57.37
  5015.4   61.99  5020.7   63.85  5164.9   64.13  5179.1   61.69  5193.2   63.58
  5207.3    64.2  5263.9   64.58    5319   66.34  5391.2   69.29  5518.5    72.4
  5546.8   73.58  5589.2   77.72  5603.3   76.57  5617.5   76.81    5872   88.02
#Mann= 5 ,-1 , 0
    4397      .1       0  4859.4     .12       0  5006.7     .07       0
  5012.7     .12       0    5319      .1       0
Bank Sta=4977.9,5207.3
XS Rating Curve= 0 ,0
Exp/Cntr=0.3,0.1

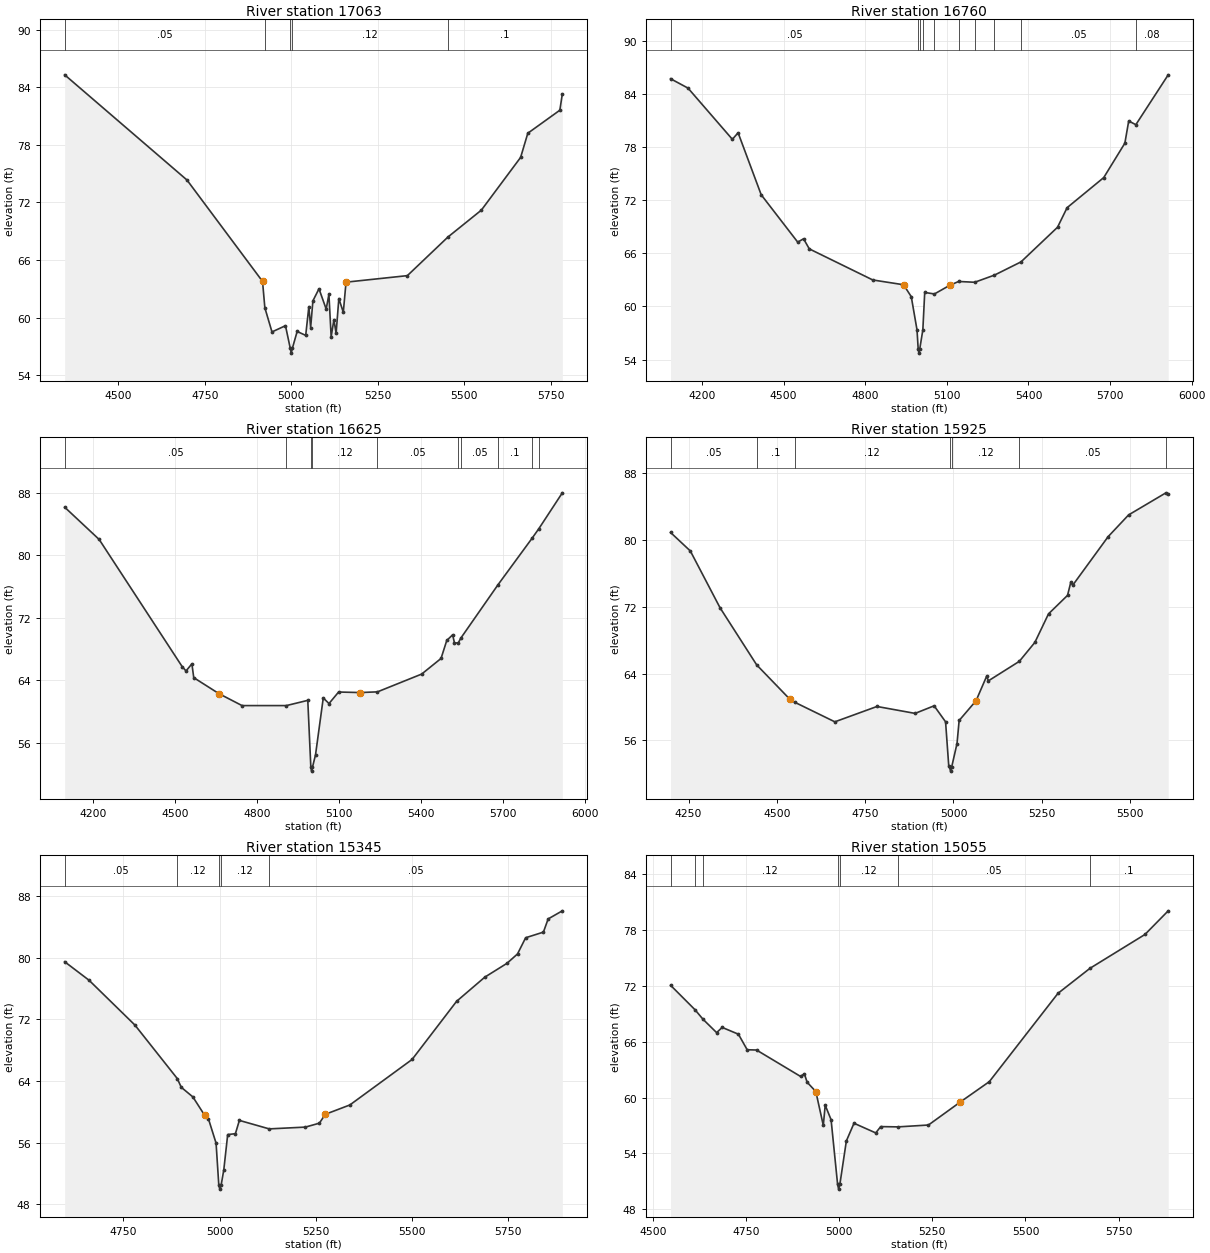
Type RM Length L Ch R = 1 ,17063   ,303,303,303
BEGIN DESCRIPTION:
SANDY HOLLOW CREEK 21.0
END DESCRIPTION:
XS GIS Cut Line= 3
      2340887.72     13170746.86      2340687.72     13170046.85
      2340237.69     13169496.82
#Sta/Elev= 30
  4344.6   85.31  4698.2   74.34  4916.6   63.77  4923.3   61.02  4943.9    58.5
  4982.9   59.15  4996.8   56.79  4999.6   56.29  5002.8   56.79  5016.7   58.55
  5041.4   58.14  5050.5   61.14  5055.7   58.96  5062.2   61.74  5079.8      63
  5100.6   60.88  5108.5   62.42    5115      58  5122.9   59.78  5129.3   58.36
  5137.2   61.98  5150.1   60.55    5158   63.69  5335.3   64.37  5452.7    68.4
  5549.2    71.2  5662.7    76.7  5683.5   79.22  5776.1   81.62  5783.3   83.32
#Mann= 5 ,-1 , 0
  4344.6     .05       0  4923.3     .12       0  4996.8     .07       0
  5002.8     .12       0  5452.7      .1       0
Bank Sta=4916.6,5158
XS Rating Curve= 0 ,0
Exp/Cntr=0.3,0.1

Type RM Length L Ch R = 1 ,16760   ,135,135,135
BEGIN DESCRIPTION:
SANDY HOLLOW CREEK 20.0
END DESCRIPTION:
XS GIS Cut Line= 2
      2341613.78     13170641.85      2340287.64     13169381.67
#Sta/Elev= 30
  4084.4   85.71  4148.6   84.65  4311.6   78.87  4332.7   79.61  4417.6   72.61
  4551.9   67.26  4573.3   67.64  4594.4    66.5  4827.8   62.99    4941   62.45
  4969.3    61.1  4990.4   57.35  4994.6   55.23  4997.4   54.73  5000.6   55.23
  5011.8   57.35  5018.7   61.58  5054.4   61.41  5110.9   62.39  5143.5   62.82
  5202.4   62.73  5275.2   63.54  5372.6   65.03  5506.9   68.94  5542.1   71.15
  5676.8   74.55  5754.4   78.43  5768.6   80.94  5794.8   80.52  5913.8   86.15
#Mann= 10 ,-1 , 0
  4084.4     .05       0  4994.6     .04       0  5000.6     .05       0
  5011.8     .12       0  5054.4     .05       0  5143.5     .12       0
  5202.4     .05       0  5275.2     .12       0  5372.6     .05       0
  5794.8     .08       0
Bank Sta=4941,5110.9
XS Rating Curve= 0 ,0
Exp/Cntr=0.3,0.1

Type RM Length L Ch R = 1 ,16625   ,700,700,700
BEGIN DESCRIPTION:
SANDY HOLLOW CREEK 19.0
END DESCRIPTION:
XS GIS Cut Line= 2
      2341721.42     13170551.58      2340388.09     13169308.52
#Sta/Elev= 30
  4095.5   86.17  4221.9   82.03  4525.8   65.74    4540   65.18  4561.5   66.09
  4568.3   64.32  4660.6   62.27  4745.2   60.74  4907.4   60.74    4986   61.41
  4997.2   52.84  4999.9   52.34  5003.2   52.84  5014.4   54.44  5042.7   61.72
  5063.7      61  5098.9   62.48    5177   62.41  5241.2    62.5  5403.2   64.78
  5474.1   66.78  5495.1   69.09  5516.6   69.81  5523.4   68.76  5537.3   68.78
  5546.6   69.39  5682.8   76.23  5807.8    82.2  5832.5   83.42  5918.4   88.01
#Mann= 10 ,-1 , 0
  4095.5     .05       0  4907.4     .12       0  4997.2     .07       0
  5003.2     .12       0  5241.2     .05       0  5537.3      .1       0
  5546.6     .05       0  5682.8      .1       0  5807.8     .08       0
  5832.5     .05       0
Bank Sta=4660.6,5177
XS Rating Curve= 0 ,0
Exp/Cntr=0.3,0.1

Type RM Length L Ch R = 1 ,15925   ,580,580,580
BEGIN DESCRIPTION:
SANDY HOLLOW CREEK 18.0
END DESCRIPTION:
XS GIS Cut Line= 4
      2341754.54     13170420.58      2341549.55     13169899.34
       2341297.7     13169278.48      2341203.98      13169126.2
#Sta/Elev= 30
    4199   80.91    4255   78.69    4339   71.89  4442.9   65.03  4536.7   60.92
  4550.4   60.56  4664.1   58.21  4783.4   60.05  4891.3   59.22  4945.2   60.13
  4977.6   58.21  4986.5   52.97  4988.9    52.8  4991.7    52.3  4994.9    52.8
    5010   55.61    5016   58.37  5063.9   60.74  5093.7   63.66  5099.1   63.13
  5186.4   65.46  5230.4   67.73    5269   71.15  5322.9   73.37  5332.1   74.94
  5337.5   74.58  5437.7    80.4  5495.7   83.01  5601.4   85.66  5607.9   85.54
#Mann= 7 ,-1 , 0
    4199     .05       0  4442.9      .1       0  4550.4     .12       0
  4988.9     .07       0  4994.9     .12       0  5186.4     .05       0
  5601.4      .1       0
Bank Sta=4536.7,5063.9
XS Rating Curve= 0 ,0
Exp/Cntr=0.3,0.1

Type RM Length L Ch R = 1 ,15345   ,290,290,290
BEGIN DESCRIPTION:
SANDY HOLLOW CREEK 17.0
END DESCRIPTION:
XS GIS Cut Line= 3
      2341988.84      13170338.6      2341930.27     13169770.48
      2341549.57     13169155.51
#Sta/Elev= 30
  4597.2   79.47  4660.6   77.07  4779.9   71.26    4890   64.33  4900.5   63.19
  4930.7   61.94  4960.9   59.59  4970.9   59.14    4991   55.95  4998.1   50.49
  5000.8   49.99  5004.1   50.49  5011.1    52.5  5021.2   57.06  5041.3   57.18
  5051.6    58.9  5129.2    57.8  5223.1   58.03  5259.7   58.54  5275.1   59.69
  5338.9    60.9  5500.8    66.8  5616.6   74.34  5689.9   77.47  5747.8   79.27
    5775   80.48  5796.2   82.58  5842.4   83.31  5854.7   85.02  5891.6   86.07
#Mann= 5 ,-1 , 0
  4597.2     .05       0    4890     .12       0  4998.1     .07       0
  5004.1     .12       0  5129.2     .05       0
Bank Sta=4960.9,5275.1
XS Rating Curve= 0 ,0
Exp/Cntr=0.3,0.1

Type RM Length L Ch R = 1 ,15055   ,376,376,376
BEGIN DESCRIPTION:
Mapping XS b1ba89b9
END DESCRIPTION:
XS GIS Cut Line= 3
      2342322.69     13170297.62      2342182.13     13169665.06
      2341731.91     13169144.67
#Sta/Elev= 30
  4547.1   72.08  4612.5   69.46  4634.4   68.42  4670.8   66.99  4685.7   67.55
  4729.3   66.82  4752.8   65.15  4777.9   65.12  4896.2   62.28  4906.4   62.57
  4913.7   61.66  4937.1   60.66  4957.2   57.02  4962.3   59.19  4978.1   57.63
  4995.6   50.67  4998.4   50.17  5001.6   50.67  5019.1   55.35  5039.6   57.25
    5098   56.21  5111.3   56.89  5158.1   56.86  5239.5   57.06  5324.9   59.53
  5402.9   61.72  5587.2   71.21  5673.1    73.9  5820.8   77.54  5883.2   80.08
#Mann= 7 ,-1 , 0
  4547.1     .12       0  4612.5      .1       0  4634.4     .12       0
  4995.6     .07       0  5001.6     .12       0  5158.1     .05       0
  5673.1      .1       0
Bank Sta=4937.1,5324.9
XS Rating Curve= 0 ,0
Exp/Cntr=0.3,0.1

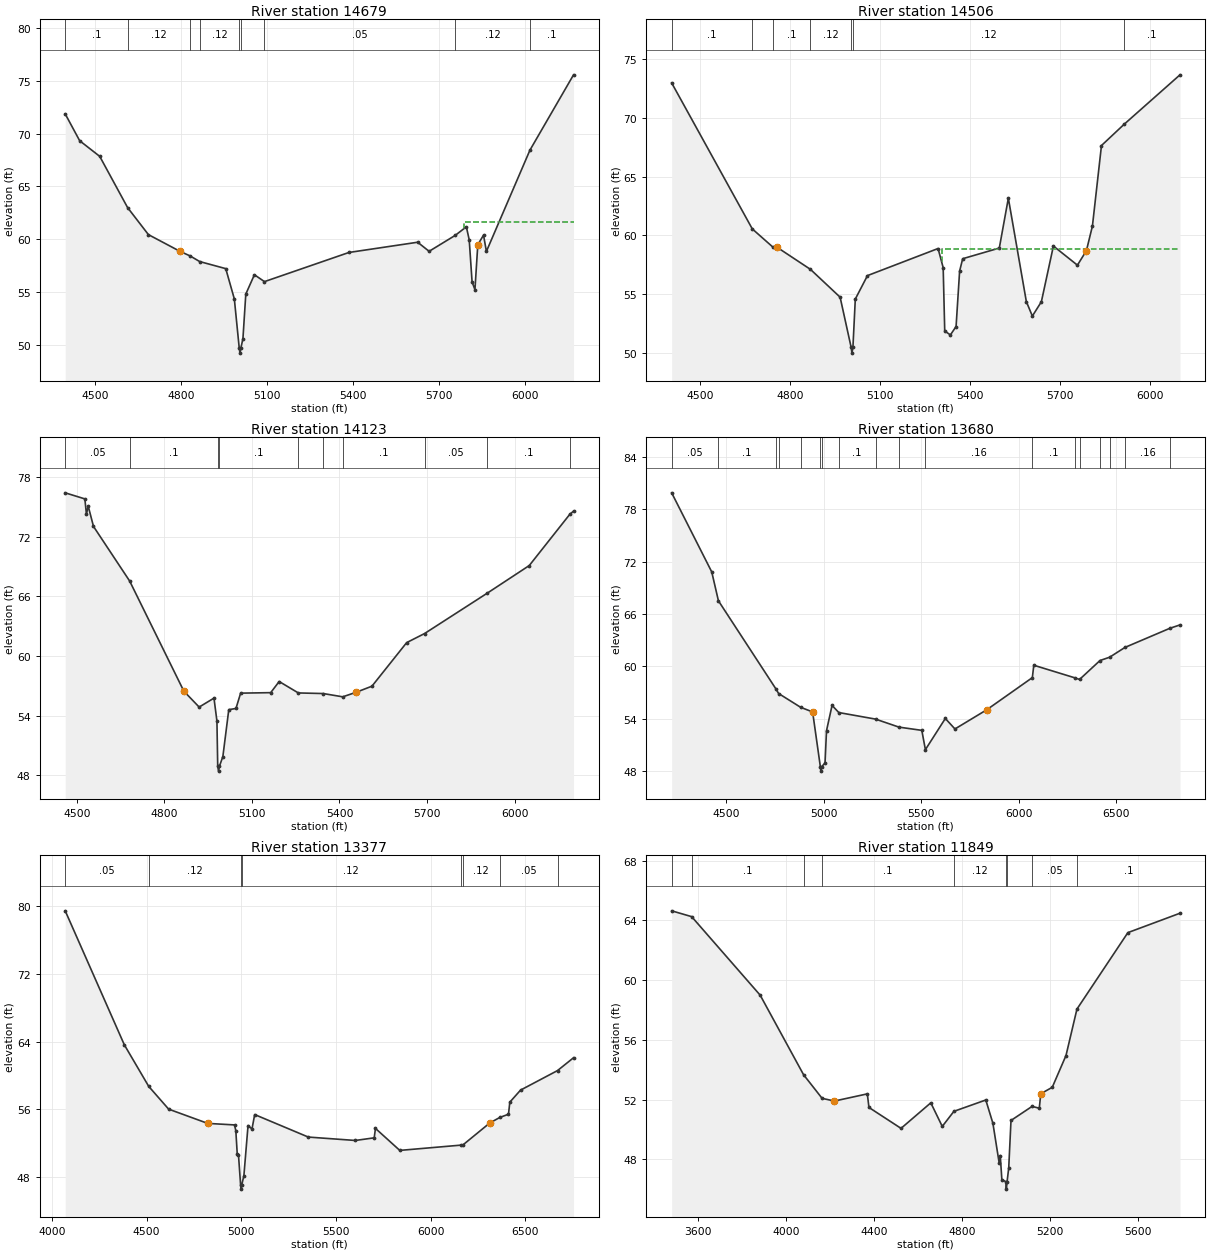
Type RM Length L Ch R = 1 ,14679   ,173,173,173
BEGIN DESCRIPTION:
SANDY HOLLOW CREEK 16.0
END DESCRIPTION:
XS GIS Cut Line= 2
      2342480.84     13170227.33      2342492.55     13168452.67
#Sta/Elev= 30
  4394.7   71.87  4445.2   69.33  4515.2   67.85  4612.5      63  4685.2   60.44
  4795.2   58.86    4831   58.42  4864.2   57.89  4955.2   57.22  4985.2   54.35
  5002.2   49.72  5004.9   49.22  5008.2   49.72  5015.2   50.59  5025.2   54.81
  5055.2   56.64  5090.4   55.99  5385.2   58.75  5625.2   59.72  5665.2   58.86
  5756.4   60.37  5795.2   61.18  5805.2   59.95  5815.2   55.96  5825.2   55.23
  5835.2   59.49  5855.2   60.39  5865.2   58.85  6017.2   68.44  6169.4   75.57
#Mann= 9 ,-1 , 0
  4394.7      .1       0  4612.5     .12       0    4831      .1       0
  4864.2     .12       0  5002.2     .07       0  5008.2     .12       0
  5090.4     .05       0  5756.4     .12       0  6017.2      .1       0
#XS Ineff= 2 , 0
                         5785.51            61.6
Permanent Ineff=
       F       F
Bank Sta=4795.2,5835.2
XS Rating Curve= 0 ,0
Exp/Cntr=0.3,0.1

Type RM Length L Ch R = 1 ,14506   ,383,383,383
BEGIN DESCRIPTION:
SANDY HOLLOW CREEK 15.0
END DESCRIPTION:
XS GIS Cut Line= 5
      2342615.55     13170186.36      2342627.27     13169747.06
      2342668.27     13169483.48      2342744.41     13169149.63
      2342767.84     13168505.39
#Sta/Elev= 30
  4406.1   72.99  4674.7   60.54  4743.7   58.98  4755.7      59  4868.5   57.09
  4967.2   54.72  5003.9   50.45  5006.6   49.95  5009.9   50.45  5017.8   54.56
  5058.3   56.56  5293.5   58.87  5310.5   57.24  5315.7   51.84  5334.5    51.5
  5353.5   52.22  5365.3   56.95  5375.5      58  5497.5   58.91  5527.6   63.16
  5587.6   54.34  5607.6   53.11  5637.6   54.33  5677.7   59.08  5757.7   57.45
  5787.7   58.69  5807.7   60.79  5837.8   67.65  5913.6   69.47  6099.4   73.68
#Mann= 7 ,-1 , 0
  4406.1      .1       0  4674.7     .12       0  4743.7      .1       0
  4868.5     .12       0  5003.9     .07       0  5009.9     .12       0
  5913.6      .1       0
#XS Ineff= 2 , 0
                         5305.11           58.82
Permanent Ineff=
       F       F
Bank Sta=4755.7,5787.7
XS Rating Curve= 0 ,0
Exp/Cntr=0.3,0.1

Type RM Length L Ch R = 1 ,14123   ,443,443,443
BEGIN DESCRIPTION:
SANDY HOLLOW CREEK 14.0
END DESCRIPTION:
XS GIS Cut Line= 4
      2342855.69      13170209.8       2342978.7      13169905.2
      2343125.13     13169067.63      2343136.84     13168505.33
#Sta/Elev= 30
  4460.6    76.4  4527.9   75.79  4533.3   74.25  4539.3   75.07  4557.5   73.02
  4681.4   67.53    4867   56.46  4919.4   54.86  4970.2   55.76  4980.3   53.46
    4983   48.92  4985.8   48.42    4989   48.92  5000.6   49.88  5020.9    54.6
  5045.5   54.72  5061.5   56.26  5164.5   56.31  5193.5   57.43  5259.2   56.28
  5344.5   56.22  5411.2   55.89  5457.4   56.35  5511.3   56.96  5630.2   61.34
  5691.4   62.25  5905.6    66.3  6050.2   69.09    6189   74.24  6201.8   74.56
#Mann= 10 ,-1 , 0
  4460.6     .05       0  4681.4      .1       0    4983     .07       0
    4989      .1       0  5259.2      .1       0  5344.5     .12       0
  5411.2      .1       0  5691.4     .05       0  5905.6      .1       0
    6189     .16       0
Bank Sta=4867,5457.4
XS Rating Curve= 0 ,0
Exp/Cntr=0.3,0.1

Type RM Length L Ch R = 1 ,13680   ,303,303,303
BEGIN DESCRIPTION:
SANDY HOLLOW CREEK 13.0
END DESCRIPTION:
XS GIS Cut Line= 2
      2342937.71     13170346.87      2344652.38     13168382.98
#Sta/Elev= 30
  4219.5   79.88    4425   70.82  4459.3   67.51  4753.2   57.45    4768   56.89
  4881.1   55.31  4942.4   54.78  4982.1    48.5  4984.9      48  4988.1    48.5
    5006   48.92  5013.6   52.63  5042.1   55.53  5076.7   54.71  5264.9   53.96
  5385.4   53.04  5502.4   52.67  5520.8   50.46    5623   54.03  5672.4   52.83
  5835.6   55.03  6069.3   58.71  6076.8   60.13  6288.4   58.68  6311.4    58.5
  6416.3   60.67  6465.8   61.05  6544.2   62.17  6774.4   64.36  6826.6   64.75
#Mann= 18 ,-1 , 0
  4219.5     .05       0  4459.3      .1       0  4753.2     .05       0
    4768      .1       0  4881.1     .12       0  4982.1     .07       0
  4988.1     .12       0  5076.7      .1       0  5264.9     .05       0
  5385.4      .1       0  5520.8     .16       0  6069.3      .1       0
  6288.4     .16       0  6311.4      .1       0  6416.3     .16       0
  6465.8      .1       0  6544.2     .16       0  6774.4      .1       0
Bank Sta=4942.4,5835.6
XS Rating Curve= 0 ,0
Exp/Cntr=0.3,0.1

Type RM Length L Ch R = 1 ,13377   ,1528,1528,1528
BEGIN DESCRIPTION:
SANDY HOLLOW CREEK 12.0
END DESCRIPTION:
XS GIS Cut Line= 2
      2343142.01     13170481.89      2344886.12     13168441.02
#Sta/Elev= 30
  4070.3   79.39  4382.6   63.61  4511.3   58.72  4616.5   56.04  4822.9   54.36
  4964.5   54.18  4971.4    53.5  4978.8   50.77  4985.3   50.69  4996.6   47.12
  4999.4   46.62  5002.6   47.12  5013.9   48.19  5035.9   54.11  5056.7    53.7
    5071    55.4  5354.2   52.75  5602.8   52.35  5702.2   52.66  5708.8   53.77
  5837.3   51.18  6160.1    51.8  6170.5   51.82  6312.6   54.41  6365.6   55.06
  6411.4   55.44  6418.4   56.86  6475.1   58.28  6670.4   60.58  6754.9   62.09
#Mann= 8 ,-1 , 0
  4070.3     .05       0  4511.3     .12       0  4996.6     .07       0
  5002.6     .12       0  6160.1     .05       0  6170.5     .12       0
  6365.6     .05       0  6670.4      .1       0
Bank Sta=4822.9,6312.6
XS Rating Curve= 0 ,0
Exp/Cntr=0.3,0.1

Type RM Length L Ch R = 1 ,11849   ,413,413,413
BEGIN DESCRIPTION:
Mapping XS 3e4eda9c
END DESCRIPTION:
XS GIS Cut Line= 3
      2344325.84     13170432.34      2344653.84     13169758.77
      2345093.11     13168259.38
#Sta/Elev= 30
  3478.8   64.64  3569.7   64.25  3881.3   58.99  4078.7   53.66  4162.9   52.08
    4219    51.9  4368.5   52.38  4375.9   51.47  4521.8   50.07  4657.2   51.78
  4709.3    50.2  4762.2   51.21  4907.3   51.97  4939.6   50.41  4967.8   47.78
    4973   48.25  4980.3   46.64  4998.1    46.5  5000.8      46  5004.1    46.5
  5011.6   47.43  5021.9    50.6  5117.6   51.54  5150.5   51.42  5157.4   52.39
  5209.5   52.82    5272   54.95  5321.8   58.06  5553.4   63.18  5790.4   64.48
#Mann= 9 ,-1 , 0
  3478.8     .05       0  3569.7      .1       0  4078.7     .12       0
  4162.9      .1       0  4762.2     .12       0  4998.1     .07       0
  5004.1     .12       0  5117.6     .05       0  5321.8      .1       0
Bank Sta=4219,5157.4
XS Rating Curve= 0 ,0
Exp/Cntr=0.3,0.1