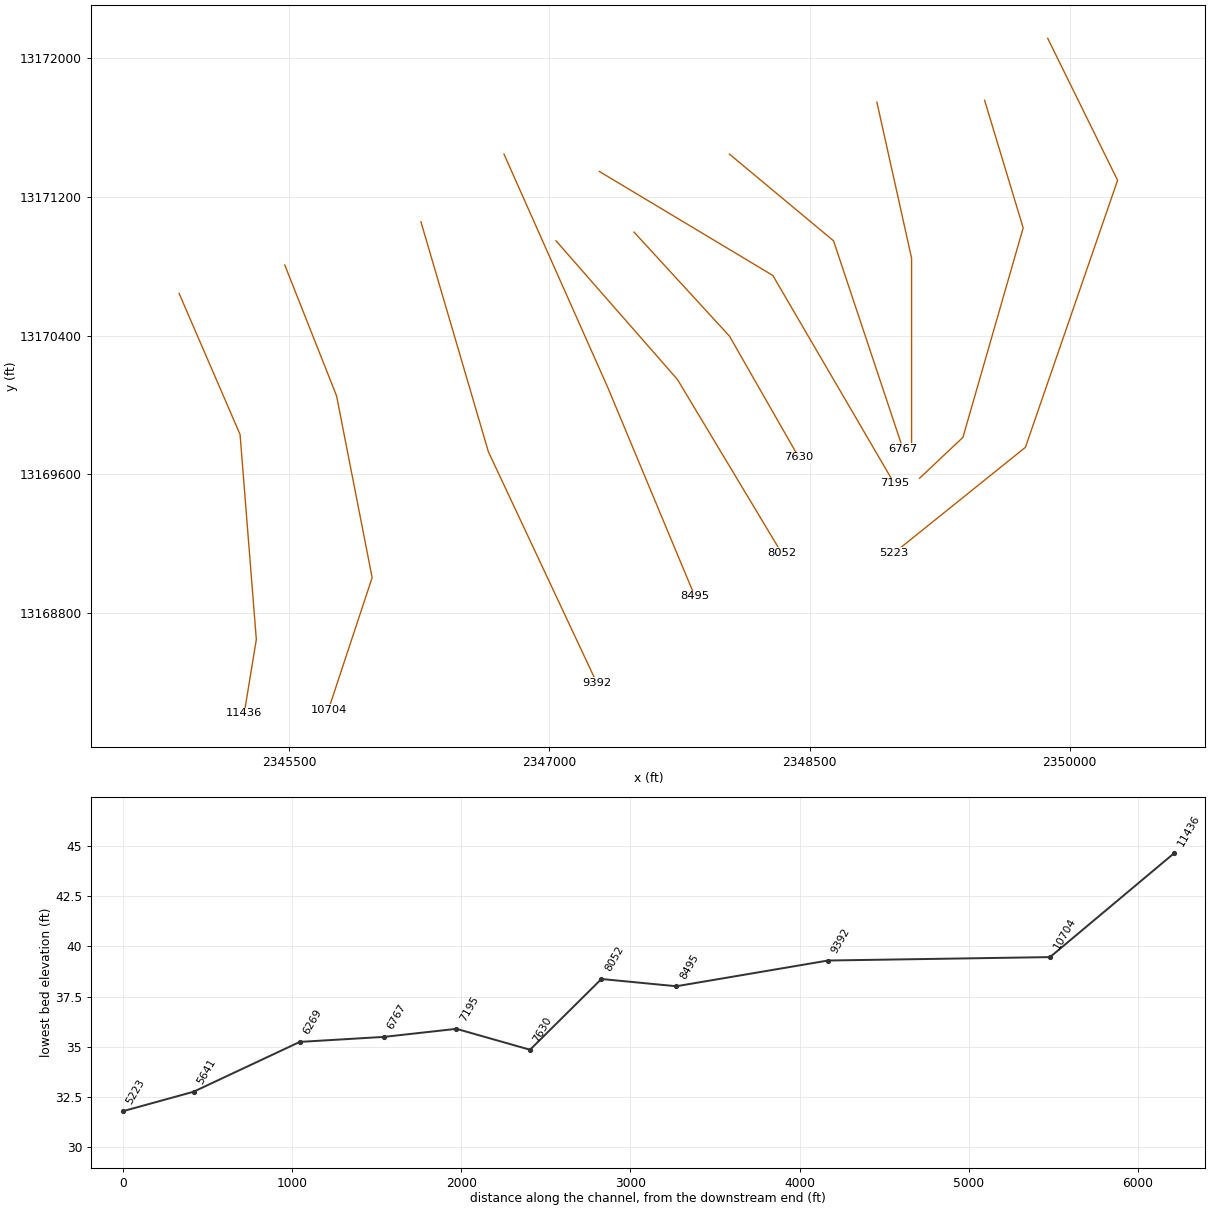
HEC-RAS study SANDY HOLLOW CREEK.prj: SANDY HOLLOW CREEK Base Level Engineering

--- SANDY HOLLOW CREEK.g01 (geometry) --- (continued)

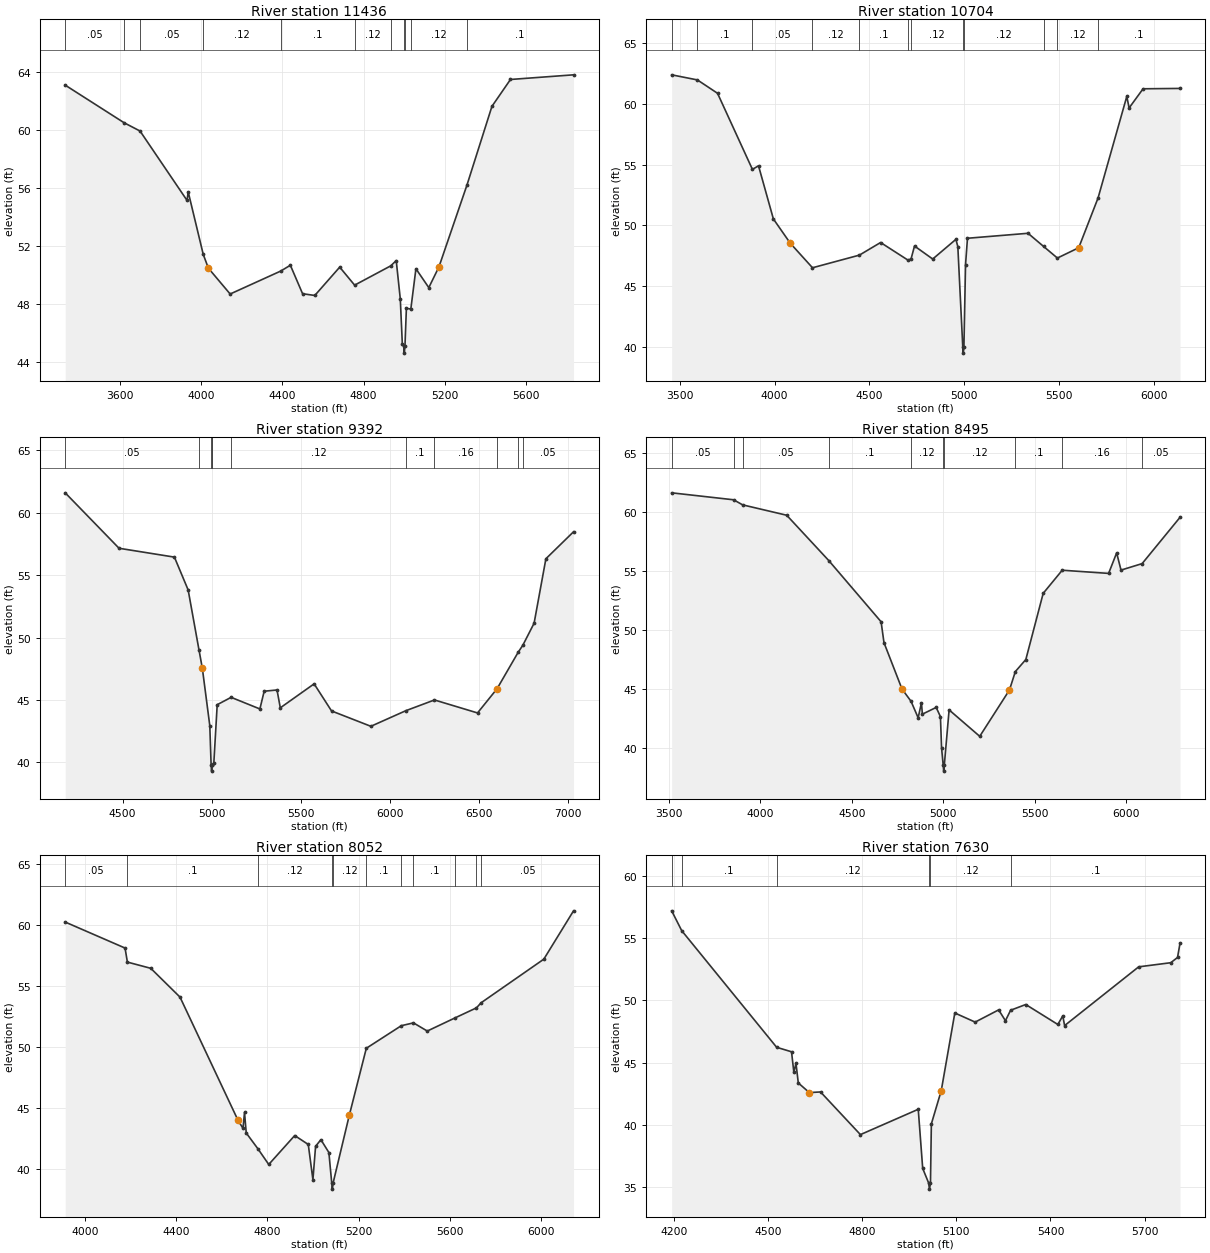
Type RM Length L Ch R = 1 ,11436   ,732,732,732
BEGIN DESCRIPTION:
SANDY HOLLOW CREEK 11.0
END DESCRIPTION:
XS GIS Cut Line= 4
       2344864.7     13170643.19      2345216.13     13169829.06
      2345309.84     13168645.91      2345239.85     13168220.12
#Sta/Elev= 30
  3329.6   63.08  3619.9   60.49  3698.4   59.92  3930.2   55.14  3935.6   55.74
  4009.8   51.43  4035.1   50.48  4142.5    48.7  4391.7   50.28  4439.2   50.68
  4499.4   48.72  4559.6    48.6  4682.4   50.55  4755.9   49.31    4934   50.64
  4960.9      51  4980.9   48.37    4991   45.26    4998   45.13  5000.7   44.63
    5004   45.13    5011   47.71  5032.9   47.67    5058   50.44  5121.4   49.14
  5171.5   50.57  5309.5    56.2  5432.6   61.62  5523.9   63.47  5834.7   63.79
#Mann= 11 ,-1 , 0
  3329.6     .05       0  3619.9      .1       0  3698.4     .05       0
  4009.8     .12       0  4391.7      .1       0  4755.9     .12       0
    4934     .05       0    4998     .04       0    5004     .05       0
  5032.9     .12       0  5309.5      .1       0
Bank Sta=4035.1,5171.5
XS Rating Curve= 0 ,0
Exp/Cntr=0.3,0.1

Type RM Length L Ch R = 1 ,10704   ,1312,1312,1312
BEGIN DESCRIPTION:
SANDY HOLLOW CREEK 10.0
END DESCRIPTION:
XS GIS Cut Line= 4
      2345473.85     13170807.17      2345772.55     13170051.63
      2345977.55      13169003.2      2345725.71      13168241.8
#Sta/Elev= 30
  3456.4   62.39  3592.2   61.97  3698.4   60.87  3882.6    54.6  3914.7    54.9
  3993.2   50.52  4082.4   48.52  4199.6    46.5  4446.9   47.54    4559   48.58
  4703.5   47.13  4719.6   47.22    4738   48.29  4834.1   47.22  4956.4   48.84
  4966.6   48.24  4992.7   39.97  4995.4   39.47  4998.7   39.97  5007.3   46.76
  5017.5   48.93  5337.1   49.34  5418.9   48.26    5492    47.3  5604.6   48.15
  5706.7   52.25  5858.3   60.61  5870.5   59.66  5944.2   61.24  6139.1   61.27
#Mann= 12 ,-1 , 0
  3456.4     .05       0  3592.2      .1       0  3882.6     .05       0
  4199.6     .12       0  4446.9      .1       0  4703.5     .05       0
  4719.6     .12       0  4992.7     .07       0  4998.7     .12       0
  5418.9      .1       0    5492     .12       0  5706.7      .1       0
Bank Sta=4082.4,5604.6
XS Rating Curve= 0 ,0
Exp/Cntr=0.3,0.1

Type RM Length L Ch R = 1 ,9392    ,897,897,897
BEGIN DESCRIPTION:
Mapping XS 4265911f
END DESCRIPTION:
XS GIS Cut Line= 3
      2346258.88     13171056.02      2346647.78      13169729.6
      2347272.73     13168396.36
#Sta/Elev= 30
    4178   61.59  4480.3   57.15  4791.3   56.44  4868.5   53.81  4929.4      49
  4948.3   47.52    4990   42.94  4997.4    39.8  5000.1    39.3  5003.4    39.8
  5003.6   39.81  5012.6   39.94  5031.6   44.62  5109.8   45.21  5271.3   44.28
  5295.4    45.7  5367.5    45.8    5386   44.37  5575.9   46.29  5673.7   44.12
  5894.6   42.89  6090.9   44.14  6251.7      45  6493.6   43.96  6603.3    45.9
  6721.4   48.81  6748.3   49.39  6811.3   51.15  6877.5   56.31  7032.7   58.47
#Mann= 11 ,-1 , 0
    4178     .05       0  4929.4     .12       0  4997.4     .07       0
  5003.4     .12       0  5003.6     .05       0  5109.8     .12       0
  6090.9      .1       0  6251.7     .16       0  6603.3      .1       0
  6721.4     .16       0  6748.3     .05       0
Bank Sta=4948.3,6603.3
XS Rating Curve= 0 ,0
Exp/Cntr=0.3,0.1

Type RM Length L Ch R = 1 ,8495    ,443,443,443
BEGIN DESCRIPTION:
SANDY HOLLOW CREEK 9.0
END DESCRIPTION:
XS GIS Cut Line= 3
      2346737.73     13171446.83      2347337.72     13170096.85
      2347837.72     13168896.86
#Sta/Elev= 30
  3515.9   61.61  3854.3   61.02  3903.6   60.59  4144.4   59.71  4374.1   55.87
  4660.1   50.68  4675.9   48.91  4774.3   44.98  4823.7   43.94  4862.6   42.54
  4880.4    43.8  4885.8   42.85  4961.1   43.42  4984.3   42.64  4990.5   39.99
  4999.4   38.52  5002.2   38.02  5005.4   38.52  5031.7   43.21    5199   40.97
  5361.5    44.9  5393.6   46.46  5450.9   47.48  5545.7   53.09  5649.7   55.05
  5903.2   54.78  5947.1   56.52  5970.9   55.06  6086.3   55.61  6293.2   59.53
#Mann= 10 ,-1 , 0
  3515.9     .05       0  3854.3     .16       0  3903.6     .05       0
  4374.1      .1       0  4823.7     .12       0  4999.4     .07       0
  5005.4     .12       0  5393.6      .1       0  5649.7     .16       0
  6086.3     .05       0
Bank Sta=4774.3,5361.5
XS Rating Curve= 0 ,0
Exp/Cntr=0.3,0.1

Type RM Length L Ch R = 1 ,8052    ,422,422,422
BEGIN DESCRIPTION:
SANDY HOLLOW CREEK 8.0
END DESCRIPTION:
XS GIS Cut Line= 3
      2347037.75     13170946.82      2347737.72     13170146.85
      2348337.74     13169146.82
#Sta/Elev= 30
  3913.1   60.26  4175.5   58.13  4185.8   56.98  4288.4   56.47  4416.6   54.11
  4670.9   44.02  4692.8   43.36  4699.4   44.66    4707   42.98    4758   41.69
  4805.7    40.4  4919.6   42.77    4979   42.04  4999.4   39.15  5011.1   41.89
  5034.4   42.43  5069.4   41.38  5081.9   38.88  5084.7   38.38  5087.9   38.88
  5158.8   44.42  5233.6   49.92  5387.1   51.77  5440.4      52  5500.9   51.33
    5624   52.42  5716.5   53.23  5737.2   53.65    6012   57.22  6142.3   61.18
#Mann= 11 ,-1 , 0
  3913.1     .05       0  4185.8      .1       0    4758     .12       0
  5081.9     .07       0  5087.9     .12       0  5233.6      .1       0
  5387.1     .16       0  5440.4      .1       0    5624     .05       0
  5716.5      .1       0  5737.2     .05       0
Bank Sta=4670.9,5158.8
XS Rating Curve= 0 ,0
Exp/Cntr=0.3,0.1

Type RM Length L Ch R = 1 ,7630    ,435,435,435
BEGIN DESCRIPTION:
SANDY HOLLOW CREEK 7.0
END DESCRIPTION:
XS GIS Cut Line= 3
      2347487.69     13170996.89      2348037.72     13170396.85
      2348437.71     13169696.87
#Sta/Elev= 30
  4192.7   57.17  4224.7   55.58  4527.3   46.23  4574.7   45.87  4582.1   44.24
  4588.9   44.94  4596.3   43.37  4631.5    42.6  4667.2   42.65  4794.3   39.23
  4978.6   41.26  4992.8   36.52  5011.6   35.36  5014.4   34.86  5017.6   35.36
  5020.4   40.09    5052   42.76  5095.2   48.98    5160   48.25  5234.9   49.23
  5256.5   48.36    5273    49.2  5321.3   49.66  5423.5   48.06  5439.3   48.75
  5445.1   47.97  5681.2   52.68  5783.4   53.01    5805   53.43  5812.9   54.56
#Mann= 6 ,-1 , 0
  4192.7     .05       0  4224.7      .1       0  4527.3     .12       0
  5011.6     .07       0  5017.6     .12       0    5273      .1       0
Bank Sta=4631.5,5052
XS Rating Curve= 0 ,0
Exp/Cntr=0.3,0.1

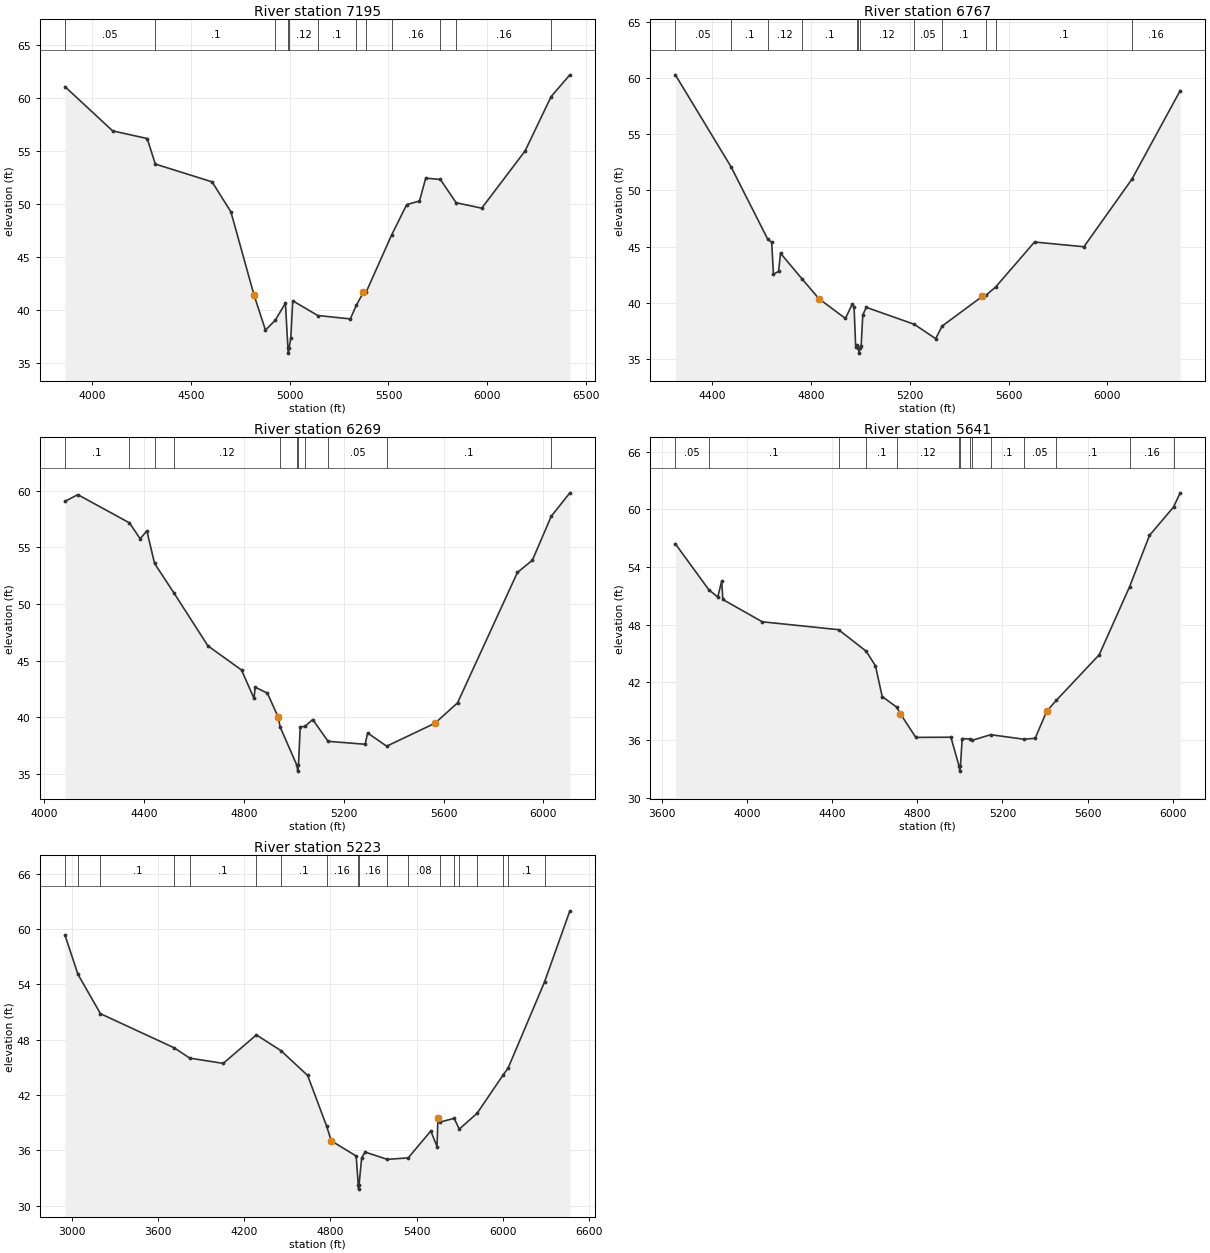
Type RM Length L Ch R = 1 ,7195    ,428,428,428
BEGIN DESCRIPTION:
SANDY HOLLOW CREEK 6.0
END DESCRIPTION:
XS GIS Cut Line= 3
      2347287.73     13171346.85      2348287.72     13170746.85
      2348987.71     13169546.87
#Sta/Elev= 30
  3862.9   61.04  4103.9   56.87  4278.8   56.15  4319.9   53.74  4607.3   52.06
  4702.5   49.23  4819.2    41.4  4877.5   38.07  4926.8      39  4978.5   40.61
  4991.1    36.4  4993.8    35.9  4997.1    36.4  5005.8   37.36  5015.5   40.84
  5142.1   39.45  5306.9   39.13  5337.4   40.41  5373.5   41.65  5388.1    41.7
  5516.8   47.08  5592.6   49.92  5657.1   50.25  5688.6   52.41  5762.7   52.29
  5842.6   50.09  5972.2   49.58  6191.3   54.97  6323.5   60.11  6418.3   62.16
#Mann= 12 ,-1 , 0
  3862.9     .05       0  4319.9      .1       0  4926.8     .12       0
  4991.1     .07       0  4997.1     .12       0  5142.1      .1       0
  5337.4     .05       0  5388.1      .1       0  5516.8     .16       0
  5762.7      .1       0  5842.6     .16       0  6323.5      .1       0
Bank Sta=4819.2,5373.5
XS Rating Curve= 0 ,0
Exp/Cntr=0.3,0.1

Type RM Length L Ch R = 1 ,6767    ,498,498,498
BEGIN DESCRIPTION:
SANDY HOLLOW CREEK 5.0
END DESCRIPTION:
XS GIS Cut Line= 3
      2348037.71     13171446.87      2348637.72     13170946.85
      2349037.74     13169746.81
#Sta/Elev= 30
  4249.6    60.3  4475.5    52.1  4623.5   45.68  4640.1   45.36  4647.3   42.52
  4668.1   42.79  4675.9    44.4  4763.7    42.1  4832.1   40.34  4938.9   38.59
  4966.2   39.85    4974   39.61  4980.5   36.08    4987   36.22  4991.8      36
  4994.6    35.5  4997.8      36  5002.7   36.14  5009.2    38.9  5023.5   39.58
  5217.9   38.07  5304.7   36.79  5330.7   37.91  5494.4   40.57  5508.9   40.66
    5548    41.4  5705.3    45.4  5905.5   44.98  6100.3   51.01  6295.6   58.89
#Mann= 12 ,-1 , 0
  4249.6     .05       0  4475.5      .1       0  4623.5     .12       0
  4763.7      .1       0    4987     .12       0  4991.8     .07       0
  4997.8     .12       0  5217.9     .05       0  5330.7      .1       0
  5508.9     .16       0    5548      .1       0  6100.3     .16       0
Bank Sta=4832.1,5494.4
XS Rating Curve= 0 ,0
Exp/Cntr=0.3,0.1

Type RM Length L Ch R = 1 ,6269    ,628,628,628
BEGIN DESCRIPTION:
SANDY HOLLOW CREEK 4.0
END DESCRIPTION:
XS GIS Cut Line= 3
      2348887.73     13171746.81      2349087.72     13170846.85
      2349087.72     13169746.86
#Sta/Elev= 30
    4084   59.05  4135.2   59.64    4342   57.15  4384.9   55.75  4411.8   56.44
  4442.6   53.57  4520.4   50.96  4656.3    46.3  4790.8   44.17  4840.7   41.68
  4845.8   42.65  4894.5   42.13    4938      40  4945.6   39.14  5012.9   35.75
  5015.7   35.25  5018.9   35.75  5025.9   39.14  5045.4   39.21  5075.9    39.8
  5137.6   37.88  5285.9   37.62  5295.9   38.62  5372.1   37.45  5565.9   39.48
  5655.9   41.27  5895.9   52.78  5955.9   53.86  6031.2   57.73  6105.9    59.8
#Mann= 11 ,-1 , 0
    4084      .1       0    4342     .05       0  4442.6      .1       0
  4520.4     .12       0  4945.6     .05       0  5012.9     .04       0
  5018.9     .05       0  5045.4      .1       0  5137.6     .05       0
  5372.1      .1       0  6031.2     .16       0
Bank Sta=4938,5565.9
XS Rating Curve= 0 ,0
Exp/Cntr=0.3,0.1

Type RM Length L Ch R = 1 ,5641    ,418,418,418
BEGIN DESCRIPTION:
Mapping XS 3cce6f65
END DESCRIPTION:
XS GIS Cut Line= 4
      2349508.88     13171757.41      2349731.11     13171021.26
      2349383.89     13169812.93      2349133.86      13169576.8
#Sta/Elev= 30
  3664.2   56.43  3821.9   51.63  3863.3   50.89    3882   52.55  3887.2   50.63
  4072.2   48.31  4430.4   47.49    4560   45.25  4603.7   43.73  4635.4   40.53
  4703.3   39.43  4720.4   38.75  4793.1   36.28    4958    36.3  4996.6   33.27
  4999.4   32.77  5002.6   33.27  5010.9   36.16  5047.8    36.1  5056.9   35.97
  5144.6   36.56  5301.4   36.09  5353.4   36.19  5407.8      39  5452.9   40.14
  5654.2   44.88  5796.5   51.94  5890.2    57.3  6003.1   60.25  6034.3   61.73
#Mann= 14 ,-1 , 0
  3664.2     .05       0  3821.9      .1       0  4430.4     .05       0
    4560      .1       0  4703.3     .12       0  4996.6     .07       0
  5002.6     .12       0  5047.8      .1       0  5056.9     .16       0
  5144.6      .1       0  5301.4     .05       0  5452.9      .1       0
  5796.5     .16       0  6003.1      .1       0
Bank Sta=4720.4,5407.8
XS Rating Curve= 0 ,0
Exp/Cntr=0.3,0.1

Type RM Length L Ch R = 1 ,5223    ,0,0,0
BEGIN DESCRIPTION:
SANDY HOLLOW CREEK 1.0
END DESCRIPTION:
XS GIS Cut Line= 4
       2349872.6     13172115.02      2350275.47     13171295.84
      2349744.05     13169755.14      2348987.22     13169146.29
#Sta/Elev= 30
  2952.7   59.34  3042.3   55.11  3199.4   50.83  3712.4   47.13    3821   46.01
  4053.8   45.44  4284.7   48.53    4456   46.82  4641.4   44.13  4772.9   38.66
    4806   37.04  4979.3   35.39  4993.4    32.3  4996.1    31.8  4999.4    32.3
  5017.5    35.2  5041.7   35.82  5195.4   35.03  5341.5   35.19  5498.8   38.11
    5542   36.42  5548.4   39.47  5560.1   39.06  5661.4   39.48  5696.8   38.31
  5820.9   40.03  6003.6   44.22  6036.5   44.92  6290.7   54.29  6466.7   61.99
#Mann= 19 ,-1 , 0
  2952.7      .1       0  3042.3     .05       0  3199.4      .1       0
  3712.4     .05       0    3821      .1       0  4284.7     .05       0
    4456      .1       0  4772.9     .16       0  4993.4     .07       0
  4999.4     .16       0  5195.4      .1       0  5341.5     .08       0
  5560.1      .1       0  5661.4     .08       0  5696.8     .16       0
  5820.9      .1       0  6003.6     .05       0  6036.5      .1       0
  6290.7     .05       0
Bank Sta=4806,5548.4
XS Rating Curve= 0 ,0
Exp/Cntr=0.3,0.1

Chan Stop Cuts=-1
Use User Specified Reach Order=0
Composite Channel Slope=5