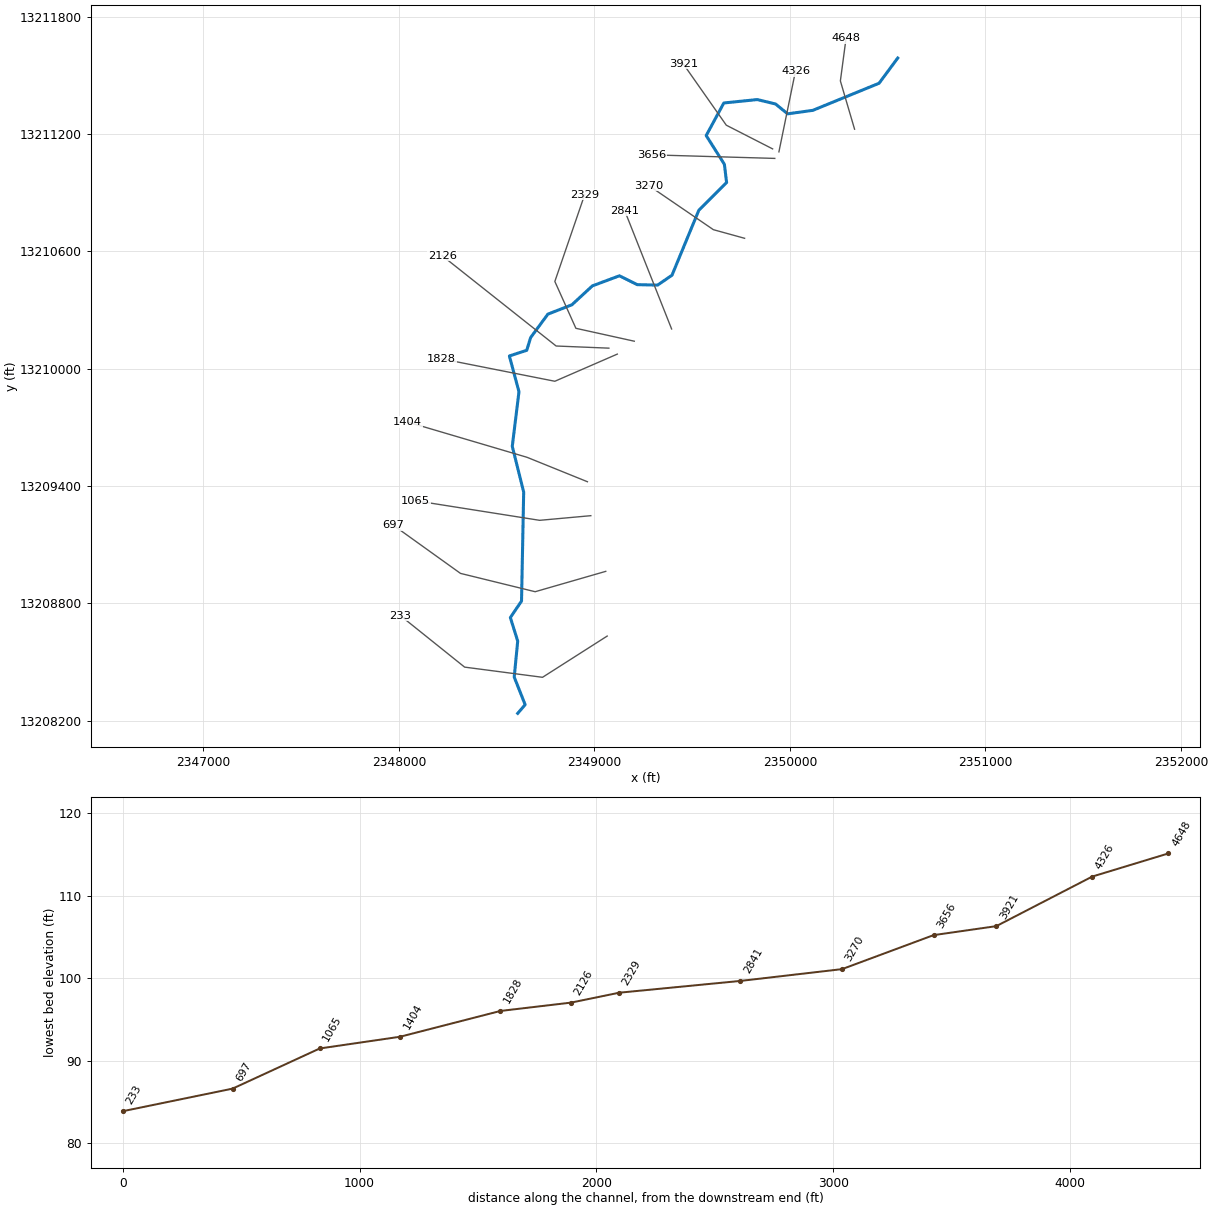
--- SIXMILE CREEK TRIB.prj (project) ---

Proj Title=SIXMILE CREEK TRIB Base Level Engineering
Current Plan=p01
Default Exp/Contr=0.3,0.1
English Units
Geom File=g01
Flow File=f01
Plan File=p01
Y Axis Title=Elevation
X Axis Title(PF)=Main Channel Distance
X Axis Title(XS)=Station
BEGIN DESCRIPTION:
SIXMILE CREEK TRIB
END DESCRIPTION:
DSS Export Rating Curves= 0
DSS Export Rating Curve Sorted= 0
DSS Export Volume Flow Curves= 0
DXF OffsetX= 0
DXF OffsetY= 0
DXF ScaleX= 1
DXF ScaleY= 10

--- SIXMILE CREEK TRIB.p01 (plan) ---

Plan Title=Multiple Run
Short Identifier=Multiple
Geom File=g01
Flow File=f01
Subcritical Flow
K Sum by GR= 0
Std Step Tol= 0.01
Critical Tol= 0.01
Num of Std Step Trials= 20
Max Error Tol= 0.3
Flow Tol Ratio= 0.001
Split Flow NTrial= 30
Split Flow Tol= 0.02
Split Flow Ratio= 0.02
Log Output Level= 0
Friction Slope Method= 1
Unsteady Friction Slope Method= 2
Unsteady Bridges Friction Slope Method= 1
Parabolic Critical Depth
Global Vel Dist=  1 , 1 , 1
Global Log Level= 0
CheckData=True
Encroach Param= -1, 0, 0, 0
BEGIN DESCRIPTION:
Multiple Run
END DESCRIPTION:

--- SIXMILE CREEK TRIB.f01 (steady flow) ---

Flow Title=Multiple
Number of Profiles=7
Profile Names=10-year,25-year,50-year,1pct_min,100-year,1pct_plu,500-year
River Rch & RM= SIXMILE CREEK TR,Reach-1,4648
     567     778     948     843    1140    1542    1653
Boundary for River Rch & Prof#=SIXMILE CREEK TR,Reach-1,1
Up Type=0
Dn Type=3
Dn Slope=0.005
Boundary for River Rch & Prof#=SIXMILE CREEK TR,Reach-1,2
Up Type=0
Dn Type=3
Dn Slope=0.005
Boundary for River Rch & Prof#=SIXMILE CREEK TR,Reach-1,3
Up Type=0
Dn Type=3
Dn Slope=0.005
Boundary for River Rch & Prof#=SIXMILE CREEK TR,Reach-1,4
Up Type=0
Dn Type=3
Dn Slope=0.005
Boundary for River Rch & Prof#=SIXMILE CREEK TR,Reach-1,5
Up Type=0
Dn Type=3
Dn Slope=0.005
Boundary for River Rch & Prof#=SIXMILE CREEK TR,Reach-1,6
Up Type=0
Dn Type=3
Dn Slope=0.005
Boundary for River Rch & Prof#=SIXMILE CREEK TR,Reach-1,7
Up Type=0
Dn Type=3
Dn Slope=0.005

--- SIXMILE CREEK TRIB.g01 (geometry) ---

Geom Title=Existing Conditions
Program Version=4.10

River Reach=SIXMILE CREEK TR,Reach-1
Reach XY= 30
      2350551.22     13211588.55      2350455.82     13211459.62
       2350116.7     13211320.98      2349987.99     13211303.24
      2349926.38     13211353.48      2349832.99     13211376.21
      2349661.85      13211358.8      2349571.56     13211192.08
      2349664.54     13211045.41      2349675.96     13210952.06
      2349533.53     13210809.38      2349396.64     13210477.77
      2349323.13     13210427.32      2349218.85     13210429.56
      2349127.73     13210474.87      2348989.26     13210423.15
      2348884.58     13210326.45      2348761.98     13210278.73
      2348673.73     13210159.03      2348653.83     13210093.88
      2348564.95     13210064.74      2348614.03     13209881.96
      2348579.82     13209602.56      2348638.13     13209368.69
       2348627.1     13208811.38      2348569.98     13208726.84
      2348607.54     13208606.65      2348589.71     13208422.56
      2348645.65     13208281.36      2348607.72     13208236.86

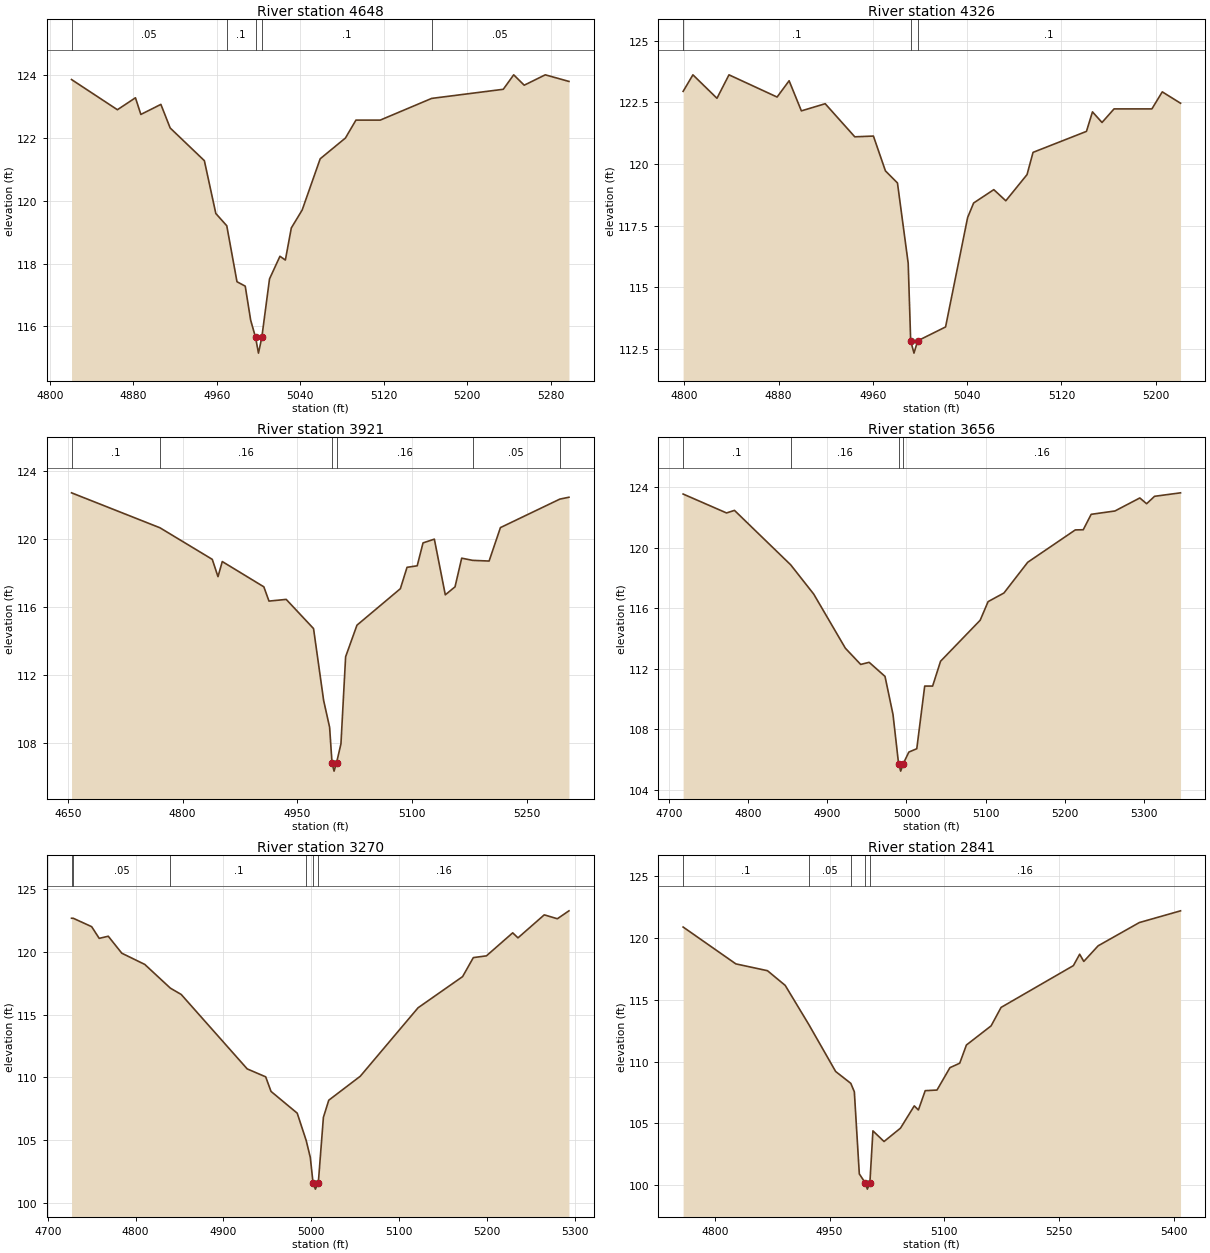
Type RM Length L Ch R = 1 ,4648    ,322,322,322
BEGIN DESCRIPTION:
SIXMILE CREEK TRIB 10.0
END DESCRIPTION:
XS GIS Cut Line= 3
      2350330.47     13211224.64      2350257.86     13211471.54
       2350286.9     13211689.35
#Sta/Elev= 30
  4820.6  123.85  4864.6  122.89  4881.9  123.27  4887.1  122.74  4906.3  123.06
  4915.2  122.31    4948  121.27    4959  119.59  4969.5   119.2  4979.3  117.42
  4987.2  117.28  4992.4   116.2  4997.1  115.65  4999.9  115.15  5003.1  115.65
  5010.5  117.51  5020.5  118.23  5025.7  118.11  5031.4  119.13  5041.8   119.7
  5059.1  121.33  5083.3  121.99  5093.4  122.56  5116.7  122.56    5166  123.25
  5234.7  123.54  5244.7     124  5254.8  123.67    5275     124  5297.7  123.79
#Mann= 5 ,-1 , 0
  4820.6     .05       0  4969.5      .1       0  4997.1     .07       0
  5003.1      .1       0    5166     .05       0
Bank Sta=4997.1,5003.1
XS Rating Curve= 0 ,0
Exp/Cntr=0.3,0.1

Type RM Length L Ch R = 1 ,4326    ,405,405,405
BEGIN DESCRIPTION:
SIXMILE CREEK TRIB 9.0
END DESCRIPTION:
XS GIS Cut Line= 2
      2349943.53     13211108.77      2350028.36     13211522.06
#Sta/Elev= 30
  4799.1  122.94  4807.4  123.61  4827.8  122.66    4838  123.61  4878.8  122.71
    4889  123.37  4899.4  122.15  4919.6  122.44  4944.7   121.1  4960.5  121.13
  4970.7  119.72  4980.9  119.23    4990  115.98  4992.1  112.84  4994.9  112.34
  4998.1  112.84  5021.7   113.4  5040.4  117.83  5045.5  118.42  5062.6  118.96
  5072.8  118.51  5090.8  119.57  5095.9  120.47  5141.2  121.32  5146.3  122.11
  5154.4  121.68  5164.6  122.23  5196.7  122.23  5205.5  122.92    5221  122.46
#Mann= 3 ,-1 , 0
  4799.1      .1       0  4992.1     .07       0  4998.1      .1       0
Bank Sta=4992.1,4998.1
XS Rating Curve= 0 ,0
Exp/Cntr=0.3,0.1

Type RM Length L Ch R = 1 ,3921    ,265,265,265
BEGIN DESCRIPTION:
Mapping XS ab5c871c
END DESCRIPTION:
XS GIS Cut Line= 3
      2349911.31     13211123.89      2349674.42     13211245.09
      2349454.07     13211559.09
#Sta/Elev= 30
  4654.9  122.73  4770.4  120.67  4838.7  118.81  4846.2  117.79  4851.8  118.68
  4906.1  117.19  4912.8  116.35  4935.3  116.45    4971  114.73  4984.2  110.49
    4992  108.91  4995.1  106.83  4997.8  106.33  5001.1  106.83  5006.8  107.94
  5012.9  113.07  5027.7  114.93  5084.4  117.08  5093.1  118.34  5106.4  118.43
    5114  119.78  5128.8     120  5143.1  116.72  5155.8  117.19  5164.5  118.88
  5178.8  118.75  5200.3  118.71  5215.1  120.68  5292.7  122.36  5304.6  122.47
#Mann= 6 ,-1 , 0
  4654.9      .1       0  4770.4     .16       0  4995.1     .07       0
  5001.1     .16       0  5178.8     .05       0  5292.7      .1       0
Bank Sta=4995.1,5001.1
XS Rating Curve= 0 ,0
Exp/Cntr=0.3,0.1

Type RM Length L Ch R = 1 ,3656    ,386,386,386
BEGIN DESCRIPTION:
SIXMILE CREEK TRIB 8.0
END DESCRIPTION:
XS GIS Cut Line= 2
      2349922.46     13211075.23      2349294.93     13211093.45
#Sta/Elev= 30
  4718.1  123.55  4772.9   122.3  4782.9  122.47  4853.9  118.87  4882.9  116.94
  4922.9  113.36  4942.2  112.29  4952.9  112.43  4972.9   111.5    4983  108.98
    4990  105.74  4992.7  105.24    4996  105.74    5003   106.5    5013  106.72
    5023  110.86    5033  110.86    5043   112.5    5093  115.21    5103  116.44
    5123  117.01    5153  119.04  5213.1  121.18  5223.1  121.19  5233.1  122.21
  5263.1  122.43  5294.5  123.29  5303.1  122.91  5313.1   123.4  5345.9  123.63
#Mann= 4 ,-1 , 0
  4718.1      .1       0  4853.9     .16       0    4990     .07       0
    4996     .16       0
Bank Sta=4990,4996
XS Rating Curve= 0 ,0
Exp/Cntr=0.3,0.1

Type RM Length L Ch R = 1 ,3270    ,429,429,429
BEGIN DESCRIPTION:
SIXMILE CREEK TRIB 7.0
END DESCRIPTION:
XS GIS Cut Line= 3
      2349768.05     13210666.67      2349608.32     13210710.73
      2349277.81     13210936.58
#Sta/Elev= 30
  4727.1  122.66    4729  122.66    4750  121.99  4758.6  121.06  4768.9  121.23
  4784.3  119.88  4810.4  118.99  4839.6   117.1  4851.9   116.6    4927  110.68
    4948  110.05  4954.1  108.89  4983.9  107.16  4994.1  104.99  4998.8  103.64
  5001.9  101.62  5004.6  101.12  5007.9  101.62  5013.7  106.83  5019.8  108.19
  5055.7   110.1  5121.4  115.54  5172.1  118.02  5184.3  119.53  5199.2  119.67
  5229.1   121.5  5235.1   121.1    5265  122.93  5279.9  122.62  5293.1  123.25
#Mann= 6 ,-1 , 0
  4727.1      .1       0    4729     .05       0  4839.6      .1       0
  4994.1     .16       0  5001.9     .07       0  5007.9     .16       0
Bank Sta=5001.9,5007.9
XS Rating Curve= 0 ,0
Exp/Cntr=0.3,0.1

Type RM Length L Ch R = 1 ,2841    ,512,512,512
BEGIN DESCRIPTION:
SIXMILE CREEK TRIB 6.0
END DESCRIPTION:
XS GIS Cut Line= 2
      2349394.72     13210202.84      2349155.15     13210806.97
#Sta/Elev= 30
  4758.7  120.88  4827.6   117.9  4868.9  117.35  4892.1  116.16  4923.1  112.98
    4958   109.2  4977.8  108.24  4982.4  107.56  4988.9  100.92  4996.7  100.19
  4999.4   99.69  5002.7  100.19  5006.7   104.4  5021.2  103.54  5042.7  104.62
  5060.7  106.42  5066.1  106.09    5075  107.65  5090.4   107.7  5107.3  109.51
  5120.1  109.87  5128.8  111.34  5161.1  112.89  5174.1  114.38  5268.6  117.76
  5276.8  118.68  5282.2   118.1  5300.9  119.36  5354.7  121.24  5408.6  122.19
#Mann= 5 ,-1 , 0
  4758.7      .1       0  4923.1     .05       0  4977.8     .16       0
  4996.7     .07       0  5002.7     .16       0
Bank Sta=4996.7,5002.7
XS Rating Curve= 0 ,0
Exp/Cntr=0.3,0.1

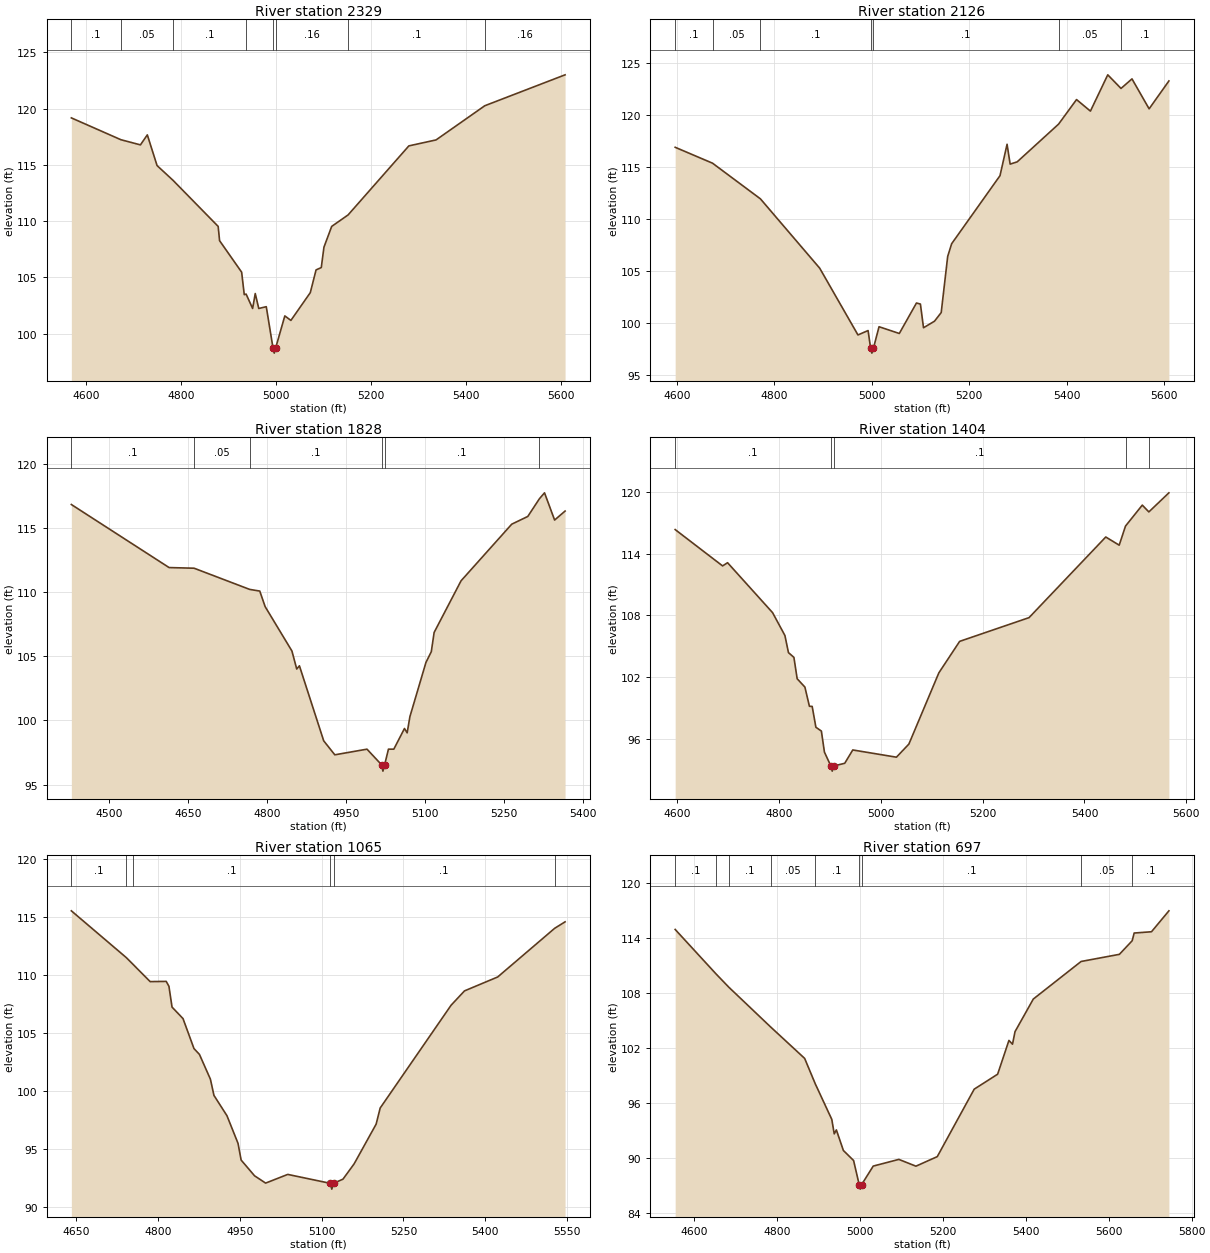
Type RM Length L Ch R = 1 ,2329    ,203,203,203
BEGIN DESCRIPTION:
SIXMILE CREEK TRIB 5.0
END DESCRIPTION:
XS GIS Cut Line= 4
      2349203.79     13210140.32      2348905.14      13210206.3
      2348797.51     13210445.89      2348950.29     13210890.36
#Sta/Elev= 30
  4569.7  119.18  4673.9  117.24    4715  116.78  4729.5  117.67    4750  114.94
  4783.5  113.63  4878.5  109.53  4881.5  108.26  4927.9  105.46  4933.4  103.46
  4937.3  103.51    4951  102.23  4956.5  103.56  4963.9  102.23  4979.7  102.39
  4993.7   98.76  4996.5   98.26  4999.7   98.76  5018.7  101.57  5031.5  101.17
  5072.3  103.64  5084.4  105.66  5095.4  105.87    5101  107.68  5117.3  109.53
  5151.8  110.55  5279.6  116.69  5336.8  117.22  5439.3  120.26  5608.2  123.01
#Mann= 8 ,-1 , 0
  4569.7      .1       0  4673.9     .05       0  4783.5      .1       0
  4937.3     .16       0  4993.7     .07       0  4999.7     .16       0
  5151.8      .1       0  5439.3     .16       0
Bank Sta=4993.7,4999.7
XS Rating Curve= 0 ,0
Exp/Cntr=0.3,0.1

Type RM Length L Ch R = 1 ,2126    ,298,298,298
BEGIN DESCRIPTION:
Mapping XS 5182af0a
END DESCRIPTION:
XS GIS Cut Line= 3
      2349073.94     13210104.76      2348804.03     13210115.78
      2348221.42     13210577.47
#Sta/Elev= 30
  4596.3  116.86    4673  115.33  4771.3   111.9    4893  105.23  4971.5   98.81
  4992.3   99.23  4997.4   97.56  5000.1   97.06  5003.4   97.56  5014.8    99.6
  5056.4   98.95  5091.6  101.88  5099.7  101.78  5106.1    99.5  5128.6  100.13
  5142.4  100.96  5155.7  106.36  5163.8  107.58  5263.1  114.13  5277.6  117.15
  5283.9  115.24  5298.4  115.46  5383.4  119.09  5420.2  121.45  5448.7  120.34
  5484.3  123.83  5511.5  122.52    5534  123.44  5569.2  120.56  5609.8  123.24
#Mann= 7 ,-1 , 0
  4596.3      .1       0    4673     .05       0  4771.3      .1       0
  4997.4     .07       0  5003.4      .1       0  5383.4     .05       0
  5511.5      .1       0
Bank Sta=4997.4,5003.4
XS Rating Curve= 0 ,0
Exp/Cntr=0.3,0.1

Type RM Length L Ch R = 1 ,1828    ,424,424,424
BEGIN DESCRIPTION:
SIXMILE CREEK TRIB 4.0
END DESCRIPTION:
XS GIS Cut Line= 3
      2349116.97     13210074.37      2348797.51     13209935.47
      2348218.21     13210050.19
#Sta/Elev= 30
  4427.9  116.81  4613.8   111.9  4661.3  111.85    4767   110.2  4786.2  110.07
  4796.4  108.86  4847.4   105.4  4856.5     104  4861.6  104.25  4907.8   98.41
  4928.9   97.32  4990.1   97.76  5017.7   96.55  5020.4   96.05  5023.7   96.55
  5030.9   97.76  5041.1   97.76  5061.4   99.37  5066.5   99.03  5071.7  100.29
  5102.2  104.51  5112.4  105.35  5117.8  106.85    5169  110.87  5265.4  115.28
  5295.9  115.88    5318  117.26  5327.7  117.72  5346.9   115.6  5366.8   116.3
#Mann= 6 ,-1 , 0
  4427.9      .1       0  4661.3     .05       0    4767      .1       0
  5017.7     .07       0  5023.7      .1       0    5318     .05       0
Bank Sta=5017.7,5023.7
XS Rating Curve= 0 ,0
Exp/Cntr=0.3,0.1

Type RM Length L Ch R = 1 ,1404    ,339,339,339
BEGIN DESCRIPTION:
SIXMILE CREEK TRIB 3.0
END DESCRIPTION:
XS GIS Cut Line= 3
      2348964.14     13209421.59      2348655.14     13209546.58
      2348044.07     13209727.12
#Sta/Elev= 30
  4595.5  116.32  4688.7   112.8  4698.5  113.11    4787  108.27  4811.2  106.06
  4818.2   104.4  4828.9  103.94  4835.3  101.87  4850.5  101.06  4859.4    99.2
  4864.8   99.19  4872.1   97.17  4882.9    96.8  4888.9   94.76  4901.5   93.42
  4904.2   92.92  4907.5   93.42  4928.8   93.68  4944.6   94.97  5030.4   94.27
  5054.9   95.54  5113.8  102.44  5154.7  105.49  5291.1  107.79  5441.9   115.6
  5468.3  114.81  5480.7  116.66  5513.7  118.69  5526.6  118.03    5566  119.88
#Mann= 5 ,-1 , 0
  4595.5      .1       0  4901.5     .07       0  4907.5      .1       0
  5480.7     .05       0  5526.6      .1       0
Bank Sta=4901.5,4907.5
XS Rating Curve= 0 ,0
Exp/Cntr=0.3,0.1

Type RM Length L Ch R = 1 ,1065    ,368,368,368
BEGIN DESCRIPTION:
SIXMILE CREEK TRIB 2.0
END DESCRIPTION:
XS GIS Cut Line= 3
      2348981.49     13209247.96      2348719.78     13209224.21
      2348085.72     13209324.35
#Sta/Elev= 30
  4641.5  115.52    4742  111.49  4754.1  110.92  4785.9  109.41  4815.3  109.43
  4820.3  109.01    4826  107.21  4846.1  106.22  4866.2  103.63  4876.2  103.13
  4896.3  100.99  4902.8   99.59  4926.6   97.84  4946.9   95.45  4952.6   94.01
  4977.2   92.65  4997.5   92.02    5038   92.77    5116      92  5118.7    91.5
    5122      92  5139.2   92.36  5159.5   93.67    5200   97.11  5207.4    98.5
  5337.3  107.37  5361.9  108.61  5422.7  109.81  5527.1  114.01  5546.2  114.57
#Mann= 6 ,-1 , 0
  4641.5      .1       0    4742     .05       0  4754.1      .1       0
    5116     .07       0    5122      .1       0  5527.1     .05       0
Bank Sta=5116,5122
XS Rating Curve= 0 ,0
Exp/Cntr=0.3,0.1

Type RM Length L Ch R = 1 ,697     ,464,464,464
BEGIN DESCRIPTION:
Mapping XS e2528ba1
END DESCRIPTION:
XS GIS Cut Line= 4
      2349057.89     13208963.24      2348696.81     13208859.08
      2348314.87     13208952.83      2347971.92     13209198.78
#Sta/Elev= 30
    4554  114.92  4652.3  110.09  4683.4  108.63  4784.7  104.28  4866.4  100.87
    4892    98.1  4931.9   94.22  4937.7   92.65  4942.9   93.08  4959.8   90.84
  4984.4   89.75  4997.9   87.13  5000.7   86.63  5003.9   87.13  5031.8   89.14
  5093.6   89.87  5134.8   89.13  5186.3   90.17  5275.4   97.52  5331.9   99.15
  5359.2  102.83  5367.8  102.42  5373.9  103.79    5418  107.34  5533.2  111.43
  5625.7  112.21  5656.5  113.69  5661.3  114.53  5703.1  114.67  5745.1  116.95
#Mann= 9 ,-1 , 0
    4554      .1       0  4652.3     .05       0  4683.4      .1       0
  4784.7     .05       0    4892      .1       0  4997.9     .07       0
  5003.9      .1       0  5533.2     .05       0  5656.5      .1       0
Bank Sta=4997.9,5003.9
XS Rating Curve= 0 ,0
Exp/Cntr=0.3,0.1

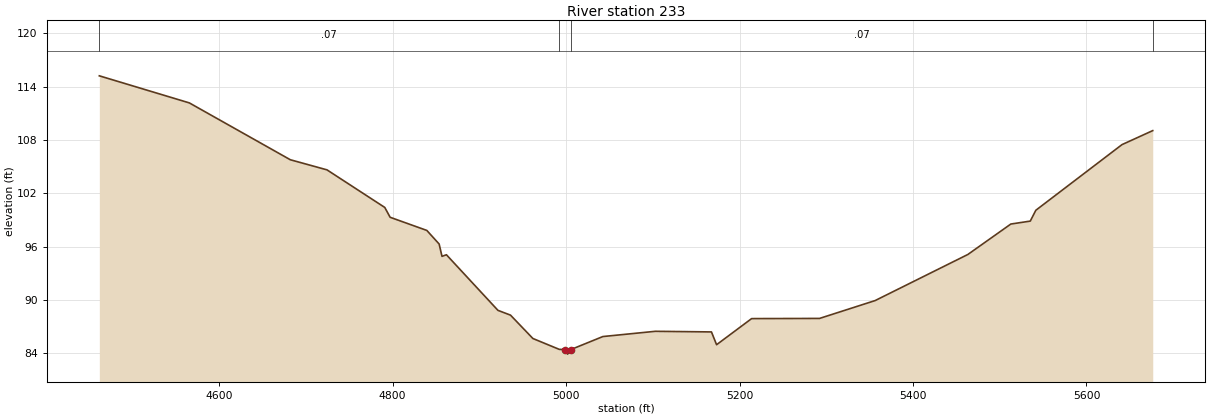
Type RM Length L Ch R = 1 ,233     ,0,0,0
BEGIN DESCRIPTION:
SIXMILE CREEK TRIB 1.0
END DESCRIPTION:
XS GIS Cut Line= 4
      2349065.21     13208632.26      2348734.51     13208421.34
      2348336.07     13208473.42      2348007.95     13208736.44
#Sta/Elev= 30
  4461.8  115.23  4565.6  112.18    4682  105.78  4724.3  104.64  4790.9  100.41
  4797.1    99.3  4839.4   97.82  4853.6   96.29  4856.9    94.9    4862   95.08
  4921.4   88.82  4935.9   88.28  4961.7   85.65    4992   84.43  4999.1   84.39
  5001.8   83.89  5005.1   84.39  5042.4   85.87  5102.9   86.46  5167.6   86.39
  5173.5   84.95  5213.9   87.89  5292.2   87.91  5356.3   89.92  5463.2   95.11
  5512.8   98.54  5535.2   98.87  5541.6  100.09  5640.9  107.48  5676.4  109.06
#Mann= 4 ,-1 , 0
  4461.8     .07       0    4992    .035       0  5005.1     .07       0
  5676.4      .1       0
Bank Sta=4999.1,5005.1
XS Rating Curve= 0 ,0
Exp/Cntr=0.3,0.1

Chan Stop Cuts=-1
Use User Specified Reach Order=0
Composite Channel Slope=5