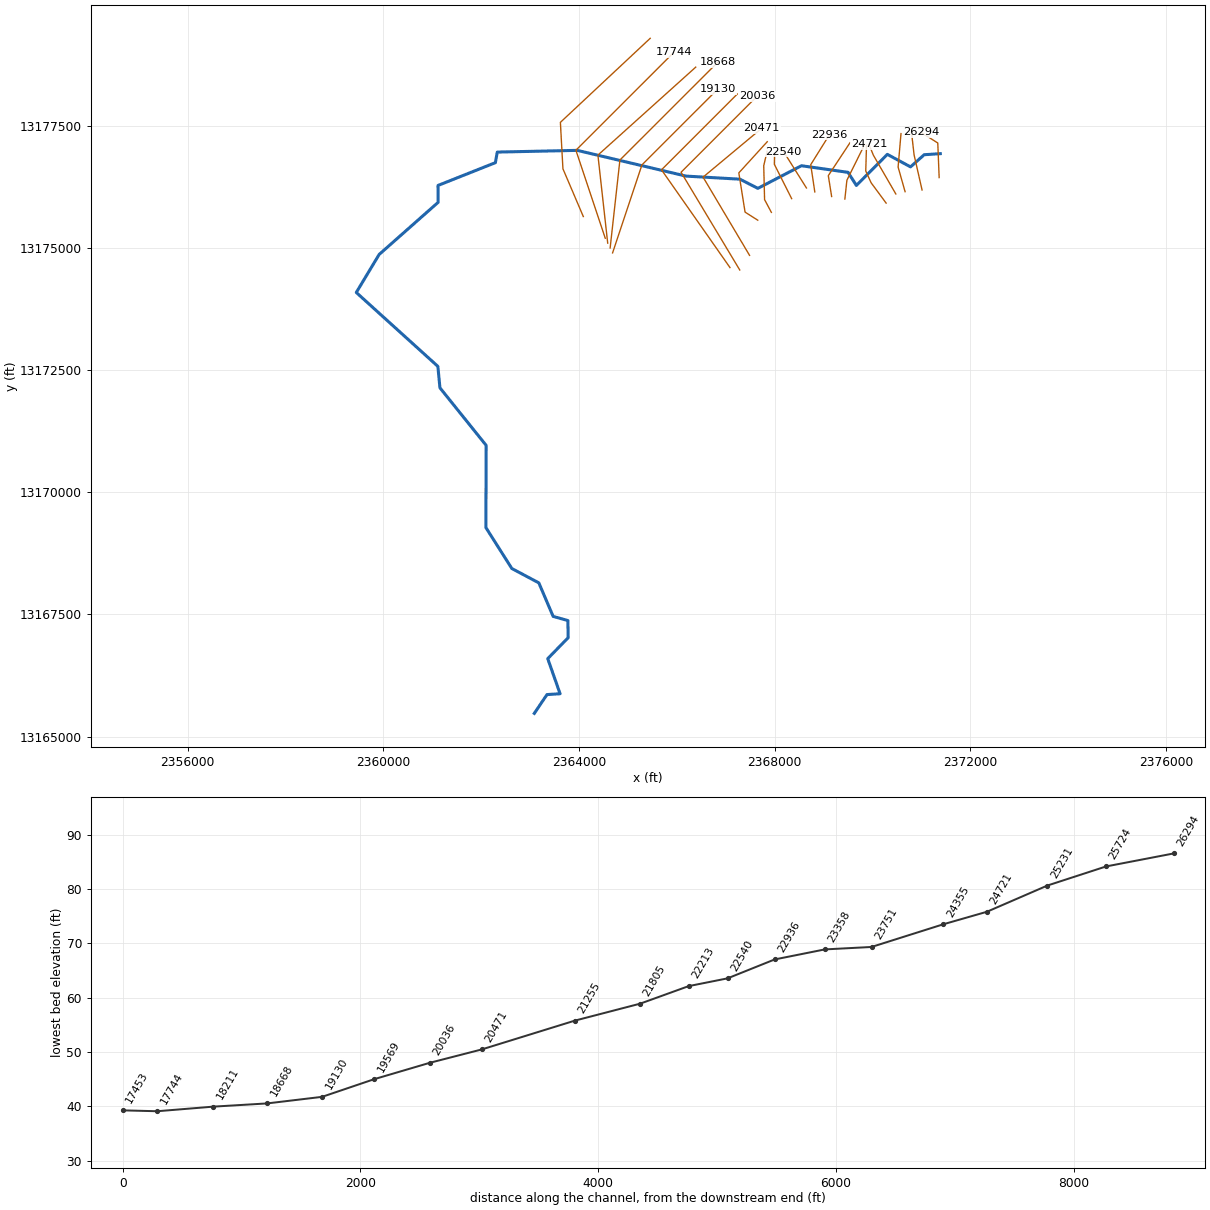
--- UNNAMED GULLY NO 8.prj (project) ---

Proj Title=UNNAMED GULLY NO 8 Base Level Engineering
Current Plan=p01
Default Exp/Contr=0.3,0.1
English Units
Geom File=g01
Flow File=f01
Plan File=p01
Y Axis Title=Elevation
X Axis Title(PF)=Main Channel Distance
X Axis Title(XS)=Station
BEGIN DESCRIPTION:
UNNAMED GULLY NO 8
END DESCRIPTION:
DSS Export Rating Curves= 0
DSS Export Rating Curve Sorted= 0
DSS Export Volume Flow Curves= 0
DXF OffsetX= 0
DXF OffsetY= 0
DXF ScaleX= 1
DXF ScaleY= 10

--- UNNAMED GULLY NO 8.p01 (plan) ---

Plan Title=Multiple Run
Short Identifier=Multiple
Geom File=g01
Flow File=f01
Subcritical Flow
K Sum by GR= 0
Std Step Tol= 0.01
Critical Tol= 0.01
Num of Std Step Trials= 20
Max Error Tol= 0.3
Flow Tol Ratio= 0.001
Split Flow NTrial= 30
Split Flow Tol= 0.02
Split Flow Ratio= 0.02
Log Output Level= 0
Friction Slope Method= 1
Unsteady Friction Slope Method= 2
Unsteady Bridges Friction Slope Method= 1
Parabolic Critical Depth
Global Vel Dist=  1 , 1 , 1
Global Log Level= 0
CheckData=True
Encroach Param= -1, 0, 0, 0
BEGIN DESCRIPTION:
Multiple Run
END DESCRIPTION:

--- UNNAMED GULLY NO 8.f01 (steady flow) ---

Flow Title=Multiple
Program Version=4.10
Number of Profiles= 7
Profile Names=10-year,25-year,50-year,1pct_min,100-year,1pct_plu,500-year
River Rch & RM=UNNAMED GULLY NO,Reach-1         ,26294
     356     482     582     516     697     943    1009
River Rch & RM=UNNAMED GULLY NO,Reach-1         ,22540
     644     893    1097     985    1332    1802    1982
Boundary for River Rch & Prof#=UNNAMED GULLY NO,Reach-1         , 1
Up Type= 0
Dn Type= 3
Dn Slope=0.0008
Boundary for River Rch & Prof#=UNNAMED GULLY NO,Reach-1         , 2
Up Type= 0
Dn Type= 3
Dn Slope=0.0008
Boundary for River Rch & Prof#=UNNAMED GULLY NO,Reach-1         , 3
Up Type= 0
Dn Type= 3
Dn Slope=0.0008
Boundary for River Rch & Prof#=UNNAMED GULLY NO,Reach-1         , 4
Up Type= 0
Dn Type= 3
Dn Slope=0.0008
Boundary for River Rch & Prof#=UNNAMED GULLY NO,Reach-1         , 5
Up Type= 0
Dn Type= 3
Dn Slope=0.0008
Boundary for River Rch & Prof#=UNNAMED GULLY NO,Reach-1         , 6
Up Type= 0
Dn Type= 3
Dn Slope=0.0008
Boundary for River Rch & Prof#=UNNAMED GULLY NO,Reach-1         , 7
Up Type= 0
Dn Type= 3
Dn Slope=0.0008
DSS Import GetInterval= 0
DSS Import GetPeak= 0
DSS Import FillOption= 0

--- UNNAMED GULLY NO 8.g01 (geometry) ---

Geom Title=Existing Conditions
Program Version=4.10

River Reach=UNNAMED GULLY NO,Reach-1
Reach XY= 30
      2371387.72     13176926.85      2371058.39     13176905.13
       2370779.4      13176656.3      2370304.91     13176912.61
      2369672.29     13176276.82       2369501.6     13176544.62
      2368548.37     13176679.98       2367657.8     13176216.95
      2367291.82     13176404.89        2366188.      13176467.9
      2363965.71     13176994.25      2362330.19     13176959.13
      2362291.01     13176742.39       2361118.2     13176276.38
      2361120.57     13175930.42      2359915.58     13174865.12
      2359447.72     13174086.86      2361115.37      13172575.8
      2361157.72     13172136.86       2362102.4     13170960.11
      2362097.72     13169276.85      2362628.08     13168440.03
      2363180.02     13168146.33      2363472.27     13167460.57
      2363774.25     13167375.42      2363779.07     13167024.27
      2363361.81     13166596.24       2363614.5     13165878.25
      2363346.43     13165861.35       2363087.3     13165476.77

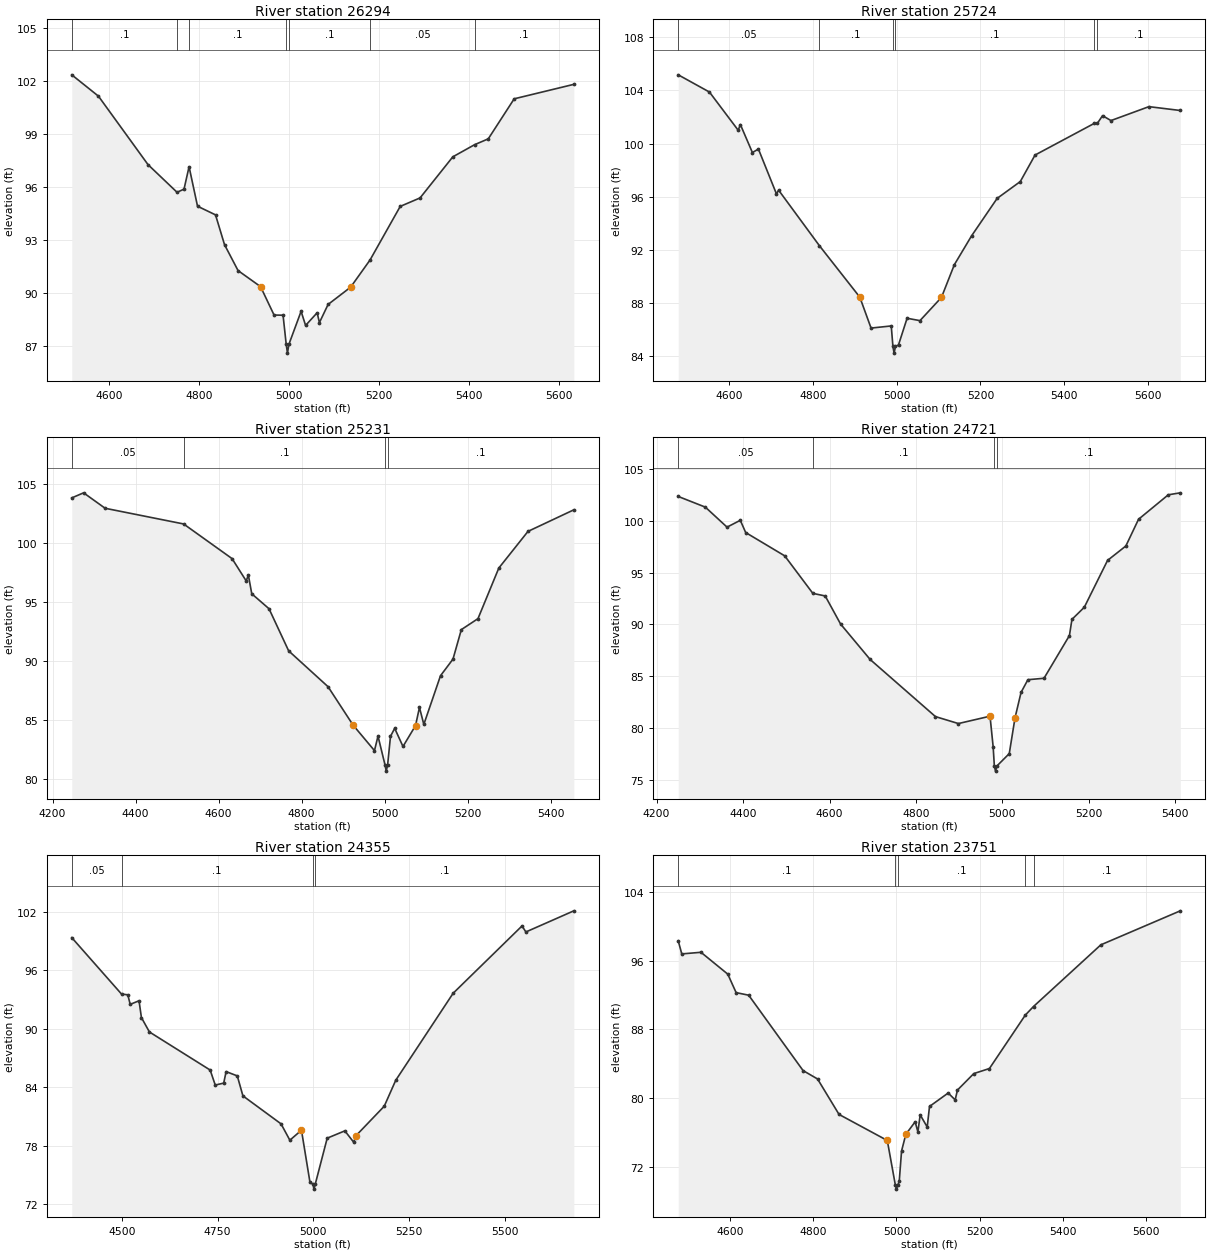
Type RM Length L Ch R = 1 ,26294   ,570,570,570
BEGIN DESCRIPTION:
UNNAMED GULLY NO 8 17.0
END DESCRIPTION:
XS GIS Cut Line= 3
      2371364.48      13176437.6      2371336.27     13177145.01
      2370991.94     13177363.74
#Sta/Elev= 30
  4516.5  102.37  4575.8  101.16  4685.9   97.28  4750.5   95.71    4766   95.89
  4777.2   97.16    4796   94.92    4836   94.43    4856   92.74  4886.1   91.27
  4936.1   90.36  4966.1   88.75  4986.1   88.74  4993.1   87.09  4995.9   86.59
  4999.1   87.09  5026.2   88.96  5036.2   88.16  5061.9   88.88  5066.9   88.32
  5086.2   89.35  5136.3   90.33  5179.4   91.87  5246.5   94.91  5290.6   95.39
  5363.4   97.72  5411.9   98.41  5442.2   98.74  5499.8  101.01  5632.4  101.83
#Mann= 7 ,-1 , 0
  4516.5      .1       0  4750.5     .05       0  4777.2      .1       0
  4993.1     .07       0  4999.1      .1       0  5179.4     .05       0
  5411.9      .1       0
Bank Sta=4936.1,5136.3
XS Rating Curve= 0 ,0
Exp/Cntr=0.3,0.1

Type RM Length L Ch R = 1 ,25724   ,493,493,493
BEGIN DESCRIPTION:
Mapping XS 5e49b44f
END DESCRIPTION:
XS GIS Cut Line= 3
      2371014.86     13176184.24      2370851.68     13176902.95
      2370799.59      13177361.3
#Sta/Elev= 30
  4478.7  105.18  4553.2  103.88  4621.8     101    4627  101.43  4655.7   99.32
  4670.1   99.58  4713.1    96.2  4718.3   96.48  4815.7   92.29  4912.1   88.41
  4938.9   86.08  4987.1   86.24  4991.1   84.69  4993.9   84.19  4997.1   84.69
  5004.4   84.81  5024.9   86.82  5055.6   86.64  5106.9   88.39  5137.7   90.86
  5178.7   93.03  5239.8   95.86  5295.1   97.13  5330.3   99.13  5471.2  101.51
  5478.8  101.51  5491.4   102.1  5511.5  101.73  5602.1  102.78    5677  102.49
#Mann= 6 ,-1 , 0
  4478.7     .05       0  4815.7      .1       0  4991.1     .07       0
  4997.1      .1       0  5471.2     .05       0  5478.8      .1       0
Bank Sta=4912.1,5106.9
XS Rating Curve= 0 ,0
Exp/Cntr=0.3,0.1

Type RM Length L Ch R = 1 ,25231   ,510,510,510
BEGIN DESCRIPTION:
Mapping XS 39ba5536
END DESCRIPTION:
XS GIS Cut Line= 3
      2370667.65     13176149.47      2370525.29     13176652.95
      2370584.32     13177336.99
#Sta/Elev= 30
  4246.4  103.85  4274.9  104.28  4326.8  102.97  4515.9  101.64  4632.7    98.7
  4666.7   96.81  4671.9   97.31  4680.1   95.72  4721.7   94.45    4769   90.88
  4863.9   87.84  4924.1   84.59  4975.8   82.42  4984.3   83.65  5001.4   81.18
  5004.1   80.68  5007.4   81.18  5014.4   83.63  5024.5   84.31  5044.5   82.77
  5074.7   84.54  5084.2   86.08  5094.7   84.64  5134.9   88.77    5165   90.18
  5185.1   92.68  5225.2   93.61  5275.4    97.9  5345.7  101.01  5456.2  102.84
#Mann= 4 ,-1 , 0
  4246.4     .05       0  4515.9      .1       0  5001.4     .07       0
  5007.4      .1       0
Bank Sta=4924.1,5074.7
XS Rating Curve= 0 ,0
Exp/Cntr=0.3,0.1

Type RM Length L Ch R = 1 ,24721   ,366,366,366
BEGIN DESCRIPTION:
Mapping XS 84838b83
END DESCRIPTION:
XS GIS Cut Line= 3
      2370478.42     13176102.58      2370020.08     13176894.27
      2369926.67     13177122.61
#Sta/Elev= 30
    4250  102.34  4312.7  101.31  4362.9   99.38  4393.6  100.04    4406   98.86
  4496.3   96.61  4561.4   92.99    4590   92.74  4625.6   90.03    4694   86.61
  4845.1    81.1  4898.1   80.43  4971.3   81.14  4978.5    78.2  4981.3   76.34
    4984   75.84  4987.3   76.34  5015.8   77.53  5029.1   80.98  5043.1   83.44
  5058.9   84.66  5096.2    84.8    5155   88.92  5160.8   90.48  5189.4   91.65
  5243.2   96.17  5285.5   97.56  5314.9  100.14  5383.7   102.5  5411.5  102.69
#Mann= 4 ,-1 , 0
    4250     .05       0  4561.4      .1       0  4981.3     .07       0
  4987.3      .1       0
Bank Sta=4971.3,5029.1
XS Rating Curve= 0 ,0
Exp/Cntr=0.3,0.1

Type RM Length L Ch R = 1 ,24355   ,604,604,604
BEGIN DESCRIPTION:
Mapping XS 2e1558b5
END DESCRIPTION:
XS GIS Cut Line= 4
      2370280.52     13175915.06       2369973.2     13176331.77
      2369863.83     13176571.35      2369879.44     13177102.18
#Sta/Elev= 30
  4368.7   99.35  4498.7   93.56  4515.2   93.48  4521.4    92.5  4544.5   92.87
  4550.7   91.15  4571.6   89.67  4730.4   85.76  4743.7   84.22  4765.8   84.42
  4772.1    85.6  4801.3   85.16    4816   83.11  4915.6   80.24  4938.7   78.56
    4969   79.59    4991    74.3    4999   74.04  5001.7   73.54    5005   74.04
  5036.3   78.77  5082.4   79.52  5105.4   78.36  5111.9   79.04  5185.4   82.05
  5215.4   84.71  5365.4   93.64  5545.5  100.55  5555.5   99.93  5680.9   102.1
#Mann= 4 ,-1 , 0
  4368.7     .05       0  4498.7      .1       0    4999     .07       0
    5005      .1       0
Bank Sta=4969,5111.9
XS Rating Curve= 0 ,0
Exp/Cntr=0.3,0.1

Type RM Length L Ch R = 1 ,23751   ,393,393,393
BEGIN DESCRIPTION:
Mapping XS 0292d01d
END DESCRIPTION:
XS GIS Cut Line= 3
      2369436.75     13175998.43      2369478.41     13176383.85
      2369842.88     13177117.99
#Sta/Elev= 30
  4475.3   98.35  4483.8   96.82    4530   97.01  4594.4   94.46  4614.5    92.3
  4644.7      92  4775.5    83.2  4810.3   82.22    4862   78.08    4978   75.04
  4997.3   69.86    5000   69.36  5003.3   69.86  5006.7   70.26  5012.3   73.81
  5022.6   75.76    5045   77.22  5051.6   76.04  5057.1   78.03    5074   76.61
  5079.5   79.01  5124.4   80.58  5141.2   79.78  5146.8   80.93    5186   82.85
  5223.6   83.44  5309.9   89.68  5329.6   90.68  5491.5   97.88  5682.6  101.85
#Mann= 5 ,-1 , 0
  4475.3      .1       0  4997.3     .07       0  5003.3      .1       0
  5309.9     .05       0  5329.6      .1       0
Bank Sta=4978,5022.6
XS Rating Curve= 0 ,0
Exp/Cntr=0.3,0.1

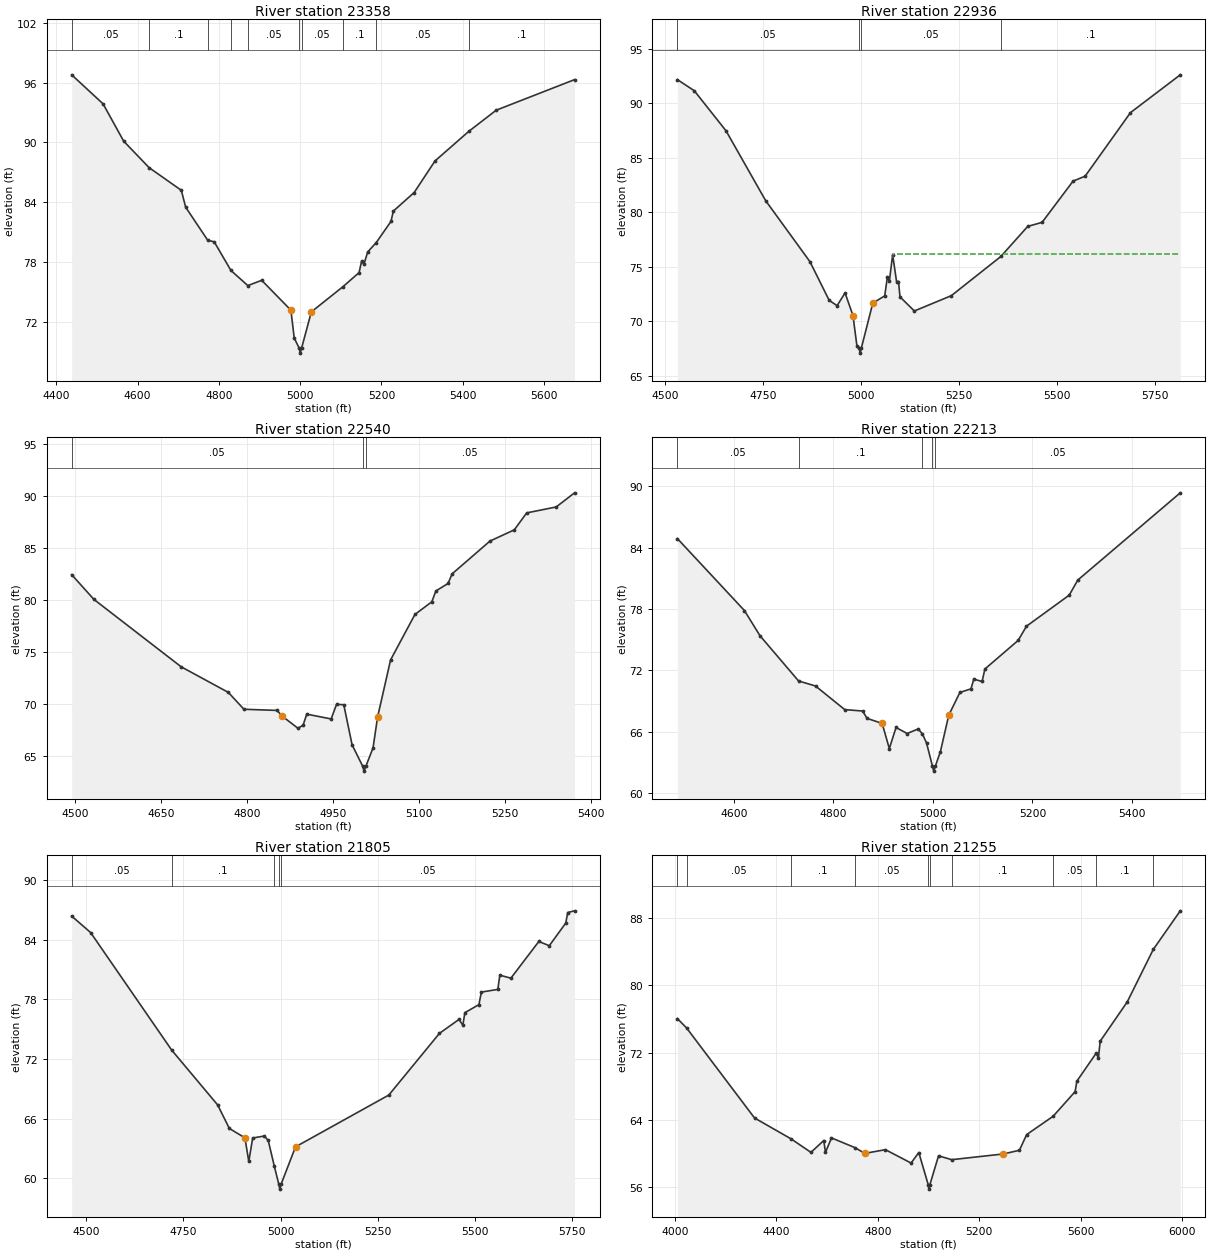
Type RM Length L Ch R = 1 ,23358   ,422,422,422
BEGIN DESCRIPTION:
Mapping XS ed381820
END DESCRIPTION:
XS GIS Cut Line= 3
      2369165.92      13176050.5       2369098.2      13176477.6
      2369540.94     13177149.51
#Sta/Elev= 30
    4438   96.77  4515.3   93.86  4565.9   90.13  4628.4   87.48  4707.7   85.21
  4718.4   83.52  4772.7   80.21  4788.7   80.05  4829.7   77.19  4871.3   75.67
  4905.5    76.2  4977.3   73.21  4985.5   70.42  4997.6   69.41  5000.3   68.91
  5003.6   69.41  5027.6   73.04    5105   75.55    5145   76.97  5151.1   78.09
  5157.1   77.81  5166.2   79.04  5187.1   79.97  5223.4   82.09  5229.4   83.13
  5280.6   84.99  5331.8   88.15  5415.2   91.12  5482.4   93.23  5675.1   96.29
#Mann= 10 ,-1 , 0
    4438     .05       0  4628.4      .1       0  4772.7     .05       0
  4829.7      .1       0  4871.3     .05       0  4997.6     .03       0
  5003.6     .05       0    5105      .1       0  5187.1     .05       0
  5415.2      .1       0
Bank Sta=4977.3,5027.6
XS Rating Curve= 0 ,0
Exp/Cntr=0.3,0.1

Type RM Length L Ch R = 1 ,22936   ,396,396,396
BEGIN DESCRIPTION:
Mapping XS db590dd5
END DESCRIPTION:
XS GIS Cut Line= 3
      2368822.16     13176144.29      2368738.83     13176701.56
      2369119.02     13177310.91
#Sta/Elev= 30
  4531.9   92.18  4574.9   91.16  4655.8   87.48  4756.9   81.06  4869.7   75.46
  4918.7   71.91  4938.9   71.42  4959.2   72.59  4979.4   70.51  4989.5   67.71
    4995   67.56  4997.7   67.06    5001   67.56  5029.9   71.65  5060.3   72.32
  5067.2   74.08  5072.2   73.67  5080.5    76.1  5090.5   73.63  5095.4   73.63
  5099.2   72.23  5135.8   70.93  5230.2   72.34  5356.4   75.94  5424.8    78.7
  5461.4   79.07  5540.4   82.86  5571.1   83.31  5686.7   89.15  5813.6   92.62
#Mann= 4 ,-1 , 0
  4531.9     .05       0    4995     .03       0    5001     .05       0
  5356.4      .1       0
#XS Ineff= 2 , 0
                         5081.82           76.15
Permanent Ineff=
       F       F
Bank Sta=4979.4,5029.9
XS Rating Curve= 0 ,0
Exp/Cntr=0.3,0.1

Type RM Length L Ch R = 1 ,22540   ,327,327,327
BEGIN DESCRIPTION:
UNNAMED GULLY NO 8 16.0
END DESCRIPTION:
XS GIS Cut Line= 2
      2368650.92     13176225.33       2368184.8     13176967.49
#Sta/Elev= 30
  4494.6   82.48  4533.3    80.1  4685.3   73.62  4767.7   71.15  4794.8   69.53
  4852.5   69.42  4861.9   68.85    4889    67.7  4897.9      68  4904.3   69.06
  4946.8    68.6  4956.2      70  4968.8   69.97  4983.3   66.11  5001.5   64.08
  5004.2   63.58  5007.5   64.08  5019.8   65.81  5027.8    68.8  5050.4   74.28
  5092.8   78.65  5122.3   79.87  5129.3   80.91  5150.5   81.63  5157.7   82.56
  5223.6   85.71    5266   86.79  5287.6   88.42    5339   88.99    5371   90.35
#Mann= 3 ,-1 , 0
  4494.6     .05       0  5001.5     .03       0  5007.5     .05       0
Bank Sta=4861.9,5027.8
XS Rating Curve= 0 ,0
Exp/Cntr=0.3,0.1

Type RM Length L Ch R = 1 ,22213   ,408,408,408
BEGIN DESCRIPTION:
Mapping XS 9aa2fd55
END DESCRIPTION:
XS GIS Cut Line= 3
      2368348.84     13176006.58      2367994.69     13176709.68
      2367999.87     13176932.76
#Sta/Elev= 30
  4486.7    84.9  4621.4   77.86  4652.6    75.4  4730.2   70.97  4764.2   70.48
  4822.9   68.17    4859   68.03  4867.7   67.31  4898.1   66.82  4912.5   64.36
    4926   66.42  4948.3   65.83  4970.6   66.28  4979.1   65.78  4987.3    64.9
  4999.1   62.65  5001.8   62.15  5005.1   62.65  5015.2   64.07  5031.9   67.62
  5054.3   69.85  5076.6    70.2  5082.2   71.15  5098.9   70.92  5104.5   72.14
  5171.4   74.94  5188.1   76.33    5274   79.37  5291.1   80.84  5497.1   89.38
#Mann= 5 ,-1 , 0
  4486.7     .05       0  4730.2      .1       0  4979.1     .05       0
  4999.1     .03       0  5005.1     .05       0
Bank Sta=4898.1,5031.9
XS Rating Curve= 0 ,0
Exp/Cntr=0.3,0.1

Type RM Length L Ch R = 1 ,21805   ,550,550,550
BEGIN DESCRIPTION:
UNNAMED GULLY NO 8 15.0
END DESCRIPTION:
XS GIS Cut Line= 4
      2367934.13     13175726.19      2367795.27     13175986.57
       2367777.9     13176681.01      2367847.36     13176976.19
#Sta/Elev= 30
  4462.9   86.37  4511.5   84.72    4720    72.9  4838.3   67.38  4868.3   65.02
  4908.3   64.08  4918.3    61.7  4928.3   64.06  4958.3   64.26  4968.3   63.81
  4983.9   61.23  4995.4   59.42  4998.1   58.92  5001.4   59.42  5038.4   63.17
  5278.4   68.38  5408.5   74.58  5458.7   75.98  5468.7    75.4  5473.9   76.66
    5510   77.47  5516.3   78.73  5558.6      79  5563.8   80.43  5592.2   80.13
  5664.1   83.82  5690.9   83.39  5733.3   85.67  5738.4   86.73  5755.9    86.9
#Mann= 5 ,-1 , 0
  4462.9     .05       0    4720      .1       0  4983.9     .05       0
  4995.4     .03       0  5001.4     .05       0
Bank Sta=4908.3,5038.4
XS Rating Curve= 0 ,0
Exp/Cntr=0.3,0.1

Type RM Length L Ch R = 1 ,21255   ,784,784,784
BEGIN DESCRIPTION:
UNNAMED GULLY NO 8 14.0
END DESCRIPTION:
XS GIS Cut Line= 4
      2367655.97     13175565.57      2367396.24     13175730.85
      2367268.76     13176533.52      2367849.53     13177170.94
#Sta/Elev= 30
  4009.4   76.06  4045.6   74.95  4313.4   64.25  4457.3   61.77    4536   60.16
  4586.6   61.57  4593.2   60.16    4617   61.88  4709.6   60.72  4748.6   60.04
  4829.6   60.48  4930.9   58.89  4961.2   60.14  4998.7   56.29  5001.5   55.79
  5004.7   56.29  5039.1   59.75    5091   59.29  5294.6   59.97  5358.1   60.41
  5386.5   62.27  5490.9   64.45  5577.7   67.38  5584.5   68.62  5660.3   71.93
  5669.6    71.4  5676.4   73.37  5783.1   78.04  5885.8   84.28  5992.3   88.87
#Mann= 10 ,-1 , 0
  4009.4      .1       0  4045.6     .05       0  4457.3      .1       0
  4709.6     .05       0  4998.7     .03       0  5004.7     .05       0
    5091      .1       0  5490.9     .05       0  5660.3      .1       0
  5885.8     .05       0
Bank Sta=4748.6,5294.6
XS Rating Curve= 0 ,0
Exp/Cntr=0.3,0.1

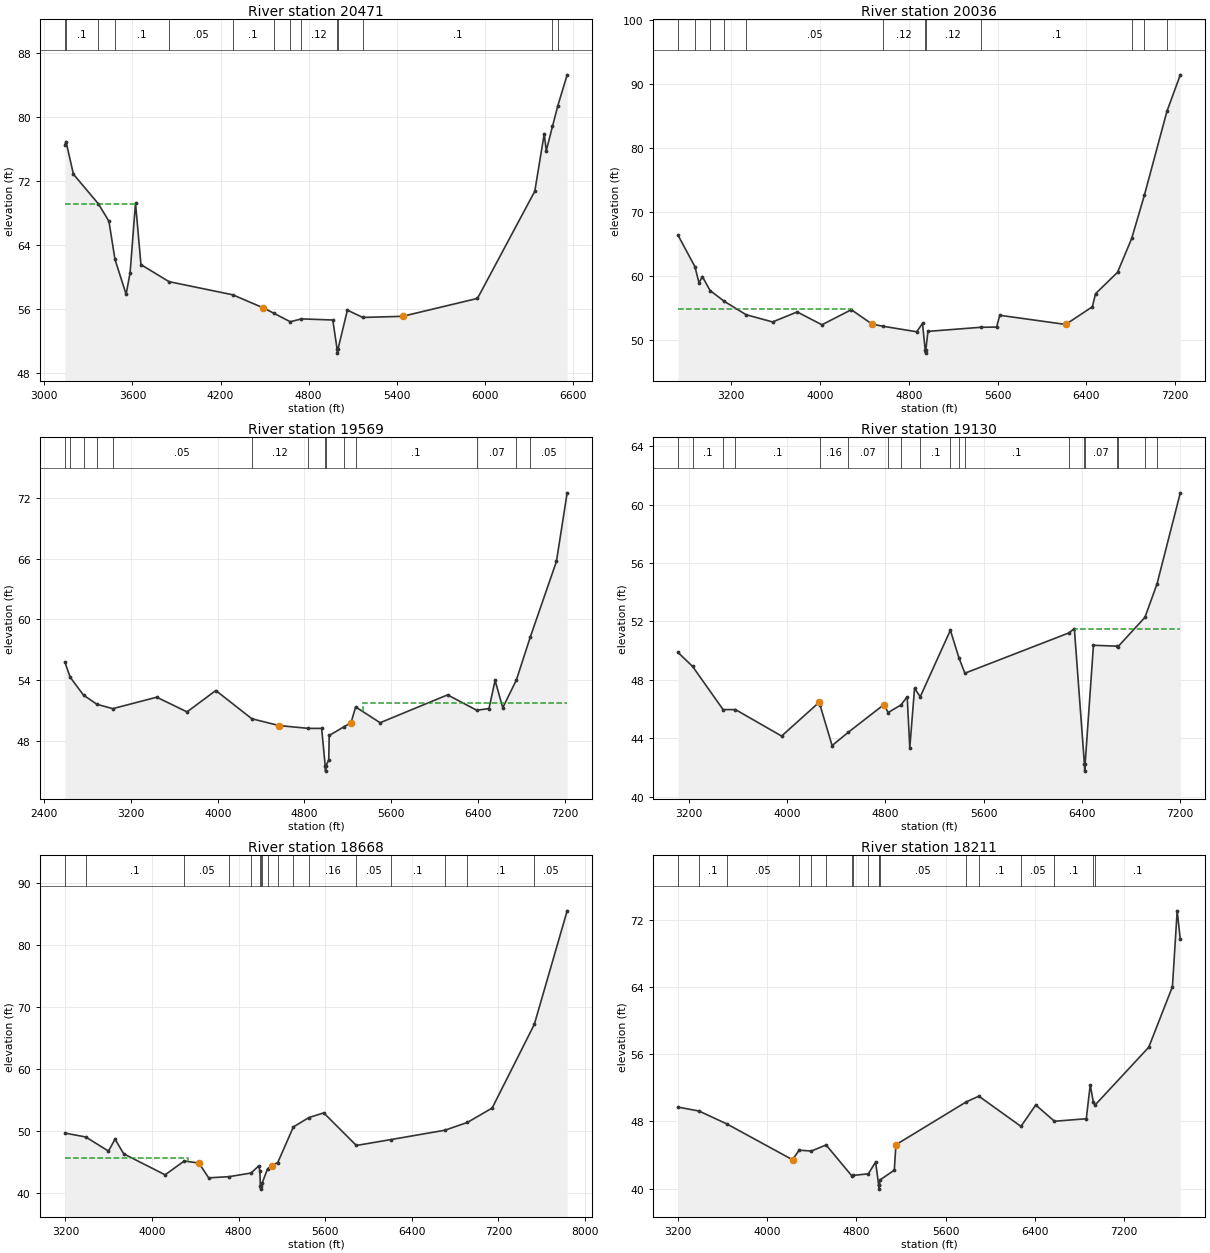
Type RM Length L Ch R = 1 ,20471   ,435,435,435
BEGIN DESCRIPTION:
UNNAMED GULLY NO 8 13.0
END DESCRIPTION:
XS GIS Cut Line= 3
      2367487.71     13174846.87      2366537.72     13176446.85
      2367737.71     13177446.84
#Sta/Elev= 30
  3139.6    76.5  3147.2   76.92  3197.7   72.84  3367.3   69.15  3439.7   66.96
  3480.9    62.2  3556.6   57.84  3583.8   60.51  3620.8   69.23  3657.9   61.54
  3849.4   59.41  4283.5   57.77  4488.7   56.16  4562.3   55.48  4675.3    54.4
  4751.6   54.76  4965.3   54.62  4994.5   50.98  4997.2   50.48  5000.5   50.98
  5064.8   55.85  5169.7   54.94    5441   55.08  5951.3   57.32  6341.8   70.71
  6406.2   77.89  6419.9   75.77  6462.3   78.81  6498.5   81.38  6562.4   85.26
#Mann= 14 ,-1 , 0
  3139.6     .05       0  3147.2      .1       0  3367.3     .05       0
  3480.9      .1       0  3849.4     .05       0  4283.5      .1       0
  4562.3     .12       0  4675.3      .1       0  4751.6     .12       0
  4994.5     .07       0  5000.5     .12       0  5169.7      .1       0
  6462.3     .05       0  6498.5      .1       0
#XS Ineff= 2 , 0
         3622.73   69.17
Permanent Ineff=
       F       F
Bank Sta=4488.7,5441
XS Rating Curve= 0 ,0
Exp/Cntr=0.3,0.1

Type RM Length L Ch R = 1 ,20036   ,467,467,467
BEGIN DESCRIPTION:
UNNAMED GULLY NO 8 12.0
END DESCRIPTION:
XS GIS Cut Line= 3
       2367287.7     13174546.89      2366087.72     13176546.85
      2367637.74     13178096.88
#Sta/Elev= 30
  2721.4    66.4  2873.7   61.49  2909.9   58.99    2941   59.96  3009.5   57.79
  3139.3   56.09    3334   54.02  3572.7   52.89  3794.3   54.45  4017.8   52.45
  4282.1    54.8  4470.6   52.54  4564.6   52.23    4871   51.36  4923.5   52.67
  4947.7   48.53  4950.5   48.03  4953.7   48.53  4972.1   51.42  5449.2   52.06
  5591.1   52.09  5619.4   53.93  6213.4    52.5  6453.8   55.26  6482.1   57.29
  6680.1   60.62    6808   65.91  6922.4   72.66  7125.5   85.73  7245.8   91.41
#Mann= 12 ,-1 , 0
  2721.4     .16       0  2873.7      .1       0  3009.5     .05       0
  3139.3      .1       0    3334     .05       0  4564.6     .12       0
  4947.7     .07       0  4953.7     .12       0  5449.2      .1       0
    6808     .05       0  6922.4      .1       0  7125.5     .05       0
#XS Ineff= 2 , 0
         4284.09   54.87
Permanent Ineff=
       F       F
Bank Sta=4470.6,6213.4
XS Rating Curve= 0 ,0
Exp/Cntr=0.3,0.1

Type RM Length L Ch R = 1 ,19569   ,439,439,439
BEGIN DESCRIPTION:
UNNAMED GULLY NO 8 11.0
END DESCRIPTION:
XS GIS Cut Line= 3
      2367087.73     13174596.84      2365687.72     13176596.85
      2367237.75     13178146.89
#Sta/Elev= 30
    2590   55.79  2638.2    54.3  2762.2   52.52  2885.4   51.62  3031.4   51.19
  3437.1   52.32  3716.9   50.87    3982   52.98  4314.7   50.19  4565.3   49.52
  4836.6   49.24  4958.5   49.24  4991.7   45.52  4994.5   45.02  4997.7   45.52
  5023.9   46.14  5028.3   48.54  5164.5    49.4  5229.3   49.79    5272   51.36
    5498    49.8  6120.3   52.55  6389.7   51.03  6502.1    51.2  6558.7   53.97
  6629.4   51.28  6754.3      54  6883.7   58.27  7124.4   65.72  7223.4    72.5
#Mann= 14 ,-1 , 0
    2590     .16       0  2638.2      .1       0  2762.2     .05       0
  2885.4      .1       0  3031.4     .05       0  4314.7     .12       0
  4836.6     .16       0  4991.7     .07       0  4997.7     .16       0
  5164.5     .05       0    5272      .1       0  6389.7     .07       0
  6754.3      .1       0  6883.7     .05       0
#XS Ineff= 2 , 0
                         5344.32           51.72
Permanent Ineff=
       F       F
Bank Sta=4565.3,5229.3
XS Rating Curve= 0 ,0
Exp/Cntr=0.3,0.1

Type RM Length L Ch R = 1 ,19130   ,462,462,462
BEGIN DESCRIPTION:
UNNAMED GULLY NO 8 10.0
END DESCRIPTION:
XS GIS Cut Line= 3
      2364687.73      13174896.9      2365287.72     13176696.85
      2366837.75     13178246.89
#Sta/Elev= 30
  3112.3   49.88    3231   48.92    3479   45.97    3580   45.97  3955.5   44.16
  4261.2   46.47  4269.4   46.25  4366.6   43.51  4500.1   44.43  4788.3   46.31
  4822.7   45.77  4927.9   46.29    4978   46.85  4999.1   43.35  5037.9   47.43
  5084.3   46.85  5329.7    51.4  5400.1   49.49  5448.1   48.46  6292.7   51.21
    6339   51.51  6420.8   42.26  6423.6   41.76  6426.8   42.26  6494.5   50.37
    6686   50.31  6690.5   50.24  6913.7   52.28  7011.8   54.56  7201.7    60.8
#Mann= 19 ,-1 , 0
  3112.3     .05       0    3231      .1       0    3479     .05       0
    3580      .1       0  4269.4     .16       0  4500.1     .07       0
  4822.7     .12       0  4927.9     .16       0  5084.3      .1       0
  5329.7     .16       0  5400.1     .05       0  5448.1      .1       0
  6292.7     .07       0  6420.8     .07       0  6426.8     .07       0
    6686     .12       0  6690.5     .07       0  6913.7      .1       0
  7011.8     .05       0
#XS Ineff= 2 , 0
       0                 6340.91       0   51.51
Permanent Ineff=
       F       T
Bank Sta=4261.2,4788.3
XS Rating Curve= 0 ,0
Exp/Cntr=0.3,0.1

Type RM Length L Ch R = 1 ,18668   ,457,457,457
BEGIN DESCRIPTION:
UNNAMED GULLY NO 8 9.0
END DESCRIPTION:
XS GIS Cut Line= 3
      2364637.72     13174996.83      2364837.72     13176796.85
       2366837.7     13178796.84
#Sta/Elev= 30
  3195.7    49.6  3388.3   48.97  3598.2   46.69  3658.6   48.62    3739   46.25
  4121.4   42.86  4297.8   45.09  4433.3   44.76  4523.8   42.37  4715.2   42.57
  4914.8   43.15  4986.7    44.3  4996.7   43.47  5001.3   41.05    5004   40.55
  5007.3   41.05    5018   41.54  5067.8   43.83  5105.8   44.34    5162   44.84
    5306   50.59    5450   52.11  5586.6   52.86  5887.8    47.6  6204.1   48.54
  6705.3   50.06  6912.8   51.31  7142.3   53.64  7531.6   67.14  7835.2   85.48
#Mann= 17 ,-1 , 0
  3195.7     .05       0  3388.3      .1       0  4297.8     .05       0
  4715.2     .07       0  4914.8      .1       0  5001.3     .07       0
  5007.3      .1       0    5018     .16       0  5067.8      .1       0
    5162     .16       0    5306     .05       0    5450     .16       0
  5887.8     .05       0  6204.1      .1       0  6705.3     .12       0
  6912.8      .1       0  7531.6     .05       0
#XS Ineff= 2 , 0
         4331.09   45.54
Permanent Ineff=
       F       F
Bank Sta=4433.3,5105.8
XS Rating Curve= 0 ,0
Exp/Cntr=0.3,0.1

Type RM Length L Ch R = 1 ,18211   ,467,467,467
BEGIN DESCRIPTION:
UNNAMED GULLY NO 8 8.0
END DESCRIPTION:
XS GIS Cut Line= 3
      2364587.72     13175096.85      2364387.72     13176896.85
      2366387.72     13178696.85
#Sta/Elev= 30
  3202.6    49.7  3389.7   49.24  3641.9   47.69  4228.9   43.44  4287.6   44.58
  4397.6   44.48  4529.6    45.2  4761.3   41.51  4771.5   41.58  4907.9   41.77
  4973.4   43.17  5000.6   40.45  5003.4   39.95  5006.6   40.45  5014.8   41.06
  5141.1   42.21  5155.3   45.23  5786.7   50.33  5898.7      51  6276.5   47.41
  6408.7   49.96  6576.3   48.02  6861.7   48.32  6897.2   52.36    6925   50.26
    6939   49.93  7421.5   56.82  7633.8   64.02  7676.4   73.04  7704.4   69.65
#Mann= 18 ,-1 , 0
  3202.6     .05       0  3389.7      .1       0  3641.9     .05       0
  4287.6      .1       0  4397.6     .05       0  4529.6     .12       0
  4761.3     .05       0  4771.5     .12       0  4907.9     .05       0
  5000.6    .035       0  5006.6     .05       0  5014.8     .05       0
  5786.7     .16       0  5898.7      .1       0  6276.5     .05       0
  6576.3      .1       0    6925     .12       0    6939      .1       0
Bank Sta=4228.9,5155.3
XS Rating Curve= 0 ,0
Exp/Cntr=0.3,0.1

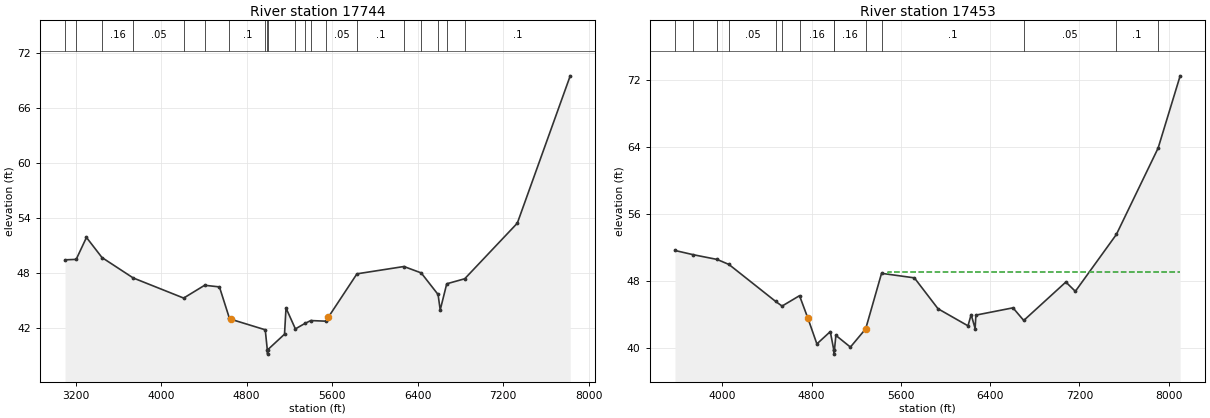
Type RM Length L Ch R = 1 ,17744   ,291,291,291
BEGIN DESCRIPTION:
UNNAMED GULLY NO 8 7.0
END DESCRIPTION:
XS GIS Cut Line= 3
      2364537.74     13175196.81      2363937.72     13176996.85
      2365937.69     13178996.83
#Sta/Elev= 30
  3101.8   49.42    3206   49.47  3302.1   51.87  3447.5   49.67  3739.2   47.44
  4211.5   45.24  4407.7   46.64    4546   46.46  4638.6   43.06  4651.4   42.93
  4974.6   41.77  4993.6   39.61  4996.3   39.11  4999.6   39.61  5154.8   41.29
  5168.9   44.15  5256.6   41.87  5345.1   42.46  5400.6   42.78  5546.8   42.71
  5564.9   43.15  5832.6   47.89  6272.1   48.69  6433.6   47.99  6591.3   45.63
  6611.4   43.94  6672.3    46.8  6840.6   47.35  7332.7   53.43  7827.6   69.54
#Mann= 20 ,-1 , 0
  3101.8     .05       0    3206      .1       0  3447.5     .16       0
  3739.2     .05       0  4211.5      .1       0  4407.7     .12       0
  4638.6      .1       0  4974.6     .16       0  4993.6     .07       0
  4999.6     .16       0  5256.6      .1       0  5345.1     .05       0
  5400.6      .1       0  5546.8     .05       0  5832.6      .1       0
  6272.1     .05       0  6433.6      .1       0  6591.3     .12       0
  6672.3      .1       0  6840.6      .1       0
Bank Sta=4651.4,5564.9
XS Rating Curve= 0 ,0
Exp/Cntr=0.3,0.1

Type RM Length L Ch R = 1 ,17453   ,0,0,0
BEGIN DESCRIPTION:
UNNAMED GULLY NO 8 1.0
END DESCRIPTION:
XS GIS Cut Line= 4
      2364089.31     13175640.23      2363672.64      13176616.8
      2363620.56     13177567.32      2365456.49     13179286.07
#Sta/Elev= 30
  3574.9   51.65  3740.3   51.14  3952.5   50.58  4058.7   49.98  4477.7   45.56
  4534.9   45.01  4691.4   46.25  4766.9   43.54    4847   40.49  4967.2   41.96
  4998.5   39.77  5001.2   39.27  5004.5   39.77  5017.3   41.51  5147.5   40.11
  5284.4   42.29  5426.6   48.92  5720.9   48.38  5932.9   44.69  6201.6   42.65
  6229.9   43.99  6265.5   42.33  6272.4   43.93    6605    44.8  6701.3   43.29
  7078.9   47.88  7163.9   46.77  7531.6   53.56    7906   63.88  8103.5   72.51
#Mann= 14 ,-1 , 0
  3574.9     .16       0  3740.3      .1       0  3952.5     .16       0
  4058.7     .05       0  4477.7      .1       0  4534.9     .08       0
  4691.4     .16       0  4998.5     .07       0  5004.5     .16       0
  5284.4     .05       0  5426.6      .1       0  6701.3     .05       0
  7531.6      .1       0    7906     .05       0
#XS Ineff= 2 , 0
                         5488.64           49.12
Permanent Ineff=
       F       F
Bank Sta=4766.9,5284.4
XS Rating Curve= 0 ,0
Exp/Cntr=0.3,0.1

Chan Stop Cuts=-1
Use User Specified Reach Order=0
Composite Channel Slope=5