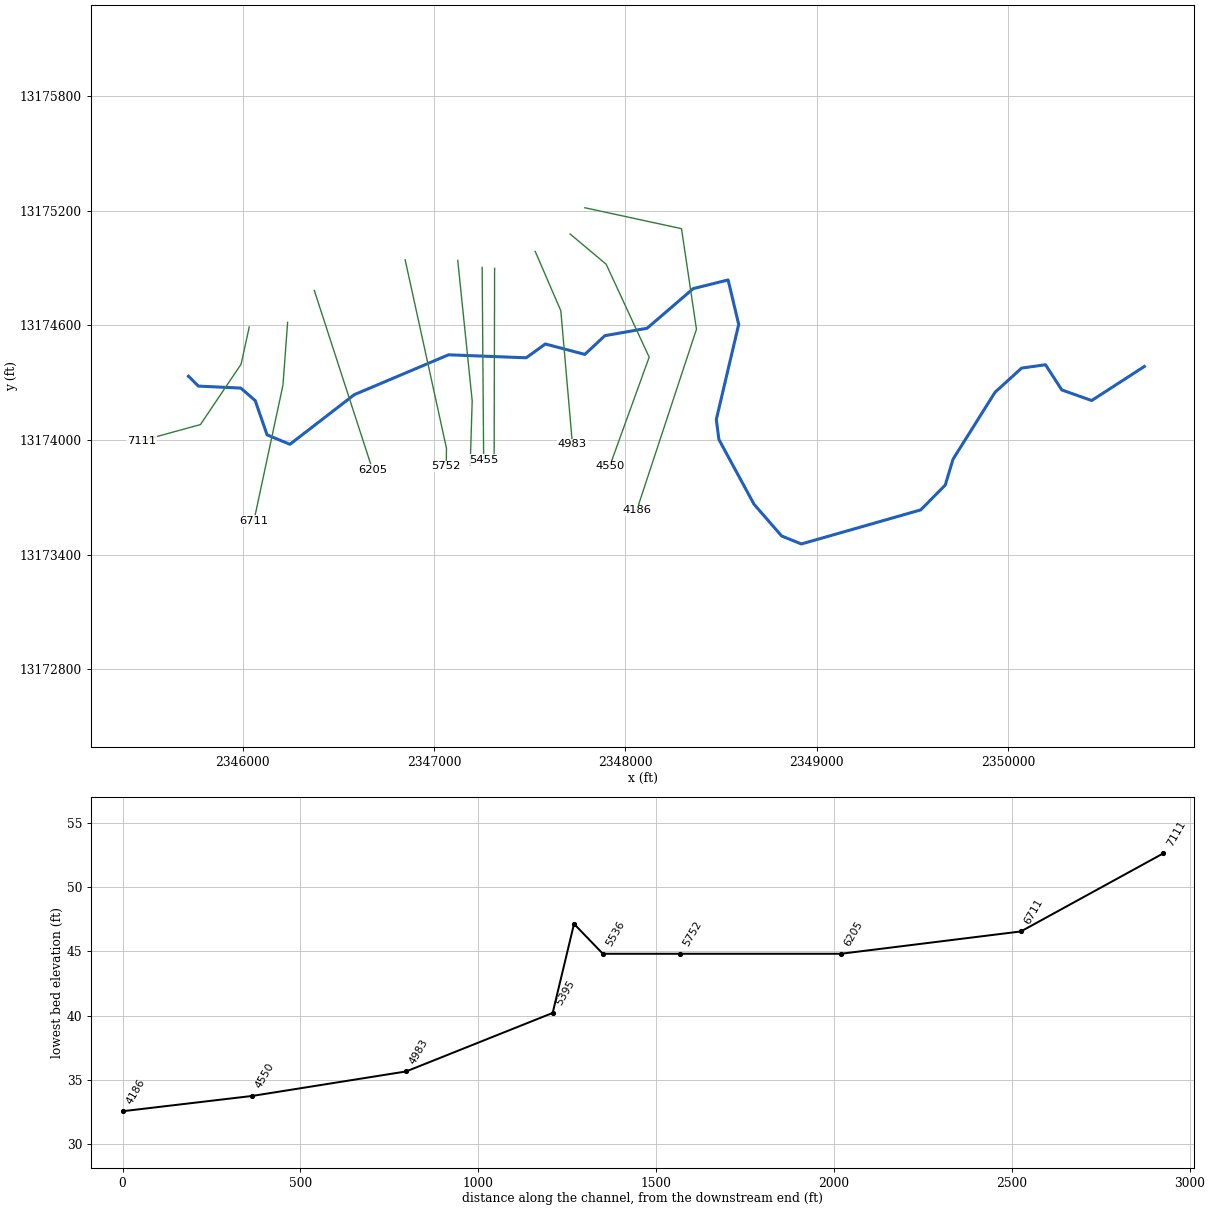
--- UNT001 IN BACR.prj (project) ---

Proj Title=UNT001 IN BACR Base Level Engineering
Current Plan=p01
Default Exp/Contr=0.3,0.1
English Units
Geom File=g01
Flow File=f01
Plan File=p01
BEGIN DESCRIPTION:
UNT001 IN BACR
END DESCRIPTION:

--- UNT001 IN BACR.p01 (plan) ---

Plan Title=Multiple Run
Short Identifier=Multiple
Geom File=g01
Flow File=f01
Subcritical Flow
K Sum by GR= 0
Std Step Tol= 0.01
Critical Tol= 0.01
Num of Std Step Trials= 20
Max Error Tol= 0.3
Flow Tol Ratio= 0.001
Split Flow NTrial= 30
Split Flow Tol= 0.02
Split Flow Ratio= 0.02
Log Output Level= 0
Friction Slope Method= 1
Unsteady Friction Slope Method= 2
Unsteady Bridges Friction Slope Method= 1
Parabolic Critical Depth
Global Vel Dist=  1 , 1 , 1
Global Log Level= 0
CheckData=True
Encroach Param= -1, 0, 0, 0
BEGIN DESCRIPTION:
Multiple Run
END DESCRIPTION:

--- UNT001 IN BACR.f01 (steady flow) ---

Flow Title=Multiple
Number of Profiles=7
Profile Names=10-year,25-year,50-year,1pct_min,100-year,1pct_plu,500-year
River Rch & RM= UNT001 IN BACR,Reach-1,7111
     751     976    1150     785    1330    1875    1764
Boundary for River Rch & Prof#=UNT001 IN BACR,Reach-1,1
Up Type=0
Dn Type=3
Dn Slope=0.005
Boundary for River Rch & Prof#=UNT001 IN BACR,Reach-1,2
Up Type=0
Dn Type=3
Dn Slope=0.005
Boundary for River Rch & Prof#=UNT001 IN BACR,Reach-1,3
Up Type=0
Dn Type=3
Dn Slope=0.005
Boundary for River Rch & Prof#=UNT001 IN BACR,Reach-1,4
Up Type=0
Dn Type=3
Dn Slope=0.005
Boundary for River Rch & Prof#=UNT001 IN BACR,Reach-1,5
Up Type=0
Dn Type=3
Dn Slope=0.005
Boundary for River Rch & Prof#=UNT001 IN BACR,Reach-1,6
Up Type=0
Dn Type=3
Dn Slope=0.005
Boundary for River Rch & Prof#=UNT001 IN BACR,Reach-1,7
Up Type=0
Dn Type=3
Dn Slope=0.005

--- UNT001 IN BACR.g01 (geometry) ---

Geom Title=Existing Conditions

River Reach=UNT001 IN BACR,Reach-1
Reach XY= 30
      2345716.75     13174333.55      2345768.77     13174281.76
      2345990.21     13174271.40      2346065.90     13174205.91
      2346127.72     13174026.85      2346247.23     13173977.48
      2346583.78     13174237.04      2347076.31     13174445.46
      2347482.12     13174429.80      2347582.15     13174502.00
      2347788.62     13174447.54      2347893.26     13174545.41
      2348114.00     13174584.26      2348355.17     13174791.61
      2348537.46     13174836.83      2348592.83     13174604.51
      2348475.78     13174107.47      2348489.25     13174002.64
      2348672.79     13173664.01      2348817.43     13173497.72
      2348920.27     13173456.28      2349544.09     13173634.41
      2349672.43     13173764.25      2349712.92     13173899.47
      2349932.77     13174249.80      2350071.42     13174376.00
      2350196.27     13174393.51      2350281.58     13174261.64
      2350437.77     13174206.28      2350712.71     13174384.32

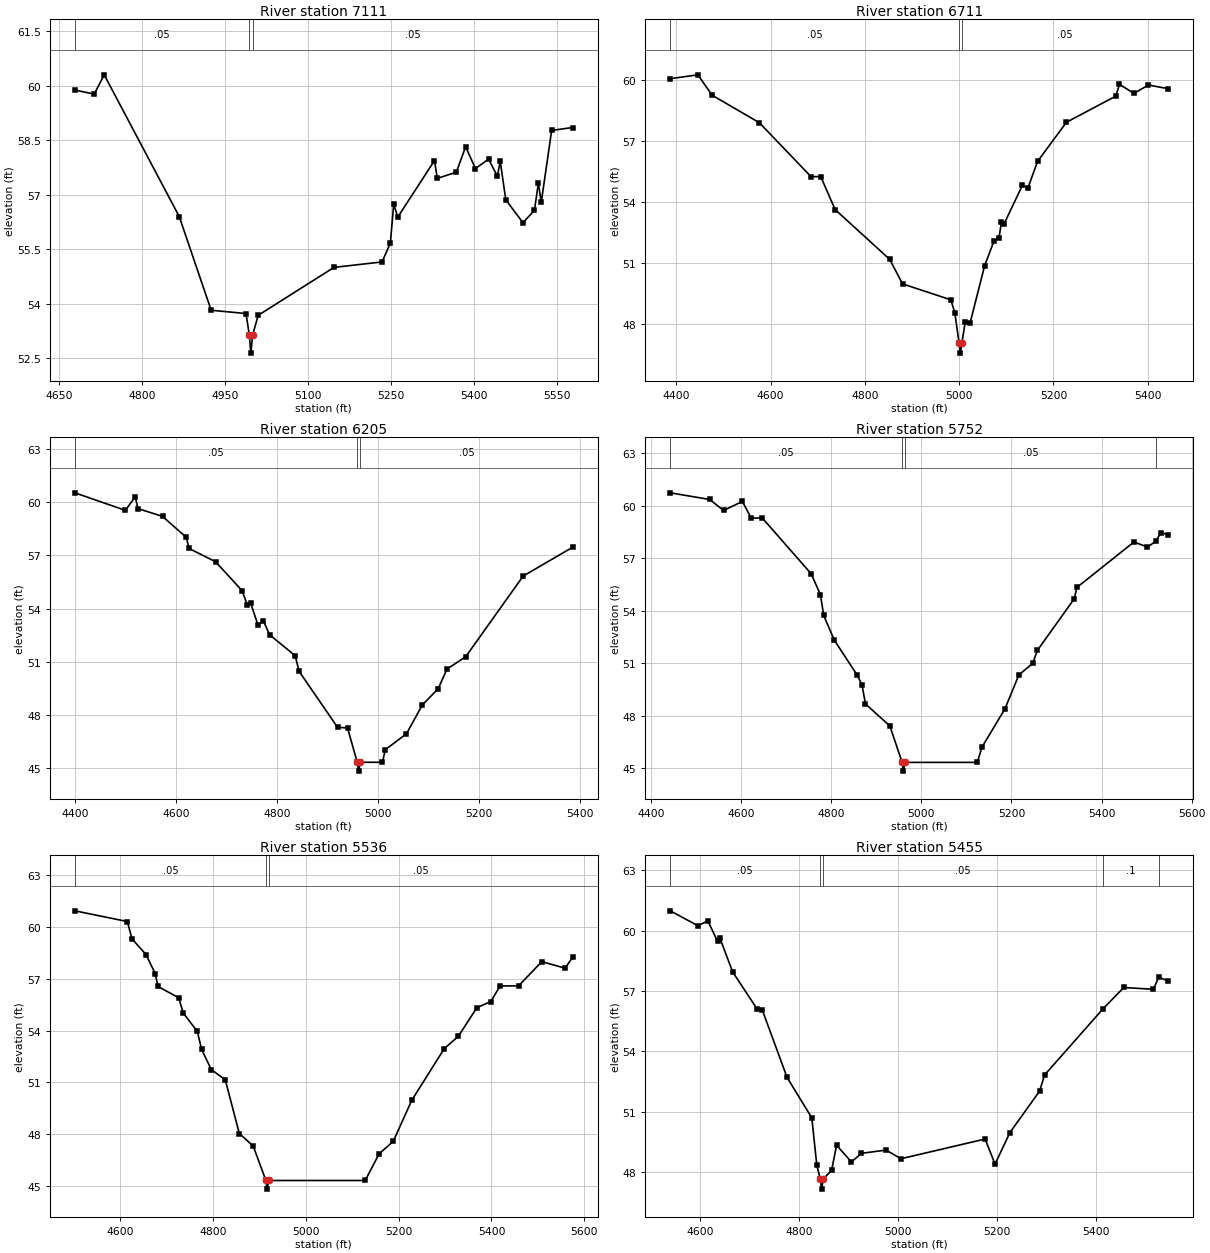
Type RM Length L Ch R = 1,7111,400,400,400
BEGIN DESCRIPTION:
UNT001 IN BACR 10.0
END DESCRIPTION:
XS GIS Cut Line= 4
      2346034.59     13174590.98      2345992.05     13174396.52
      2345779.38     13174080.54      2345471.12     13173995.92
#Sta/Elev= 30
  4679.1   59.88  4714.0   59.77  4732.0   60.30  4867.6   56.40  4925.3   53.82
  4988.3   53.73  4994.3   53.14  4997.0   52.64  5000.3   53.14  5010.3   53.68
  5147.3   55.00  5234.2   55.15  5249.2   55.67  5255.3   56.75  5262.5   56.38
  5328.9   57.94  5334.1   57.45  5368.5   57.62  5385.2   58.32  5403.0   57.72
  5426.7   57.98  5442.6   57.51  5447.8   57.92  5457.8   56.86  5488.9   56.23
  5509.6   56.57  5516.7   57.32  5521.9   56.79  5540.7   58.77  5578.7   58.85
#Mann=3,-1,0
  4679.1    0.05       0  4994.3   0.035       0  5000.3    0.05       0
Bank Sta=4994.3,5000.3
Exp/Cntr=0.3,0.1

Type RM Length L Ch R = 1,6711,506,506,506
BEGIN DESCRIPTION:
UNT001 IN BACR 9.0
END DESCRIPTION:
XS GIS Cut Line= 3
      2346235.11     13174615.28      2346210.80     13174287.14
      2346058.90     13173576.23
#Sta/Elev= 30
  4387.0   60.04  4445.6   60.23  4475.7   59.23  4575.9   57.88  4685.6   55.23
  4706.3   55.23  4736.8   53.61  4852.4   51.17  4879.9   49.96  4982.2   49.18
  4990.7   48.55  4999.7   47.06  5002.4   46.56  5005.7   47.06  5012.9   48.10
  5023.1   48.04  5053.8   50.84  5074.2   52.09  5084.5   52.23  5089.6   53.00
  5094.7   52.88  5134.0   54.80  5145.8   54.67  5166.3   55.98  5227.6   57.90
  5332.0   59.18  5340.1   59.76  5370.8   59.32  5401.5   59.73  5443.0   59.55
#Mann=3,-1,0
  4387.0    0.05       0  4999.7   0.035       0  5005.7    0.05       0
Bank Sta=4999.7,5005.7
Exp/Cntr=0.3,0.1

Type RM Length L Ch R = 1,6205,453,453,453
BEGIN DESCRIPTION:
UNT001 IN BACR 8.0
END DESCRIPTION:
XS GIS Cut Line= 2
      2346374.65     13174782.00      2346679.25     13173843.49
#Sta/Elev= 30
  4399.4   60.53  4499.4   59.54  4519.0   60.31  4524.2   59.64  4573.0   59.20
  4620.1   58.02  4625.6   57.39  4678.2   56.64  4730.7   55.01  4741.2   54.20
  4748.0   54.29  4762.3   53.06  4772.8   53.32  4785.2   52.52  4835.9   51.34
  4843.9   50.45  4920.0   47.29  4939.8   47.26  4959.0   45.32  4961.8   44.82
  4965.0   45.32  5009.0   45.32  5014.6   46.03  5056.6   46.93  5088.2   48.56
  5119.7   49.48  5136.8   50.58  5174.1   51.28  5287.9   55.83  5386.1   57.46
#Mann=3,-1,0
  4399.4    0.05       0  4959.0   0.035       0  4965.0    0.05       0
Bank Sta=4959,4965
Exp/Cntr=0.3,0.1

Type RM Length L Ch R = 1,5752,216,216,216
BEGIN DESCRIPTION:
UNT001 IN BACR 7.0
END DESCRIPTION:
XS GIS Cut Line= 3
      2346849.37     13174942.38      2347065.53     13173956.38
      2347063.89     13173861.41
#Sta/Elev= 30
  4443.1   60.73  4530.7   60.35  4561.4   59.72  4603.1   60.24  4622.8   59.28
  4647.0   59.30  4755.9   56.10  4776.4   54.90  4783.6   53.72  4807.1   52.31
  4858.3   50.29  4868.5   49.75  4876.3   48.66  4930.4   47.40  4957.6   45.32
  4960.4   44.82  4963.6   45.32  5124.4   45.32  5134.7   46.19  5185.9   48.39
  5216.6   50.32  5247.3   50.98  5257.6   51.72  5339.4   54.67  5345.3   55.32
  5472.0   57.92  5502.0   57.63  5520.4   57.96  5532.0   58.46  5547.5   58.33
#Mann=4,-1,0
  4443.1    0.05       0  4957.6   0.035       0  4963.6    0.05       0
  5520.4     0.1       0
Bank Sta=4957.6,4963.6
Exp/Cntr=0.3,0.1

Type RM Length L Ch R = 1,5536,81,81,81
BEGIN DESCRIPTION:
Mapping XS 68ccbddf
END DESCRIPTION:
XS GIS Cut Line= 3
      2347124.34     13174939.26      2347199.86     13174204.86
      2347189.49     13173870.39
#Sta/Elev= 30
  4502.1   60.93  4615.1   60.31  4625.1   59.31  4655.3   58.40  4675.4   57.28
  4681.1   56.55  4725.7   55.90  4735.7   55.01  4765.9   53.95  4775.2   52.91
  4796.0   51.74  4826.2   51.15  4856.4   48.04  4886.5   47.31  4913.7   45.32
  4916.4   44.82  4919.7   45.32  5127.8   45.32  5157.9   46.87  5188.1   47.58
  5228.3   49.97  5298.4   52.96  5328.4   53.66  5368.4   55.32  5398.5   55.68
  5418.5   56.58  5458.5   56.59  5508.5   57.99  5558.5   57.61  5575.0   58.24
#Mann=3,-1,0
  4502.1    0.05       0  4913.7   0.035       0  4919.7    0.05       0
Bank Sta=4913.7,4919.7
Exp/Cntr=0.3,0.1

Type RM Length L Ch R = 1,5455,60,60,60
BEGIN DESCRIPTION:
UNT001 IN BACR 6.0
END DESCRIPTION:
XS GIS Cut Line= 2
      2347251.94     13174902.75      2347259.75     13173897.58
#Sta/Elev= 30
  4540.0   60.98  4595.9   60.24  4615.9   60.48  4635.5   59.47  4640.5   59.61
  4665.9   57.95  4715.9   56.08  4725.9   56.05  4775.9   52.70  4825.9   50.69
  4835.9   48.35  4842.9   47.65  4845.7   47.15  4848.9   47.65  4865.9   48.09
  4875.9   49.33  4905.9   48.50  4925.9   48.93  4975.9   49.09  5005.9   48.66
  5175.9   49.64  5195.9   48.39  5225.9   49.96  5285.9   52.02  5295.9   52.82
  5413.6   56.10  5455.9   57.17  5515.9   57.08  5526.3   57.68  5545.2   57.50
#Mann=5,-1,0
  4540.0    0.05       0  4842.9   0.035       0  4848.9    0.05       0
  5413.6     0.1       0  5526.3    0.05       0
Bank Sta=4842.9,4848.9
Exp/Cntr=0.3,0.1

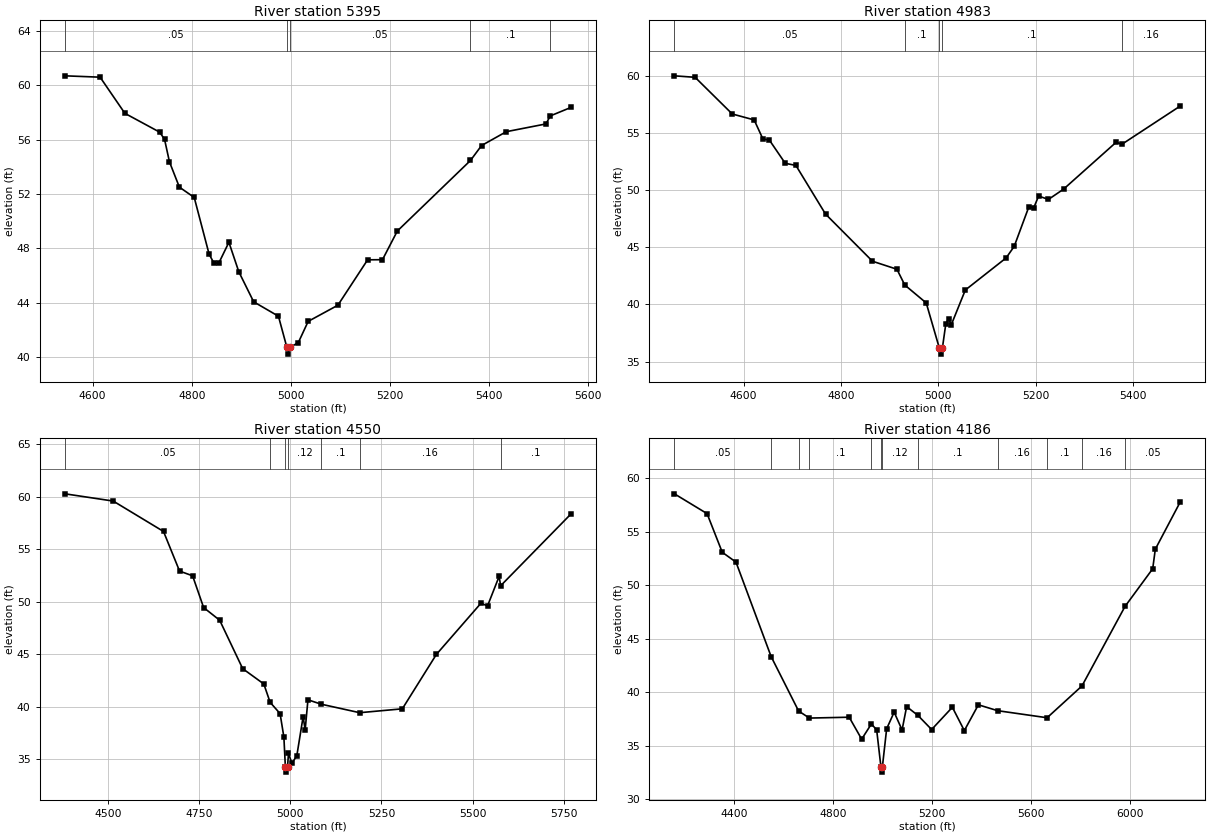
Type RM Length L Ch R = 1,5395,412,412,412
BEGIN DESCRIPTION:
Mapping XS 13cae0fc
END DESCRIPTION:
XS GIS Cut Line= 2
      2347317.05     13174897.55      2347314.44     13173876.75
#Sta/Elev= 30
  4544.3   60.69  4615.0   60.59  4665.0   57.93  4735.0   56.55  4745.0   56.03
  4755.0   54.36  4775.0   52.50  4805.0   51.74  4835.0   47.57  4845.0   46.89
  4855.0   46.94  4875.0   48.44  4895.0   46.27  4925.0   44.06  4975.0   43.00
  4992.0   40.71  4994.7   40.21  4998.0   40.71  5015.0   41.05  5035.0   42.62
  5095.0   43.81  5155.0   47.15  5185.0   47.16  5215.0   49.27  5362.6   54.46
  5385.0   55.56  5435.0   56.58  5515.0   57.15  5523.7   57.74  5565.1   58.36
#Mann=5,-1,0
  4544.3    0.05       0  4992.0   0.035       0  4998.0    0.05       0
  5362.6     0.1       0  5523.7    0.05       0
Bank Sta=4992,4998
Exp/Cntr=0.3,0.1

Type RM Length L Ch R = 1,4983,433,433,433
BEGIN DESCRIPTION:
UNT001 IN BACR 5.0
END DESCRIPTION:
XS GIS Cut Line= 3
      2347529.38     13174985.91      2347663.06     13174676.03
      2347723.82     13173977.25
#Sta/Elev= 30
  4457.9   60.01  4500.4   59.88  4576.7   56.67  4621.7   56.15  4639.8   54.47
  4652.9   54.39  4685.6   52.35  4707.4   52.17  4768.3   47.91  4864.8   43.78
  4915.0   43.08  4931.1   41.70  4975.2   40.13  5002.3   36.15  5005.1   35.65
  5008.3   36.15  5015.4   38.30  5021.4   38.76  5026.4   38.19  5055.5   41.26
  5139.3   44.07  5155.9   45.08  5186.0   48.54  5196.1   48.46  5206.1   49.49
  5226.2   49.19  5257.3   50.09  5365.2   54.19  5377.6   54.03  5496.8   57.36
#Mann=5,-1,0
  4457.9    0.05       0  4931.1     0.1       0  5002.3    0.07       0
  5008.3     0.1       0  5377.6    0.16       0
Bank Sta=5002.3,5008.3
Exp/Cntr=0.3,0.1

Type RM Length L Ch R = 1,4550,364,364,364
BEGIN DESCRIPTION:
UNT001 IN BACR 4.0
END DESCRIPTION:
XS GIS Cut Line= 4
      2347711.68     13175077.06      2347900.04     13174919.09
      2348124.86     13174432.97      2347918.27     13173861.80
#Sta/Elev= 30
  4381.1   60.29  4513.3   59.60  4651.4   56.70  4695.5   52.92  4731.3   52.47
  4761.6   49.44  4805.7   48.23  4868.9   43.61  4926.9   42.15  4944.2   40.40
  4971.6   39.32  4982.0   37.08  4986.1   34.24  4988.8   33.74  4992.1   34.24
  4994.6   35.52  5004.0   34.59  5017.5   35.30  5034.9   39.04  5040.4   37.76
  5048.1   40.64  5084.6   40.22  5190.2   39.41  5307.3   39.78  5400.8   44.97
  5523.4   49.86  5541.2   49.59  5573.1   52.41  5577.3   51.52  5769.9   58.35
#Mann=7,-1,0
  4381.1    0.05       0  4944.2    0.12       0  4986.1    0.07       0
  4992.1    0.12       0  5084.6     0.1       0  5190.2    0.16       0
  5577.3     0.1       0
Bank Sta=4986.1,4992.1
Exp/Cntr=0.3,0.1

Type RM Length L Ch R = 1,4186,0,0,0
BEGIN DESCRIPTION:
UNT001 IN BACR 1.0
END DESCRIPTION:
XS GIS Cut Line= 4
      2347788.60     13175214.41      2348293.83     13175105.03
      2348371.95     13174578.99      2348059.59     13173631.49
#Sta/Elev= 30
  4157.6   58.55  4289.7   56.70  4351.1   53.09  4406.7   52.17  4549.0   43.34
  4660.1   38.26  4703.7   37.60  4864.8   37.68  4915.3   35.63  4954.6   37.05
  4976.0   36.50  4993.2   33.05  4995.9   32.55  4999.2   33.05  5016.4   36.60
  5046.7   38.15  5078.8   36.49  5097.3   38.67  5142.9   37.85  5198.4   36.53
  5282.3   38.61  5330.7   36.43  5387.6   38.84  5465.5   38.29  5665.7   37.63
  5806.7   40.60  5981.0   48.03  6093.0   51.55  6103.6   53.38  6204.0   57.77
#Mann=12,-1,0
  4157.6    0.05       0  4549.0     0.1       0  4660.1    0.05       0
  4703.7     0.1       0  4954.6    0.12       0  4993.2    0.07       0
  4999.2    0.12       0  5142.9     0.1       0  5465.5    0.16       0
  5665.7     0.1       0  5806.7    0.16       0  5981.0    0.05       0
Bank Sta=4993.2,4999.2
Exp/Cntr=0.3,0.1

Chan Stop Cuts=-1