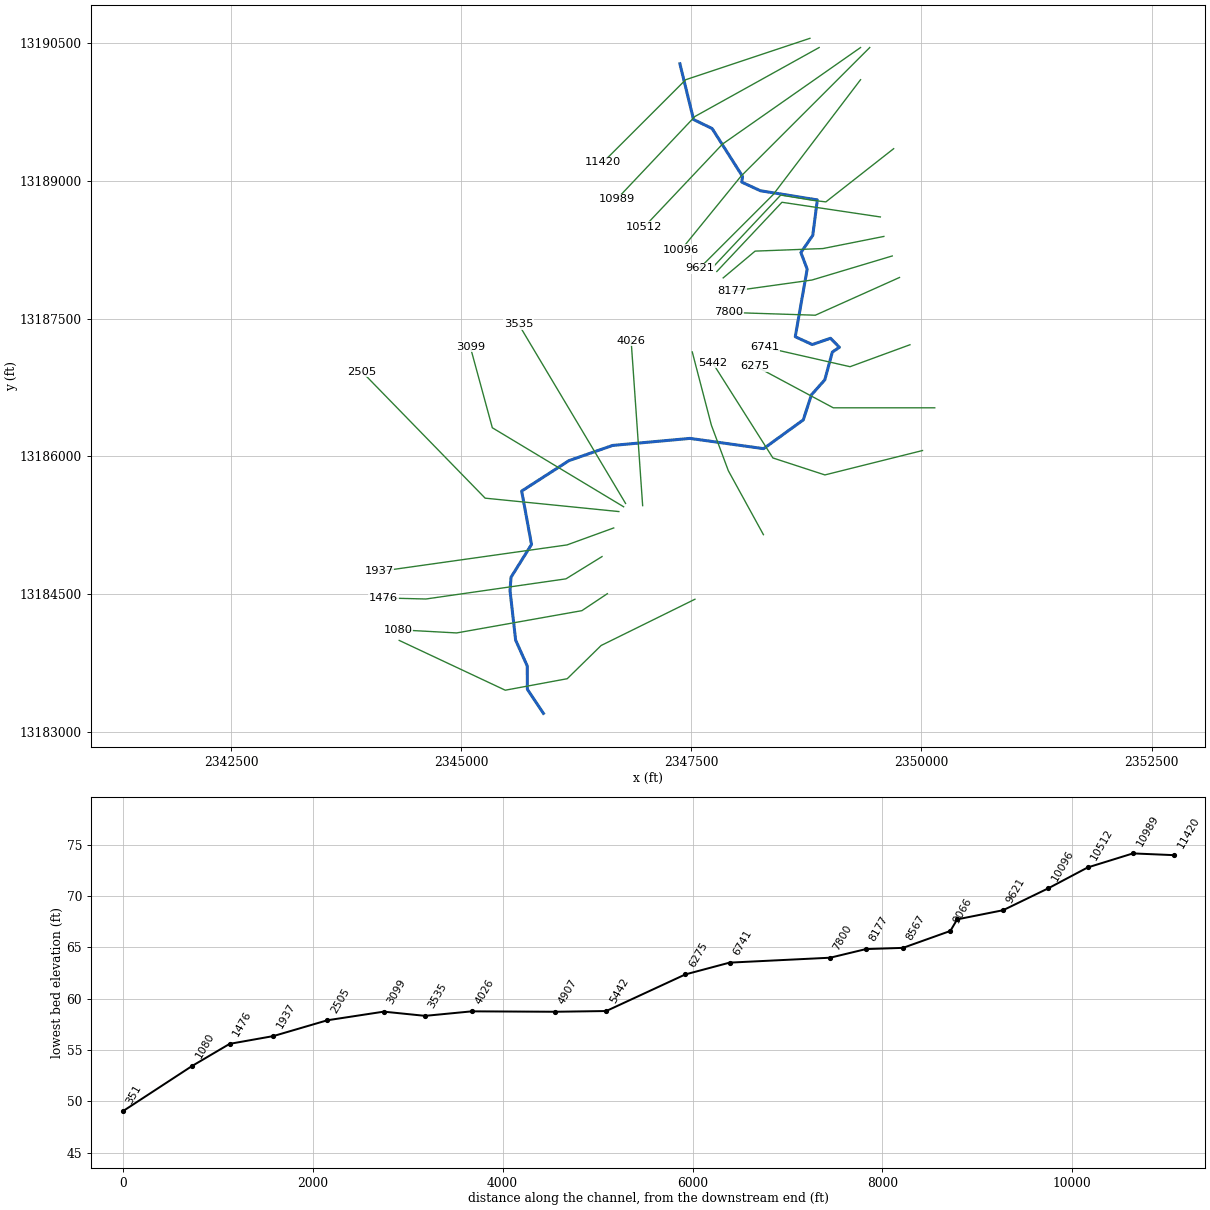
--- UNT003 IN BACR.prj (project) ---

Proj Title=UNT003 IN BACR Base Level Engineering
Current Plan=p01
Default Exp/Contr=0.3,0.1
English Units
Geom File=g01
Flow File=f01
Plan File=p01
Y Axis Title=Elevation
X Axis Title(PF)=Main Channel Distance
X Axis Title(XS)=Station
BEGIN DESCRIPTION:
UNT003 IN BACR
END DESCRIPTION:
DSS Export Rating Curves= 0
DSS Export Rating Curve Sorted= 0
DSS Export Volume Flow Curves= 0
DXF OffsetX= 0
DXF OffsetY= 0
DXF ScaleX= 1
DXF ScaleY= 10

--- UNT003 IN BACR.p01 (plan) ---

Plan Title=Multiple Run
Short Identifier=Multiple
Geom File=g01
Flow File=f01
Subcritical Flow
K Sum by GR= 0
Std Step Tol= 0.01
Critical Tol= 0.01
Num of Std Step Trials= 20
Max Error Tol= 0.3
Flow Tol Ratio= 0.001
Split Flow NTrial= 30
Split Flow Tol= 0.02
Split Flow Ratio= 0.02
Log Output Level= 0
Friction Slope Method= 1
Unsteady Friction Slope Method= 2
Unsteady Bridges Friction Slope Method= 1
Parabolic Critical Depth
Global Vel Dist=  1 , 1 , 1
Global Log Level= 0
CheckData=True
Encroach Param= -1, 0, 0, 0
BEGIN DESCRIPTION:
Multiple Run
END DESCRIPTION:

--- UNT003 IN BACR.f01 (steady flow) ---

Flow Title=Multiple
Program Version=4.10
Number of Profiles= 7
Profile Names=10-year,25-year,50-year,1pct_min,100-year,1pct_plu,500-year
River Rch & RM=UNT003 IN BACR,Reach-1         ,11420
     297     387     455     390     528     714     713
River Rch & RM=UNT003 IN BACR,Reach-1         ,9138
     439     586     700     609     824    1115    1147
River Rch & RM=UNT003 IN BACR,Reach-1         ,1937
     669     917    1117     990    1339    1811    1934
Boundary for River Rch & Prof#=UNT003 IN BACR,Reach-1         , 1
Up Type= 0
Dn Type= 3
Dn Slope=0.0061
Boundary for River Rch & Prof#=UNT003 IN BACR,Reach-1         , 2
Up Type= 0
Dn Type= 3
Dn Slope=0.0061
Boundary for River Rch & Prof#=UNT003 IN BACR,Reach-1         , 3
Up Type= 0
Dn Type= 3
Dn Slope=0.0061
Boundary for River Rch & Prof#=UNT003 IN BACR,Reach-1         , 4
Up Type= 0
Dn Type= 3
Dn Slope=0.0061
Boundary for River Rch & Prof#=UNT003 IN BACR,Reach-1         , 5
Up Type= 0
Dn Type= 3
Dn Slope=0.0061
Boundary for River Rch & Prof#=UNT003 IN BACR,Reach-1         , 6
Up Type= 0
Dn Type= 3
Dn Slope=0.0061
Boundary for River Rch & Prof#=UNT003 IN BACR,Reach-1         , 7
Up Type= 0
Dn Type= 3
Dn Slope=0.0061
DSS Import GetInterval= 0
DSS Import GetPeak= 0
DSS Import FillOption= 0

--- UNT003 IN BACR.g01 (geometry) ---

Geom Title=Existing Conditions
Program Version=4.10

River Reach=UNT003 IN BACR  ,Reach-1
Reach XY= 30
      2347374.51     13190270.24      2347522.95     13189663.86
      2347725.27     13189565.48      2348055.03     13189045.62
       2348047.1     13188982.98      2348248.78     13188889.68
      2348867.99     13188789.69      2348818.45      13188404.5
      2348689.47     13188217.16      2348757.63     13188037.18
      2348628.17     13187301.84      2348812.83     13187216.75
      2349011.68     13187285.28      2349107.72     13187186.86
      2349031.21     13187135.17      2348949.25     13186833.33
      2348803.46     13186669.21      2348715.54     13186397.88
      2348284.35     13186084.57        2347484.     13186196.26
      2346643.38     13186119.64      2346168.77     13185954.37
      2345655.03     13185623.29      2345762.03     13185042.94
      2345539.44     13184686.14      2345528.37     13184541.62
      2345589.45     13184002.52       2345715.8     13183721.06
      2345716.87     13183467.44      2345891.64     13183205.87

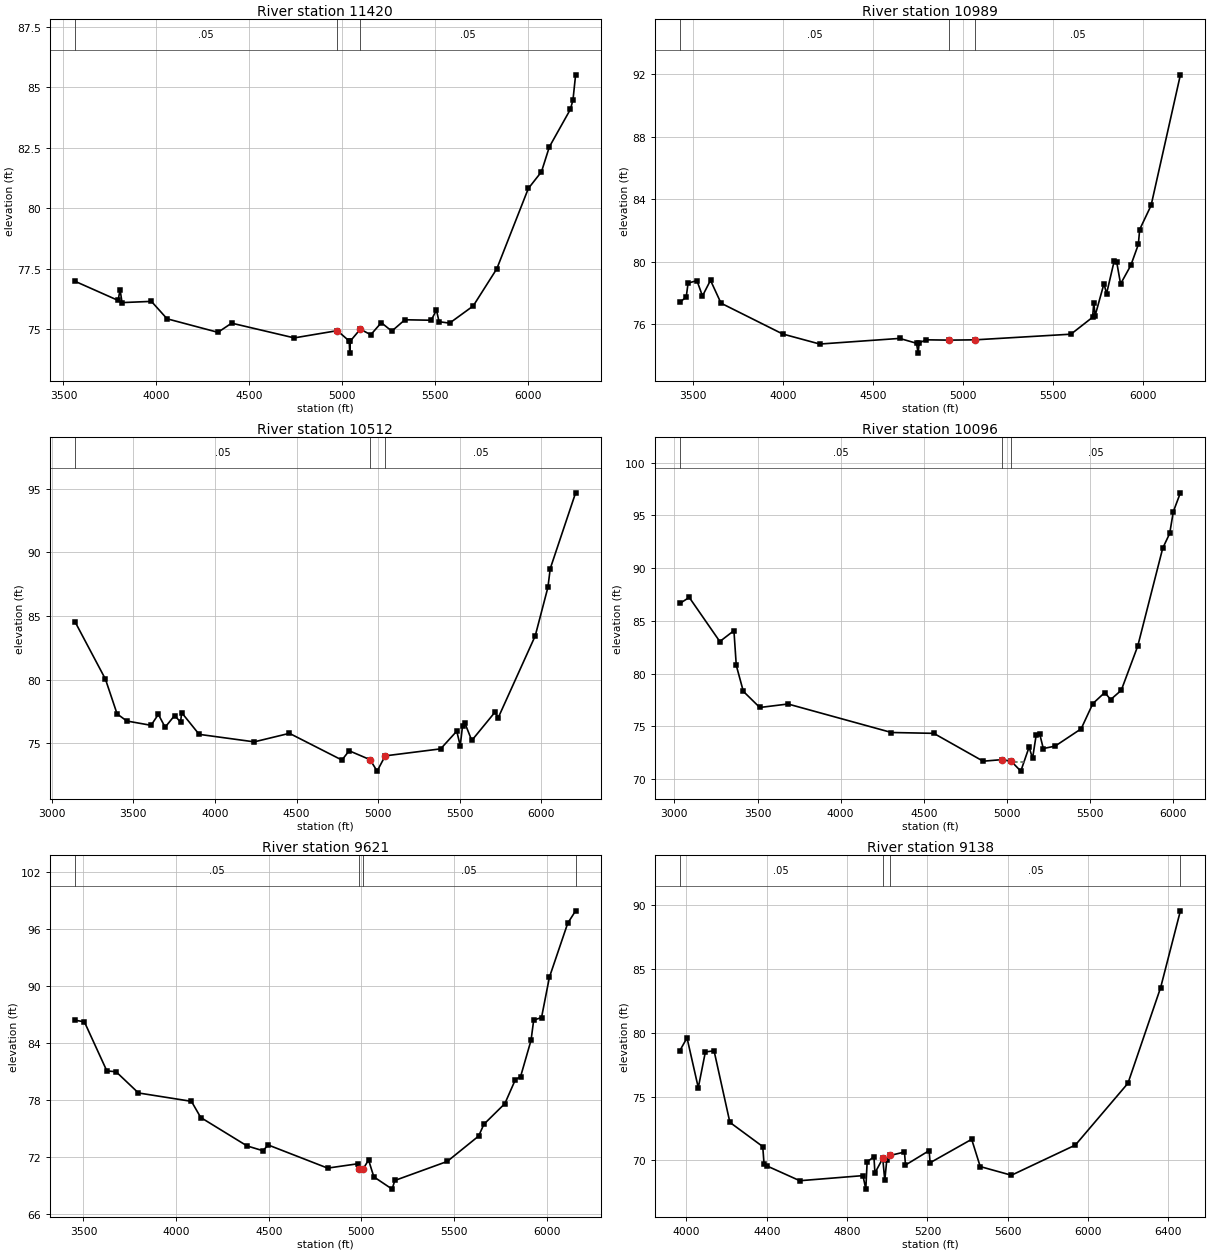
Type RM Length L Ch R = 1 ,11420   ,431,431,431
BEGIN DESCRIPTION:
UNT003 IN BACR 18.0
END DESCRIPTION:
XS GIS Cut Line= 3
      2348787.69     13190546.84      2347437.72     13190096.85
      2346537.71     13189196.84
#Sta/Elev= 30
  3562.7   76.97  3794.6   76.18  3805.1   76.63  3815.6   76.09  3973.8   76.14
  4058.1   75.42  4332.2   74.86  4405.9   75.24  4743.2   74.63  4975.1   74.93
  5039.3    74.5    5042      74  5045.3    74.5  5098.8   74.99  5155.4   74.76
    5212   75.26  5268.5   74.91  5339.2   75.38  5480.7   75.36  5508.9   75.78
  5523.1    75.3  5579.7   75.24  5706.9   75.95  5834.2   77.49  6003.9   80.81
  6074.6    81.5  6117.1   82.53  6230.2   84.08  6244.3   84.47  6258.5   85.51
#Mann= 3 , 0 , 0
  3562.7     .05       0  4975.1    .035       0  5098.8     .05       0
Bank Sta=4975.1,5098.8
XS Rating Curve= 0 ,0
Exp/Cntr=0.3,0.1

Type RM Length L Ch R = 1 ,10989   ,477,477,477
BEGIN DESCRIPTION:
UNT003 IN BACR 17.0
END DESCRIPTION:
XS GIS Cut Line= 3
       2348887.7     13190446.84      2347537.72     13189696.85
      2346687.69     13188796.83
#Sta/Elev= 30
  3426.8   77.42  3462.2   77.75  3472.5   78.64  3521.7    78.8  3552.6   77.82
  3597.2   78.82  3655.6   77.36  3998.8   75.39  4204.7   74.75  4648.5   75.11
  4742.3    74.8  4751.2   74.17  4757.2   74.82  4794.9   75.02  4925.4      75
    5070   75.02  5600.8   75.38    5721   76.46  5727.8    77.4  5735.1   76.56
  5784.5   78.61  5798.6   77.96  5841.1   80.05  5855.3   79.97  5876.7   78.59
  5933.4   79.77  5975.4   81.11  5982.7   82.06  6046.2    83.6  6209.1   91.94
#Mann= 3 , 0 , 0
  3426.8     .05       0  4925.4    .035       0    5070     .05       0
Bank Sta=4925.4,5070
XS Rating Curve= 0 ,0
Exp/Cntr=0.3,0.1

Type RM Length L Ch R = 1 ,10512   ,416,416,416
BEGIN DESCRIPTION:
UNT003 IN BACR 16.0
END DESCRIPTION:
XS GIS Cut Line= 3
      2349337.68     13190446.83      2347837.72     13189396.85
      2346987.71     13188496.84
#Sta/Elev= 30
  3142.3   84.53  3328.4   80.03  3399.9    77.3  3459.2   76.74  3608.3    76.4
  3652.8   77.26  3694.6   76.25  3752.6   77.17  3789.2   76.65  3795.7    77.4
    3903   75.69  4240.8    75.1  4456.6   75.77  4778.4   73.67  4822.8    74.4
    4951    73.7  4994.2    72.8  5043.8      74  5383.7   74.55  5482.4   75.94
  5503.8    74.8    5518   76.36  5532.1   76.58  5574.6   75.21    5716   77.42
  5737.2   77.01  5963.6   83.43  6041.5   87.25  6055.6   88.71  6211.2   94.67
#Mann= 3 , 0 , 0
  3142.3     .05       0    4951    .035       0  5043.8     .05       0
Bank Sta=4951,5043.8
XS Rating Curve= 0 ,0
Exp/Cntr=0.3,0.1

Type RM Length L Ch R = 1 ,10096   ,475,475,475
BEGIN DESCRIPTION:
UNT003 IN BACR 15.0
END DESCRIPTION:
XS GIS Cut Line= 3
      2349437.72     13190446.86      2348037.72     13189046.85
      2347387.71     13188246.84
#Sta/Elev= 30
  3032.7   86.65  3089.3   87.22  3273.1   83.04    3358   84.07  3372.1   80.78
  3414.5   78.32  3513.5   76.79  3683.2   77.12  4305.5   74.42  4560.1   74.34
    4857    71.7  4970.2   71.85  5026.2   71.69  5083.5   70.76  5133.3   73.03
  5154.3   71.97  5176.4   74.23  5197.2   74.28  5218.8    72.9  5289.9   73.13
  5446.5   74.77  5516.8   77.16  5588.7   78.21  5623.9   77.54  5687.8   78.42
  5786.9   82.61  5937.1   91.88    5979   93.28    6001   95.35  6043.4   97.13
#Mann= 3 , 0 , 0
  3032.7     .05       0  4970.2    .035       0  5026.2     .05       0
#XS Ineff= 2 ,-1
 5034.12 5100.57   71.61 5133.05 5167.4272.60539
Permanent Ineff=
       F       F
Bank Sta=4970.2,5026.2
XS Rating Curve= 0 ,0
Exp/Cntr=0.3,0.1

Type RM Length L Ch R = 1 ,9621    ,483,483,483
BEGIN DESCRIPTION:
UNT003 IN BACR 14.0
END DESCRIPTION:
XS GIS Cut Line= 3
       2349337.7     13190096.83      2348387.72     13188846.85
       2347587.7     13188046.83
#Sta/Elev= 30
  3454.8   86.39    3505   86.22  3626.3   81.06  3676.2   80.97  3796.9   78.74
  4082.8   77.86    4133   76.16  4383.2   73.17  4468.5   72.67  4497.3   73.27
  4817.9   70.84  4982.2    71.3 4989.72   70.71  5007.9   70.71  5038.9   71.69
  5067.2   69.92    5166   68.63  5180.4   69.54  5463.2   71.54  5632.9   74.21
  5661.2   75.45  5774.3   77.62  5830.9   80.13  5859.2   80.46  5915.8   84.29
  5929.9    86.4  5972.3   86.67  6014.7    90.9  6113.7   96.59  6156.2   97.89
#Mann= 4 ,-1 , 0
  3454.8     .05       0 4989.72    .035       0  5007.9     .05       0
  6156.2     .05       0
#XS Ineff= 2 ,-1
 4752.31 4974.06   71.27 5043.41 5516.3770.66907
Permanent Ineff=
       F       F
Bank Sta=4989.72,5007.9
XS Rating Curve= 0 ,0
Exp/Cntr=0.3,0.1

Type RM Length L Ch R = 1 ,9138    ,72,72,72
BEGIN DESCRIPTION:
UNT003 IN BACR 13.0
END DESCRIPTION:
XS GIS Cut Line= 5
      2349697.26     13189346.74      2348960.72     13188768.17
      2348820.44       13188785.      2348470.19     13188842.38
      2347744.89     13188070.76
#Sta/Elev= 30
  3967.6   78.61  4003.3   79.61  4059.4    75.7  4094.7   78.51    4138   78.59
  4216.7   72.98  4380.3   71.08  4386.6   69.75  4401.1   69.56  4564.7    68.4
  4879.1    68.8  4893.3   67.74    4900   69.88  4933.8   70.28  4938.8   69.01
  4977.7   70.15  4987.8   68.42  4997.9   70.05    5016   70.39  5085.8   70.65
  5090.9   69.63  5208.5   70.76  5213.5   69.81  5420.4   71.65  5462.9   69.51
  5618.2   68.83  5936.7    71.2  6198.4   76.05  6361.1   83.56  6459.4   89.58
#Mann= 4 ,-1 , 0
  3967.6     .05       0  4977.7    .035       0    5016     .05       0
  6459.4     .05       0
Bank Sta=4977.7,5016
XS Rating Curve= 0 ,0
Exp/Cntr=0.3,0.1

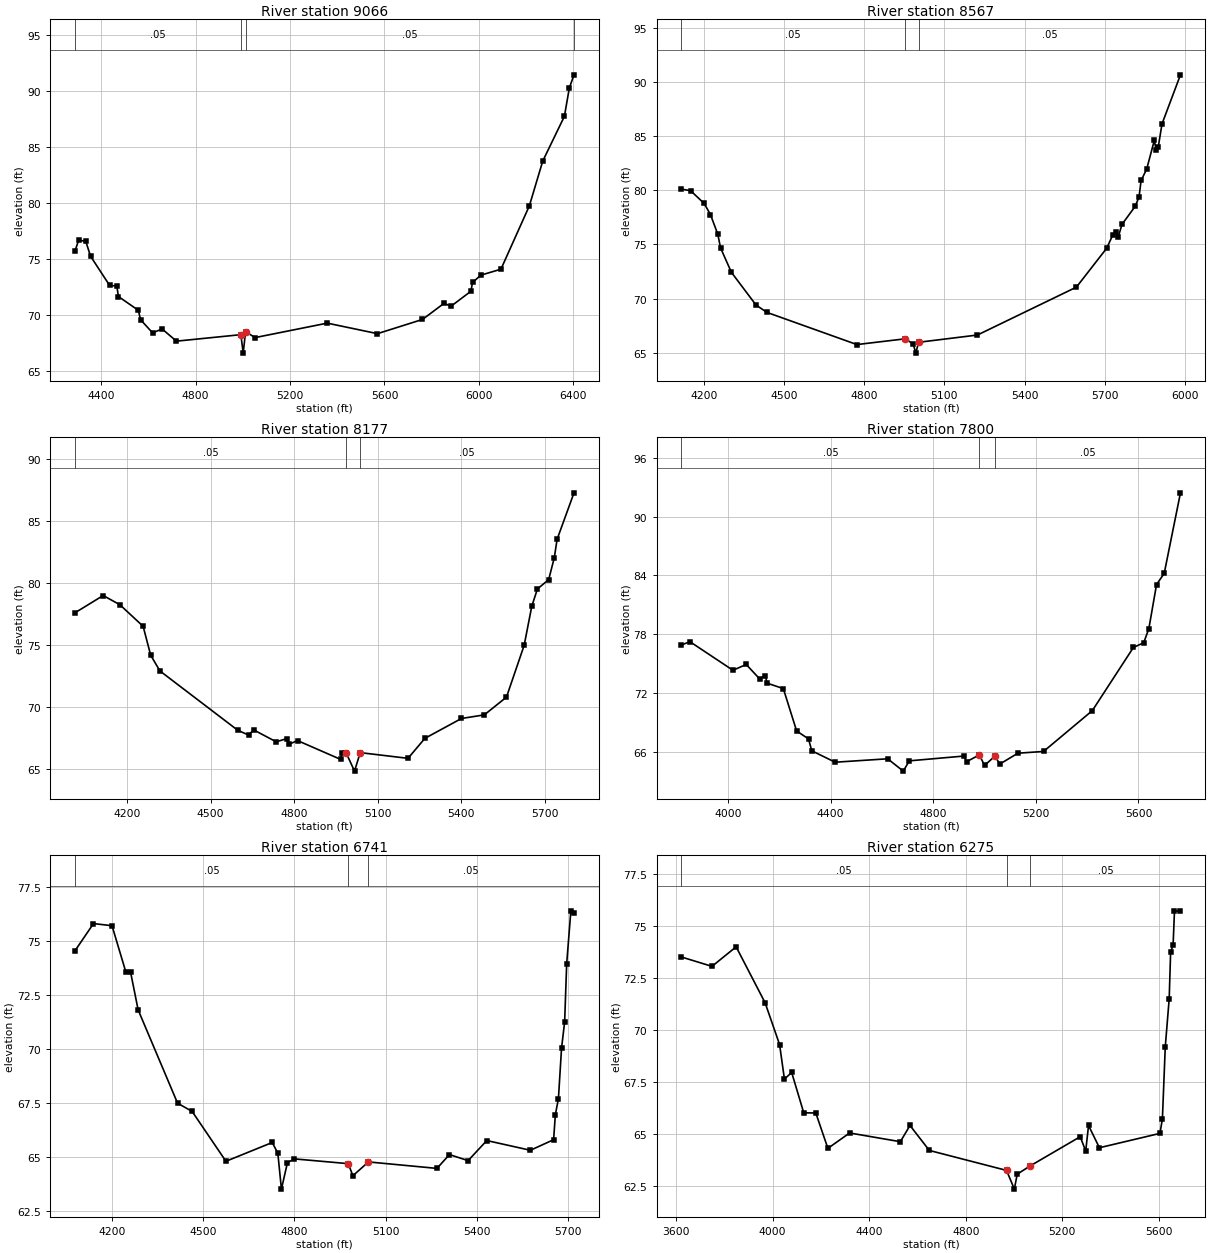
Type RM Length L Ch R = 1 ,9066    ,499,499,499
BEGIN DESCRIPTION:
UNT003 IN BACR 12.0
END DESCRIPTION:
XS GIS Cut Line= 3
       2349552.9     13188604.38      2348483.44     13188764.11
       2347775.7     13188011.27
#Sta/Elev= 30
  4288.6   75.73    4304    76.7  4334.2   76.61  4354.5   75.27  4435.4   72.66
  4465.7   72.61  4472.7   71.67  4556.7   70.44  4566.8   69.59  4617.4   68.42
  4657.8   68.77  4718.5   67.68  4991.5   68.26  5001.4   66.61  5011.4   68.52
  5052.2      68  5357.6   69.29  5570.3   68.35  5761.2   69.62  5853.1   71.07
  5881.4   70.79  5966.4   72.14  5973.2   72.93  6008.9   73.58  6093.6   74.11
    6214   79.77  6270.7   83.77  6362.5   87.77  6383.5   90.31  6403.2   91.48
#Mann= 4 ,-1 , 0
  4288.6     .05       0  4991.5    .035       0  5011.4     .05       0
  6403.2     .05       0
Bank Sta=4991.5,5011.4
XS Rating Curve= 0 ,0
Exp/Cntr=0.3,0.1

Type RM Length L Ch R = 1 ,8567    ,390,390,390
BEGIN DESCRIPTION:
Mapping XS eb8e0b2b
END DESCRIPTION:
XS GIS Cut Line= 4
      2349591.04     13188392.57      2348927.88     13188260.64
      2348191.77     13188232.86      2347844.98     13187941.55
#Sta/Elev= 30
  4116.9   80.09  4150.9   79.95  4201.9   78.77  4225.2   77.75  4252.8   75.93
    4263   74.67  4303.8   72.41  4395.6    69.4  4436.4   68.72  4772.8   65.75
  4953.3   66.28  4983.4    65.8  4993.1   64.96  5003.4   65.96  5223.5   66.63
  5593.6   71.05  5706.8   74.64  5728.9   75.83  5743.2   76.16  5749.7   75.66
    5764   76.84  5813.4   78.51  5827.7   79.37  5835.4   80.89  5856.3   81.94
    5885   84.61  5891.5   83.67  5899.3   83.94  5913.6   86.11  5982.6   90.64
#Mann= 3 , 0 , 0
  4116.9     .05       0  4953.3    .035       0  5003.4     .05       0
Bank Sta=4953.3,5003.4
XS Rating Curve= 0 ,0
Exp/Cntr=0.3,0.1

Type RM Length L Ch R = 1 ,8177    ,377,377,377
BEGIN DESCRIPTION:
UNT003 IN BACR 11.0
END DESCRIPTION:
XS GIS Cut Line= 3
      2349682.04     13188180.15      2348810.02     13187918.55
      2347937.68     13187796.85
#Sta/Elev= 30
  4013.3   77.59  4114.4   78.98  4174.4   78.24  4257.9    76.5  4284.9   74.18
    4318   72.91  4598.1   68.12  4636.4   67.75  4654.7   68.16  4735.6    67.2
  4773.9   67.46    4780   66.99  4812.1    67.3  4966.4   65.79  4971.8   66.34
  4986.6   66.31  5016.7   64.84  5037.1   66.33  5208.7   65.87  5269.3   67.48
  5400.6   69.08  5482.6   69.37  5562.1    70.8  5625.6   74.97    5653   78.12
  5673.2   79.51  5713.6   80.26  5733.8   82.03  5743.9   83.51  5804.5   87.25
#Mann= 3 , 0 , 0
  4013.3     .05       0  4986.6    .035       0  5037.1     .05       0
Bank Sta=4986.6,5037.1
XS Rating Curve= 0 ,0
Exp/Cntr=0.3,0.1

Type RM Length L Ch R = 1 ,7800    ,1059,1059,1059
BEGIN DESCRIPTION:
UNT003 IN BACR 10.0
END DESCRIPTION:
XS GIS Cut Line= 3
      2349761.05     13187946.11      2348846.29     13187535.81
      2347904.45     13187566.19
#Sta/Elev= 30
  3818.8   76.88  3851.7   77.22  4019.5    74.3  4071.3   74.89  4123.1   73.43
  4146.3   73.75  4151.8   72.99  4215.8   72.43  4267.7    68.1    4314   67.29
  4326.6   66.08  4417.7   64.91  4622.5   65.26  4683.4      64  4706.8   65.05
    4920   65.54    4930   64.96    4980   65.66    5000   64.58  5040.1   65.52
  5060.1   64.73  5130.1   65.83  5230.1   66.01  5420.2   70.18  5580.3   76.63
  5620.4   77.11  5640.4   78.54  5670.4   83.05  5700.4    84.2  5763.7   92.42
#Mann= 3 , 0 , 0
  3818.8     .05       0    4980    .035       0  5040.1     .05       0
Bank Sta=4980,5040.1
XS Rating Curve= 0 ,0
Exp/Cntr=0.3,0.1

Type RM Length L Ch R = 1 ,6741    ,466,466,466
BEGIN DESCRIPTION:
UNT003 IN BACR 9.0
END DESCRIPTION:
XS GIS Cut Line= 3
      2349874.91     13187214.62      2349223.89     13186975.92
      2348297.72     13187186.87
#Sta/Elev= 30
  4077.4   74.56  4138.3   75.82  4199.3   75.72  4244.8   73.58  4260.3   73.58
  4285.4   71.82  4415.2    67.5  4463.1   67.12  4574.5   64.81    4727   65.68
  4745.4   65.18  4757.2   63.52  4777.1   64.75  4800.2   64.92  4977.4    64.7
  4992.5   64.14  5043.8   64.78  5269.4   64.48  5310.5   65.12    5372   64.84
  5433.5   65.77  5577.1   65.32  5653.6   65.81  5659.2   66.96  5669.4   67.71
  5679.7   70.05  5689.9   71.27  5696.6   73.96  5710.4   76.41  5720.7   76.29
#Mann= 3 , 0 , 0
  4077.4     .05       0  4977.4     .03       0  5043.8     .05       0
Bank Sta=4977.4,5043.8
XS Rating Curve= 0 ,0
Exp/Cntr=0.3,0.1

Type RM Length L Ch R = 1 ,6275    ,833,833,833
BEGIN DESCRIPTION:
UNT003 IN BACR 8.0
END DESCRIPTION:
XS GIS Cut Line= 3
      2350144.07     13186528.87       2349041.6     13186528.87
      2348191.83      13186984.1
#Sta/Elev= 30
  3622.9   73.53  3749.3   73.08  3849.3   74.02  3969.3   71.33  4029.3   69.32
  4049.3   67.66  4079.3   67.98  4129.3   66.04  4179.3   66.03  4229.3   64.33
  4319.3   65.07  4529.3   64.65  4569.3   65.43  4649.3   64.23  4969.2   63.27
  5001.4   62.37  5013.4   63.09  5067.5   63.49  5274.3   64.89    5297    64.2
  5308.7   65.43  5353.7   64.36  5604.5   65.05  5614.6   65.75  5626.4    69.2
  5642.7   71.52  5648.7   73.77  5658.9    74.1  5664.6   75.75  5689.4   75.72
#Mann= 3 , 0 , 0
  3622.9     .05       0  4969.2     .03       0  5067.5     .05       0
Bank Sta=4969.2,5067.5
XS Rating Curve= 0 ,0
Exp/Cntr=0.3,0.1

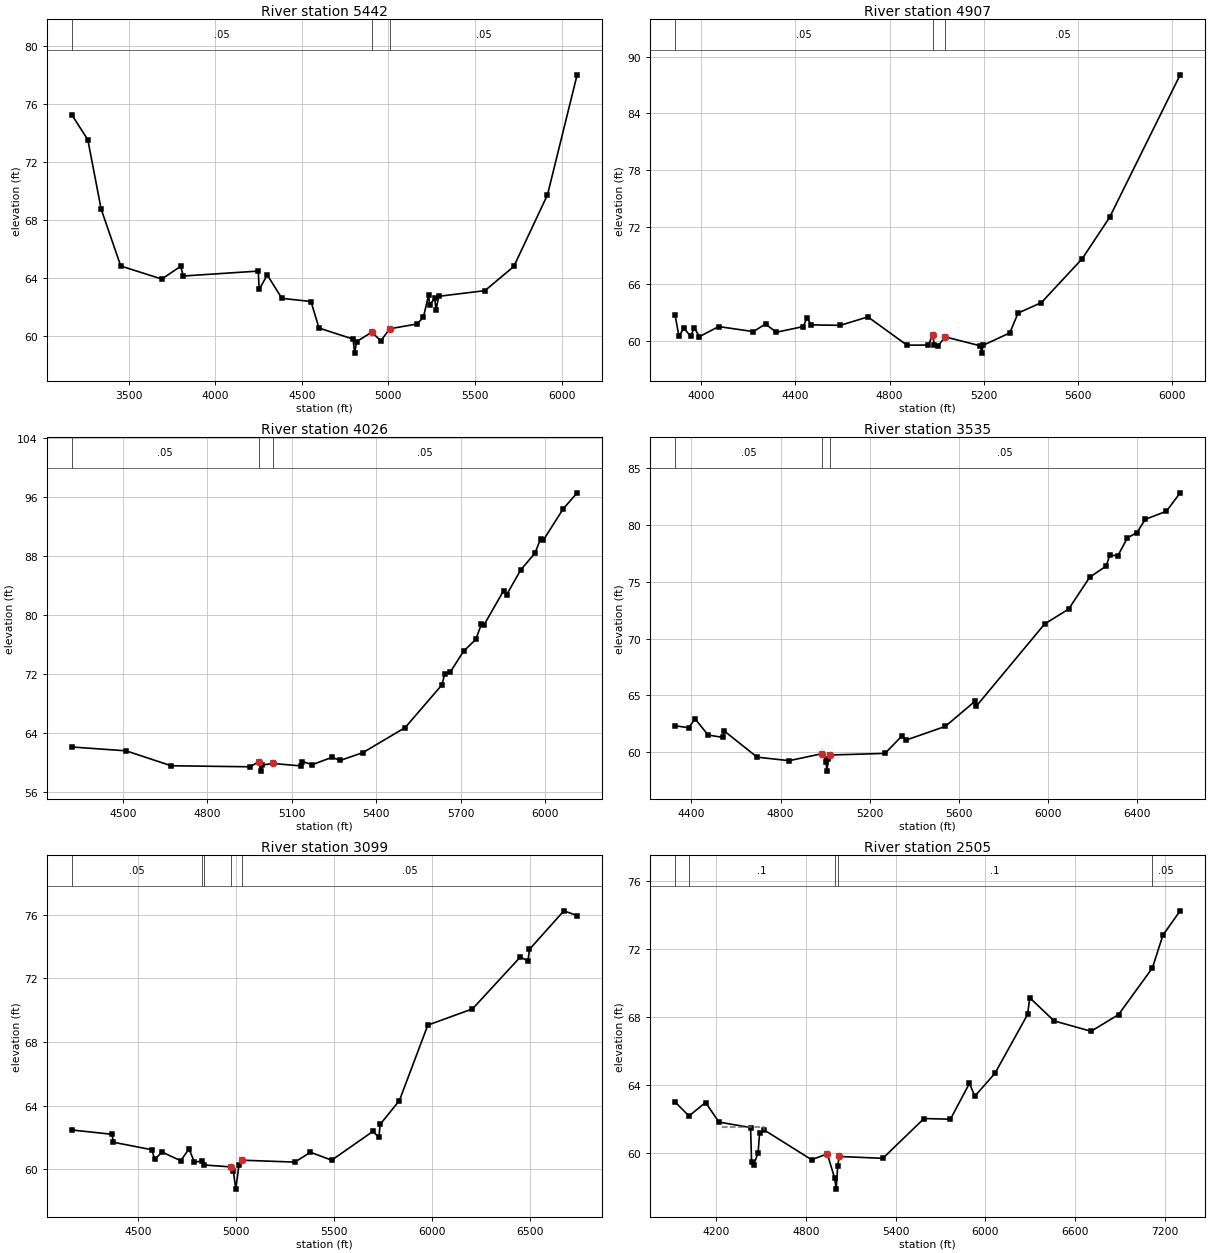
Type RM Length L Ch R = 1 ,5442    ,535,535,535
BEGIN DESCRIPTION:
UNT003 IN BACR 7.0
END DESCRIPTION:
XS GIS Cut Line= 4
      2350011.24     13186064.24      2348950.25       13185799.
      2348385.15     13185983.52      2347727.79     13187021.46
#Sta/Elev= 30
  3173.2   75.23    3265   73.52  3341.8   68.74  3455.1   64.81  3692.2   63.91
    3801   64.79  3815.9   64.12  4248.8   64.46  4254.5    63.2  4301.1   64.19
  4385.2   62.58  4553.5   62.36  4599.5   60.53  4796.1   59.77  4805.8    58.8
  4816.5   59.59    4905   60.25  4956.7   59.64  5007.3   60.48    5166   60.81
  5202.4   61.28  5232.2   62.79  5238.9   62.12  5267.7   62.59  5275.3   61.78
  5290.6   62.72  5557.5   63.11  5724.5   64.78  5918.7   69.72  6089.9      78
#Mann= 3 , 0 , 0
  3173.2     .05       0    4905     .03       0  5007.3     .05       0
Bank Sta=4905,5007.3
XS Rating Curve= 0 ,0
Exp/Cntr=0.3,0.1

Type RM Length L Ch R = 1 ,4907    ,881,881,881
BEGIN DESCRIPTION:
UNT003 IN BACR 6.0
END DESCRIPTION:
XS GIS Cut Line= 4
      2348282.11     13185149.48      2347900.77     13185845.13
      2347716.25     13186341.04      2347508.67     13187136.77
#Sta/Elev= 30
  3889.1    62.8  3905.9   60.54  3927.7   61.36  3955.2    60.5  3971.3   61.38
  3993.1   60.47  4074.7   61.53  4221.6      61  4273.8    61.8  4319.2   60.93
    4434   61.53  4450.1   62.48  4466.2   61.71  4591.3   61.66  4708.2   62.55
  4874.3   59.57  4965.3   59.58    4983   60.67  4990.3   59.57  5004.4   59.45
  5036.4   60.44  5185.7    59.5  5191.8   58.73  5197.4   59.56  5310.6   60.86
  5345.6   62.95  5444.9   64.06  5618.6    68.7  5734.3   73.04  6033.9   88.07
#Mann= 3 , 0 , 0
  3889.1     .05       0    4983     .03       0  5036.4     .05       0
Bank Sta=4983,5036.4
XS Rating Curve= 0 ,0
Exp/Cntr=0.3,0.1

Type RM Length L Ch R = 1 ,4026    ,491,491,491
BEGIN DESCRIPTION:
Mapping XS 4438b6bb
END DESCRIPTION:
XS GIS Cut Line= 2
      2346969.76     13185464.81      2346844.77     13187256.46
#Sta/Elev= 30
  4318.4   62.05  4510.9   61.53  4671.3    59.5    4952   59.36  4982.1   60.04
  4990.4   58.77  4995.7    59.6  5032.2   59.81  5132.4   59.48  5137.7   60.07
  5172.5   59.65  5242.7   60.64  5272.8   60.23    5353   61.29  5503.3    64.7
  5633.6   70.49  5643.7   71.97  5663.7   72.26  5710.8   75.08  5753.9   76.67
    5774   78.74    5784   78.69  5852.8   83.29  5864.2   82.78  5914.3   86.15
  5964.4    88.4  5984.5   90.35  5994.5   90.19  6064.7   94.42  6114.4   96.61
#Mann= 3 , 0 , 0
  4318.4     .05       0  4982.1     .03       0  5032.2     .05       0
Bank Sta=4982.1,5032.2
XS Rating Curve= 0 ,0
Exp/Cntr=0.3,0.1

Type RM Length L Ch R = 1 ,3535    ,436,436,436
BEGIN DESCRIPTION:
Mapping XS 1a2f4d2f
END DESCRIPTION:
XS GIS Cut Line= 2
        2346784.     13185489.09      2345622.64     13187436.84
#Sta/Elev= 30
  4325.8   62.33  4387.1   62.15  4416.3   62.93  4474.6   61.51  4540.8    61.3
  4546.7   61.87  4694.6   59.56  4838.6   59.25  4986.6   59.87  5004.3   59.17
  5007.8   58.33  5013.8   59.37  5021.8   59.75  5268.8   59.89  5342.8   61.39
  5364.2   61.07  5539.4   62.27  5671.8   64.47  5677.6   64.03  5985.2   71.29
  6092.9    72.6  6187.6   75.41  6261.5   76.39  6277.1   77.34  6314.1   77.31
  6356.9   78.88  6399.7   79.34  6436.7    80.5  6532.1   81.22  6593.5   82.84
#Mann= 3 , 0 , 0
  4325.8     .05       0  4986.6     .03       0  5021.8     .05       0
Bank Sta=4986.6,5021.8
XS Rating Curve= 0 ,0
Exp/Cntr=0.3,0.1

Type RM Length L Ch R = 1 ,3099    ,594,594,594
BEGIN DESCRIPTION:
Mapping XS 221f68d4
END DESCRIPTION:
XS GIS Cut Line= 3
      2346763.15     13185452.63      2345336.09       13186312.
      2345096.55     13187192.04
#Sta/Elev= 30
    4162   62.46  4366.8   62.19  4373.2   61.69  4569.3   61.22  4584.8   60.62
  4621.7   61.07  4716.9   60.53  4759.6   61.26    4787   60.45  4823.2   60.49
  4835.8   60.26  4971.3   60.14  4985.5   59.89  4998.2   58.74    5014   60.23
  5029.6   60.56  5299.5   60.44  5379.1   61.06  5487.4   60.56  5697.6   62.37
  5728.7      62  5734.5   62.81  5832.9   64.31    5978   69.06    6206   70.08
  6449.7   73.34  6489.5    73.1  6496.2   73.82  6672.3   76.25  6739.9   75.95
#Mann= 5 ,-1 , 0
    4162     .05       0  4823.2      .1       0  4835.8     .05       0
  4971.3     .03       0  5029.6     .05       0
Bank Sta=4971.3,5029.6
XS Rating Curve= 0 ,0
Exp/Cntr=0.3,0.1

Type RM Length L Ch R = 1 ,2505    ,568,568,568
BEGIN DESCRIPTION:
UNT003 IN BACR 5.0
END DESCRIPTION:
XS GIS Cut Line= 3
      2346711.11     13185400.54      2345257.96     13185546.37
      2343919.41     13186921.38
#Sta/Elev= 30
  3924.1   63.03    4018    62.2  4128.5   62.99    4219   61.84    4430   61.52
  4436.5   59.52  4450.1   59.31  4480.3   60.04  4490.3   61.21  4520.5   61.38
  4837.8   59.63  4943.2   59.97  4992.8   58.53  5002.6    57.9  5012.9   59.27
    5023   59.82  5314.4   59.71  5590.2   62.05  5766.9   62.01  5894.2   64.12
  5929.5   63.36    6064    64.7  6283.1   68.17  6297.3   69.15  6459.9   67.79
  6707.5   67.18  6891.4   68.16  7117.6    70.9  7188.3   72.83  7303.5   74.26
#Mann= 5 ,-1 , 0
  3924.1     .05       0    4018      .1       0  4992.8     .05       0
  5012.9      .1       0  7117.6     .05       0
#XS Ineff= 1 ,-1
    4236  4520.8   61.54
Permanent Ineff=
       F
Bank Sta=4943.2,5023
XS Rating Curve= 0 ,0
Exp/Cntr=0.3,0.1

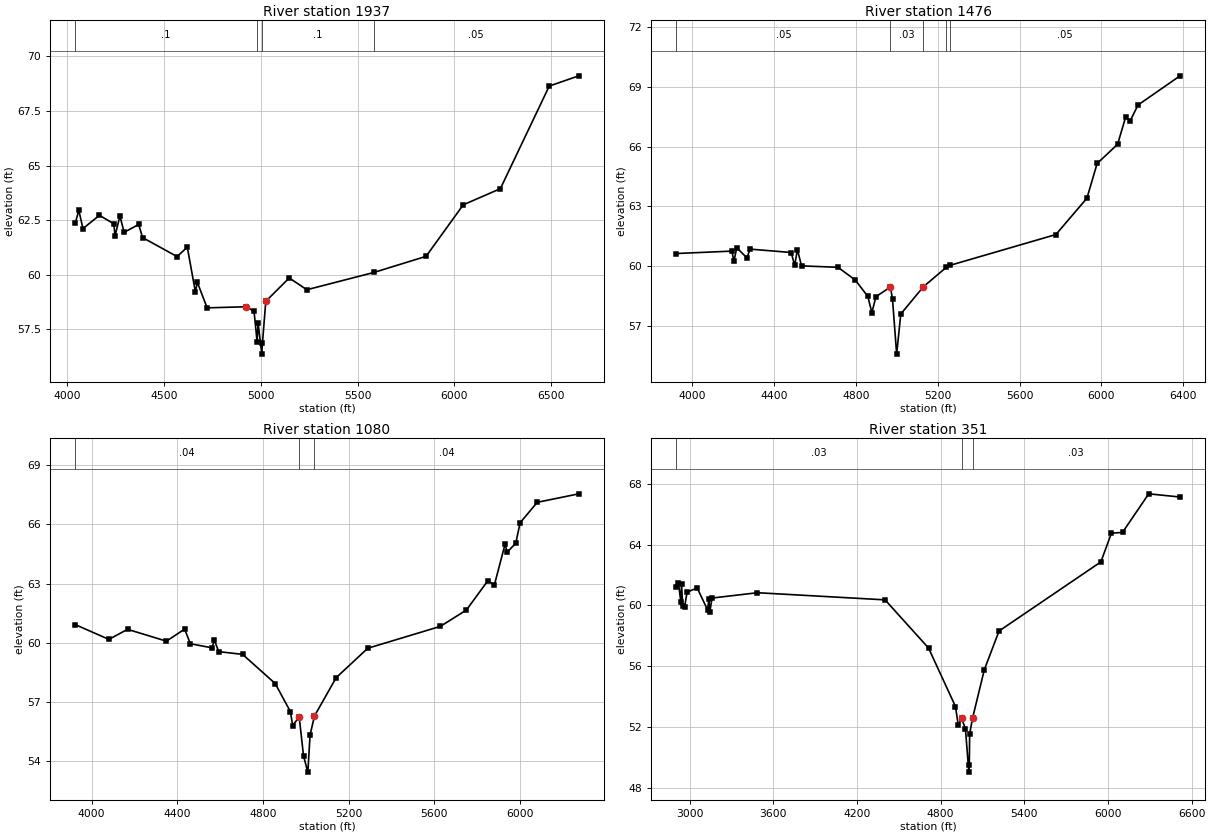
Type RM Length L Ch R = 1 ,1937    ,461,461,461
BEGIN DESCRIPTION:
UNT003 IN BACR 4.0
END DESCRIPTION:
XS GIS Cut Line= 3
      2346655.23     13185222.36       2346147.8     13185037.84
       2344106.5     13184749.52
#Sta/Elev= 30
  4041.2   62.35  4059.8   62.95  4081.1   62.11  4166.2   62.72  4240.7   62.33
  4246.8   61.77    4272   62.69  4293.9   61.94  4369.1    62.3  4389.1    61.7
  4567.3   60.83  4620.2   61.26    4662   59.21  4672.1   59.65  4722.6   58.48
  4924.6   58.53    4965   58.32  4980.8   56.93  4985.8    57.8  5005.1   56.36
  5008.4   56.86  5025.6   58.78  5146.8   59.85  5237.7   59.31  5583.4    60.1
  5853.7   60.84  6045.6    63.2  6237.5   63.94    6490   68.64  6642.7   69.11
#Mann= 4 ,-1 , 0
  4041.2      .1       0  4980.8     .05       0  5008.4      .1       0
  5583.4     .05       0
Bank Sta=4924.6,5025.6
XS Rating Curve= 0 ,0
Exp/Cntr=0.3,0.1

Type RM Length L Ch R = 1 ,1476    ,396,396,396
BEGIN DESCRIPTION:
UNT003 IN BACR 3.0
END DESCRIPTION:
XS GIS Cut Line= 4
      2346528.41       13184911.      2346136.26     13184668.79
      2344613.94     13184449.67      2344152.72      13184461.2
#Sta/Elev= 30
    3924   60.64  4195.2   60.76  4204.4   60.24  4218.7   60.93  4268.2   60.42
  4283.6   60.86  4484.5   60.69  4501.7   60.04  4514.8   60.84    4535   60.02
  4713.1   59.95  4797.7   59.31    4859   58.49  4878.5   57.68  4898.7   58.48
  4969.4   58.96  4979.5   58.35  4999.7    55.6  5019.9   57.61  5130.8   58.98
  5242.7   59.95  5261.3   60.05  5777.7   61.59  5929.2   63.41  5979.2   65.15
  6079.2   66.11  6119.2    67.5  6139.2   67.26  6179.2   68.08  6384.3   69.54
#Mann= 5 ,-1 , 0
    3924     .05       0  4969.4     .03       0  5130.8     .05       0
  5242.7      .1       0  5261.3     .05       0
Bank Sta=4969.4,5130.8
XS Rating Curve= 0 ,0
Exp/Cntr=0.3,0.1

Type RM Length L Ch R = 1 ,1080    ,729,729,729
BEGIN DESCRIPTION:
UNT003 IN BACR 2.0
END DESCRIPTION:
XS GIS Cut Line= 4
      2346586.01     13184507.31      2346309.26     13184322.81
      2344948.39     13184080.62      2344314.09     13184115.22
#Sta/Elev= 30
    3924   60.92  4081.1   60.17  4168.3   60.68  4349.6   60.08  4434.6   60.69
  4461.3   59.95  4562.9   59.74    4573   60.15  4593.4   59.55  4705.1   59.41
  4857.4   57.93  4928.5    56.5  4938.7    55.8  4969.2   56.24  4989.5   54.26
  5009.6   53.44    5020   55.32  5040.3   56.28  5141.8   58.23  5289.2   59.72
  5628.1   60.83  5749.7   61.66    5850   63.15  5879.9   62.92    5930      65
    5940   64.59    5980   65.05  6000.1   66.08  6080.2   67.12  6274.1   67.55
#Mann= 3 , 0 , 0
    3924     .04       0  4969.2     .03       0  5040.3     .04       0
Bank Sta=4969.2,5040.3
XS Rating Curve= 0 ,0
Exp/Cntr=0.3,0.1

Type RM Length L Ch R = 1 ,351     ,0,0,0
BEGIN DESCRIPTION:
UNT003 IN BACR 1.0
END DESCRIPTION:
XS GIS Cut Line= 5
      2347537.74     13184446.86      2346518.38     13183943.94
      2346150.32     13183582.83      2345476.71     13183457.83
      2344323.93      13183999.5
#Sta/Elev= 30
  2905.9    61.2  2919.9   61.51  2936.8   60.25  2942.4    61.4  2950.5   59.99
  2964.8   59.91  2981.7   60.88  3054.6   61.15  3128.9   59.71  3138.9   60.45
  3144.4   59.55  3161.3   60.49  3486.8   60.84  4401.6   60.37  4713.4    57.2
  4906.6   53.35    4927    52.1  4949.8   52.58  4977.8    51.9  5002.4   49.03
  5005.6   49.53  5008.4   51.55  5028.7   52.57  5113.4   55.77  5219.1   58.32
  5949.3   62.87  6024.9   64.76  6104.4   64.81  6292.4   67.35    6517   67.14
#Mann= 3 , 0 , 0
  2905.9     .03       0  4949.8    .025       0  5028.7     .03       0
Bank Sta=4949.8,5028.7
XS Rating Curve= 0 ,0
Exp/Cntr=0.3,0.1

Chan Stop Cuts=-1
Use User Specified Reach Order=0
Composite Channel Slope=5