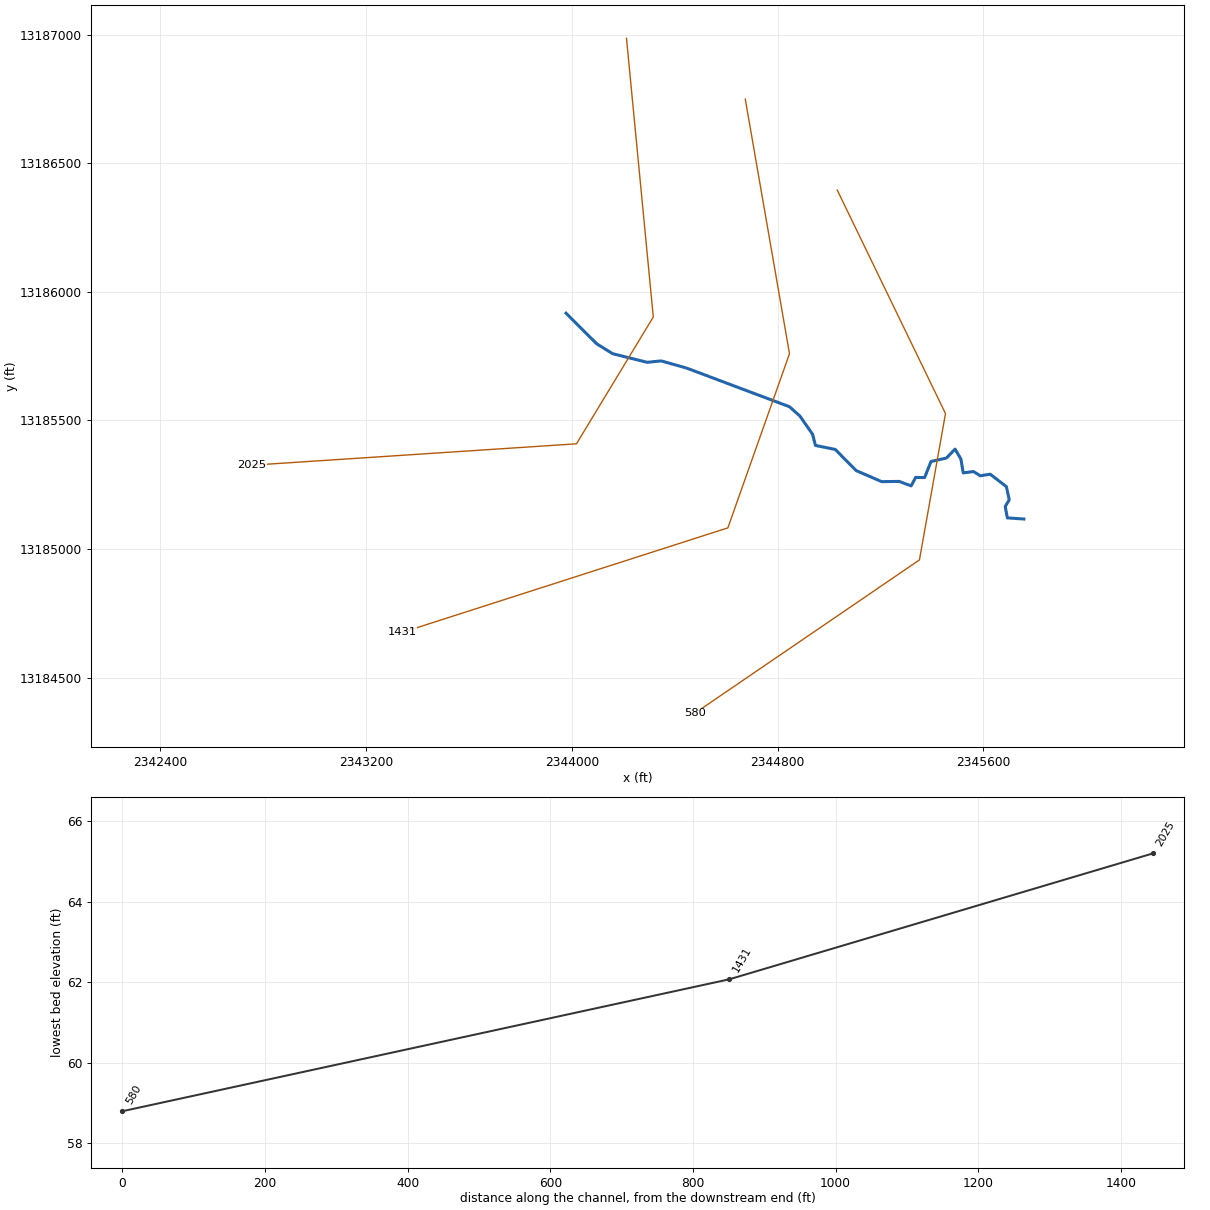
--- UNT004 IN BACR.prj (project) ---

Proj Title=UNT004 IN BACR Base Level Engineering
Current Plan=p01
Default Exp/Contr=0.3,0.1
English Units
Geom File=g01
Flow File=f01
Plan File=p01
Y Axis Title=Elevation
X Axis Title(PF)=Main Channel Distance
X Axis Title(XS)=Station
BEGIN DESCRIPTION:
UNT004 IN BACR
END DESCRIPTION:
DSS Export Rating Curves= 0
DSS Export Rating Curve Sorted= 0
DSS Export Volume Flow Curves= 0
DXF OffsetX= 0
DXF OffsetY= 0
DXF ScaleX= 1
DXF ScaleY= 10

--- UNT004 IN BACR.p01 (plan) ---

Plan Title=Multiple Run
Short Identifier=Multiple
Geom File=g01
Flow File=f01
Subcritical Flow
K Sum by GR= 0
Std Step Tol= 0.01
Critical Tol= 0.01
Num of Std Step Trials= 20
Max Error Tol= 0.3
Flow Tol Ratio= 0.001
Split Flow NTrial= 30
Split Flow Tol= 0.02
Split Flow Ratio= 0.02
Log Output Level= 0
Friction Slope Method= 1
Unsteady Friction Slope Method= 2
Unsteady Bridges Friction Slope Method= 1
Parabolic Critical Depth
Global Vel Dist=  1 , 1 , 1
Global Log Level= 0
CheckData=True
Encroach Param= -1, 0, 0, 0
BEGIN DESCRIPTION:
Multiple Run
END DESCRIPTION:

--- UNT004 IN BACR.f01 (steady flow) ---

Flow Title=Multiple
Number of Profiles=7
Profile Names=10-year,25-year,50-year,1pct_min,100-year,1pct_plu,500-year
River Rch & RM= UNT004 IN BACR,Reach-1,2025
     508     661     779     532     902    1271    1197
Boundary for River Rch & Prof#=UNT004 IN BACR,Reach-1,1
Up Type=0
Dn Type=3
Dn Slope=0.005
Boundary for River Rch & Prof#=UNT004 IN BACR,Reach-1,2
Up Type=0
Dn Type=3
Dn Slope=0.005
Boundary for River Rch & Prof#=UNT004 IN BACR,Reach-1,3
Up Type=0
Dn Type=3
Dn Slope=0.005
Boundary for River Rch & Prof#=UNT004 IN BACR,Reach-1,4
Up Type=0
Dn Type=3
Dn Slope=0.005
Boundary for River Rch & Prof#=UNT004 IN BACR,Reach-1,5
Up Type=0
Dn Type=3
Dn Slope=0.005
Boundary for River Rch & Prof#=UNT004 IN BACR,Reach-1,6
Up Type=0
Dn Type=3
Dn Slope=0.005
Boundary for River Rch & Prof#=UNT004 IN BACR,Reach-1,7
Up Type=0
Dn Type=3
Dn Slope=0.005

--- UNT004 IN BACR.g01 (geometry) ---

Geom Title=Existing Conditions
Program Version=4.10

River Reach=UNT004 IN BACR  ,Reach-1
Reach XY= 30
      2343977.72     13185916.86      2344097.36     13185797.83
      2344158.93      13185759.6      2344292.82     13185726.09
      2344347.99     13185731.52      2344446.42     13185703.63
      2344846.32     13185553.49      2344887.19     13185516.82
      2344936.29     13185446.24      2344947.46     13185402.87
      2345024.35     13185387.32      2345105.59     13185305.17
      2345204.71     13185262.18      2345272.79       13185263.
      2345319.26     13185245.59      2345337.06     13185278.56
      2345371.72      13185277.9      2345396.84     13185340.44
      2345456.81     13185353.97      2345490.21     13185388.59
      2345512.91     13185350.02      2345521.95     13185296.23
      2345561.79     13185301.37      2345588.89     13185284.73
      2345626.81     13185291.17      2345689.76     13185242.56
      2345700.86     13185191.37      2345685.23     13185165.43
      2345693.45     13185121.25      2345757.72     13185116.86

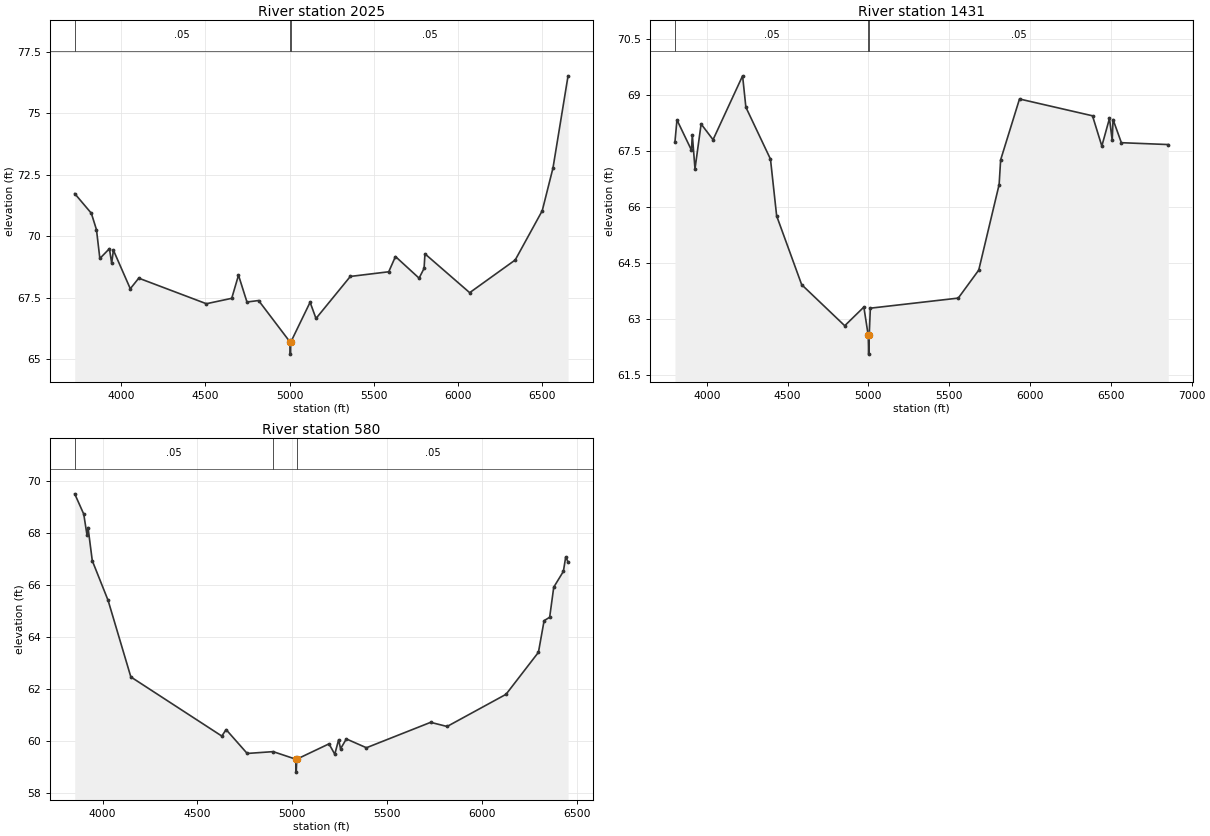
Type RM Length L Ch R = 1 ,2025    ,594,594,594
BEGIN DESCRIPTION:
UNT004 IN BACR 2.0
END DESCRIPTION:
XS GIS Cut Line= 4
      2344212.82     13186985.61      2344316.99     13185902.28
      2344018.38     13185409.22      2342754.49     13185325.89
#Sta/Elev= 30
  3722.9   71.73  3821.7   70.93  3852.3   70.26  3872.3   69.09  3929.2   69.49
  3942.7   68.89  3952.7   69.43  4053.2   67.86  4103.4   68.29  4505.2   67.25
  4655.9   67.47  4696.1   68.41  4746.4   67.32  4815.6   67.38  5001.6    65.7
  5004.4    65.2  5007.6    65.7  5121.5   67.31  5156.6   66.65  5360.6   68.36
  5588.8   68.55  5628.8   69.17  5769.1   68.29  5798.9   68.69  5803.9   69.28
  6069.8    67.7  6340.4   69.03  6500.7   71.03  6564.7   72.77  6654.3   76.52
#Mann= 3 ,-1 , 0
  3722.9     .05       0  5001.6     .03       0  5007.6     .05       0
Bank Sta=5001.6,5007.6
XS Rating Curve= 0 ,0
Exp/Cntr=0.3,0.1

Type RM Length L Ch R = 1 ,1431    ,851,851,851
BEGIN DESCRIPTION:
Mapping XS 23fa42e9
END DESCRIPTION:
XS GIS Cut Line= 4
      2344674.63     13186749.07       2344846.5     13185759.48
      2344606.92      13185082.4      2343341.25     13184676.13
#Sta/Elev= 30
  3803.6   67.75    3816   68.34  3905.8   67.53  3910.9   67.94  3927.6   67.03
  3965.5   68.23  4039.3   67.81    4222   69.52  4242.3   68.68  4394.5   67.29
  4432.7   65.77  4587.4   63.93  4853.9   62.83  4972.2   63.33  4999.2   62.57
  5001.9   62.07  5005.2   62.57  5012.3    63.3  5556.2   63.57  5682.9   64.32
    5809   66.61  5818.3   67.27    5935    68.9  6386.6   68.45  6444.3   67.64
  6491.6   68.38  6508.5   67.79  6513.7   68.35  6565.1   67.73  6855.5   67.68
#Mann= 3 ,-1 , 0
  3803.6     .05       0  4999.2     .03       0  5005.2     .05       0
Bank Sta=4999.2,5005.2
XS Rating Curve= 0 ,0
Exp/Cntr=0.3,0.1

Type RM Length L Ch R = 1 ,580     ,0,0,0
BEGIN DESCRIPTION:
UNT004 IN BACR 1.0
END DESCRIPTION:
XS GIS Cut Line= 4
      2345032.28      13186395.3      2345453.04     13185526.79
      2345351.71     13184957.83      2344477.59     13184361.21
#Sta/Elev= 30
  3852.7   69.52  3900.3   68.74  3917.3   67.94  3922.9   68.22  3945.4   66.94
  4028.8   65.41  4148.7   62.46  4628.4   60.18    4651   60.43  4762.1   59.51
    4899   59.58  5017.8   59.29  5020.6   58.79  5023.8   59.29  5193.5   59.88
    5224   59.48  5244.3   60.04  5254.5   59.69  5284.9   60.07  5390.8   59.73
  5729.5   60.71  5816.2   60.55  6126.9   61.79  6297.8   63.41  6327.7   64.63
    6357   64.76  6378.5   65.92  6429.3   66.53  6441.7   67.09    6454   66.89
#Mann= 3 ,-1 , 0
  3852.7     .05       0    4899    .035       0  5023.8     .05       0
Bank Sta=5017.8,5023.8
XS Rating Curve= 0 ,0
Exp/Cntr=0.3,0.1

Chan Stop Cuts=-1
Use User Specified Reach Order=0
Composite Channel Slope=5