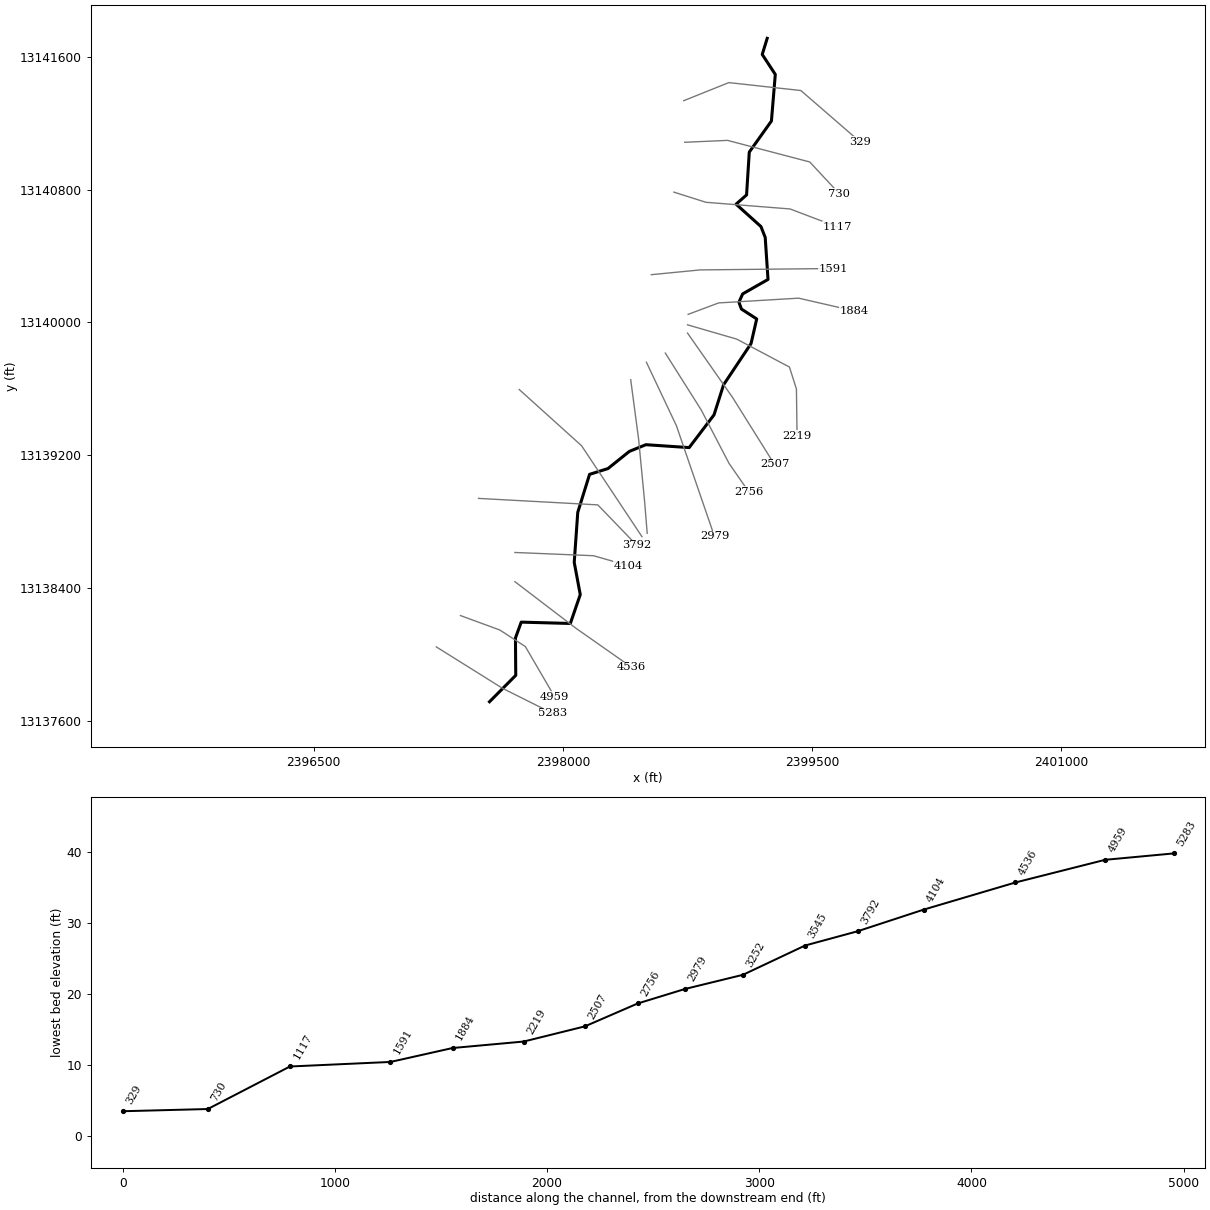
--- UNT006 IN BACR.prj (project) ---

Proj Title=UNT006 IN BACR Base Level Engineering
Current Plan=p01
Default Exp/Contr=0.3,0.1
English Units
Geom File=g01
Flow File=f01
Plan File=p01
BEGIN DESCRIPTION:
UNT006 IN BACR
END DESCRIPTION:

--- UNT006 IN BACR.p01 (plan) ---

Plan Title=Multiple Run
Short Identifier=Multiple
Geom File=g01
Flow File=f01
Subcritical Flow
K Sum by GR= 0
Std Step Tol= 0.01
Critical Tol= 0.01
Num of Std Step Trials= 20
Max Error Tol= 0.3
Flow Tol Ratio= 0.001
Split Flow NTrial= 30
Split Flow Tol= 0.02
Split Flow Ratio= 0.02
Log Output Level= 0
Friction Slope Method= 1
Unsteady Friction Slope Method= 2
Unsteady Bridges Friction Slope Method= 1
Parabolic Critical Depth
Global Vel Dist=  1 , 1 , 1
Global Log Level= 0
CheckData=True
Encroach Param= -1, 0, 0, 0
BEGIN DESCRIPTION:
Multiple Run
END DESCRIPTION:

--- UNT006 IN BACR.f01 (steady flow) ---

Flow Title=Multiple
Number of Profiles=7
Profile Names=10-year,25-year,50-year,1pct_min,100-year,1pct_plu,500-year
River Rch & RM= UNT006 IN BACR,Reach-1,5283
     372     508     620     554     749    1014    1105
Boundary for River Rch & Prof#=UNT006 IN BACR,Reach-1,1
Up Type=0
Dn Type=3
Dn Slope=0.005
Boundary for River Rch & Prof#=UNT006 IN BACR,Reach-1,2
Up Type=0
Dn Type=3
Dn Slope=0.005
Boundary for River Rch & Prof#=UNT006 IN BACR,Reach-1,3
Up Type=0
Dn Type=3
Dn Slope=0.005
Boundary for River Rch & Prof#=UNT006 IN BACR,Reach-1,4
Up Type=0
Dn Type=3
Dn Slope=0.005
Boundary for River Rch & Prof#=UNT006 IN BACR,Reach-1,5
Up Type=0
Dn Type=3
Dn Slope=0.005
Boundary for River Rch & Prof#=UNT006 IN BACR,Reach-1,6
Up Type=0
Dn Type=3
Dn Slope=0.005
Boundary for River Rch & Prof#=UNT006 IN BACR,Reach-1,7
Up Type=0
Dn Type=3
Dn Slope=0.005

--- UNT006 IN BACR.g01 (geometry) ---

Geom Title=Existing Conditions

River Reach=UNT006 IN BACR,Reach-1
Reach XY= 30
      2397557.72     13137716.85      2397715.64     13137875.78
      2397713.90     13138100.76      2397748.57     13138196.10
      2398044.27     13138188.04      2398103.94     13138361.86
      2398067.67     13138555.77      2398088.89     13138856.88
      2398160.02     13139085.59      2398270.89     13139120.54
      2398399.55     13139223.91      2398498.93     13139264.17
      2398759.50     13139246.66      2398909.05     13139443.63
      2398966.69     13139624.88      2399131.97     13139872.80
      2399166.09     13140021.12      2399074.10     13140080.64
      2399058.98     13140121.75      2399081.63     13140171.90
      2399234.10     13140258.93      2399217.25     13140511.79
      2399191.62     13140577.14      2399041.84     13140711.97
      2399104.99     13140767.54      2399121.34     13141025.36
      2399254.65     13141212.47      2399277.99     13141492.93
      2399199.34     13141613.20      2399229.20     13141710.18

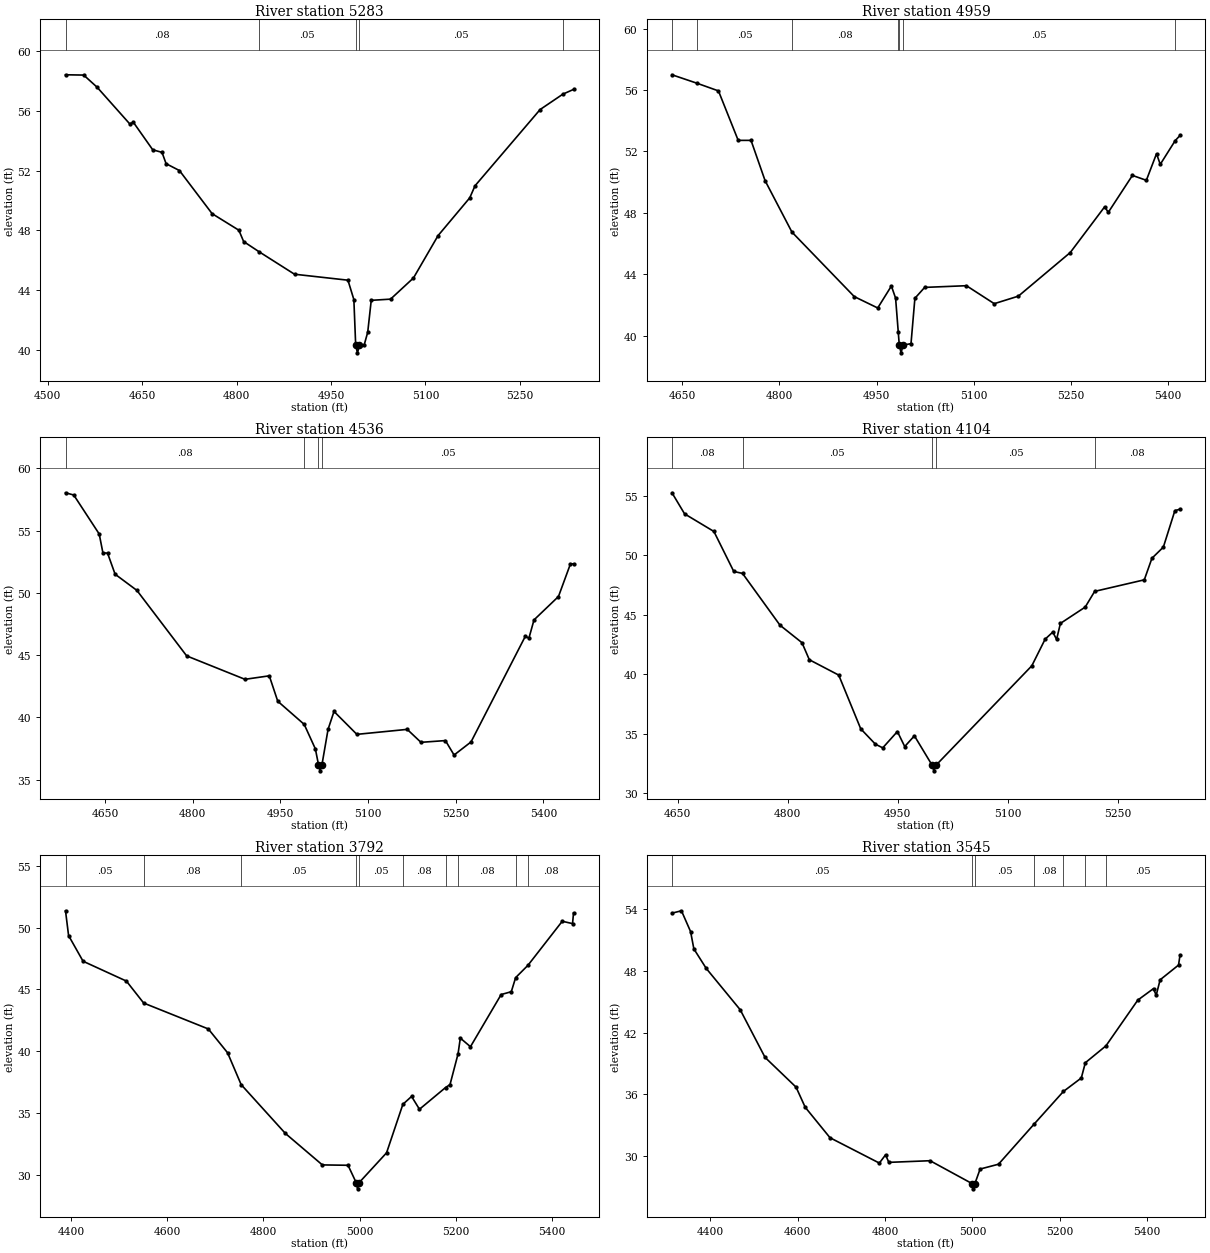
Type RM Length L Ch R = 1,5283,324,324,324
BEGIN DESCRIPTION:
UNT006 IN BACR 11.0
END DESCRIPTION:
XS GIS Cut Line= 3
      2397237.72     13138046.86      2397637.72     13137796.85
      2397937.71     13137646.86
#Sta/Elev= 30
  4528.2   58.43  4557.1   58.41  4578.3   57.60  4630.2   55.14  4636.1   55.24
  4666.8   53.40  4681.5   53.23  4688.0   52.47  4709.2   52.01  4761.1   49.12
  4803.6   48.01  4811.2   47.25  4835.6   46.57  4892.0   45.06  4976.9   44.66
  4986.3   43.36  4989.2   40.29  4992.0   39.79  4995.2   40.29  5002.7   40.32
  5008.3   41.17  5013.9   43.31  5044.6   43.39  5081.0   44.81  5120.1   47.65
  5170.4   50.18  5178.8   50.99  5282.2   56.10  5318.3   57.13  5335.3   57.45
#Mann=5,-1,0
  4528.2    0.08       0  4835.6    0.05       0  4989.2    0.04       0
  4995.2    0.05       0  5318.3    0.08       0
Bank Sta=4989.2,4995.2
Exp/Cntr=0.3,0.1

Type RM Length L Ch R = 1,4959,423,423,423
BEGIN DESCRIPTION:
Mapping XS 38cb9c38
END DESCRIPTION:
XS GIS Cut Line= 4
      2397382.76     13138235.66      2397619.35     13138148.84
      2397773.43     13138049.01      2397949.19     13137747.39
#Sta/Elev= 30
  4634.0   56.99  4673.3   56.43  4705.8   55.94  4736.3   52.72  4756.1   52.72
  4777.8   50.10  4819.3   46.75  4915.6   42.55  4951.8   41.81  4972.9   43.24
  4979.4   42.45  4983.5   40.25  4985.1   39.39  4987.8   38.89  4991.1   39.39
  5003.2   39.49  5009.2   42.44  5024.3   43.15  5088.8   43.26  5131.8   42.09
  5169.0   42.58  5249.2   45.42  5302.2   48.39  5308.0   48.04  5345.2   50.44
  5366.7   50.12  5382.4   51.85  5388.2   51.16  5411.2   52.70  5418.7   53.04
#Mann=7,-1,0
  4634.0    0.08       0  4673.3    0.05       0  4819.3    0.08       0
  4983.5    0.05       0  4985.1    0.04       0  4991.1    0.05       0
  5411.2    0.08       0
Bank Sta=4985.1,4991.1
Exp/Cntr=0.3,0.1

Type RM Length L Ch R = 1,4536,432,432,432
BEGIN DESCRIPTION:
UNT006 IN BACR 10.0
END DESCRIPTION:
XS GIS Cut Line= 3
      2397710.46     13138439.66      2398077.25     13138159.69
      2398411.43     13137925.33
#Sta/Elev= 30
  4582.1   58.03  4596.2   57.85  4639.8   54.72  4646.1   53.21  4654.1   53.18
  4667.0   51.49  4704.3   50.19  4789.5   44.93  4889.3   43.05  4930.9   43.33
  4945.4   41.29  4990.7   39.43  5009.8   37.46  5015.1   36.20  5017.8   35.70
  5021.1   36.20  5031.5   39.03  5041.7   40.47  5080.8   38.63  5167.0   39.03
  5190.5   37.99  5232.4   38.13  5247.2   36.97  5276.2   38.02  5369.2   46.51
  5375.3   46.35  5384.0   47.82  5425.9   49.70  5446.4   52.32  5451.7   52.32
#Mann=4,-1,0
  4582.1    0.08       0  4990.7    0.05       0  5015.1    0.04       0
  5021.1    0.05       0
Bank Sta=5015.1,5021.1
Exp/Cntr=0.3,0.1

Type RM Length L Ch R = 1,4104,312,312,312
BEGIN DESCRIPTION:
UNT006 IN BACR 9.0
END DESCRIPTION:
XS GIS Cut Line= 3
      2397710.54     13138615.41      2398183.58     13138595.89
      2398394.50     13138535.62
#Sta/Elev= 30
  4642.0   55.24  4659.2   53.47  4699.2   51.99  4726.3   48.63  4738.2   48.47
  4789.3   44.12  4819.3   42.65  4829.3   41.22  4869.4   39.93  4899.4   35.42
  4919.4   34.13  4929.4   33.82  4949.4   35.19  4959.4   33.93  4972.6   34.83
  4996.5   32.39  4999.2   31.89  5002.5   32.39  5132.7   40.71  5150.9   42.95
  5161.3   43.54  5166.5   42.93  5171.7   44.27  5205.5   45.64  5218.4   46.96
  5286.1   47.93  5296.5   49.74  5312.1   50.68  5327.8   53.74  5334.8   53.86
#Mann=5,-1,0
  4642.0    0.08       0  4738.2    0.05       0  4996.5    0.04       0
  5002.5    0.05       0  5218.4    0.08       0
Bank Sta=4996.5,5002.5
Exp/Cntr=0.3,0.1

Type RM Length L Ch R = 1,3792,247,247,247
BEGIN DESCRIPTION:
UNT006 IN BACR 8.0
END DESCRIPTION:
XS GIS Cut Line= 3
      2397491.30     13138940.94      2398209.62     13138901.87
      2398443.35     13138659.49
#Sta/Elev= 30
  4388.6   51.38  4395.0   49.37  4425.1   47.29  4515.2   45.68  4551.1   43.90
  4685.5   41.80  4725.5   39.87  4753.7   37.29  4845.7   33.33  4922.5   30.78
  4975.9   30.75  4992.9   29.34  4995.7   28.84  4998.9   29.34  5056.0   31.76
  5089.9   35.69  5108.0   36.33  5124.4   35.29  5178.6   37.05  5187.9   37.29
  5204.6   39.78  5209.3   41.06  5230.4   40.36  5294.2   44.59  5315.3   44.82
  5324.3   45.96  5349.9   46.96  5421.2   50.53  5442.6   50.34  5444.7   51.21
#Mann=10,-1,0
  4388.6    0.05       0  4551.1    0.08       0  4753.7    0.05       0
  4992.9    0.04       0  4998.9    0.05       0  5089.9    0.08       0
  5178.6    0.05       0  5204.6    0.08       0  5324.3    0.05       0
  5349.9    0.08       0
Bank Sta=4992.9,4998.9
Exp/Cntr=0.3,0.1

Type RM Length L Ch R = 1,3545,293,293,293
BEGIN DESCRIPTION:
Mapping XS b20c3314
END DESCRIPTION:
XS GIS Cut Line= 3
      2397736.53     13139596.32      2398111.97     13139257.78
      2398475.50     13138710.32
#Sta/Elev= 30
  4312.4   53.60  4334.1   53.83  4355.0   51.81  4362.5   50.13  4390.9   48.23
  4468.6   44.22  4525.4   39.60  4596.4   36.71  4617.3   34.76  4674.1   31.80
  4787.0   29.34  4801.2   30.14  4808.7   29.41  4903.1   29.57  4999.6   27.34
  5002.3   26.84  5005.6   27.34  5017.6   28.76  5059.7   29.23  5141.3   33.13
  5208.2   36.29  5249.2   37.60  5258.4   39.08  5305.6   40.72  5378.5   45.16
  5414.5   46.28  5420.5   45.62  5429.6   47.13  5471.7   48.56  5475.1   49.52
#Mann=7,-1,0
  4312.4    0.05       0  4999.6    0.04       0  5005.6    0.05       0
  5141.3    0.08       0  5208.2    0.05       0  5258.4    0.08       0
  5305.6    0.05       0
Bank Sta=4999.6,5005.6
Exp/Cntr=0.3,0.1

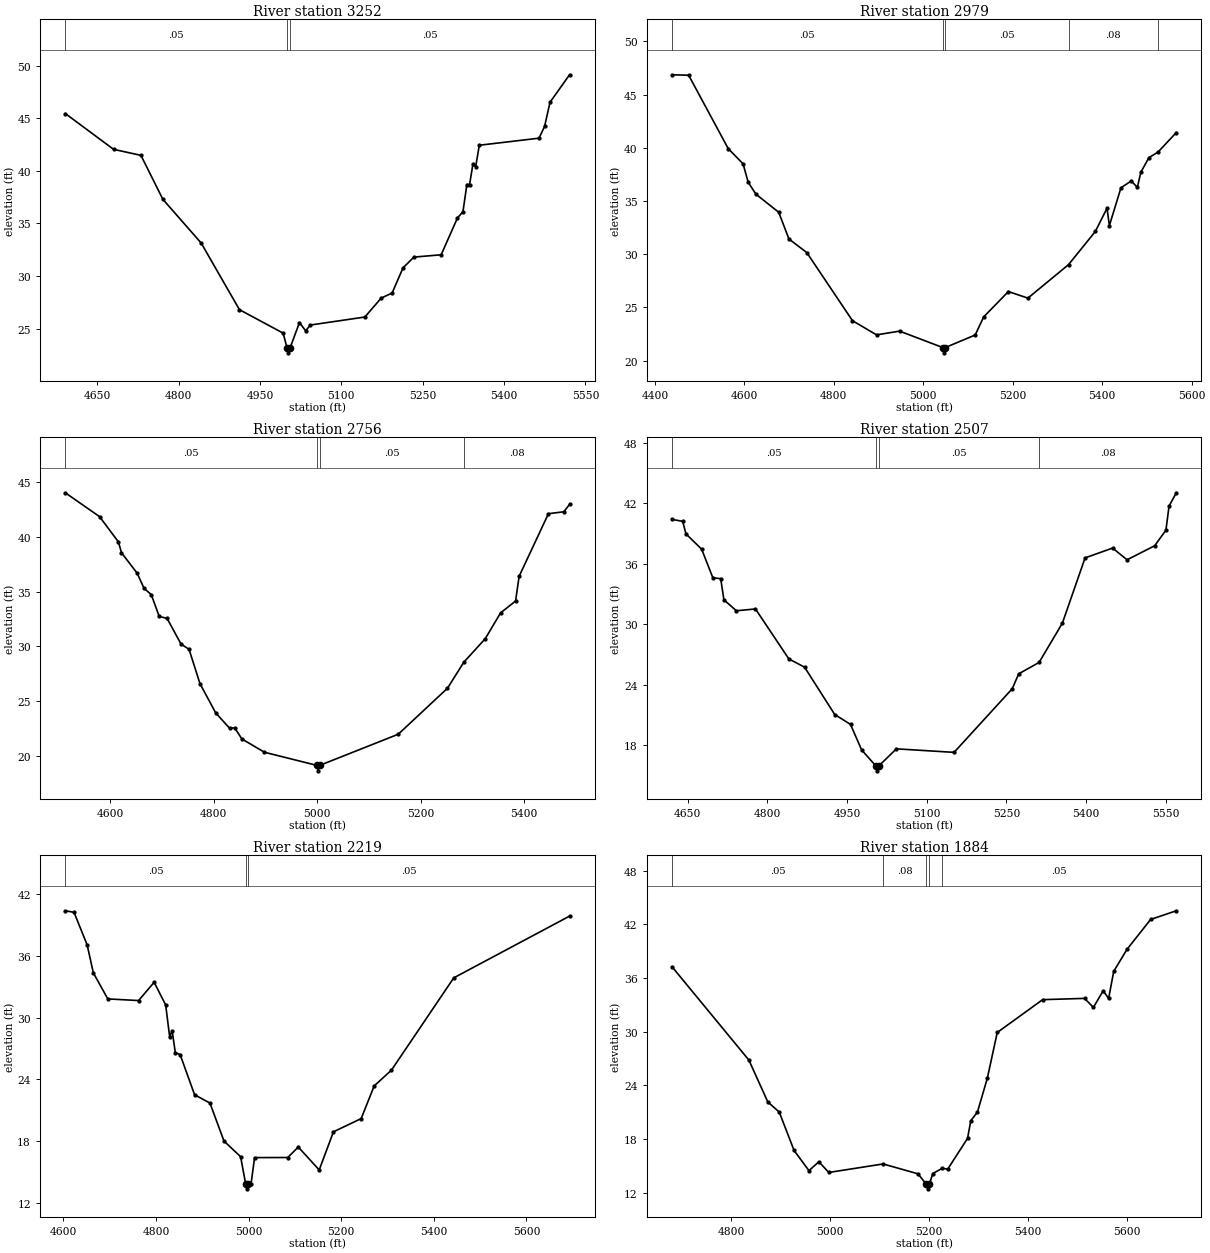
Type RM Length L Ch R = 1,3252,273,273,273
BEGIN DESCRIPTION:
UNT006 IN BACR 7.0
END DESCRIPTION:
XS GIS Cut Line= 4
      2398407.62     13139655.07      2398455.39     13139295.79
      2398491.70     13138917.42      2398506.92     13138730.99
#Sta/Elev= 30
  4591.1   45.44  4680.1   42.04  4730.5   41.47  4770.9   37.30  4841.5   33.15
  4912.1   26.82  4992.7   24.59  4999.7   23.22  5002.4   22.72  5005.7   23.22
  5022.8   25.60  5034.1   24.81  5042.9   25.36  5143.3   26.12  5173.5   27.92
  5193.6   28.40  5213.7   30.79  5233.8   31.81  5284.0   32.03  5314.1   35.53
  5324.2   36.12  5331.4   38.70  5336.4   38.70  5342.7   40.68  5347.7   40.39
  5354.3   42.43  5464.4   43.10  5474.7   44.22  5484.7   46.51  5520.7   49.12
#Mann=3,-1,0
  4591.1    0.05       0  4999.7    0.04       0  5005.7    0.05       0
Bank Sta=4999.7,5005.7
Exp/Cntr=0.3,0.1

Type RM Length L Ch R = 1,2979,223,223,223
BEGIN DESCRIPTION:
Mapping XS d63e5d95
END DESCRIPTION:
XS GIS Cut Line= 3
      2398502.15     13139760.40      2398682.71     13139378.44
      2398911.87     13138711.82
#Sta/Elev= 30
  4438.3   46.86  4475.4   46.82  4563.9   39.92  4597.1   38.49  4608.5   36.76
  4625.8   35.64  4676.8   33.94  4699.6   31.43  4739.6   30.15  4841.7   23.75
  4895.5   22.42  4947.1   22.77  5043.4   21.23  5046.2   20.73  5049.4   21.23
  5116.2   22.41  5134.9   24.10  5190.3   26.49  5233.9   25.87  5324.8   29.02
  5384.8   32.14  5410.8   34.32  5416.1   32.69  5442.0   36.24  5465.2   36.89
  5478.6   36.27  5486.4   37.70  5504.5   39.07  5525.0   39.60  5565.7   41.43
#Mann=5,-1,0
  4438.3    0.05       0  5043.4    0.04       0  5049.4    0.05       0
  5324.8    0.08       0  5525.0    0.05       0
Bank Sta=5043.4,5049.4
Exp/Cntr=0.3,0.1

Type RM Length L Ch R = 1,2756,249,249,249
BEGIN DESCRIPTION:
UNT006 IN BACR 6.0
END DESCRIPTION:
XS GIS Cut Line= 4
      2398615.94     13139815.54      2398831.85     13139473.51
      2399000.02     13139150.56      2399118.00     13138981.19
#Sta/Elev= 30
  4513.1   43.98  4579.3   41.81  4615.8   39.51  4621.7   38.53  4652.2   36.65
  4665.3   35.29  4679.3   34.72  4694.6   32.74  4709.9   32.55  4737.0   30.21
  4752.3   29.75  4773.5   26.62  4804.0   23.95  4831.1   22.55  4840.5   22.61
  4854.5   21.59  4898.2   20.38  4999.2   19.19  5002.0   18.69  5005.2   19.19
  5156.9   22.02  5252.0   26.20  5283.7   28.57  5325.1   30.71  5354.8   33.06
  5383.7   34.13  5390.6   36.38  5447.3   42.08  5477.0   42.25  5488.1   42.92
#Mann=4,-1,0
  4513.1    0.05       0  4999.2    0.04       0  5005.2    0.05       0
  5283.7    0.08       0
Bank Sta=4999.2,5005.2
Exp/Cntr=0.3,0.1

Type RM Length L Ch R = 1,2507,288,288,288
BEGIN DESCRIPTION:
UNT006 IN BACR 5.0
END DESCRIPTION:
XS GIS Cut Line= 3
      2398749.67     13139935.97      2399021.04     13139548.04
      2399273.00     13139145.28
#Sta/Elev= 30
  4620.9   40.38  4640.9   40.19  4647.0   38.95  4676.6   37.43  4697.6   34.60
  4712.4   34.51  4718.5   32.41  4741.9   31.33  4777.8   31.51  4840.6   26.56
  4870.2   25.74  4926.9   21.05  4956.6   20.07  4977.5   17.54  5004.1   15.97
  5006.9   15.47  5010.1   15.97  5042.9   17.65  5151.4   17.30  5260.9   23.61
  5272.9   25.08  5311.3   26.21  5355.2   30.11  5397.8   36.57  5449.6   37.54
  5476.8   36.38  5528.7   37.77  5549.9   39.31  5555.8   41.70  5569.4   43.02
#Mann=4,-1,0
  4620.9    0.05       0  5004.1    0.04       0  5010.1    0.05       0
  5311.3    0.08       0
Bank Sta=5004.1,5010.1
Exp/Cntr=0.3,0.1

Type RM Length L Ch R = 1,2219,335,335,335
BEGIN DESCRIPTION:
Mapping XS 8d0a5bd6
END DESCRIPTION:
XS GIS Cut Line= 5
      2398749.65     13139985.66      2399045.88     13139899.66
      2399363.10     13139731.49      2399405.14     13139599.63
      2399408.96     13139316.85
#Sta/Elev= 30
  4604.3   40.41  4623.1   40.26  4651.5   37.08  4664.8   34.37  4696.0   31.83
  4762.5   31.67  4796.1   33.45  4821.0   31.24  4829.6   28.14  4834.9   28.74
  4841.8   26.61  4852.2   26.41  4883.4   22.50  4916.6   21.69  4946.9   17.99
  4982.8   16.47  4993.6   13.84  4996.3   13.34  4999.6   13.84  5005.4   13.84
  5012.9   16.38  5084.6   16.39  5107.3   17.41  5152.5   15.18  5183.2   18.89
  5243.1   20.18  5271.2   23.36  5308.4   24.89  5443.0   33.88  5693.0   39.89
#Mann=3,-1,0
  4604.3    0.05       0  4993.6    0.04       0  4999.6    0.05       0
Bank Sta=4993.6,4999.6
Exp/Cntr=0.3,0.1

Type RM Length L Ch R = 1,1884,293,293,293
BEGIN DESCRIPTION:
UNT006 IN BACR 4.0
END DESCRIPTION:
XS GIS Cut Line= 4
      2398753.54     13140048.73      2398936.95     13140117.50
      2399418.52     13140146.17      2399751.05     13140069.73
#Sta/Elev= 30
  4680.9   37.24  4836.2   26.82  4874.5   22.14  4897.6   21.01  4927.6   16.72
  4957.7   14.46  4977.7   15.46  4997.8   14.26  5107.6   15.21  5178.1   14.11
  5195.1   12.93  5197.9   12.43  5201.1   12.93  5208.1   14.14  5227.3   14.73
  5238.2   14.63  5278.3   18.06  5284.9   20.04  5298.3   21.00  5318.3   24.78
  5338.4   29.90  5430.2   33.57  5514.9   33.71  5532.8   32.70  5552.6   34.56
  5563.6   33.70  5573.9   36.73  5600.6   39.18  5648.5   42.53  5700.4   43.50
#Mann=5,-1,0
  4680.9    0.05       0  5107.6    0.08       0  5195.1    0.04       0
  5201.1    0.08       0  5227.3    0.05       0
Bank Sta=5195.1,5201.1
Exp/Cntr=0.3,0.1

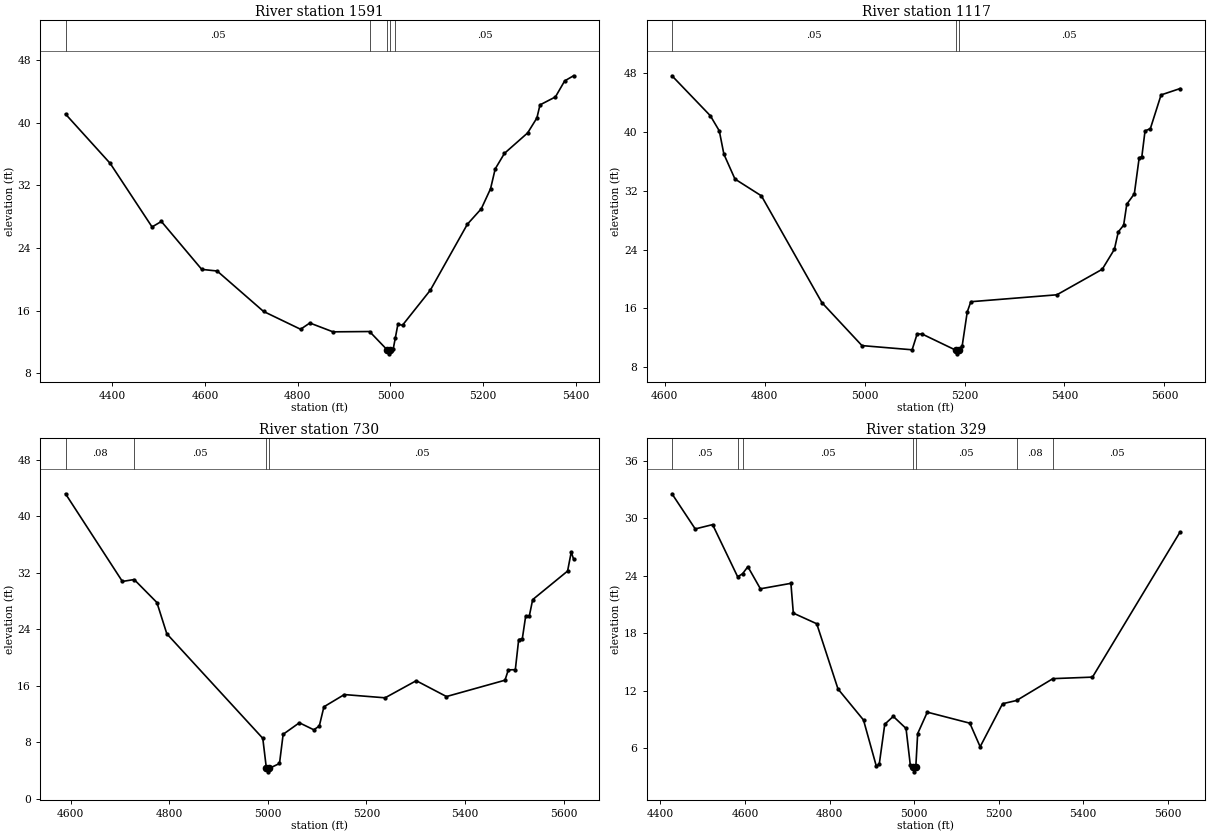
Type RM Length L Ch R = 1,1591,474,474,474
BEGIN DESCRIPTION:
Mapping XS f90eb858
END DESCRIPTION:
XS GIS Cut Line= 4
      2398531.82     13140287.58      2398826.12     13140316.24
      2399556.10     13140323.89      2399626.78     13140323.89
#Sta/Elev= 30
  4298.8   41.10  4395.2   34.80  4485.6   26.68  4505.7   27.38  4592.8   21.26
  4626.1   21.05  4726.1   15.89  4806.1   13.61  4826.1   14.41  4876.1   13.28
  4955.0   13.32  4993.1   10.97  4995.9   10.47  4999.1   10.97  5006.1   11.11
  5010.5   12.48  5016.1   14.23  5026.1   14.13  5086.1   18.60  5166.1   27.03
  5196.1   29.00  5216.1   31.56  5226.1   34.09  5246.1   36.08  5296.1   38.69
  5316.1   40.60  5322.8   42.27  5356.1   43.29  5376.1   45.34  5395.2   45.99
#Mann=5,-1,0
  4298.8    0.05       0  4955.0    0.08       0  4993.1    0.07       0
  4999.1    0.08       0  5010.5    0.05       0
Bank Sta=4993.1,4999.1
Exp/Cntr=0.3,0.1

Type RM Length L Ch R = 1,1117,387,387,387
BEGIN DESCRIPTION:
UNT006 IN BACR 3.0
END DESCRIPTION:
XS GIS Cut Line= 4
      2398667.49     13140784.44      2398860.52     13140723.28
      2399366.92     13140683.15      2399653.17     13140574.37
#Sta/Elev= 30
  4614.5   47.60  4691.3   42.17  4709.2   40.12  4718.4   36.95  4740.6   33.57
  4793.5   31.29  4914.5   16.79  4994.7   10.95  5095.1   10.38  5105.1   12.53
  5115.1   12.52  5182.3   10.33  5185.1    9.83  5188.3   10.33  5195.4   10.96
  5205.4   15.52  5212.6   16.91  5384.8   17.85  5475.6   21.32  5499.9   24.03
  5507.7   26.40  5518.4   27.31  5524.7   30.16  5539.8   31.57  5549.5   36.47
  5554.8   36.61  5561.2   40.11  5571.9   40.43  5593.3   45.00  5631.2   45.86
#Mann=3,-1,0
  4614.5    0.05       0  5182.3    0.04       0  5188.3    0.05       0
Bank Sta=5182.3,5188.3
Exp/Cntr=0.3,0.1

Type RM Length L Ch R = 1,730,401,401,401
BEGIN DESCRIPTION:
UNT006 IN BACR 2.0
END DESCRIPTION:
XS GIS Cut Line= 4
      2398732.46     13141084.45      2398990.46     13141095.92
      2399485.40     13140965.97      2399662.89     13140775.12
#Sta/Elev= 30
  4589.6   43.18  4705.0   30.78  4728.9   31.05  4775.0   27.80  4795.1   23.38
  4989.8    8.59  4997.1    4.35  4999.9    3.85  5003.1    4.35  5023.7    5.03
  5031.1    9.16  5064.0   10.79  5093.2    9.80  5104.4   10.32  5113.8   13.05
  5155.2   14.78  5237.9   14.32  5301.1   16.74  5362.4   14.50  5481.1   16.81
  5487.9   18.27  5502.1   18.30  5508.9   22.56  5516.3   22.69  5523.1   25.88
  5530.5   25.91  5537.3   28.21  5608.1   32.25  5615.5   34.93  5620.2   33.96
#Mann=4,-1,0
  4589.6    0.08       0  4728.9    0.05       0  4997.1    0.04       0
  5003.1    0.05       0
Bank Sta=4997.1,5003.1
Exp/Cntr=0.3,0.1

Type RM Length L Ch R = 1,329,0,0,0
BEGIN DESCRIPTION:
UNT006 IN BACR 1.0
END DESCRIPTION:
XS GIS Cut Line= 4
      2398726.71     13141334.77      2398998.10     13141443.71
      2399431.89     13141395.94      2399789.21     13141086.39
#Sta/Elev= 30
  4427.3   32.57  4482.3   28.90  4523.4   29.35  4582.6   23.91  4594.3   24.22
  4606.8   24.96  4636.4   22.65  4708.6   23.22  4714.3   20.11  4769.7   19.00
  4820.0   12.19  4880.3    8.95  4910.5    4.15  4917.5    4.32  4930.6    8.51
  4950.7    9.33  4980.9    8.07  4991.0    4.25  4998.0    4.04  5000.8    3.54
  5004.0    4.04  5008.4    7.53  5031.2    9.77  5131.8    8.62  5156.2    6.16
  5209.2   10.65  5242.4   10.99  5328.3   13.27  5421.9   13.43  5628.9   28.57
#Mann=7,-1,0
  4427.3    0.05       0  4582.6     0.1       0  4594.3    0.05       0
  4998.0    0.04       0  5004.0    0.05       0  5242.4    0.08       0
  5328.3    0.05       0
Bank Sta=4998,5004
Exp/Cntr=0.3,0.1

Chan Stop Cuts=-1