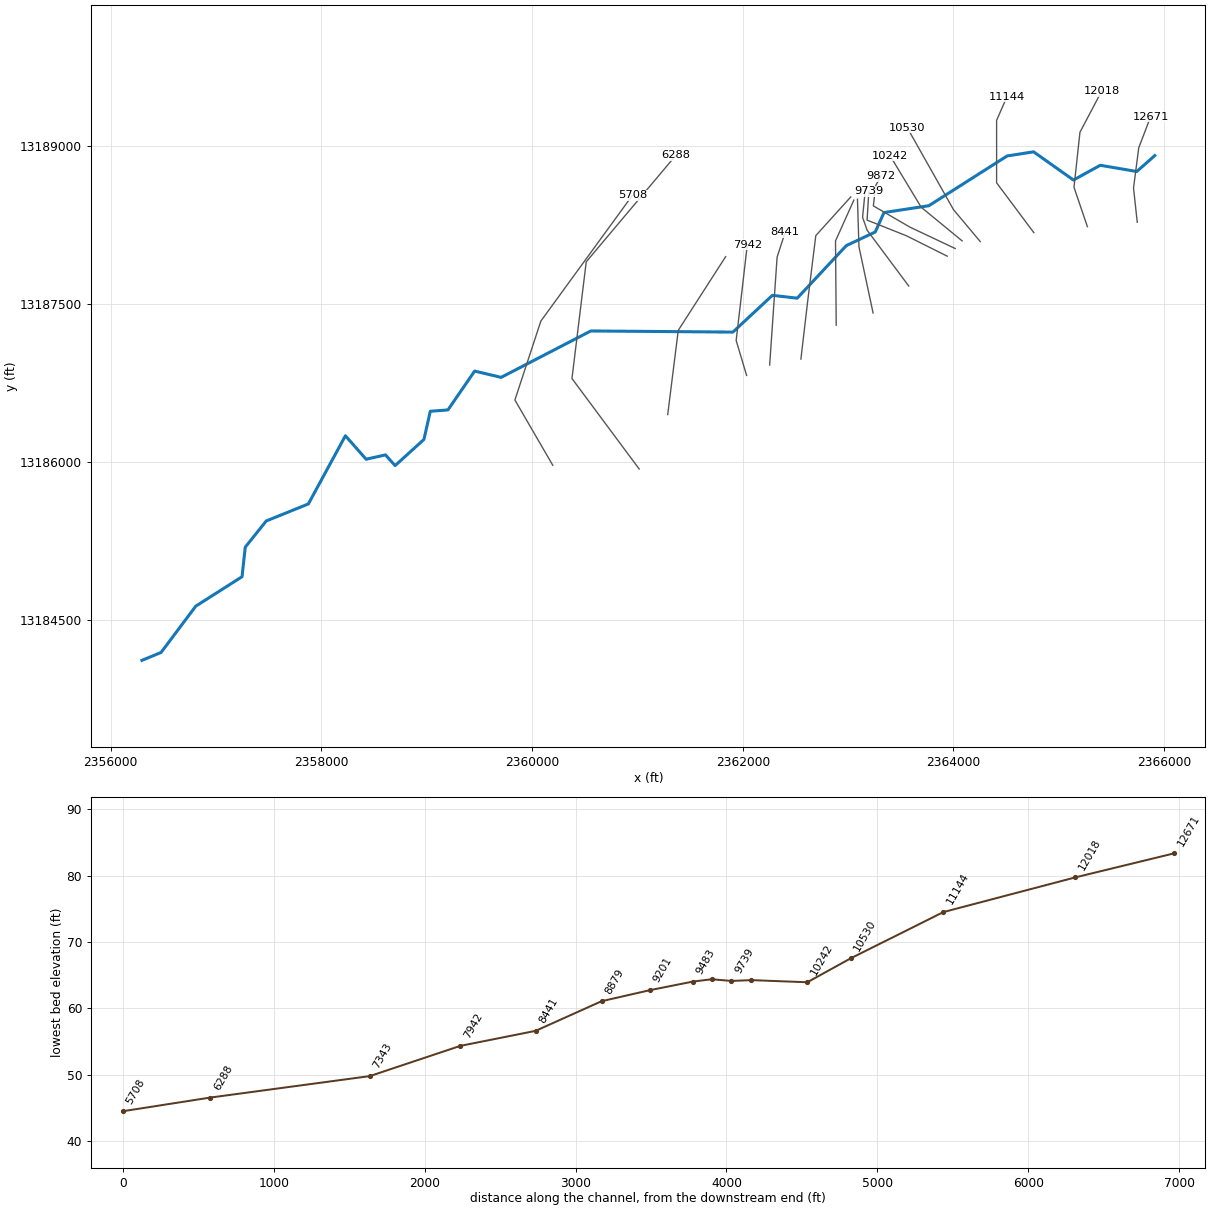
--- UNT007 IN BACR.prj (project) ---

Proj Title=UNT007 IN BACR Base Level Engineering
Current Plan=p01
Default Exp/Contr=0.3,0.1
English Units
Geom File=g01
Flow File=f01
Plan File=p01
Y Axis Title=Elevation
X Axis Title(PF)=Main Channel Distance
X Axis Title(XS)=Station
BEGIN DESCRIPTION:
UNT007 IN BACR
END DESCRIPTION:
DSS Export Rating Curves= 0
DSS Export Rating Curve Sorted= 0
DSS Export Volume Flow Curves= 0
DXF OffsetX= 0
DXF OffsetY= 0
DXF ScaleX= 1
DXF ScaleY= 10

--- UNT007 IN BACR.p01 (plan) ---

Plan Title=Multiple Run
Short Identifier=Multiple
Geom File=g01
Flow File=f01
Subcritical Flow
K Sum by GR= 0
Std Step Tol= 0.01
Critical Tol= 0.01
Num of Std Step Trials= 20
Max Error Tol= 0.3
Flow Tol Ratio= 0.001
Split Flow NTrial= 30
Split Flow Tol= 0.02
Split Flow Ratio= 0.02
Log Output Level= 0
Friction Slope Method= 1
Unsteady Friction Slope Method= 2
Unsteady Bridges Friction Slope Method= 1
Parabolic Critical Depth
Global Vel Dist=  1 , 1 , 1
Global Log Level= 0
CheckData=True
Encroach Param= -1, 0, 0, 0
BEGIN DESCRIPTION:
Multiple Run
END DESCRIPTION:

--- UNT007 IN BACR.f01 (steady flow) ---

Flow Title=Multiple
Program Version=4.10
Number of Profiles= 7
Profile Names=10-year,25-year,50-year,1pct_min,100-year,1pct_plu,500-year
River Rch & RM=UNT007 IN BACR,Reach-1         ,12671
     382     510     612     535     724     979    1016
River Rch & RM=UNT007 IN BACR,Reach-1         ,12018
     584     806     986     880    1190    1609    1739
Boundary for River Rch & Prof#=UNT007 IN BACR,Reach-1         , 1
Up Type= 0
Dn Type= 3
Dn Slope=0.005
Boundary for River Rch & Prof#=UNT007 IN BACR,Reach-1         , 2
Up Type= 0
Dn Type= 3
Dn Slope=0.005
Boundary for River Rch & Prof#=UNT007 IN BACR,Reach-1         , 3
Up Type= 0
Dn Type= 3
Dn Slope=0.005
Boundary for River Rch & Prof#=UNT007 IN BACR,Reach-1         , 4
Up Type= 0
Dn Type= 3
Dn Slope=0.005
Boundary for River Rch & Prof#=UNT007 IN BACR,Reach-1         , 5
Up Type= 0
Dn Type= 3
Dn Slope=0.005
Boundary for River Rch & Prof#=UNT007 IN BACR,Reach-1         , 6
Up Type= 0
Dn Type= 3
Dn Slope=0.005
Boundary for River Rch & Prof#=UNT007 IN BACR,Reach-1         , 7
Up Type= 0
Dn Type= 3
Dn Slope=0.005
DSS Import GetInterval= 0
DSS Import GetPeak= 0
DSS Import FillOption= 0

--- UNT007 IN BACR.g01 (geometry) ---

Geom Title=Existing Conditions
Program Version=4.10

River Reach=UNT007 IN BACR  ,Reach-1
Reach XY= 30
      2365910.91     13188906.53      2365739.84     13188755.69
      2365393.12     13188814.57      2365139.08     13188674.52
      2364760.59     13188942.52      2364509.19     13188903.23
      2363766.38     13188430.49      2363340.93     13188365.73
       2363257.6     13188181.01      2362982.82     13188051.47
      2362516.98      13187552.3      2362281.28     13187579.27
      2361906.34     13187230.17      2360557.66       13187241.
      2359706.36     13186800.05      2359454.93     13186859.98
      2359201.56     13186490.87      2359034.13     13186478.32
      2358973.66      13186210.4      2358700.15     13185962.13
      2358608.51     13186064.03      2358424.94     13186022.37
      2358228.26     13186245.68      2357876.67     13185597.81
      2357476.73     13185436.08      2357277.67     13185187.28
      2357247.02     13184906.51      2356807.72     13184626.86
      2356478.32     13184186.78      2356296.87     13184112.17

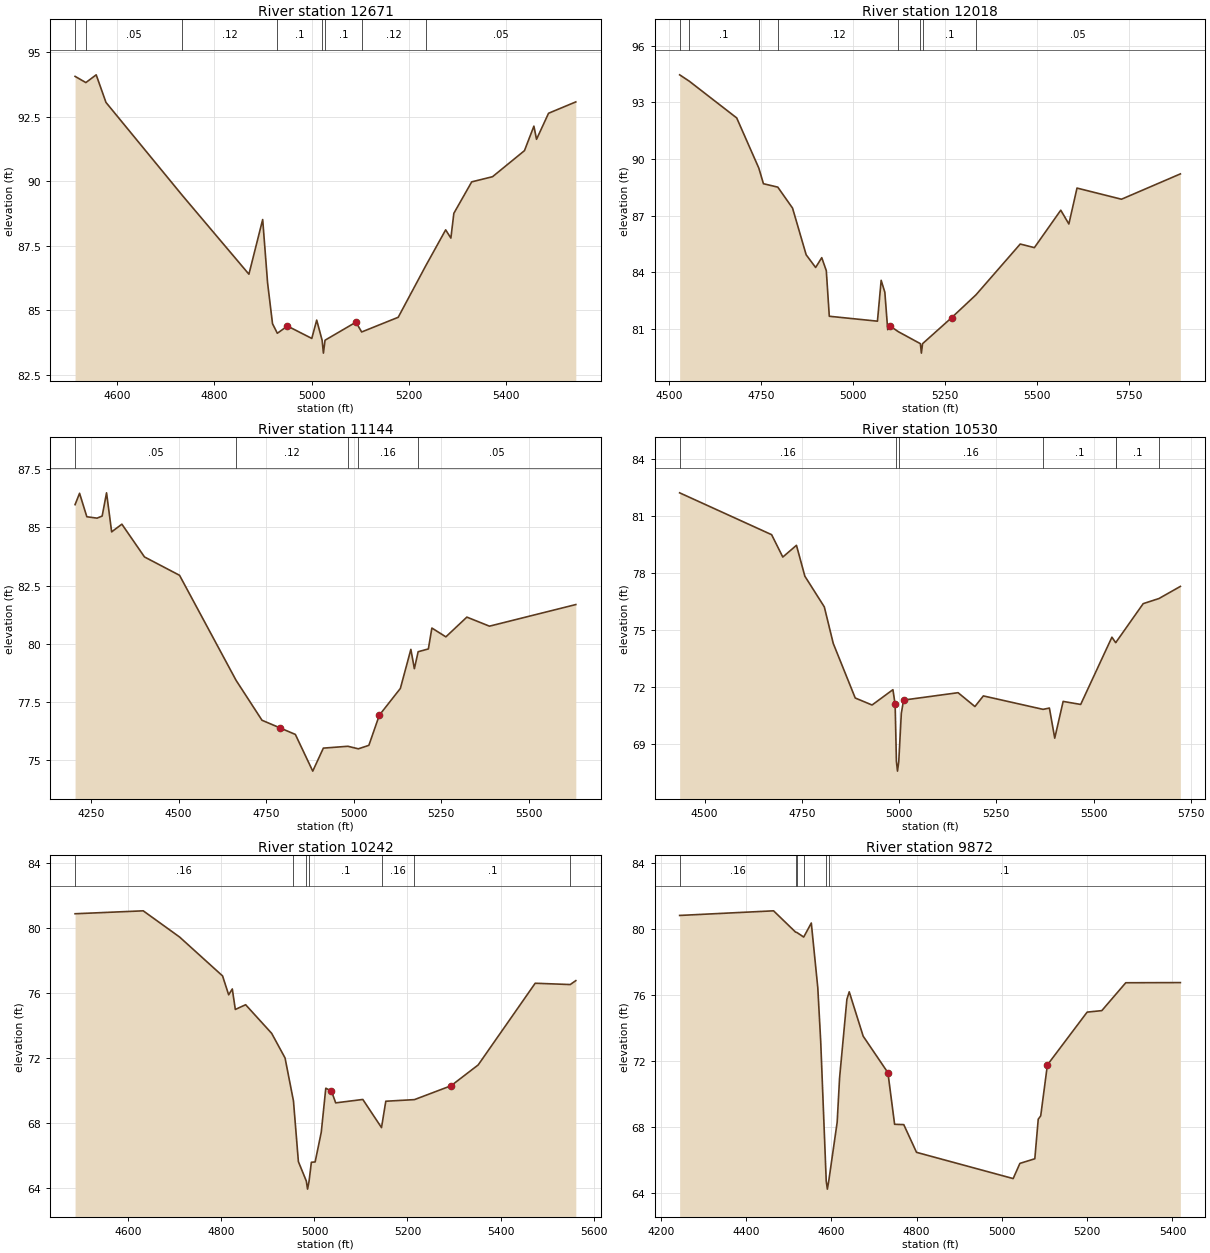
Type RM Length L Ch R = 1 ,12671   ,653,653,653
BEGIN DESCRIPTION:
UNT007 IN BACR 16.0
END DESCRIPTION:
XS GIS Cut Line= 4
      2365744.55     13188273.71      2365709.23     13188598.65
      2365758.67     13188980.06      2365871.68     13189276.71
#Sta/Elev= 30
    4514   94.07  4536.2   93.83  4557.4   94.13  4577.5   93.06  4734.6   89.45
  4871.2    86.4  4899.5   88.52  4909.6   86.06  4919.7   84.48  4929.6   84.11
  4950.4   84.39  5000.4   83.91  5010.5   84.62  5021.6   83.84  5024.3   83.34
  5027.6   83.84  5091.1   84.54  5102.9   84.16    5178   84.73  5234.1   86.71
  5275.5   88.12  5286.2    87.8  5292.3   88.76    5329   89.98  5371.8   90.18
  5437.4   91.19  5456.8   92.14  5462.2   91.63  5486.9   92.64  5542.9   93.08
#Mann= 8 ,-1 , 0
    4514      .1       0  4536.2     .05       0  4734.6     .12       0
  4929.6      .1       0  5021.6     .07       0  5027.6      .1       0
  5102.9     .12       0  5234.1     .05       0
Bank Sta=4950.4,5091.1
XS Rating Curve= 0 ,0
Exp/Cntr=0.3,0.1

Type RM Length L Ch R = 1 ,12018   ,874,874,874
BEGIN DESCRIPTION:
Mapping XS ce3aba77
END DESCRIPTION:
XS GIS Cut Line= 4
      2365271.31     13188231.38      2365144.17     13188605.71
      2365200.68     13189128.39       2365405.5     13189516.84
#Sta/Elev= 30
  4529.4   94.45  4555.1   94.12  4684.4   92.17  4744.6   89.51    4757   88.69
    4796   88.51  4836.1    87.4  4873.1   84.93  4898.8   84.26  4915.4   84.78
  4927.8   84.09  4935.9   81.68  5066.7   81.42  5076.8   83.58  5086.8   82.95
  5094.6   80.97  5099.6   81.18  5123.8   80.86  5183.3   80.23  5186.1   79.73
  5189.3   80.23  5267.9    81.6  5334.2   82.81  5454.6    85.5    5493   85.31
  5564.7   87.29  5586.7   86.56  5608.8   88.46  5729.6   87.87  5889.6   89.21
#Mann= 8 ,-1 , 0
  4529.4     .05       0  4555.1      .1       0  4744.6     .05       0
    4796     .12       0  5123.8      .1       0  5183.3     .07       0
  5189.3      .1       0  5334.2     .05       0
Bank Sta=5099.6,5267.9
XS Rating Curve= 0 ,0
Exp/Cntr=0.3,0.1

Type RM Length L Ch R = 1 ,11144   ,614,614,614
BEGIN DESCRIPTION:
UNT007 IN BACR 15.0
END DESCRIPTION:
XS GIS Cut Line= 4
      2364762.76     13188174.85       2364409.6     13188648.09
       2364409.6      13189241.4      2364508.48     13189467.42
#Sta/Elev= 30
  4204.5   85.98  4217.3   86.47  4238.1   85.46  4267.3    85.4  4281.9   85.49
  4294.4   86.49    4309   84.81  4338.2   85.14  4402.8   83.73  4502.9   82.94
  4664.4   78.42  4738.5    76.7  4788.5   76.38  4833.8   76.09  4883.5   74.51
  4913.8    75.5  4983.8   75.58  5013.8   75.47  5043.8   75.62  5073.8   76.92
  5133.8   78.07  5163.8   79.75  5173.8   78.92  5184.6   79.65  5213.8   79.77
  5223.8   80.67  5263.8   80.29  5323.8   81.14  5388.3   80.75    5635   81.68
#Mann= 5 ,-1 , 0
  4204.5     .05       0  4664.4     .12       0  4983.8     .07       0
  5013.8     .16       0  5184.6     .05       0
Bank Sta=4788.5,5073.8
XS Rating Curve= 0 ,0
Exp/Cntr=0.3,0.1

Type RM Length L Ch R = 1 ,10530   ,288,288,288
BEGIN DESCRIPTION:
UNT007 IN BACR 14.0
END DESCRIPTION:
XS GIS Cut Line= 3
      2364254.23     13188090.07      2363999.94     13188393.81
      2363562.36     13189170.15
#Sta/Elev= 30
    4436   82.24  4672.5   80.03  4701.2   78.85  4736.3   79.47  4757.9   77.84
  4807.9   76.22  4830.9   74.29  4887.4   71.41  4930.7   71.04  4984.3   71.85
    4990   71.07  4993.3   68.05  4996.1   67.55  4999.3   68.05  5005.9    70.6
  5011.7    71.3  5151.8   71.69  5195.1   70.96  5216.8   71.52  5370.3   70.81
  5386.6   70.88  5400.3   69.29  5421.9   71.23    5467   71.07  5547.3   74.62
  5556.7   74.34    5557   74.33  5627.7   76.39  5668.2   76.66  5723.3    77.3
#Mann= 7 ,-1 , 0
    4436     .16       0  4993.3     .07       0  4999.3     .16       0
  5370.3      .1       0  5556.7     .05       0    5557      .1       0
  5668.2     .05       0
Bank Sta=4990,5011.7
XS Rating Curve= 0 ,0
Exp/Cntr=0.3,0.1

Type RM Length L Ch R = 1 ,10242   ,370,370,370
BEGIN DESCRIPTION:
Mapping XS ea1359d4
END DESCRIPTION:
XS GIS Cut Line= 3
      2364082.71     13188096.27      2363694.04     13188415.77
      2363397.59     13188906.55
#Sta/Elev= 30
  4485.4   80.86  4631.9   81.04  4710.1   79.43  4802.5   77.04  4815.6   75.88
  4823.4   76.24  4829.9   74.98  4852.1   75.27  4908.1   73.51  4936.8      72
  4954.9   69.36  4965.5   65.63  4982.5   64.44  4985.2   63.94  4988.5   64.44
  4993.4   65.59  5001.5   65.61  5014.7   67.44  5024.4   70.14  5036.5   69.97
  5045.7   69.24    5104   69.45  5144.2   67.72  5153.4   69.34    5215   69.44
  5293.6   70.29    5352   71.57  5474.6   76.59  5549.9   76.51  5561.9   76.75
#Mann= 7 ,-1 , 0
  4485.4     .16       0  4954.9      .1       0  4982.5     .07       0
  4988.5      .1       0  5144.2     .16       0    5215      .1       0
  5549.9     .05       0
#XS Ineff= 2 , 0
         5023.86   69.96
Permanent Ineff=
       F       F
Bank Sta=5036.5,5293.6
XS Rating Curve= 0 ,0
Exp/Cntr=0.3,0.1

Type RM Length L Ch R = 1 ,9872    ,133,133,133
BEGIN DESCRIPTION:
UNT007 IN BACR 13.0
END DESCRIPTION:
XS GIS Cut Line= 5
      2364016.81     13188023.83      2363585.35     13188228.03
      2363239.51     13188428.94      2363262.57     13188623.27
      2363311.86       13188712.
#Sta/Elev= 30
  4244.1   80.85  4464.4   81.13    4516   79.84  4518.9   79.82  4535.1   79.54
  4552.9   80.39  4568.1   76.48    4575    73.2  4587.9   64.76  4590.6   64.26
  4593.9   64.76  4613.6   68.32  4619.2   70.99  4636.4   75.77  4641.9   76.22
  4674.6   73.53  4732.6   71.32  4748.3   68.19  4769.8   68.17  4799.7   66.49
  5026.4    64.9  5042.2   65.82  5077.2    66.1  5085.2    68.5    5091    68.7
  5106.7   71.79  5199.9   74.99  5234.3   75.08  5290.5   76.77  5418.6   76.78
#Mann= 6 ,-1 , 0
  4244.1     .16       0    4516      .1       0  4518.9     .16       0
  4535.1      .1       0  4587.9     .07       0  4593.9      .1       0
#XS Ineff= 2 , 0
         4641.48   75.85
Permanent Ineff=
       F       F
Bank Sta=4732.6,5106.7
XS Rating Curve= 0 ,0
Exp/Cntr=0.3,0.1

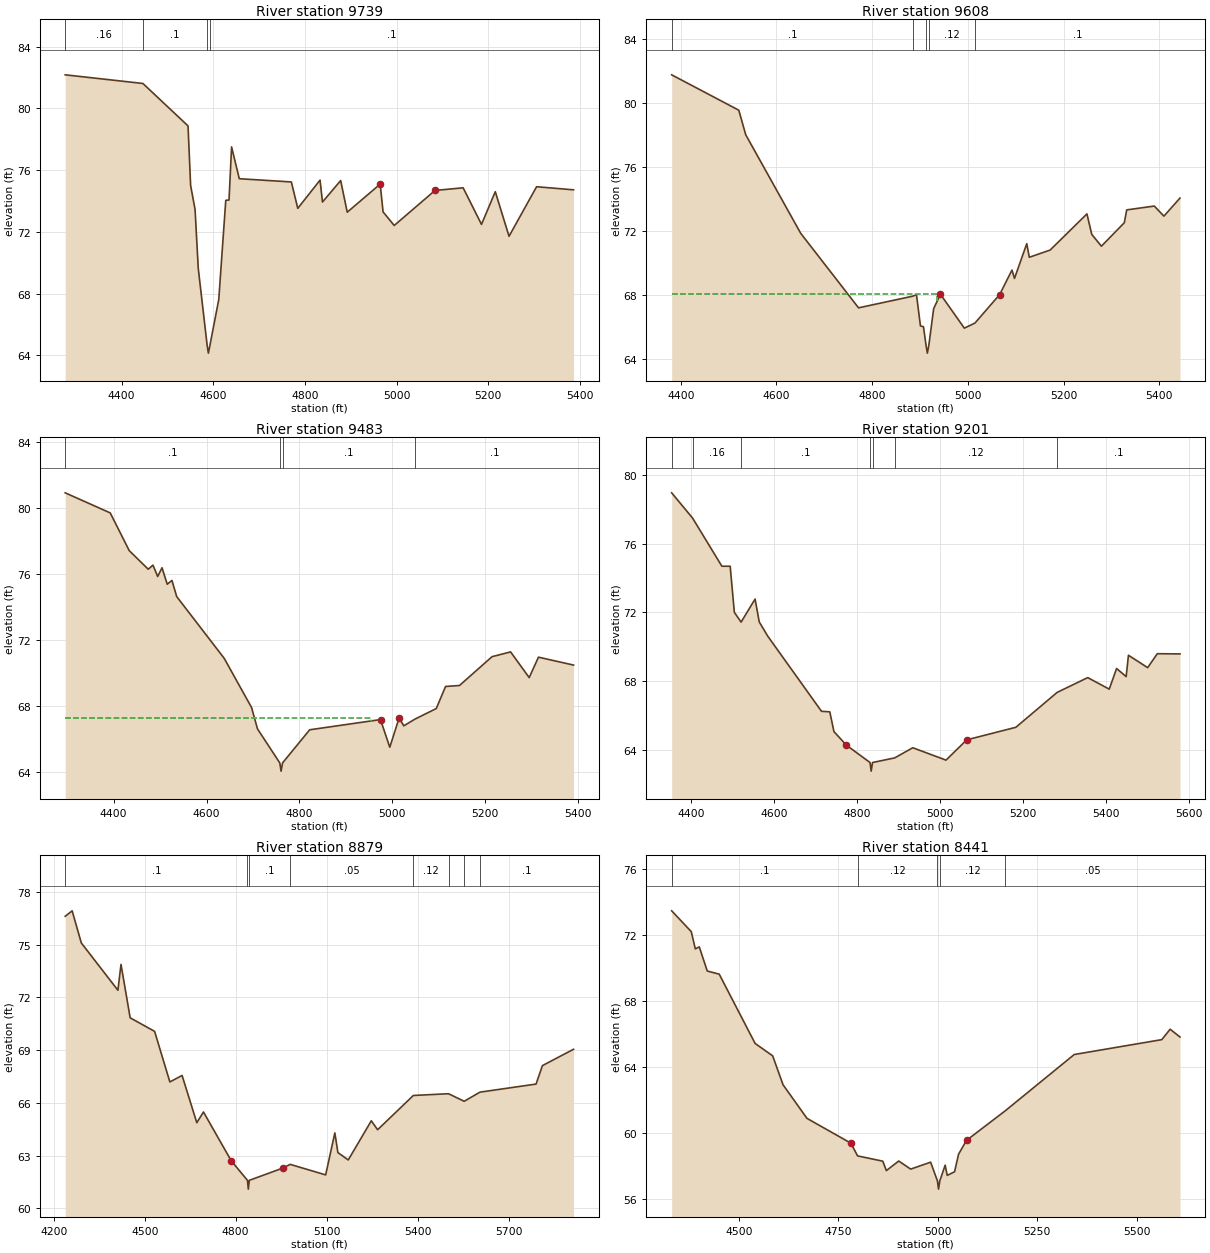
Type RM Length L Ch R = 1 ,9739    ,131,131,131
BEGIN DESCRIPTION:
UNT007 IN BACR 12.0
END DESCRIPTION:
XS GIS Cut Line= 4
      2363941.07     13187951.36      2363552.41     13188145.69
      2363180.23      13188293.9      2363196.69     13188567.26
#Sta/Elev= 30
  4276.9   82.17  4446.4   81.61  4544.9   78.86  4550.5   75.01  4560.2   73.45
  4567.2   69.63  4586.6   64.64  4589.3   64.14  4592.6   64.64  4611.9   67.61
  4627.2   74.04  4634.3   74.06  4639.9    77.5  4656.7   75.44  4770.3   75.23
  4784.3   73.52  4832.9   75.35  4838.2   73.93  4877.9   75.32  4892.2   73.27
  4964.1   75.09  4970.4   73.29  4994.7   72.41  5083.7   74.68  5145.1   74.85
  5185.1   72.48  5215.2    74.6  5245.2   71.71  5305.3   74.92  5385.9   74.72
#Mann= 4 ,-1 , 0
  4276.9     .16       0  4446.4      .1       0  4586.6     .07       0
  4592.6      .1       0
#XS Ineff= 2 , 0
         4639.77   76.68
Permanent Ineff=
       F       F
Bank Sta=4964.1,5083.7
XS Rating Curve= 0 ,0
Exp/Cntr=0.3,0.1

Type RM Length L Ch R = 1 ,9608    ,125,125,125
BEGIN DESCRIPTION:
Mapping XS a64b5b80
END DESCRIPTION:
XS GIS Cut Line= 4
      2363575.49     13187668.07      2363180.23     13188198.39
      2363137.41     13188320.25      2363163.75     13188590.29
#Sta/Elev= 30
  4381.1   81.78  4521.3   79.57  4535.9   78.03  4650.6   71.88  4771.5   67.22
    4885   67.95  4892.5   68.05  4900.8   66.09  4907.1   66.04  4912.4   64.89
  4915.2   64.39  4918.4   64.89  4928.4   67.17  4942.5   68.07  4992.5   65.95
  5014.7   66.27  5066.3   68.05    5092   69.58  5097.3   69.06  5122.9   71.23
  5128.2   70.38  5171.7   70.83  5248.6   73.09  5258.7   71.81  5278.8   71.07
  5326.7   72.54  5331.7   73.34  5389.3   73.58  5409.4   72.95    5443   74.08
#Mann= 5 ,-1 , 0
  4381.1      .1       0    4885     .12       0  4912.4     .07       0
  4918.4     .12       0  5014.7      .1       0
#XS Ineff= 2 , 0
          4935.8    68.1
Permanent Ineff=
       F       F
Bank Sta=4942.5,5066.3
XS Rating Curve= 0 ,0
Exp/Cntr=0.3,0.1

Type RM Length L Ch R = 1 ,9483    ,282,282,282
BEGIN DESCRIPTION:
Mapping XS 5f83127a
END DESCRIPTION:
XS GIS Cut Line= 3
      2363237.11       13187412.      2363102.91     13188040.65
      2363088.79     13188492.32
#Sta/Elev= 30
  4295.7   80.94  4392.7   79.72  4433.6   77.43  4474.5    76.3  4484.7   76.55
  4494.9   75.86  4504.2   76.39  4515.4   75.39  4525.6   75.62  4535.8   74.64
  4638.1   70.89  4697.1    67.9  4709.7   66.61  4757.8   64.54  4760.6   64.04
  4763.8   64.54  4822.2   66.55  4974.7   67.17  4994.7   65.49  5014.8   67.27
  5024.8   66.79    5049    67.2  5094.8   67.84  5114.8   69.18  5144.8   69.24
  5214.9   70.99  5254.9   71.28  5294.9   69.72  5314.9   70.96  5390.4   70.48
#Mann= 4 ,-1 , 0
  4295.7      .1       0  4757.8     .07       0  4763.8      .1       0
    5049      .1       0
#XS Ineff= 2 , 0
         4954.09   67.27
Permanent Ineff=
       F       F
Bank Sta=4974.7,5014.8
XS Rating Curve= 0 ,0
Exp/Cntr=0.3,0.1

Type RM Length L Ch R = 1 ,9201    ,322,322,322
BEGIN DESCRIPTION:
Mapping XS fda8176e
END DESCRIPTION:
XS GIS Cut Line= 3
      2362887.09      13187295.9       2362880.5     13188096.29
      2363054.38     13188483.42
#Sta/Elev= 30
    4354   78.95  4404.4   77.48    4475   74.68    4495   74.68    4505      72
  4521.3   71.43    4555   72.77    4565   71.44    4585   70.63    4715   66.24
    4735   66.21    4745   65.06    4775   64.27    4832   63.26  4834.7   62.76
    4838   63.26  4891.4   63.53    4935   64.12    5015    63.4    5065   64.58
  5183.3   65.31  5282.8   67.34  5356.5    68.2  5408.3   67.53    5426   68.73
  5449.1   68.26  5454.6    69.5  5500.9   68.78  5524.1   69.59  5578.8   69.58
#Mann= 7 ,-1 , 0
    4354      .1       0  4404.4     .16       0  4521.3      .1       0
    4832     .07       0    4838      .1       0  4891.4     .12       0
  5282.8      .1       0
Bank Sta=4775,5065
XS Rating Curve= 0 ,0
Exp/Cntr=0.3,0.1

Type RM Length L Ch R = 1 ,8879    ,438,438,438
BEGIN DESCRIPTION:
UNT007 IN BACR 11.0
END DESCRIPTION:
XS GIS Cut Line= 4
      2362551.97     13186974.06      2362615.55     13187517.98
      2362693.24      13188146.6      2363025.21     13188513.88
#Sta/Elev= 30
  4237.9   76.62  4260.8   76.93  4291.1    75.1  4411.7   72.41  4421.9   73.88
  4452.1   70.84  4532.7   70.07    4583   67.19  4623.3   67.56  4671.8   64.87
  4693.8   65.48  4785.5    62.7  4838.9   61.59  4841.7   61.09  4844.9   61.59
  4955.7   62.29  4979.7    62.5  5096.7    61.9    5127   64.29  5137.1   63.17
  5171.2   62.75  5247.2   64.98    5268   64.47  5385.8   66.42  5501.8   66.52
  5553.5   66.09  5605.5   66.61  5790.5   67.07  5811.4   68.12    5914   69.05
#Mann= 8 ,-1 , 0
  4237.9      .1       0  4838.9     .04       0  4844.9      .1       0
  4979.7     .05       0  5385.8     .12       0  5501.8      .1       0
  5553.5     .12       0  5605.5      .1       0
Bank Sta=4785.5,4955.7
XS Rating Curve= 0 ,0
Exp/Cntr=0.3,0.1

Type RM Length L Ch R = 1 ,8441    ,499,499,499
BEGIN DESCRIPTION:
UNT007 IN BACR 10.0
END DESCRIPTION:
XS GIS Cut Line= 3
      2362255.33     13186917.64      2362325.96     13187941.77
      2362403.17     13188180.43
#Sta/Elev= 30
  4331.5   73.45  4380.8   72.19  4390.9   71.15  4400.9   71.27  4420.9   69.81
    4451   69.62  4541.2   65.43  4585.3   64.68  4611.4   62.93  4671.5    60.9
  4781.8    59.4  4798.7   58.63    4862   58.31    4871   57.74  4902.1   58.32
  4932.1   57.83  4982.3   58.25  4999.3   57.12  5002.1   56.62  5005.3   57.12
  5018.8   58.07  5023.9   57.45  5042.4   57.67  5052.4   58.73  5072.5   59.57
  5169.4   61.35  5343.1   64.76  5563.1   65.66  5584.1   66.29  5608.9   65.82
#Mann= 5 ,-1 , 0
  4331.5      .1       0  4798.7     .12       0  4999.3     .07       0
  5005.3     .12       0  5169.4     .05       0
Bank Sta=4781.8,5072.5
XS Rating Curve= 0 ,0
Exp/Cntr=0.3,0.1

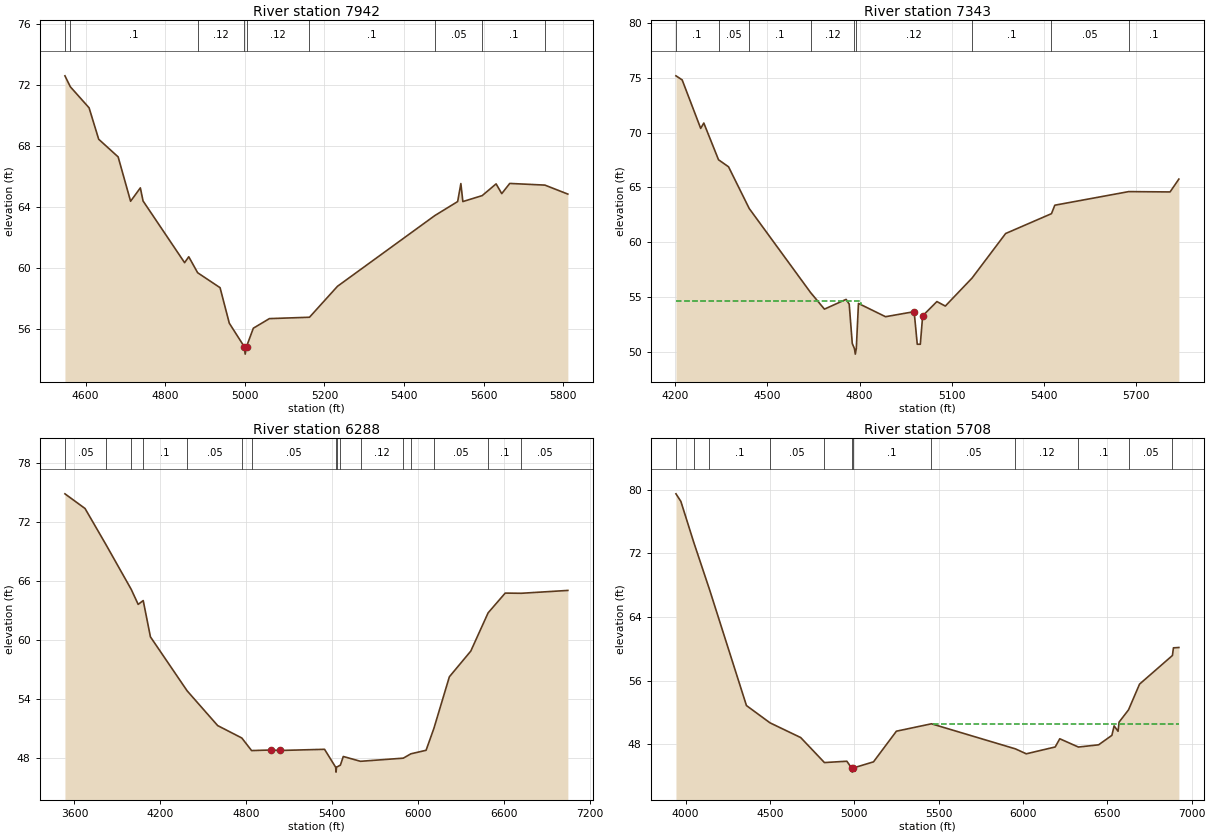
Type RM Length L Ch R = 1 ,7942    ,599,599,599
BEGIN DESCRIPTION:
Mapping XS dfc562bf
END DESCRIPTION:
XS GIS Cut Line= 3
      2362036.37     13186818.71      2361937.48     13187150.69
      2362043.43     13188061.86
#Sta/Elev= 30
  4547.9   72.62  4561.5    71.9  4608.6   70.52  4632.7   68.46  4681.6    67.3
  4712.9   64.39  4737.4   65.27  4744.2   64.41  4848.6   60.36    4859   60.75
  4881.4    59.7  4937.7   58.72  4960.9   56.39  4998.2   54.86  5000.9   54.36
  5004.2   54.86  5021.3   56.06  5061.6   56.69  5162.4   56.78  5232.7   58.81
  5477.3   63.45  5534.7   64.37  5542.8   65.55  5547.8   64.37  5596.3   64.76
  5631.3   65.53  5645.5   64.89  5665.6   65.56  5753.9   65.45  5811.6   64.86
#Mann= 9 ,-1 , 0
  4547.9     .05       0  4561.5      .1       0  4881.4     .12       0
  4998.2     .07       0  5004.2     .12       0  5162.4      .1       0
  5477.3     .05       0  5596.3      .1       0  5753.9     .05       0
Bank Sta=4998.2,5004.2
XS Rating Curve= 0 ,0
Exp/Cntr=0.3,0.1

Type RM Length L Ch R = 1 ,7343    ,1057,1057,1057
BEGIN DESCRIPTION:
UNT007 IN BACR 9.0
END DESCRIPTION:
XS GIS Cut Line= 3
      2361287.72     13186446.86      2361387.72     13187246.85
      2361837.73     13187946.87
#Sta/Elev= 30
  4201.8   75.17    4222    74.8  4282.4   70.38  4292.5   70.87  4340.5   67.52
  4373.1   66.88  4440.5   63.08  4640.4   55.42  4685.5   53.91  4756.1    54.8
  4766.2   54.37  4776.2   50.78  4783.3   50.31  4786.1   49.81  4789.3   50.31
  4796.4   54.43  4884.6   53.22  4977.8   53.68  4987.9   50.71  4997.9   50.71
  5005.5    53.3  5051.9    54.6  5079.3   54.19  5166.4   56.74  5275.8    60.8
  5425.2   62.61    5436   63.38  5676.8   64.62  5811.5   64.59  5840.2   65.76
#Mann= 9 ,-1 , 0
  4201.8      .1       0  4340.5     .05       0  4440.5      .1       0
  4640.4     .12       0  4783.3     .07       0  4789.3     .12       0
  5166.4      .1       0  5425.2     .05       0  5676.8      .1       0
#XS Ineff= 2 , 0
       0 4804.58   54.61               0
Permanent Ineff=
       T       F
Bank Sta=4977.8,5005.5
XS Rating Curve= 0 ,0
Exp/Cntr=0.3,0.1

Type RM Length L Ch R = 1 ,6288    ,580,580,580
BEGIN DESCRIPTION:
Mapping XS 66bc5416
END DESCRIPTION:
XS GIS Cut Line= 4
      2361016.82     13185929.72      2360378.77     13186789.13
       2360514.2     13187897.61      2361367.81     13188912.58
#Sta/Elev= 30
  3533.3   74.87  3673.7   73.38  3818.7   69.74  3996.7   65.15    4045   63.63
  4080.2   64.02  4130.6   60.33  4387.2   54.84  4600.4   51.31    4769   50.05
  4837.3   48.77  4974.1   48.83  5034.6   48.78  5346.9    48.9  5424.5   47.08
  5427.2   46.58  5430.5   47.08  5457.6   47.29  5477.8   48.17  5598.1   47.68
  5897.1      48  5949.7   48.44  6056.2    48.8  6110.9   51.03  6218.9   56.27
  6368.4   58.88  6489.5   62.77  6609.1   64.78  6721.3   64.76  7046.6   65.05
#Mann= 16 ,-1 , 0
  3533.3     .05       0  3818.7      .1       0  3996.7     .05       0
  4080.2      .1       0  4387.2     .05       0    4769      .1       0
  4837.3     .05       0  5424.5     .03       0  5430.5     .05       0
  5457.6     .05       0  5598.1     .12       0  5897.1     .05       0
  5949.7      .1       0  6110.9     .05       0  6489.5      .1       0
  6721.3     .05       0
Bank Sta=4974.1,5034.6
XS Rating Curve= 0 ,0
Exp/Cntr=0.3,0.1

Type RM Length L Ch R = 1 ,5708    ,0,0,0
BEGIN DESCRIPTION:
UNT007 IN BACR 1.0
END DESCRIPTION:
XS GIS Cut Line= 4
       2360196.5     13185965.31      2359837.11     13186585.11
      2360083.53     13187334.81      2360951.71     13188527.84
#Sta/Elev= 30
  3943.3   79.47  3972.4   78.52  4048.5    73.4  4141.5    67.5  4361.2   52.88
  4500.8   50.71  4682.8   48.86  4823.5   45.72  4956.3   45.89  4984.9   45.02
  4987.7   44.52  4990.9   45.02  5114.2   45.81    5250   49.66  5457.9   50.59
  5955.7   47.44  6019.8   46.82  6191.3   47.68  6218.4   48.71  6328.9   47.67
  6448.6   47.95  6527.4   49.14  6540.6   50.33  6563.8   49.65    6570    50.8
  6625.9   52.34  6691.3   55.57  6886.3   59.17  6892.2   60.13  6924.4   60.17
#Mann= 12 ,-1 , 0
  3943.3      .1       0  4048.5     .05       0  4141.5      .1       0
  4500.8     .05       0  4823.5      .1       0  4984.9     .07       0
  4990.9      .1       0  5457.9     .05       0  5955.7     .12       0
  6328.9      .1       0  6625.9     .05       0  6886.3      .1       0
#XS Ineff= 2 , 0
                         5464.77           50.56
Permanent Ineff=
       F       F
Bank Sta=4984.9,4990.9
XS Rating Curve= 0 ,0
Exp/Cntr=0.3,0.1

Chan Stop Cuts=-1
Use User Specified Reach Order=0
Composite Channel Slope=5