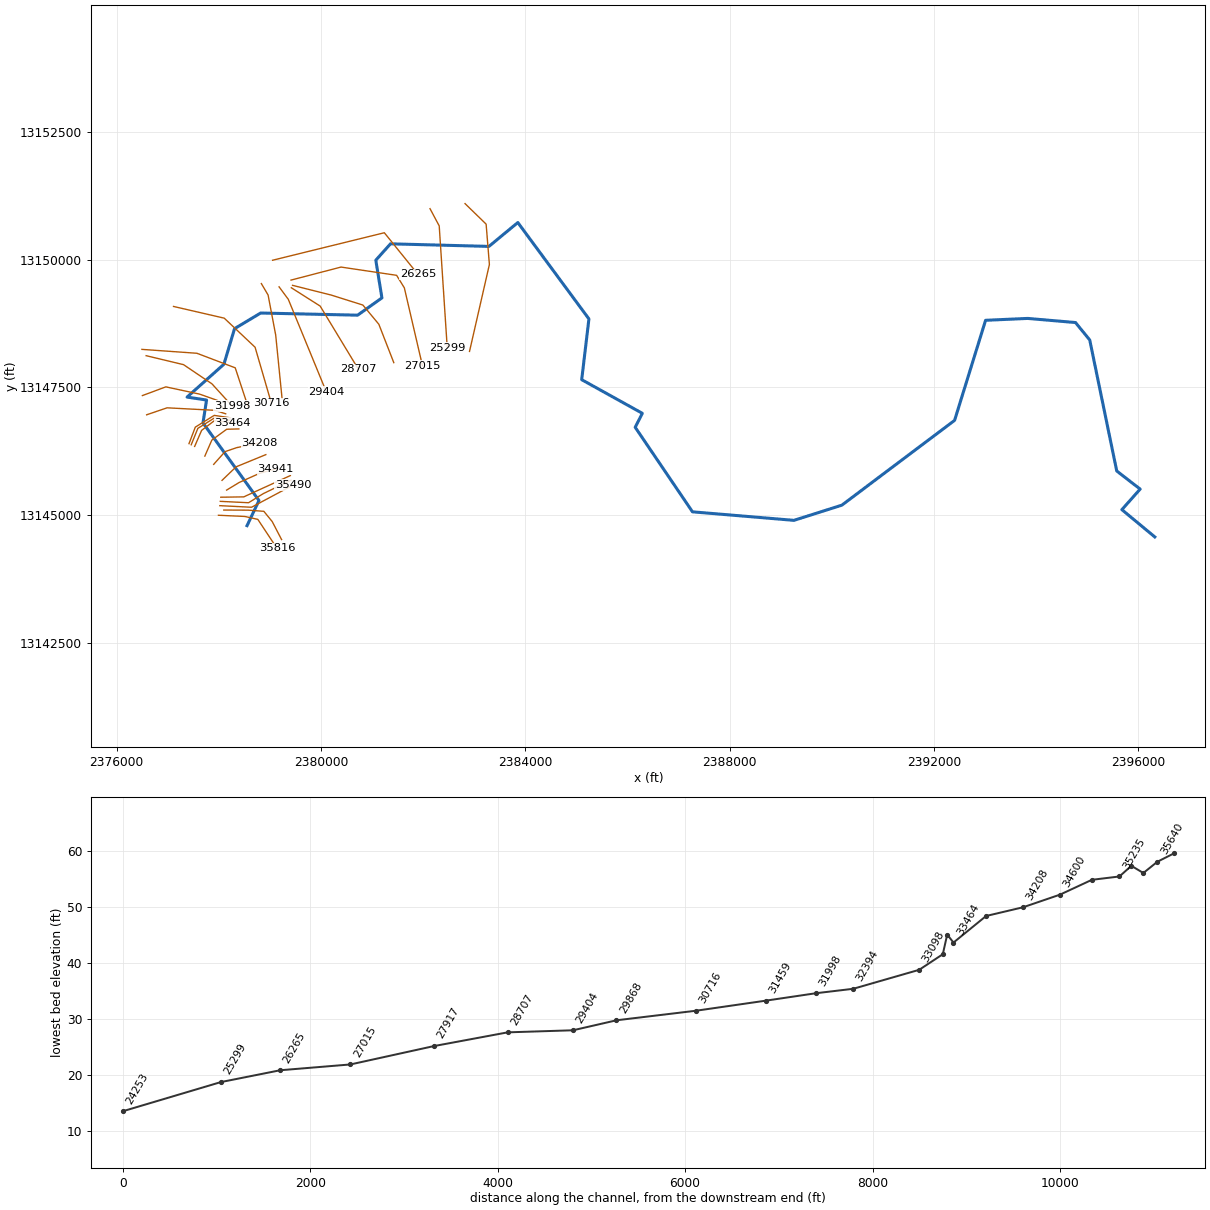
--- UNT008 IN BACR.prj (project) ---

Proj Title=UNT008 IN BACR Base Level Engineering
Current Plan=p01
Default Exp/Contr=0.3,0.1
English Units
Geom File=g01
Flow File=f01
Plan File=p01
Y Axis Title=Elevation
X Axis Title(PF)=Main Channel Distance
X Axis Title(XS)=Station
BEGIN DESCRIPTION:
UNT008 IN BACR
END DESCRIPTION:
DSS Export Rating Curves= 0
DSS Export Rating Curve Sorted= 0
DSS Export Volume Flow Curves= 0
DXF OffsetX= 0
DXF OffsetY= 0
DXF ScaleX= 1
DXF ScaleY= 10

--- UNT008 IN BACR.p01 (plan) ---

Plan Title=Multiple Run
Short Identifier=Multiple
Geom File=g01
Flow File=f01
Subcritical Flow
K Sum by GR= 0
Std Step Tol= 0.01
Critical Tol= 0.01
Num of Std Step Trials= 20
Max Error Tol= 0.3
Flow Tol Ratio= 0.001
Split Flow NTrial= 30
Split Flow Tol= 0.02
Split Flow Ratio= 0.02
Log Output Level= 0
Friction Slope Method= 1
Unsteady Friction Slope Method= 2
Unsteady Bridges Friction Slope Method= 1
Parabolic Critical Depth
Global Vel Dist=  1 , 1 , 1
Global Log Level= 0
CheckData=True
Encroach Param= -1, 0, 0, 0
BEGIN DESCRIPTION:
Multiple Run
END DESCRIPTION:

--- UNT008 IN BACR.f01 (steady flow) ---

Flow Title=Multiple
Program Version=4.10
Number of Profiles= 7
Profile Names=10-year,25-year,50-year,1pct_min,100-year,1pct_plu,500-year
River Rch & RM=UNT008 IN BACR,Reach-1         ,35816
     475     653     799     715     967    1307    1428
River Rch & RM=UNT008 IN BACR,Reach-1         ,28707
     576     798     981     881    1191    1611    1776
Boundary for River Rch & Prof#=UNT008 IN BACR,Reach-1         , 1
Up Type= 0
Dn Type= 3
Dn Slope=0.0035
Boundary for River Rch & Prof#=UNT008 IN BACR,Reach-1         , 2
Up Type= 0
Dn Type= 3
Dn Slope=0.0035
Boundary for River Rch & Prof#=UNT008 IN BACR,Reach-1         , 3
Up Type= 0
Dn Type= 3
Dn Slope=0.0035
Boundary for River Rch & Prof#=UNT008 IN BACR,Reach-1         , 4
Up Type= 0
Dn Type= 3
Dn Slope=0.0035
Boundary for River Rch & Prof#=UNT008 IN BACR,Reach-1         , 5
Up Type= 0
Dn Type= 3
Dn Slope=0.0035
Boundary for River Rch & Prof#=UNT008 IN BACR,Reach-1         , 6
Up Type= 0
Dn Type= 3
Dn Slope=0.0035
Boundary for River Rch & Prof#=UNT008 IN BACR,Reach-1         , 7
Up Type= 0
Dn Type= 3
Dn Slope=0.0035
DSS Import GetInterval= 0
DSS Import GetPeak= 0
DSS Import FillOption= 0

--- UNT008 IN BACR.g01 (geometry) ---

Geom Title=Existing Conditions
Program Version=4.10

River Reach=UNT008 IN BACR  ,Reach-1
Reach XY= 30
      2378551.92     13144790.18      2378785.19     13145282.03
      2377689.42     13146800.47      2377759.01     13147249.46
      2377377.72     13147306.85      2378099.49     13147950.57
      2378306.96     13148646.33      2378818.45     13148952.52
      2380716.23     13148910.43       2381192.4     13149248.46
      2381072.83     13149986.43       2381360.2     13150307.12
      2383287.51     13150256.74       2383853.1     13150723.91
      2385244.96     13148837.04       2385103.7     13147647.88
      2386290.61      13146989.2      2386151.03     13146715.82
      2387272.64     13145060.78      2389258.75     13144894.12
      2390196.81     13145191.14      2392403.78     13146850.86
      2393010.83     13148810.17      2393835.42     13148846.86
      2394771.26      13148766.2       2395049.9     13148425.05
      2395578.55     13145859.95      2396036.88     13145505.78
      2395679.25     13145103.48      2396323.12     13144569.48

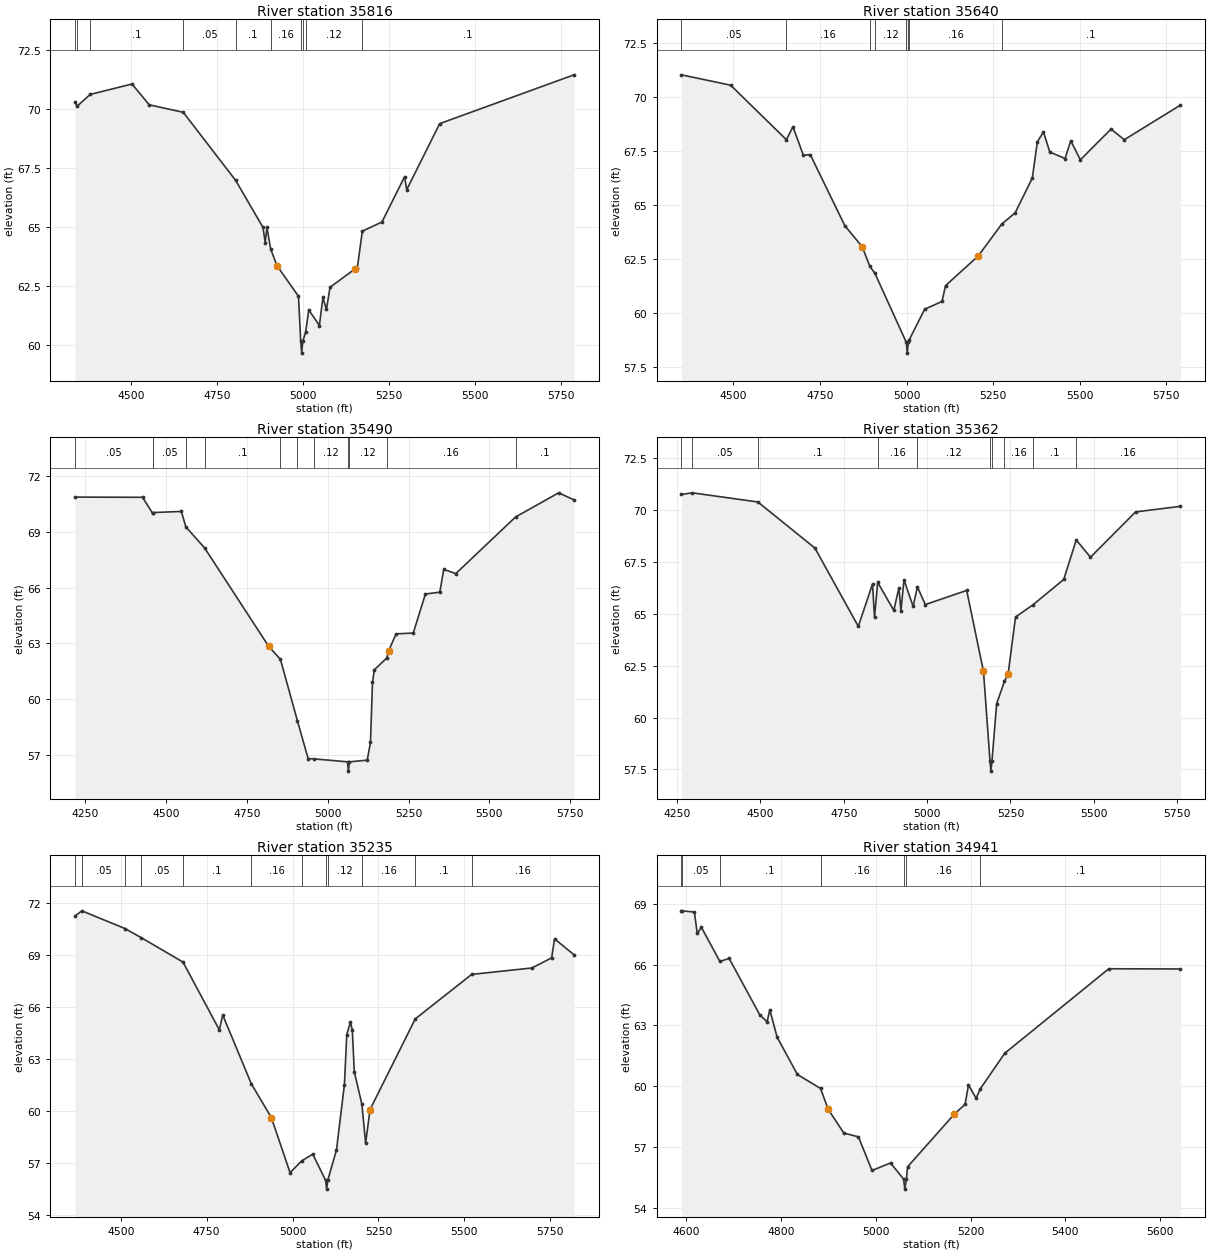
Type RM Length L Ch R = 1 ,35816   ,176,176,176
BEGIN DESCRIPTION:
UNT008 IN BACR 45.0
END DESCRIPTION:
XS GIS Cut Line= 4
      2377992.11     13144993.65      2378507.74     13144970.21
      2378762.95     13144912.92      2379134.89      13144351.1
#Sta/Elev= 30
  4337.6   70.27  4343.8   70.11  4382.1   70.61  4503.4   71.05  4553.4   70.17
  4652.6   69.85  4805.1   66.96  4884.5   64.97  4890.8   64.33  4895.9   64.97
    4907   64.04  4925.5   63.34  4987.7   62.05  4994.2   60.14    4997   59.64
  5000.2   60.14  5008.2   60.52  5017.7   61.47  5048.5   60.81  5058.7      62
    5069   61.49  5079.4   62.43  5151.9   63.21  5158.6   63.23  5173.4   64.81
  5230.5    65.2  5296.3   67.12  5302.5   66.57  5398.4   69.37  5789.1   71.44
#Mann= 10 ,-1 , 0
  4337.6      .1       0  4343.8     .05       0  4382.1      .1       0
  4652.6     .05       0  4805.1      .1       0    4907     .16       0
  4994.2     .07       0  5000.2     .16       0  5008.2     .12       0
  5173.4      .1       0
Bank Sta=4925.5,5151.9
XS Rating Curve= 0 ,0
Exp/Cntr=0.3,0.1

Type RM Length L Ch R = 1 ,35640   ,150,150,150
BEGIN DESCRIPTION:
Mapping XS 48e1fe6c
END DESCRIPTION:
XS GIS Cut Line= 5
      2378095.55     13145095.74      2378573.41     13145093.66
      2378880.88     13145070.81      2379045.01     13144869.28
      2379227.81     13144518.21
#Sta/Elev= 30
  4349.7   71.02  4491.9   70.54  4652.9   68.02  4671.9   68.62  4701.9    67.3
  4721.9   67.33  4821.9   64.04    4872   63.07  4894.1   62.16  4908.4   61.85
  4999.4   58.65  5002.1   58.15  5005.4   58.65    5007   58.74  5052.5   60.18
  5102.6   60.54  5112.7   61.27    5207   62.64  5275.4   64.12    5314   64.64
  5363.6   66.25    5378   67.92  5395.8   68.38    5414   67.45  5458.2   67.15
  5474.6   67.97  5502.4   67.09  5590.8   68.51  5629.3   68.02  5791.6   69.62
#Mann= 8 ,-1 , 0
  4349.7     .05       0  4652.9     .16       0  4894.1      .1       0
  4908.4     .12       0  4999.4     .07       0  5005.4     .12       0
    5007     .16       0  5275.4      .1       0
Bank Sta=4872,5207
XS Rating Curve= 0 ,0
Exp/Cntr=0.3,0.1

Type RM Length L Ch R = 1 ,35490   ,128,128,128
BEGIN DESCRIPTION:
Mapping XS 1423a40b
END DESCRIPTION:
XS GIS Cut Line= 3
      2378018.98     13145181.66      2378638.81      13145150.4
      2379453.32     13145584.98
#Sta/Elev= 30
    4218   70.86    4427   70.85  4458.5   69.98  4460.7   70.03  4547.2   70.09
  4560.9   69.26  4618.9   68.13  4817.5   62.83  4853.6   62.14  4906.2   58.83
  4939.4    56.8  4956.9   56.79  5061.1   56.63  5063.8   56.13  5067.1   56.63
  5122.1   56.72  5132.1   57.67  5138.4    60.9  5144.1   61.58  5182.1    62.2
  5188.7   62.61  5211.4   63.51  5264.5   63.55  5302.1   65.65  5346.6   65.75
  5358.8   66.97  5396.2   66.75  5580.9   69.79  5714.2   71.09  5761.8   70.71
#Mann= 12 ,-1 , 0
    4218     .05       0  4458.5      .1       0  4460.7     .05       0
  4560.9     .16       0  4618.9      .1       0  4853.6     .12       0
  4906.2     .16       0  4956.9     .12       0  5061.1     .07       0
  5067.1     .12       0  5182.1     .16       0  5580.9      .1       0
Bank Sta=4817.5,5188.7
XS Rating Curve= 0 ,0
Exp/Cntr=0.3,0.1

Type RM Length L Ch R = 1 ,35362   ,127,127,127
BEGIN DESCRIPTION:
UNT008 IN BACR 44.0
END DESCRIPTION:
XS GIS Cut Line= 4
      2378027.91     13145265.93      2378581.52     13145238.95
      2378867.98     13145416.03      2379412.27     13145681.66
#Sta/Elev= 30
  4263.3   70.74  4295.7   70.82  4492.4   70.38  4663.6   68.16  4793.7   64.39
  4836.4   66.43  4842.3   64.82  4851.8   66.51  4900.2   65.16  4915.6   66.25
  4921.5   65.14  4930.7   66.63  4958.1   65.35    4971   66.29  4994.8   65.44
  5118.8   66.12  5169.2   62.22  5188.7   57.92  5191.5   57.42  5194.7   57.92
  5208.7   60.67  5232.1   61.74  5243.1    62.1  5265.3   64.84  5318.6   65.44
    5410   66.65  5447.4   68.55  5490.1   67.72  5625.3    69.9    5760   70.17
#Mann= 10 ,-1 , 0
  4263.3      .1       0  4295.7     .05       0  4492.4      .1       0
  4851.8     .16       0    4971     .12       0  5188.7     .07       0
  5194.7     .12       0  5232.1     .16       0  5318.6      .1       0
  5447.4     .16       0
Bank Sta=5169.2,5243.1
XS Rating Curve= 0 ,0
Exp/Cntr=0.3,0.1

Type RM Length L Ch R = 1 ,35235   ,294,294,294
BEGIN DESCRIPTION:
UNT008 IN BACR 43.0
END DESCRIPTION:
XS GIS Cut Line= 3
      2378037.77     13145346.86      2378487.77     13145353.53
       2379399.2     13145770.18
#Sta/Elev= 30
  4366.8   71.23  4386.9   71.53  4512.2   70.51  4560.1   69.98  4681.1   68.58
  4786.8   64.68  4796.8   65.53  4879.8   61.58  4938.2   59.63  4992.7   56.46
  5026.8   57.14  5058.8   57.52  5096.3   56.01  5099.1   55.51  5102.3   56.01
  5127.8   57.77  5150.9   61.53  5157.7   64.41  5168.4   65.12  5173.9   64.67
  5179.6   62.27  5201.8   60.39  5212.6   58.16  5225.4   60.09  5357.1   65.31
  5521.2   67.87  5696.4   68.24  5753.9   68.82  5762.4   69.92    5819      69
#Mann= 12 ,-1 , 0
  4366.8      .1       0  4386.9     .05       0  4512.2      .1       0
  4560.1     .05       0  4681.1      .1       0  4879.8     .16       0
  5026.8     .12       0  5096.3     .07       0  5102.3     .12       0
  5201.8     .16       0  5357.1      .1       0  5521.2     .16       0
Bank Sta=4938.2,5225.4
XS Rating Curve= 0 ,0
Exp/Cntr=0.3,0.1

Type RM Length L Ch R = 1 ,34941   ,341,341,341
BEGIN DESCRIPTION:
Mapping XS 8db7ec86
END DESCRIPTION:
XS GIS Cut Line= 4
      2378151.65      13145486.3      2378398.89      13145635.9
      2378801.94     13145816.64      2379113.17     13145899.64
#Sta/Elev= 30
  4590.1   68.64  4590.4   68.65  4617.4   68.59  4623.3   67.54  4632.3   67.83
  4671.2   66.15  4690.7    66.3  4755.2   63.52  4770.7   63.17  4776.5   63.76
    4792   62.41  4834.7   60.57  4883.5   59.88  4899.7   58.85  4932.6   57.68
  4963.5   57.49  4992.1   55.83  5031.2    56.2  5058.7   55.41  5061.4   54.91
  5064.7   55.41  5067.1   56.01  5165.3    58.6  5188.5    59.1  5195.6   60.05
  5211.7    59.4  5220.8   59.87  5272.3   61.62  5491.7   65.79  5642.9   65.78
#Mann= 7 ,-1 , 0
  4590.1      .1       0  4590.4     .05       0  4671.2      .1       0
  4883.5     .16       0  5058.7     .07       0  5064.7     .16       0
  5220.8      .1       0
Bank Sta=4899.7,5165.3
XS Rating Curve= 0 ,0
Exp/Cntr=0.3,0.1

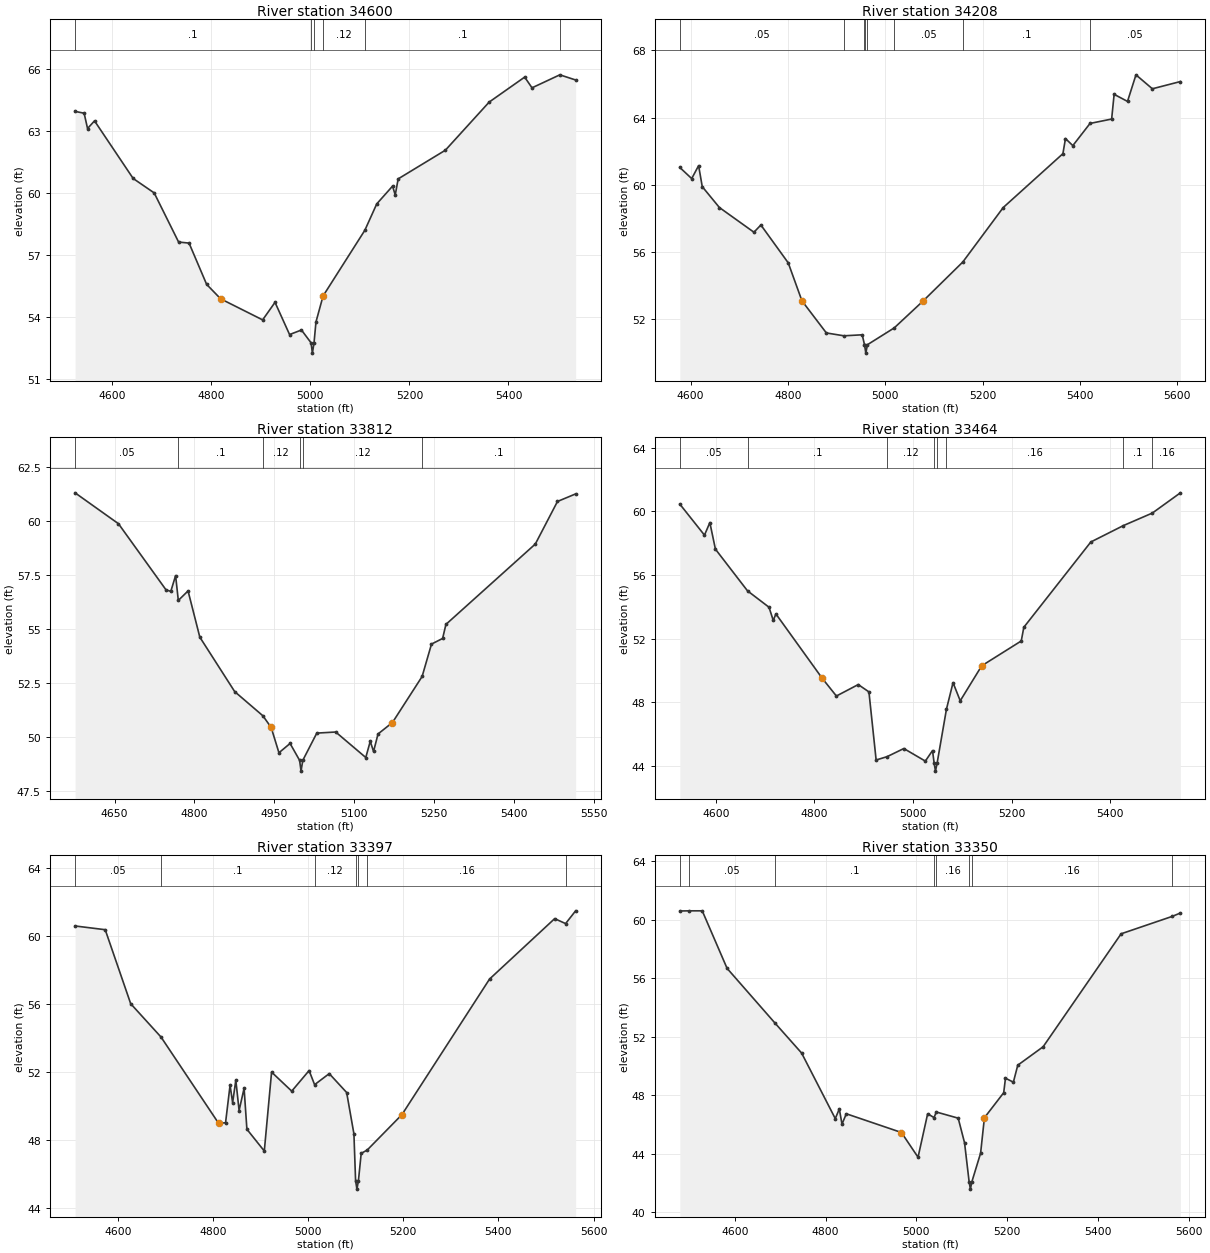
Type RM Length L Ch R = 1 ,34600   ,392,392,392
BEGIN DESCRIPTION:
UNT008 IN BACR 42.0
END DESCRIPTION:
XS GIS Cut Line= 3
      2378061.99     13145676.88       2378337.6     13145941.64
      2378919.24     13146180.37
#Sta/Elev= 30
  4524.7   63.96    4543   63.87  4549.9   63.13    4564    63.5    4642   60.71
  4684.5   60.01  4733.8   57.63  4754.9   57.58  4790.4   55.58  4818.7   54.88
  4903.5   53.86  4928.5   54.71  4957.9   53.15  4981.9   53.37  5001.3   52.75
    5004   52.25  5007.3   52.75  5011.2   53.76  5025.6   55.02  5109.9    58.2
    5134   59.48  5165.9   60.34  5171.3   59.91  5177.2   60.69  5272.6   62.08
    5361   64.41  5432.7   65.62  5447.5    65.1  5503.7   65.73  5535.6   65.48
#Mann= 6 ,-1 , 0
  4524.7      .1       0  5001.3     .07       0  5007.3      .1       0
  5025.6     .12       0  5109.9      .1       0  5503.7     .05       0
Bank Sta=4818.7,5025.6
XS Rating Curve= 0 ,0
Exp/Cntr=0.3,0.1

Type RM Length L Ch R = 1 ,34208   ,396,396,396
BEGIN DESCRIPTION:
UNT008 IN BACR 41.0
END DESCRIPTION:
XS GIS Cut Line= 4
      2377899.28     13145990.47      2378120.58     13146238.95
      2378348.45     13146317.07      2378794.12      13146410.1
#Sta/Elev= 30
  4577.7   61.04  4602.1   60.38  4616.3   61.15  4623.8    59.9    4659   58.66
    4730   57.19  4744.3   57.62  4800.5   55.37  4828.7   53.11  4878.9    51.2
    4915   51.03  4952.6   51.09  4957.2   50.51  4957.3    50.5    4960      50
  4963.3    50.5  5018.4    51.5  5077.7    53.1  5159.4   55.42  5242.5   58.66
  5365.1   61.86  5370.4   62.76  5385.5   62.34  5420.9   63.66  5465.3   63.92
  5470.4   65.39  5497.9   64.97  5515.3   66.55    5549   65.72  5606.6   66.15
#Mann= 8 ,-1 , 0
  4577.7     .05       0    4915      .1       0  4957.2     .12       0
  4957.3     .07       0  4963.3     .12       0  5018.4     .05       0
  5159.4      .1       0  5420.9     .05       0
Bank Sta=4828.7,5077.7
XS Rating Curve= 0 ,0
Exp/Cntr=0.3,0.1

Type RM Length L Ch R = 1 ,33812   ,348,348,348
BEGIN DESCRIPTION:
UNT008 IN BACR 40.0
END DESCRIPTION:
XS GIS Cut Line= 4
      2377725.63     13146152.17      2377862.34     13146464.64
      2378153.14     13146677.31      2378391.81     13146683.82
#Sta/Elev= 30
  4575.9   61.31  4657.4   59.88  4746.7   56.82  4755.7   56.75  4764.7   57.48
  4769.8   56.33  4788.1   56.77  4810.2   54.63  4875.7   52.11  4928.7   50.99
  4944.2   50.45  4958.8   49.28  4979.7   49.71  4997.6   48.93  5000.3   48.43
  5003.6   48.93  5029.9   50.19  5065.4   50.24  5121.9   49.06  5130.3   49.81
  5136.5   49.34  5144.9   50.15    5172   50.68  5227.7   52.81  5245.3   54.31
  5266.2   54.57  5272.4   55.22  5440.3   58.94  5481.9   60.91    5516   61.26
#Mann= 6 ,-1 , 0
  4575.9     .05       0  4769.8      .1       0  4928.7     .12       0
  4997.6     .07       0  5003.6     .12       0  5227.7      .1       0
Bank Sta=4944.2,5172
XS Rating Curve= 0 ,0
Exp/Cntr=0.3,0.1

Type RM Length L Ch R = 1 ,33464   ,67,67,67
BEGIN DESCRIPTION:
Mapping XS 13c7b4ec
END DESCRIPTION:
XS GIS Cut Line= 4
      2377525.97     13146340.95      2377662.68     13146655.61
      2377914.42     13146846.58      2378268.12     13146803.19
#Sta/Elev= 30
    4527   60.45    4577    58.5  4587.9   59.29  4599.2   57.62  4664.3      55
  4707.9   53.97  4716.5   53.14  4721.9   53.55  4815.7   49.51  4844.6   48.39
  4888.9   49.11  4910.6   48.65  4925.2   44.37  4947.5   44.58  4981.4   45.09
    5025    44.3  5039.6   44.96  5042.9   44.17  5045.6   43.67  5048.9   44.17
  5067.9   47.57  5081.2   49.23  5095.8   48.09  5139.4   50.29  5219.6   51.85
  5224.8   52.71  5360.7   58.07  5426.7    59.1  5485.6   59.89  5542.4   61.16
#Mann= 8 ,-1 , 0
    4527     .05       0  4664.3      .1       0  4947.5     .12       0
  5042.9     .07       0  5048.9     .12       0  5067.9     .16       0
  5426.7      .1       0  5485.6     .16       0
Bank Sta=4815.7,5139.4
XS Rating Curve= 0 ,0
Exp/Cntr=0.3,0.1

Type RM Length L Ch R = 1 ,33397   ,47,47,47
BEGIN DESCRIPTION:
UNT008 IN BACR 39.0
END DESCRIPTION:
XS GIS Cut Line= 4
      2377458.71     13146373.54       2377588.9     13146694.68
      2377920.93     13146903.01      2378231.24      13146853.1
#Sta/Elev= 30
  4509.6   60.57    4573   60.35  4626.6      56  4690.4   54.04  4811.5   48.97
  4826.1      49  4835.6   51.21    4841   50.18  4847.7   51.51  4854.6   49.72
  4865.1   51.03    4871   48.62  4907.6   47.34  4922.9   51.98  4965.3   50.86
  5001.8   52.07  5013.4   51.24  5044.2   51.89  5080.8   50.78  5096.1   48.35
  5099.6    45.6  5102.4    45.1  5105.6    45.6  5111.4    47.2  5124.1    47.4
  5197.1   49.48  5381.4   57.45  5518.3      61  5541.3   60.71  5562.4   61.46
#Mann= 7 ,-1 , 0
  4509.6     .05       0  4690.4      .1       0  5013.4     .12       0
  5099.6     .07       0  5105.6     .12       0  5124.1     .16       0
  5541.3      .1       0
Bank Sta=4811.5,5197.1
XS Rating Curve= 0 ,0
Exp/Cntr=0.3,0.1

Type RM Length L Ch R = 1 ,33350   ,252,252,252
BEGIN DESCRIPTION:
Mapping XS dfd3a08e
END DESCRIPTION:
XS GIS Cut Line= 5
      2377415.28     13146395.19      2377538.99     13146718.55
      2377855.83     13146916.03      2377910.08     13146948.58
      2378226.87     13146900.85
#Sta/Elev= 30
  4478.8   60.59  4500.1    60.6  4528.2    60.6  4582.9   56.67  4688.5   52.93
  4747.2   50.88  4821.4    46.4  4830.3   47.06  4836.2   46.02  4845.7   46.73
  4967.2   45.45  5003.8   43.76    5025   46.73    5039   46.47  5044.1   46.85
  5092.3   46.43  5106.3   44.75  5116.4   42.08  5119.2   41.58  5122.4   42.08
  5141.7   44.04  5150.1   46.46  5192.6   48.17  5196.5   49.16  5213.9   48.89
  5223.6   50.05  5279.5   51.31  5451.4   59.03    5564   60.22    5582   60.45
#Mann= 8 ,-1 , 0
  4478.8      .1       0  4500.1     .05       0  4688.5      .1       0
    5039     .12       0  5044.1     .16       0  5116.4     .07       0
  5122.4     .16       0    5564      .1       0
Bank Sta=4967.2,5150.1
XS Rating Curve= 0 ,0
Exp/Cntr=0.3,0.1

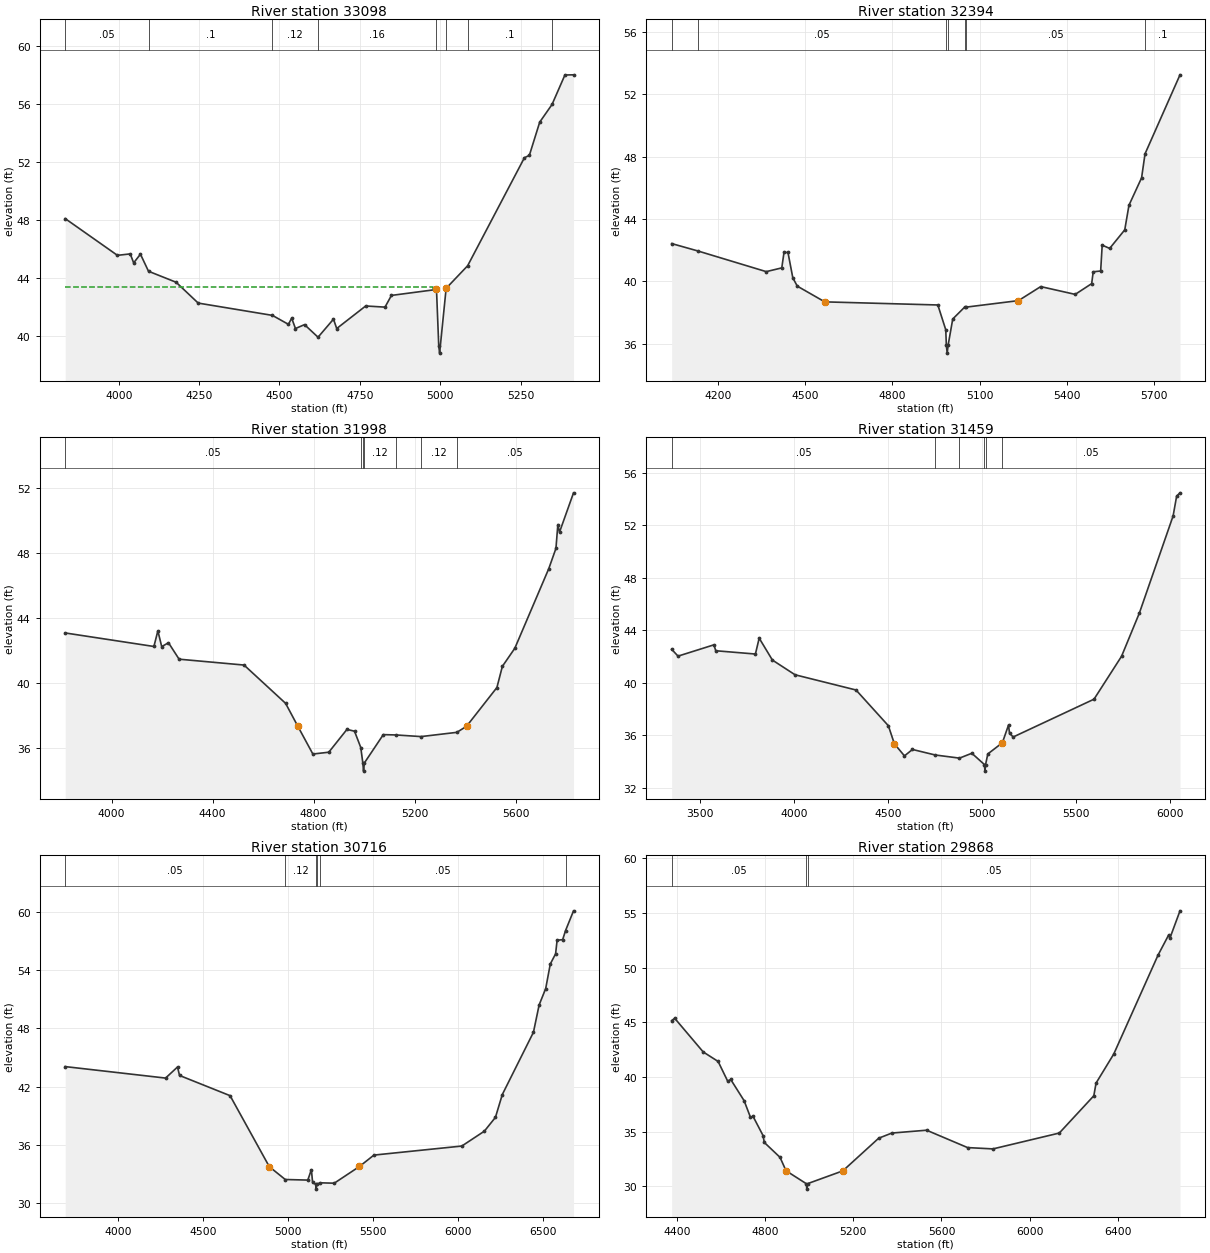
Type RM Length L Ch R = 1 ,33098   ,704,704,704
BEGIN DESCRIPTION:
Mapping XS 3be234a6
END DESCRIPTION:
XS GIS Cut Line= 4
      2376586.15     13146960.32       2376986.5     13147097.02
      2377919.12     13147048.19      2378133.29     13146980.04
#Sta/Elev= 30
  3833.3   48.09  3995.8   45.55  4035.7   45.65  4046.3   45.03  4067.4   45.63
  4092.5   44.45  4178.4   43.69  4247.1   42.25    4478    41.4  4527.9   40.78
    4538   41.21  4549.7   40.49    4578   40.76    4620   39.89  4668.1   41.14
  4678.1   40.49  4768.3   42.05  4828.4   41.97  4848.4   42.78  4988.6   43.19
  4995.6   39.29  4998.3   38.79  5018.6   43.27  5085.5   44.83  5262.2    52.3
  5277.5   52.46  5309.8   54.76  5348.1   55.98  5388.2   58.02    5415   58.03
#Mann= 8 ,-1 , 0
  3833.3     .05       0  4092.5      .1       0    4478     .12       0
    4620     .16       0  4988.6     .07       0  5018.6     .16       0
  5085.5      .1       0  5348.1     .16       0
#XS Ineff= 2 , 0
       0 4978.18   43.35               0
Permanent Ineff=
       T       F
Bank Sta=4988.6,5018.6
XS Rating Curve= 0 ,0
Exp/Cntr=0.3,0.1

Type RM Length L Ch R = 1 ,32394   ,396,396,396
BEGIN DESCRIPTION:
Mapping XS 1bb88585
END DESCRIPTION:
XS GIS Cut Line= 5
      2376503.14     13147336.29      2376962.08     13147507.18
      2377621.26     13147365.57      2377967.11     13147243.64
      2378099.77     13147072.62
#Sta/Elev= 30
  4041.5   42.42  4130.9   41.95  4366.5   40.62  4419.9   40.86  4427.6   41.85
  4441.2   41.85  4457.9   40.22  4473.2   39.69  4567.7   38.68  4956.3   38.48
  4983.5   36.89  4985.6   35.89  4988.4   35.39  4991.6   35.89  5007.5   37.58
  5048.3   38.34  5052.8   38.34  5233.5   38.76  5309.9   39.66  5428.4   39.16
    5485   39.85  5490.3   40.61  5515.9   40.66  5521.2   42.32  5546.9   42.11
  5598.7    43.3  5613.2   44.88  5656.6   46.64  5668.4   48.18  5788.6   53.25
#Mann= 7 ,-1 , 0
  4041.5      .1       0  4130.9     .05       0  4985.6     .03       0
  4991.6     .05       0  5048.3     .12       0  5052.8     .05       0
  5668.4      .1       0
Bank Sta=4567.7,5233.5
XS Rating Curve= 0 ,0
Exp/Cntr=0.3,0.1

Type RM Length L Ch R = 1 ,31998   ,539,539,539
BEGIN DESCRIPTION:
UNT008 IN BACR 38.0
END DESCRIPTION:
XS GIS Cut Line= 4
       2376576.3     13148117.54      2377308.76     13147941.75
       2377865.4     13147565.77      2378260.58     13147131.56
#Sta/Elev= 30
  3816.5   43.08  4167.6   42.25  4183.3   43.21  4198.5   42.24  4225.3   42.48
  4267.3   41.47  4524.4   41.11  4688.9   38.76  4737.4   37.35  4796.8   35.65
  4859.8   35.76  4931.7   37.16  4961.7   37.05  4986.4   36.05  4994.6    35.1
  4997.4    34.6  5000.6    35.1  5075.6   36.84    5126   36.82    5225   36.72
  5366.7   36.98    5405   37.35  5525.3   39.73  5546.9   41.03  5596.2   42.14
  5730.7   47.03    5759   48.27  5766.5   49.73  5773.2   49.27  5828.6   51.68
#Mann= 7 ,-1 , 0
  3816.5     .05       0  4986.4     .12       0  4994.6     .07       0
  5000.6     .12       0    5126     .05       0    5225     .12       0
  5366.7     .05       0
Bank Sta=4737.4,5405
XS Rating Curve= 0 ,0
Exp/Cntr=0.3,0.1

Type RM Length L Ch R = 1 ,31459   ,743,743,743
BEGIN DESCRIPTION:
UNT008 IN BACR 37.0
END DESCRIPTION:
XS GIS Cut Line= 4
      2376493.98     13148241.04      2377570.41     13148164.65
      2378320.41     13147879.93      2378577.36     13147102.13
#Sta/Elev= 30
  3350.4   42.54  3384.2   42.02  3574.7   42.88  3584.7   42.43  3795.3   42.18
  3815.3   43.39  3885.5   41.72  4005.8    40.6  4329.7   39.44  4501.5   36.72
  4533.6   35.34  4587.1   34.42  4629.6   34.91  4750.2   34.49  4879.4   34.25
    4945   34.62    5012   33.76  5014.7   33.26    5018   33.76    5030   34.57
  5107.2   35.42  5139.9   36.77  5145.2   36.15  5164.7   35.86  5594.1   38.74
  5740.5   42.01  5835.3   45.31  6014.3    52.7  6033.1   54.21  6050.9   54.46
#Mann= 6 ,-1 , 0
  3350.4     .05       0  4750.2      .1       0  4879.4     .12       0
    5012     .07       0    5018     .12       0  5107.2     .05       0
Bank Sta=4533.6,5107.2
XS Rating Curve= 0 ,0
Exp/Cntr=0.3,0.1

Type RM Length L Ch R = 1 ,30716   ,848,848,848
BEGIN DESCRIPTION:
UNT008 IN BACR 36.0
END DESCRIPTION:
XS GIS Cut Line= 4
      2377112.05     13149081.32      2378105.13     13148852.15
       2378709.3      13148282.7      2379028.75     13147185.47
#Sta/Elev= 30
  3690.1   44.06  4280.9   42.88  4351.2   44.02    4363   43.15  4660.6   41.07
  4891.5   33.77  4985.3   32.45  5118.1   32.39  5139.1   33.46  5146.4   32.15
  5164.4   31.96  5167.2   31.46  5170.4   31.96    5191   32.11  5273.8   32.07
  5422.3   33.79  5507.3   34.96  6024.7   35.89  6157.4   37.42  6222.6   38.84
  6263.1   41.19  6446.3   47.59  6479.8    50.4  6518.5   52.09  6545.5   54.61
  6576.7   55.66  6585.6   57.05  6618.4   57.12  6635.1   58.04  6682.3   60.08
#Mann= 6 ,-1 , 0
  3690.1     .05       0  4985.3     .12       0  5164.4     .07       0
  5170.4     .12       0    5191     .05       0  6635.1      .1       0
Bank Sta=4891.5,5422.3
XS Rating Curve= 0 ,0
Exp/Cntr=0.3,0.1

Type RM Length L Ch R = 1 ,29868   ,464,464,464
BEGIN DESCRIPTION:
UNT008 IN BACR 35.0
END DESCRIPTION:
XS GIS Cut Line= 4
      2378832.21     13149528.64      2378964.04     13149304.05
      2379112.72     13148521.85      2379237.47     13147277.71
#Sta/Elev= 30
  4375.6   45.17  4389.3   45.38  4518.7    42.3  4586.4   41.43  4630.2   39.61
  4643.3   39.79  4704.4   37.84    4733   36.33  4745.1    36.4  4790.3   34.65
    4796   34.02  4867.3   32.66  4894.7   31.43  4986.4   30.25  4989.2   29.75
  4992.4   30.25  5152.3   31.42  5315.2   34.41  5374.9   34.88  5532.6   35.14
  5718.6   33.55  5833.7   33.43  6134.8   34.88  6291.5   38.29  6301.6   39.45
    6382   42.11    6583   51.16  6631.6   53.02  6636.6    52.7  6682.6   55.21
#Mann= 3 ,-1 , 0
  4375.6     .05       0  4986.4     .03       0  4992.4     .05       0
Bank Sta=4894.7,5152.3
XS Rating Curve= 0 ,0
Exp/Cntr=0.3,0.1

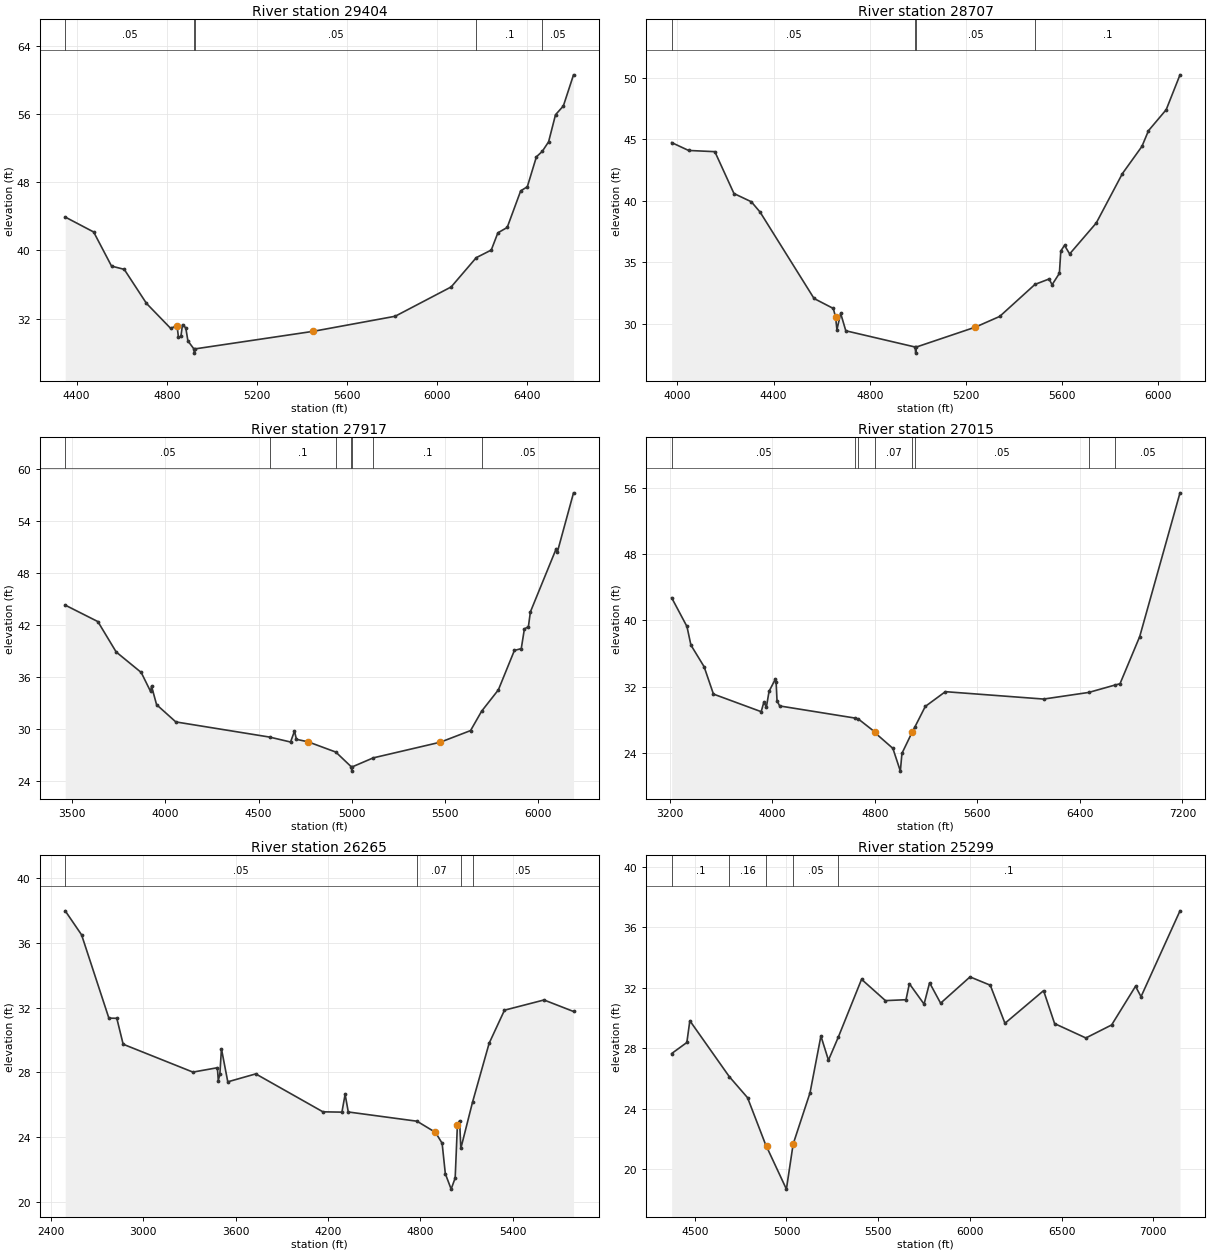
Type RM Length L Ch R = 1 ,29404   ,697,697,697
BEGIN DESCRIPTION:
UNT008 IN BACR 34.0
END DESCRIPTION:
XS GIS Cut Line= 3
      2379178.89     13149465.17      2379359.54     13149221.04
      2380101.71     13147414.45
#Sta/Elev= 30
  4349.2   43.91  4475.5   42.16  4554.9   38.16  4611.2   37.78    4710   33.79
  4816.7   30.88    4846   31.14    4852    29.8  4862.8   29.91    4870    31.3
  4884.5   30.92    4894   29.39  4920.4   28.46  4923.1   27.96  4926.4   28.46
  5451.4   30.52    5814   32.28  6062.8   35.72  6174.1   39.15  6240.7   40.04
  6270.1   42.06  6311.5   42.69  6371.4   46.98  6400.8   47.46  6441.2   50.97
  6467.2   51.61  6495.3   52.73    6526    55.9  6560.8   56.93    6606   60.58
#Mann= 5 ,-1 , 0
  4349.2     .05       0  4920.4     .03       0  4926.4     .05       0
  6174.1      .1       0  6467.2     .05       0
Bank Sta=4846,5451.4
XS Rating Curve= 0 ,0
Exp/Cntr=0.3,0.1

Type RM Length L Ch R = 1 ,28707   ,790,790,790
BEGIN DESCRIPTION:
UNT008 IN BACR 33.0
END DESCRIPTION:
XS GIS Cut Line= 3
      2379418.95     13149446.76      2379983.17     13149088.69
      2380731.84     13147851.77
#Sta/Elev= 30
  3975.9   44.74  4046.2    44.1  4155.5      44    4235   40.59  4307.2   39.92
  4343.6   39.08  4568.1   32.04  4648.1   31.23  4657.4   30.54  4663.2    29.5
  4678.7   30.83  4700.1   29.41    4988   28.09  4990.8   27.59    4994   28.09
  5239.3   29.71  5340.2   30.58    5487   33.19  5545.7   33.63    5558   33.16
  5588.4   34.09  5594.3   35.91  5609.8   36.37  5631.1   35.67  5741.7   38.19
  5850.3   42.21  5931.7   44.43  5958.9   45.71  6032.6   47.42    6090   50.26
#Mann= 4 ,-1 , 0
  3975.9     .05       0    4988     .03       0    4994     .05       0
    5487      .1       0
Bank Sta=4657.4,5239.3
XS Rating Curve= 0 ,0
Exp/Cntr=0.3,0.1

Type RM Length L Ch R = 1 ,27917   ,888,888,888
BEGIN DESCRIPTION:
UNT008 IN BACR 32.0
END DESCRIPTION:
XS GIS Cut Line= 5
      2379442.55     13149494.48      2380199.39     13149304.05
      2380819.51     13149108.74      2381132.01     13148732.76
      2381424.77     13147981.35
#Sta/Elev= 30
  3462.5   44.28  3637.6   42.38  3735.9   38.87    3870   36.51  3920.2   34.32
  3925.4   34.93  3952.5   32.79  4055.6    30.8  4558.4   29.05    4671   28.48
    4692   29.74  4702.5   28.79  4765.4    28.5  4913.6   27.32  4996.6   25.62
  4999.3   25.12  5002.6   25.62  5114.4   26.65  5474.2   28.46  5636.2    29.8
  5695.6   32.04  5785.4    34.5  5871.3   39.05  5908.1   39.26  5924.9   41.53
  5946.4    41.8  5957.1    43.5  6095.7    50.8  6101.1   50.36  6188.4   57.24
#Mann= 7 ,-1 , 0
  3462.5     .05       0  4558.4      .1       0  4913.6     .12       0
  4996.6     .07       0  5002.6     .12       0  5114.4      .1       0
  5695.6     .05       0
Bank Sta=4765.4,5474.2
XS Rating Curve= 0 ,0
Exp/Cntr=0.3,0.1

Type RM Length L Ch R = 1 ,27015   ,750,750,750
BEGIN DESCRIPTION:
UNT008 IN BACR 32.0
END DESCRIPTION:
XS GIS Cut Line= 5
      2379412.38     13149596.91      2380391.59     13149852.13
      2381480.13     13149690.68      2381631.17     13149445.88
      2381985.98     13147920.83
#Sta/Elev= 30
  3215.7   42.72  3334.9   39.26  3365.9   37.02  3468.6   34.42  3541.6   31.12
    3914      29  3934.3   30.11  3954.9   29.58  3975.6   31.46  4025.2   32.94
  4030.4   32.63  4037.6   30.31  4058.3   29.69  4646.6   28.23  4671.1   28.13
    4800   26.57  4804.4   26.43  4941.5   24.58  4999.8   21.84  5012.2   23.98
  5093.1   26.57  5112.6   27.14  5194.2   29.63  5351.1   31.41  6117.8   30.52
    6470   31.32  6676.8   32.22  6713.3   32.36  6867.3   38.05  7181.5   55.36
#Mann= 8 ,-1 , 0
  3215.7     .05       0  4646.6      .1       0  4671.1     .05       0
  4804.4     .07       0  5093.1     .12       0  5112.6     .05       0
    6470      .1       0  6676.8     .05       0
Bank Sta=4800,5093.1
XS Rating Curve= 0 ,0
Exp/Cntr=0.3,0.1

Type RM Length L Ch R = 1 ,26265   ,633,633,633
BEGIN DESCRIPTION:
UNT008 IN BACR 32.1
END DESCRIPTION:
XS GIS Cut Line= 3
      2379052.19     13149985.82      2381239.68     13150524.01
      2381899.38     13149708.06
#Sta/Elev= 30
  2492.8   37.97  2599.1   36.49  2776.5   31.35    2828   31.34  2869.2   29.74
  3322.4   28.02  3481.4   28.29  3487.1    27.5  3497.4   27.88  3507.7   29.46
  3548.9   27.42  3730.5   27.91  4166.8   25.57  4290.4   25.55    4311   26.65
  4331.6   25.56  4778.1   24.99  4898.1    24.3  4941.2   23.63    4962   21.75
  4999.8    20.8    5026   21.49  5040.4   24.76  5054.7   25.02  5062.7   23.31
  5138.6   26.16  5246.6    29.8  5346.3   31.84  5603.1   32.47  5794.8   31.76
#Mann= 4 ,-1 , 0
  2492.8     .05       0  4778.1     .07       0  5062.7      .1       0
  5138.6     .05       0
Bank Sta=4898.1,5040.4
XS Rating Curve= 0 ,0
Exp/Cntr=0.3,0.1

Type RM Length L Ch R = 1 ,25299   ,1046,1046,1046
BEGIN DESCRIPTION:
UNT008 IN BACR 32.3
END DESCRIPTION:
XS GIS Cut Line= 3
      2382133.96     13150995.17      2382314.12     13150658.08
      2382471.06     13148274.96
#Sta/Elev= 30
  4374.5   27.65  4457.2   28.38  4473.5   29.82  4688.6   26.12    4788   24.73
  4890.4    21.5  4891.4    21.5  4999.8   18.68  5036.6   21.66  5128.7   25.06
  5187.9   28.81    5229   27.21  5282.9   28.74  5409.4   32.56  5539.6   31.15
  5651.7   31.21  5669.9   32.27  5750.1   30.92  5780.2   32.33  5840.3   30.98
  6000.6   32.72  6110.9   32.17    6191   29.65  6401.5   31.81  6461.6   29.63
    6632   28.68  6772.3   29.54  6902.6    32.1  6932.6   31.41    7145   37.09
#Mann= 5 ,-1 , 0
  4374.5      .1       0  4688.6     .16       0  4890.4     .04       0
  5036.6     .05       0  5282.9      .1       0
Bank Sta=4891.4,5036.6
XS Rating Curve= 0 ,0
Exp/Cntr=0.3,0.1

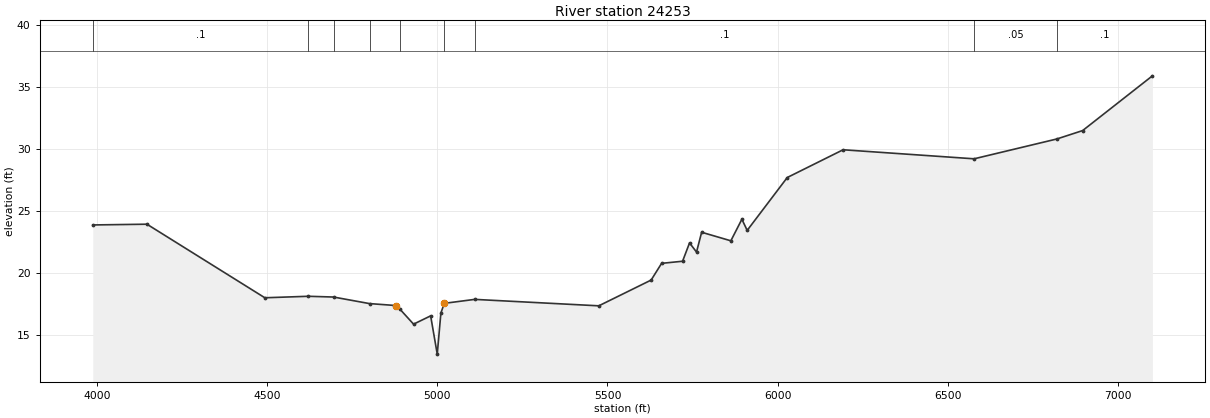
Type RM Length L Ch R = 1 ,24253   ,0,0,0
BEGIN DESCRIPTION:
UNT008 IN BACR 1.0
END DESCRIPTION:
XS GIS Cut Line= 4
      2382819.79     13151094.04       2383232.5     13150692.96
      2383296.43     13149902.46      2382907.29     13148200.66
#Sta/Elev= 30
  3987.4   23.89  4146.6   23.95  4493.1   18.01  4620.6   18.13  4694.9   18.07
  4800.7   17.54    4880   17.38  4890.1   17.09  4930.2   15.88  4980.4   16.55
  4999.8   13.46  5010.5   16.78  5020.5   17.56  5109.9   17.88  5474.6   17.36
  5628.4   19.44  5659.2   20.79  5720.8   20.96  5741.3   22.44  5761.8    21.7
  5776.8    23.3  5862.7   22.61  5895.1   24.35  5910.7   23.45  6028.5   27.72
  6192.6   29.96  6577.6   29.23  6820.6   30.83  6896.6   31.51  7101.7   35.93
#Mann= 9 ,-1 , 0
  3987.4      .1       0  4620.6     .16       0  4694.9      .1       0
  4800.7      .1       0  4890.1     .03       0  5020.5      .1       0
  5109.9      .1       0  6577.6     .05       0  6820.6      .1       0
Bank Sta=4880,5020.5
XS Rating Curve= 0 ,0
Exp/Cntr=0.3,0.1

Chan Stop Cuts=-1
Use User Specified Reach Order=0
Composite Channel Slope=5