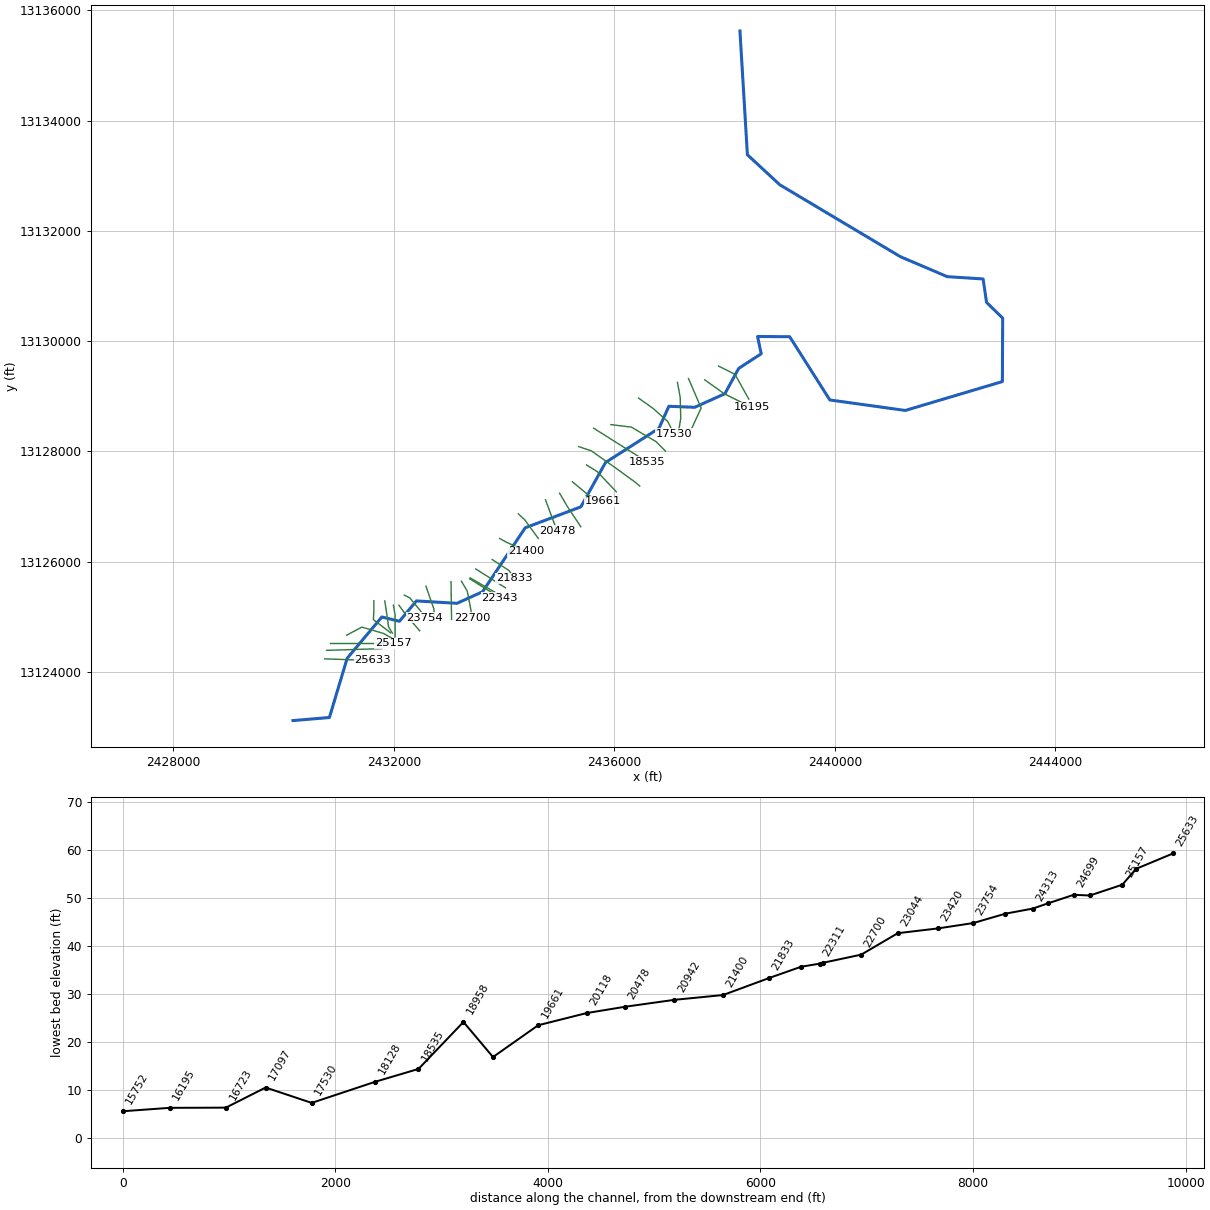
--- UNT009 IN BACR.prj (project) ---

Proj Title=UNT009 IN BACR Base Level Engineering
Current Plan=p01
Default Exp/Contr=0.3,0.1
English Units
Geom File=g01
Flow File=f01
Plan File=p01
Y Axis Title=Elevation
X Axis Title(PF)=Main Channel Distance
X Axis Title(XS)=Station
BEGIN DESCRIPTION:
UNT009 IN BACR
END DESCRIPTION:
DSS Export Rating Curves= 0
DSS Export Rating Curve Sorted= 0
DSS Export Volume Flow Curves= 0
DXF OffsetX= 0
DXF OffsetY= 0
DXF ScaleX= 1
DXF ScaleY= 10

--- UNT009 IN BACR.p01 (plan) ---

Plan Title=Multiple Run
Short Identifier=Multiple
Geom File=g01
Flow File=f01
Subcritical Flow
K Sum by GR= 0
Std Step Tol= 0.01
Critical Tol= 0.01
Num of Std Step Trials= 20
Max Error Tol= 0.3
Flow Tol Ratio= 0.001
Split Flow NTrial= 30
Split Flow Tol= 0.02
Split Flow Ratio= 0.02
Log Output Level= 0
Friction Slope Method= 1
Unsteady Friction Slope Method= 2
Unsteady Bridges Friction Slope Method= 1
Parabolic Critical Depth
Global Vel Dist=  1 , 1 , 1
Global Log Level= 0
CheckData=True
Encroach Param= -1, 0, 0, 0
BEGIN DESCRIPTION:
Multiple Run
END DESCRIPTION:

--- UNT009 IN BACR.f01 (steady flow) ---

Flow Title=Multiple
Program Version=4.10
Number of Profiles= 7
Profile Names=10-year,25-year,50-year,1pct_min,100-year,1pct_plu,500-year
River Rch & RM=UNT009 IN BACR,Reach-1         ,25633
     630     820     966     659    1117    1575    1483
River Rch & RM=UNT009 IN BACR,Reach-1         ,24459
     969    1259    1483    1012    1715    2418    2275
River Rch & RM=UNT009 IN BACR,Reach-1         ,22134
    1106    1437    1692    1155    1957    2760    2595
River Rch & RM=UNT009 IN BACR,Reach-1         ,18535
    1202    1561    1838    1254    2126    2998    2819
River Rch & RM=UNT009 IN BACR,Reach-1         ,15258
    1391    1806    2125    1451    2459    3467    3259
Boundary for River Rch & Prof#=UNT009 IN BACR,Reach-1         , 1
Up Type= 0
Dn Type= 3
Dn Slope=0.005
Boundary for River Rch & Prof#=UNT009 IN BACR,Reach-1         , 2
Up Type= 0
Dn Type= 3
Dn Slope=0.005
Boundary for River Rch & Prof#=UNT009 IN BACR,Reach-1         , 3
Up Type= 0
Dn Type= 3
Dn Slope=0.005
Boundary for River Rch & Prof#=UNT009 IN BACR,Reach-1         , 4
Up Type= 0
Dn Type= 3
Dn Slope=0.005
Boundary for River Rch & Prof#=UNT009 IN BACR,Reach-1         , 5
Up Type= 0
Dn Type= 3
Dn Slope=0.005
Boundary for River Rch & Prof#=UNT009 IN BACR,Reach-1         , 6
Up Type= 0
Dn Type= 3
Dn Slope=0.005
Boundary for River Rch & Prof#=UNT009 IN BACR,Reach-1         , 7
Up Type= 0
Dn Type= 3
Dn Slope=0.005
DSS Import GetInterval= 0
DSS Import GetPeak= 0
DSS Import FillOption= 0

--- UNT009 IN BACR.g01 (geometry) ---

Geom Title=Existing Conditions
Program Version=4.10

River Reach=UNT009 IN BACR  ,Reach-1
Reach XY= 30
      2430169.04     13123114.93      2430830.06     13123170.88
      2431151.91     13124244.75      2431781.76     13124994.79
      2432100.14     13124916.19       2432407.6     13125285.61
      2433143.74     13125242.19      2433609.73     13125453.09
      2434381.59     13126611.98      2435391.14     13126992.19
      2435839.37     13127797.23      2436808.01      13128416.8
      2436988.01     13128816.49      2437456.98     13128797.98
      2438004.24     13129044.69       2438255.2     13129504.49
      2438663.25     13129768.88      2438596.35     13130082.47
      2439179.27      13130078.3      2439908.37     13128930.95
      2441277.19      13128740.8      2443037.95     13129264.85
      2443043.16     13130415.89      2442750.78     13130700.45
      2442688.12     13131126.17       2442038.1     13131167.78
      2441188.85     13131529.58      2438999.88      13132834.7
      2438412.34     13133379.73       2438277.2     13135624.94

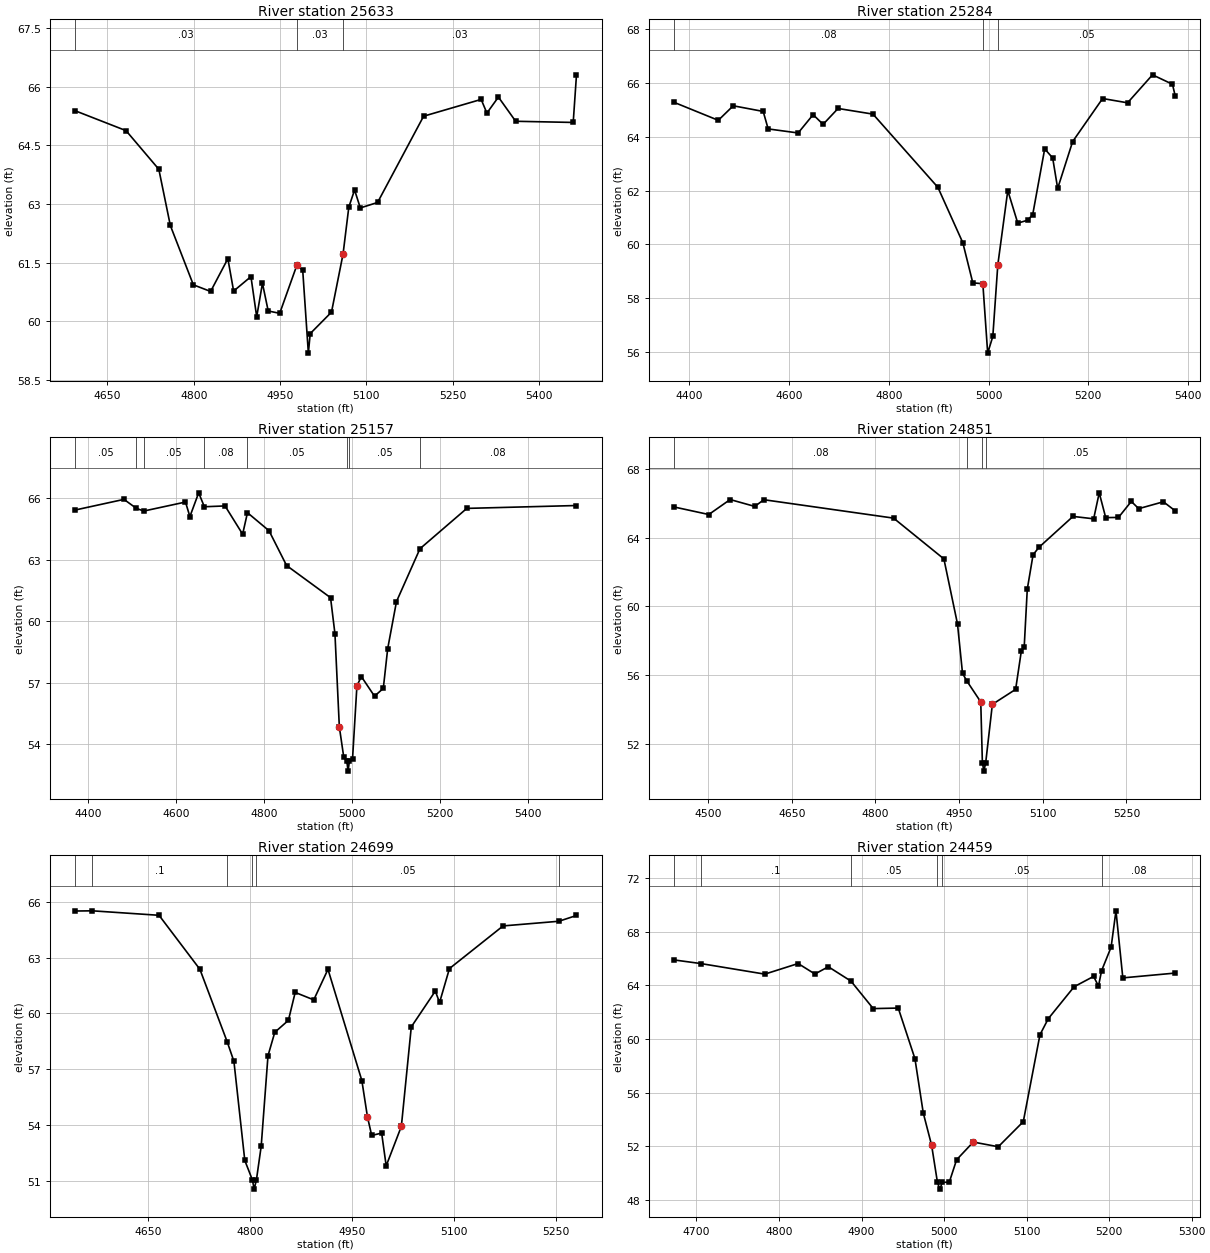
Type RM Length L Ch R = 1 ,25633   ,349,349,349
BEGIN DESCRIPTION:
Mapping XS 483cceae
END DESCRIPTION:
XS GIS Cut Line= 3
      2430742.35     13124234.92      2431260.83     13124216.56
       2431613.4     13124221.14
#Sta/Elev= 30
  4593.9   65.39  4682.4   64.88  4739.4   63.89  4759.4   62.45  4799.4   60.93
  4829.4   60.76  4859.4    61.6  4869.4   60.77  4899.5   61.14  4909.5   60.11
  4919.5   60.97  4929.5   60.26  4949.5    60.2  4979.5   61.44  4989.5    61.3
  4999.3   59.18  5002.5   59.68  5039.5   60.23  5059.6   61.72  5069.6   62.92
  5079.6   63.36  5089.6    62.9  5119.6   63.04  5199.6   65.25  5299.6   65.68
  5309.6   65.33  5329.6   65.74  5359.6   65.12  5459.6   65.09  5465.3   66.31
#Mann= 3 , 0 , 0
  4593.9     .03       0  4979.5     .03       0  5059.6     .03       0
Bank Sta=4979.5,5059.6
XS Rating Curve= 0 ,0
Exp/Cntr=0.3,0.1

Type RM Length L Ch R = 1 ,25284   ,127,127,127
BEGIN DESCRIPTION:
UNT009 IN BACR 31.0
END DESCRIPTION:
XS GIS Cut Line= 2
      2430778.87     13124388.79      2431783.38     13124420.02
#Sta/Elev= 30
  4369.3   65.28  4458.2   64.61  4488.2   65.15  4548.2   64.94  4558.2   64.29
  4618.3   64.14  4648.3   64.82  4668.3   64.46  4698.3   65.05  4768.3   64.84
  4898.4   62.12  4948.4   60.06  4968.4   58.57  4988.5   58.54  4998.2   55.96
  5008.5   56.58  5018.5   59.24  5038.5      62  5058.5   60.79  5078.5    60.9
  5088.5   61.11  5112.5   63.55  5128.5   63.21  5138.5   62.08  5168.5   63.82
  5228.6   65.42  5278.6   65.26  5328.6    66.3  5368.6   65.95  5374.3    65.5
#Mann= 3 , 0 , 0
  4369.3     .08       0  4988.5     .03       0  5018.5     .05       0
Bank Sta=4988.5,5018.5
XS Rating Curve= 0 ,0
Exp/Cntr=0.3,0.1

Type RM Length L Ch R = 1 ,25157   ,306,306,306
BEGIN DESCRIPTION:
Mapping XS c1f2f029
END DESCRIPTION:
XS GIS Cut Line= 2
       2430846.6     13124513.79       2431987.2     13124513.79
#Sta/Elev= 30
  4370.4   65.43  4481.5   65.95  4509.9   65.51  4526.5   65.38  4621.5   65.82
  4631.5   65.11  4651.5   66.27  4664.4   65.59  4711.5   65.63  4751.5   64.25
  4762.5    65.3  4811.5   64.42  4851.5   62.72  4951.5   61.15  4961.5   59.39
  4971.5   54.84  4981.5   53.37  4988.5   53.18  4991.3   52.68  4994.5   53.18
  5001.5   53.27  5011.5   56.84  5021.5    57.3  5051.5   56.34  5071.5   56.72
  5081.5   58.66  5101.5   60.96  5154.9   63.54  5261.5   65.51    5511   65.65
#Mann= 8 ,-1 , 0
  4370.4     .05       0  4509.9     .08       0  4526.5     .05       0
  4664.4     .08       0  4762.5     .05       0  4988.5     .04       0
  4994.5     .05       0  5154.9     .08       0
Bank Sta=4971.5,5011.5
XS Rating Curve= 0 ,0
Exp/Cntr=0.3,0.1

Type RM Length L Ch R = 1 ,24851   ,152,152,152
BEGIN DESCRIPTION:
UNT009 IN BACR 30.0
END DESCRIPTION:
XS GIS Cut Line= 4
      2431143.42     13124664.82      2431419.49     13124810.67
      2431810.11     13124696.08      2431966.36     13124607.55
#Sta/Elev= 30
  4438.8   65.78  4501.3   65.34  4539.6   66.21  4583.7   65.81    4600    66.2
  4832.6   65.13  4922.8   62.76  4947.2   58.98  4956.2   56.11  4964.5   55.64
  4988.9   54.45  4991.8   50.93  4994.5   50.43  4997.8   50.93  5009.7   54.31
  5051.4   55.18  5061.6    57.4  5066.8   57.65  5072.3      61  5082.7      63
  5093.1   63.43  5154.3   65.23  5191.3   65.09  5201.3    66.6  5212.9   65.16
  5235.8   65.17  5258.8    66.1  5272.1   65.68  5316.3   66.08  5337.7   65.55
#Mann= 4 ,-1 , 0
  4438.8     .08       0  4964.5     .05       0  4991.8     .04       0
  4997.8     .05       0
Bank Sta=4988.9,5009.7
XS Rating Curve= 0 ,0
Exp/Cntr=0.3,0.1

Type RM Length L Ch R = 1 ,24699   ,240,240,240
BEGIN DESCRIPTION:
UNT009 IN BACR 29.0
END DESCRIPTION:
XS GIS Cut Line= 4
      2431637.09     13125290.29      2431637.09      13125125.1
      2431627.91     13124946.15      2431939.96     13124707.52
#Sta/Elev= 30
  4543.1    65.5  4568.6   65.51  4666.5   65.27  4726.6   62.37  4766.6   58.49
  4776.6   57.43  4792.6   52.11  4803.7   51.07  4806.4   50.57  4809.7   51.07
  4816.7   52.87  4826.7   57.73  4836.7   58.99  4856.7   59.63  4866.7   61.13
    4894   60.73  4914.9   62.37  4964.7    56.4    4973   54.44  4979.2   53.45
  4993.8   53.58  5000.5   51.82  5022.8   53.94  5037.4   59.28  5072.7    61.2
    5079   60.59  5093.5   62.41  5172.4    64.7  5254.4   64.95  5280.3   65.26
#Mann= 6 ,-1 , 0
  4543.1     .08       0  4568.6      .1       0  4766.6     .05       0
  4803.7     .04       0  4809.7     .05       0  5254.4     .08       0
#XS Ineff= 2 , 0
         4912.25   61.96
Permanent Ineff=
       F       F
Bank Sta=4973,5022.8
XS Rating Curve= 0 ,0
Exp/Cntr=0.3,0.1

Type RM Length L Ch R = 1 ,24459   ,146,146,146
BEGIN DESCRIPTION:
Mapping XS d1a23fe2
END DESCRIPTION:
XS GIS Cut Line= 4
       2431834.4     13125285.68      2431866.52     13125074.63
      2431903.23     13124813.08      2431972.08     13124702.92
#Sta/Elev= 30
  4672.7    65.9  4705.1   65.63  4782.8   64.84  4823.2   65.63  4843.5   64.85
  4859.8   65.39  4887.2   64.32  4914.2   62.27  4944.5   62.31  4964.7   58.54
  4974.8   54.49  4984.9   52.09    4992   49.31  4994.8   48.81    4998   49.31
  5006.4   49.34  5015.2      51  5035.4   52.32  5065.7   51.97    5096   53.84
  5116.2   60.32  5126.3   61.52  5157.6    63.9  5181.2   64.67  5187.1   63.95
  5190.9    65.1  5202.4   66.85  5208.3   69.56  5216.6   64.56  5280.2   64.92
#Mann= 6 ,-1 , 0
  4672.7     .08       0  4705.1      .1       0  4887.2     .05       0
    4992     .04       0    4998     .05       0  5190.9     .08       0
Bank Sta=4984.9,5035.4
XS Rating Curve= 0 ,0
Exp/Cntr=0.3,0.1

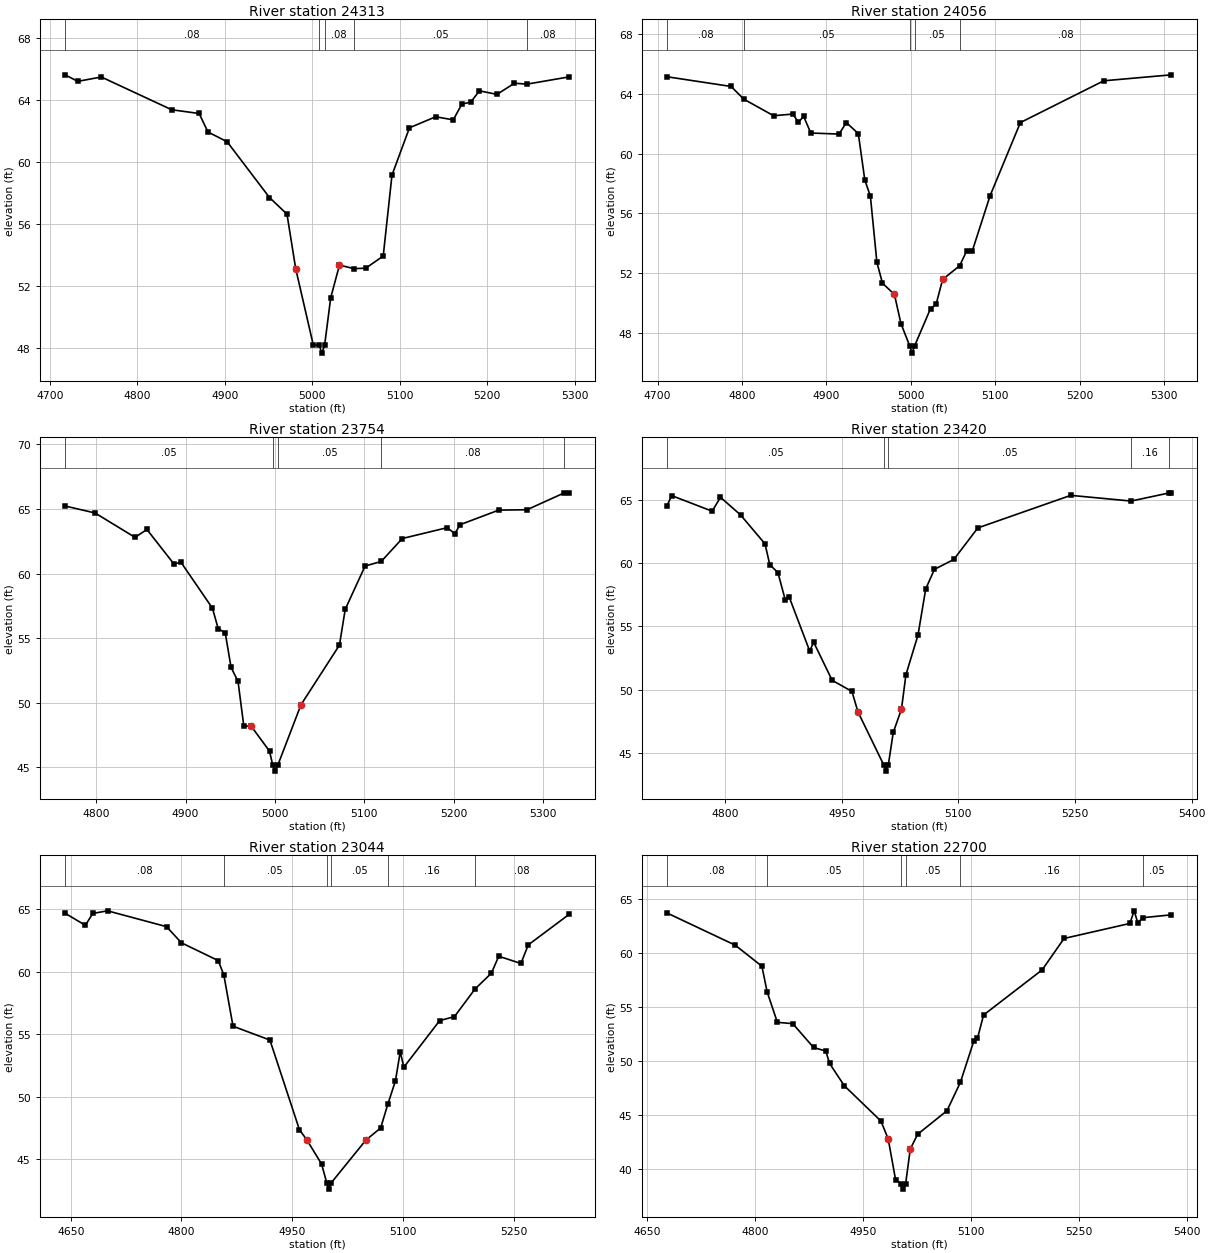
Type RM Length L Ch R = 1 ,24313   ,257,257,257
BEGIN DESCRIPTION:
UNT009 IN BACR 28.0
END DESCRIPTION:
XS GIS Cut Line= 3
      2431990.41     13125207.71      2432022.53     13125028.74
      2432022.53     13124634.17
#Sta/Elev= 30
  4717.3   65.62  4731.9    65.2  4758.8   65.48  4839.3   63.37  4870.6   63.13
  4880.7   61.94  4902.6   61.31    4951   57.72    4971   56.65    4981   53.13
    5001   48.24    5008    48.2  5010.8    47.7    5014    48.2    5021   51.27
    5031   53.37  5047.5   53.14    5061   53.17    5081   53.95    5091   59.16
    5111   62.21    5141   62.92    5161   62.72    5171   63.74    5181   63.86
    5191   64.59    5211   64.36    5231   65.08  5245.3   65.02  5293.7   65.49
#Mann= 5 ,-1 , 0
  4717.3     .08       0    5008     .07       0    5014     .08       0
  5047.5     .05       0  5245.3     .08       0
Bank Sta=4981,5031
XS Rating Curve= 0 ,0
Exp/Cntr=0.3,0.1

Type RM Length L Ch R = 1 ,24056   ,302,302,302
BEGIN DESCRIPTION:
Mapping XS 7c7a6236
END DESCRIPTION:
XS GIS Cut Line= 3
      2432091.36      13125207.7      2432210.66     13125042.51
      2432467.65     13124744.22
#Sta/Elev= 30
  4711.3   65.16  4787.2   64.51  4802.2   63.66  4837.5   62.55  4860.4   62.66
  4866.9   62.11  4873.1   62.51  4881.6   61.39  4915.1   61.32  4923.7   62.09
  4937.9   61.35  4945.6   58.24  4952.2   57.16  4959.9   52.73  4966.5   51.33
  4980.7   50.57  4988.4   48.62  4998.7   47.14  5001.5   46.64  5004.7   47.14
  5023.5   49.63  5030.1   49.92  5037.8   51.58  5057.9   52.49  5066.3   53.49
  5072.9   53.48  5094.1    57.2  5129.9   62.09  5228.7   64.89  5308.8   65.29
#Mann= 5 ,-1 , 0
  4711.3     .08       0  4802.2     .05       0  4998.7     .04       0
  5004.7     .05       0  5057.9     .08       0
Bank Sta=4980.7,5037.8
XS Rating Curve= 0 ,0
Exp/Cntr=0.3,0.1

Type RM Length L Ch R = 1 ,23754   ,334,334,334
BEGIN DESCRIPTION:
Mapping XS 4f38d716
END DESCRIPTION:
XS GIS Cut Line= 4
      2432187.71     13125391.24      2432288.67     13125340.76
      2432481.39     13125106.75       2432554.8     13124978.28
#Sta/Elev= 30
  4765.2   65.23  4798.8   64.69  4843.5    62.8  4856.8   63.41    4887   60.74
  4894.9   60.87  4930.1   57.31  4936.5   55.73  4944.4    55.4  4950.9   52.73
  4958.7   51.64  4965.2   48.16  4973.1    48.2  4993.9   46.24  4997.4   45.19
  5000.1   44.69  5003.4   45.19  5029.1   49.83  5072.1   54.45  5078.6   57.23
  5100.8   60.58  5118.8   60.93  5142.4   62.71  5192.6   63.55  5201.2   63.09
    5207   63.78  5250.2   64.91  5281.9   64.94  5323.7   66.25  5329.2   66.25
#Mann= 5 ,-1 , 0
  4765.2     .05       0  4997.4     .04       0  5003.4     .05       0
  5118.8     .08       0  5323.7     .05       0
Bank Sta=4973.1,5029.1
XS Rating Curve= 0 ,0
Exp/Cntr=0.3,0.1

Type RM Length L Ch R = 1 ,23420   ,376,376,376
BEGIN DESCRIPTION:
UNT009 IN BACR 27.0
END DESCRIPTION:
XS GIS Cut Line= 4
      2432582.34     13125551.84      2432651.17     13125349.94
      2432724.58     13125143.46      2432738.35     13124927.76
#Sta/Elev= 30
  4725.3   64.53  4731.2   65.32  4783.3   64.09    4794   65.19  4819.9   63.79
  4851.3   61.51  4857.4   59.87  4867.9   59.24  4877.3   57.09  4882.6   57.28
  4908.7   53.06  4913.9   53.74  4937.6   50.74  4963.1   49.86  4970.8   48.25
  5003.9   44.07  5006.7   43.57  5009.9   44.07  5016.2   46.62  5026.8   48.47
  5032.5   51.18    5048    54.3    5058   57.96  5069.2    59.5  5094.1   60.28
    5125   62.77  5244.5   65.34  5322.1   64.89    5371   65.53  5373.9   65.54
#Mann= 5 ,-1 , 0
  4725.3     .05       0  5003.9     .04       0  5009.9     .05       0
  5322.1     .16       0    5371     .05       0
Bank Sta=4970.8,5026.8
XS Rating Curve= 0 ,0
Exp/Cntr=0.3,0.1

Type RM Length L Ch R = 1 ,23044   ,344,344,344
BEGIN DESCRIPTION:
UNT009 IN BACR 26.0
END DESCRIPTION:
XS GIS Cut Line= 2
      2433036.61     13125634.44      2433045.77      13124951.3
#Sta/Elev= 30
  4642.3    64.7  4669.9   63.73  4679.9   64.68  4699.9   64.89  4779.9   63.62
  4799.9   62.33  4849.9    60.9  4857.5   59.74  4869.9   55.64  4919.9   54.53
  4959.9   47.34  4969.9   46.53  4989.9   44.59  4996.9   43.08  4999.7   42.58
  5002.9   43.08  5049.9   46.51  5069.9   47.48  5079.6   49.38  5089.9   51.25
  5096.4   53.58  5101.4   52.36  5149.9   56.09  5169.9   56.41  5197.7   58.62
  5219.9   59.89  5229.9   61.25  5259.9   60.67  5269.9   62.16  5325.5   64.62
#Mann= 6 ,-1 , 0
  4642.3     .08       0  4857.5     .05       0  4996.9     .04       0
  5002.9     .05       0  5079.6     .16       0  5197.7     .08       0
Bank Sta=4969.9,5049.9
XS Rating Curve= 0 ,0
Exp/Cntr=0.3,0.1

Type RM Length L Ch R = 1 ,22700   ,357,357,357
BEGIN DESCRIPTION:
UNT009 IN BACR 25.0
END DESCRIPTION:
XS GIS Cut Line= 4
      2433224.73     13125643.62      2433330.27     13125464.66
      2433380.75      13125207.7      2433421.72     13124980.09
#Sta/Elev= 30
  4677.7   63.69  4772.4   60.71  4809.5   58.76  4816.8   56.38    4831   53.56
  4852.4   53.44  4881.3   51.23  4898.3    50.9  4903.6   49.75    4924   47.69
  4974.9   44.42  4985.1   42.75  4995.3   38.98  5003.3   38.61    5006   38.11
  5009.3   38.61  5015.7   41.81  5025.9   43.19  5066.7   45.37  5085.4   48.01
    5104   51.82  5109.1   52.07  5117.6   54.24    5199   58.42  5229.5   61.33
  5320.9   62.72  5326.9   63.89    5332   62.76  5338.6   63.25  5378.6   63.52
#Mann= 6 ,-1 , 0
  4677.7     .08       0  4816.8     .05       0  5003.3     .04       0
  5009.3     .05       0  5085.4     .16       0  5338.6     .05       0
Bank Sta=4985.1,5015.7
XS Rating Curve= 0 ,0
Exp/Cntr=0.3,0.1

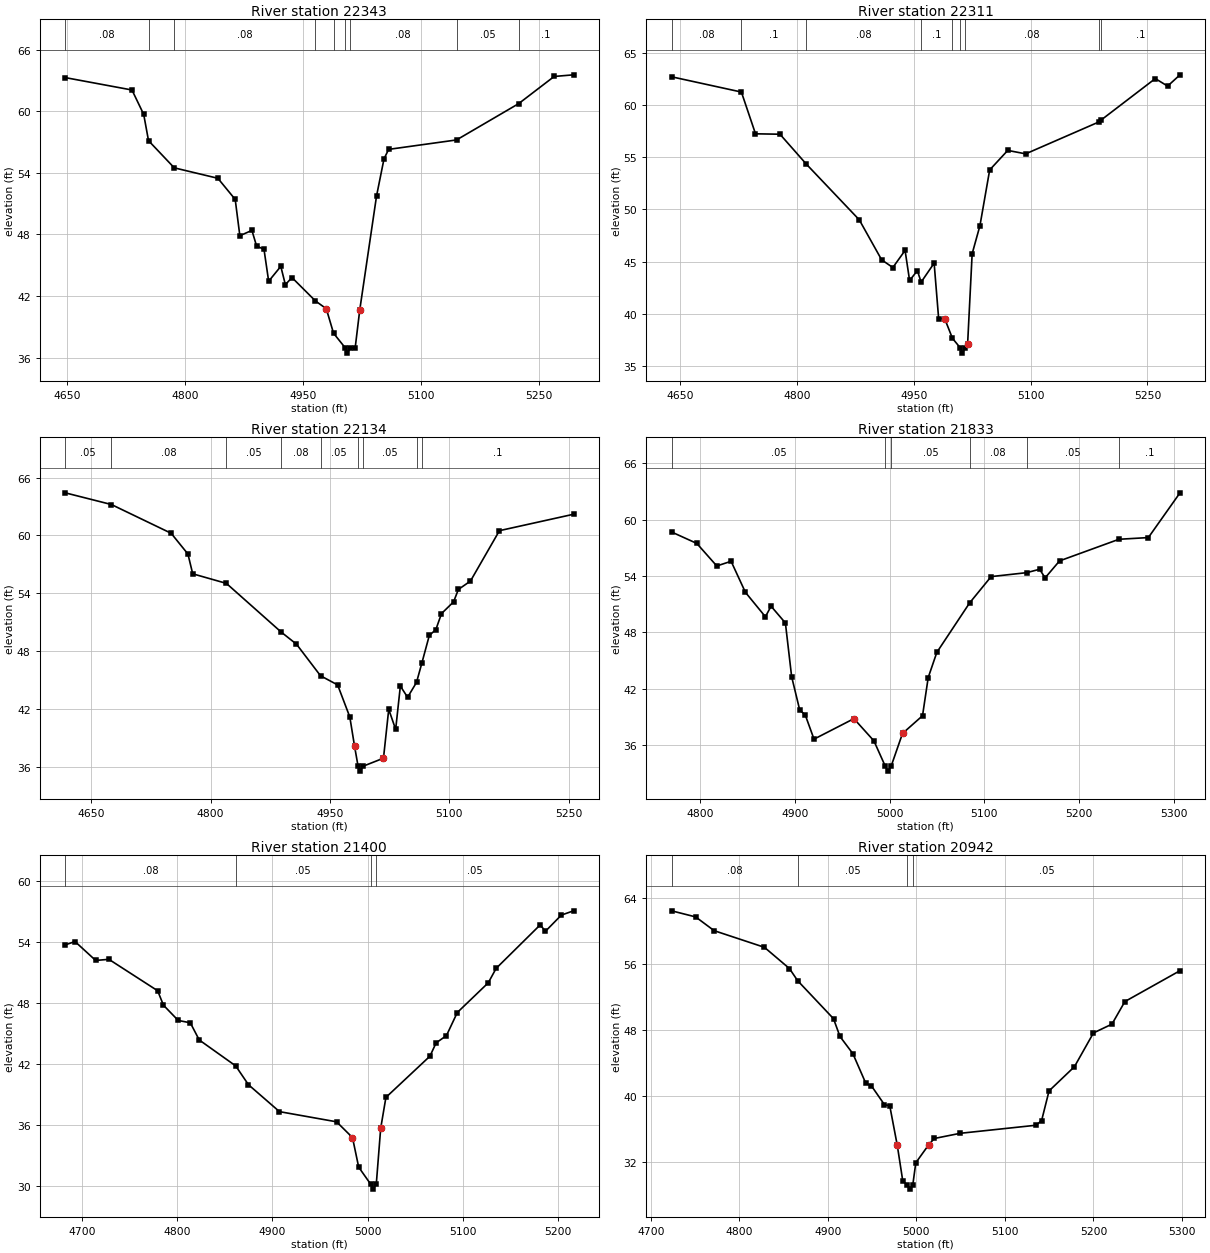
Type RM Length L Ch R = 1 ,22343   ,32,32,32
BEGIN DESCRIPTION:
UNT009 IN BACR 24.0
END DESCRIPTION:
XS GIS Cut Line= 2
      2433372.95     13125687.93      2433921.59     13125347.64
#Sta/Elev= 30
  4647.8    63.3  4732.6   62.09  4747.5   59.71  4753.6   57.15  4786.3    54.5
  4841.7   53.48  4863.7   51.42  4869.6   47.88  4884.9    48.4  4890.8   46.89
  4900.3   46.54  4906.2   43.44  4921.6   44.89  4927.4   43.11  4935.8    43.8
  4965.6   41.52  4979.4   40.76  4988.6   38.37  5003.6   36.93  5006.3   36.43
  5009.6   36.93  5016.1   36.96  5021.9   40.65  5043.2   51.75  5052.7   55.38
  5058.6    56.3  5144.8   57.22  5223.7   60.76  5268.8   63.41  5293.4   63.57
#Mann= 9 ,-1 , 0
  4647.8     .08       0  4753.6      .1       0  4786.3     .08       0
  4965.6     .05       0  4988.6     .08       0  5003.6     .07       0
  5009.6     .08       0  5144.8     .05       0  5223.7      .1       0
Bank Sta=4979.4,5021.9
XS Rating Curve= 0 ,0
Exp/Cntr=0.3,0.1

Type RM Length L Ch R = 1 ,22311   ,177,177,177
BEGIN DESCRIPTION:
Mapping XS 5ff33551
END DESCRIPTION:
XS GIS Cut Line= 2
       2433384.7     13125702.96      2433948.95     13125375.26
#Sta/Elev= 30
  4639.3   62.71  4728.8   61.25  4746.9   57.25  4778.3   57.21  4812.1   54.35
  4880.1   49.01  4908.8   45.18  4923.2   44.44  4938.9   46.08  4944.7    43.2
  4954.7   44.14  4959.5   43.04  4976.2   44.86    4982   39.54  4989.7   39.55
  4999.7   37.66  5009.8   36.74  5012.6   36.24  5015.8   36.74  5019.2   37.15
    5025   45.76    5035   48.45  5047.5   53.79  5070.7   55.66  5093.7   55.33
  5187.2   58.37  5190.2   58.55  5260.1   62.54  5275.9   61.82  5291.8    62.9
#Mann= 9 ,-1 , 0
  4639.3     .08       0  4728.8      .1       0  4812.1     .08       0
  4959.5      .1       0  4999.7     .08       0  5009.8     .07       0
  5015.8     .08       0  5187.2     .05       0  5190.2      .1       0
Bank Sta=4989.7,5019.2
XS Rating Curve= 0 ,0
Exp/Cntr=0.3,0.1

Type RM Length L Ch R = 1 ,22134   ,301,301,301
BEGIN DESCRIPTION:
Mapping XS b05917c7
END DESCRIPTION:
XS GIS Cut Line= 2
      2433484.47     13125865.76      2434023.76     13125523.55
#Sta/Elev= 30
  4617.4   64.42  4675.4   63.21  4750.5   60.23  4771.6   58.08  4777.6   56.03
  4819.9   55.04    4889   49.98    4908   48.74  4938.2   45.47  4959.7   44.52
    4975    41.2  4980.9    38.2  4985.4   36.09  4988.1   35.59  4991.4   36.09
  5017.3   36.93  5023.9   41.99  5032.6   39.91  5038.5    44.4  5047.6   43.24
  5058.8   44.78  5065.5   46.78  5074.9   49.65  5083.1   50.25  5090.2   51.91
  5105.4   53.13  5111.4   54.41  5126.6   55.28    5163    60.5  5256.1    62.2
#Mann= 9 ,-1 , 0
  4617.4     .05       0  4675.4     .08       0  4819.9     .05       0
    4889     .08       0  4938.2     .05       0  4985.4     .04       0
  4991.4     .05       0  5058.8     .08       0  5065.5      .1       0
Bank Sta=4980.9,5017.3
XS Rating Curve= 0 ,0
Exp/Cntr=0.3,0.1

Type RM Length L Ch R = 1 ,21833   ,433,433,433
BEGIN DESCRIPTION:
UNT009 IN BACR 23.0
END DESCRIPTION:
XS GIS Cut Line= 3
      2433781.78      13126037.2      2434089.97     13125835.35
      2434181.14     13125694.26
#Sta/Elev= 30
    4770   58.67  4796.5   57.46  4817.6   55.06  4832.7   55.56  4847.8   52.26
  4868.9   49.66  4874.9   50.78    4890      49  4896.6   43.28  4905.1   39.75
    4911    39.2  4920.2   36.64  4962.3   38.82  4983.4   36.46  4995.5   33.74
  4998.3   33.24  5001.5   33.74  5013.6   37.25  5034.7   39.13  5040.7   43.19
  5049.8   45.87  5084.4   51.13  5107.1   53.93  5144.7   54.35  5158.2   54.71
  5164.1    53.8  5179.3    55.6    5242    57.9    5273   58.08  5306.4   62.84
#Mann= 6 ,-1 , 0
    4770     .05       0  4995.5     .04       0  5001.5     .05       0
  5084.4     .08       0  5144.7     .05       0    5242      .1       0
Bank Sta=4962.3,5013.6
XS Rating Curve= 0 ,0
Exp/Cntr=0.3,0.1

Type RM Length L Ch R = 1 ,21400   ,458,458,458
BEGIN DESCRIPTION:
UNT009 IN BACR 22.0
END DESCRIPTION:
XS GIS Cut Line= 3
      2433917.65     13126419.06      2434032.33     13126354.84
      2434399.44     13126189.64
#Sta/Elev= 30
  4682.4   53.72  4692.7   54.05  4714.4   52.19  4728.3    52.3  4779.5   49.21
  4785.6   47.79  4801.1   46.29  4813.8   46.06  4823.2   44.37  4861.5   41.82
  4874.9   39.97  4907.5   37.32  4967.5   36.32  4984.2   34.77  4990.7   31.86
  5003.2    30.2  5005.9    29.7  5009.2    30.2  5013.8   35.67  5019.3   38.72
  5065.6   42.78    5072   44.08  5082.9    44.8  5094.3   47.07  5126.8   49.99
  5135.1   51.41  5181.4   55.69  5186.9   55.06  5203.6   56.65  5216.4   57.07
#Mann= 4 ,-1 , 0
  4682.4     .08       0  4861.5     .05       0  5003.2     .04       0
  5009.2     .05       0
Bank Sta=4984.2,5013.8
XS Rating Curve= 0 ,0
Exp/Cntr=0.3,0.1

Type RM Length L Ch R = 1 ,20942   ,464,464,464
BEGIN DESCRIPTION:
UNT009 IN BACR 21.0
END DESCRIPTION:
XS GIS Cut Line= 3
      2434257.15     13126864.19      2434371.88     13126758.63
      2434618.63     13126420.49
#Sta/Elev= 30
  4723.4    62.5  4750.5   61.76  4771.4   60.09  4828.2   58.07  4856.5   55.49
  4865.8   54.01  4906.3    49.4  4913.6   47.24  4928.2   45.15  4942.9   41.53
  4949.1   41.25  4963.8   38.97  4969.9   38.81  4978.4      34  4984.6   29.68
  4989.9    29.2  4992.7    28.7  4995.9    29.2  4999.3    31.9    5014    34.1
  5020.2   34.85  5049.5   35.48  5135.2   36.46  5141.5   37.03  5149.9   40.63
  5178.6   43.57  5200.1   47.67    5221   48.74  5235.6   51.48  5297.9   55.23
#Mann= 4 ,-1 , 0
  4723.4     .08       0  4865.8     .05       0  4989.9     .04       0
  4995.9     .05       0
Bank Sta=4978.4,5014
XS Rating Curve= 0 ,0
Exp/Cntr=0.3,0.1

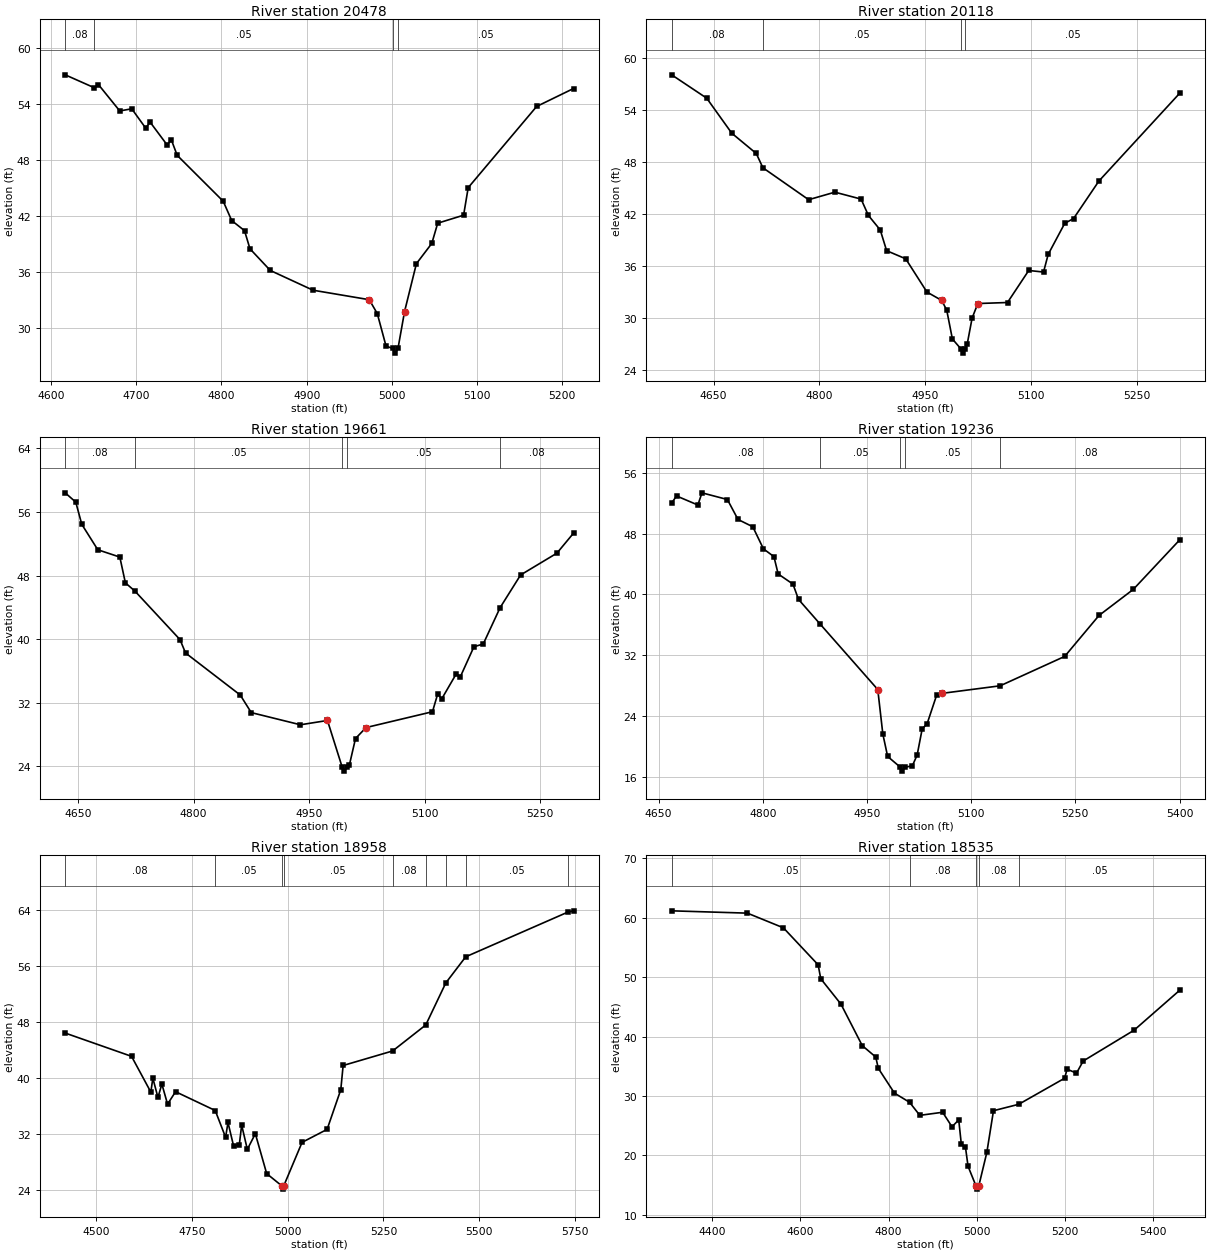
Type RM Length L Ch R = 1 ,20478   ,360,360,360
BEGIN DESCRIPTION:
UNT009 IN BACR 20.0
END DESCRIPTION:
XS GIS Cut Line= 2
      2434749.71     13127120.03      2434957.73     13126560.98
#Sta/Elev= 30
  4616.7   57.16  4650.9   55.77  4655.7   56.11  4680.7   53.28  4694.8   53.51
  4711.1   51.44  4716.4   52.07  4736.1   49.65  4741.4   50.14  4748.1   48.51
  4802.1   43.58  4812.1    41.5  4827.1   40.42  4833.5   38.47  4857.4   36.14
  4907.5   34.02  4973.5      33  4982.9   31.51  4993.2   28.01  5001.2   27.76
    5004   27.26  5007.2   27.76  5014.9   31.72  5028.8   36.87  5046.9   39.05
  5053.8   41.22  5084.2   42.08  5089.6   45.04  5169.9   53.76  5213.2   55.69
#Mann= 4 ,-1 , 0
  4616.7     .08       0  4650.9     .05       0  5001.2     .04       0
  5007.2     .05       0
Bank Sta=4973.5,5014.9
XS Rating Curve= 0 ,0
Exp/Cntr=0.3,0.1

Type RM Length L Ch R = 1 ,20118   ,457,457,457
BEGIN DESCRIPTION:
UNT009 IN BACR 19.0
END DESCRIPTION:
XS GIS Cut Line= 3
      2435005.09     13127240.45      2435147.35     13126997.24
      2435389.99     13126630.98
#Sta/Elev= 30
  4590.5   58.11  4640.2   55.41  4675.8   51.36  4710.5   49.02  4719.9   47.37
  4784.8   43.68    4822   44.55  4859.2   43.75  4869.6   41.86  4886.4   40.18
  4895.4   37.79  4922.5   36.85  4952.6   33.01  4973.6   32.04  4980.7   30.91
  4988.7   27.59  5000.7   26.45  5003.5   25.95  5006.7   26.45  5009.7   26.98
  5016.7      30  5024.8   31.68  5066.9    31.8    5097    35.5    5118   35.32
  5124.6   37.36  5148.1   40.95  5160.6    41.5  5196.6   45.84  5311.6   56.02
#Mann= 4 ,-1 , 0
  4590.5     .08       0  4719.9     .05       0  5000.7     .04       0
  5006.7     .05       0
Bank Sta=4973.6,5024.8
XS Rating Curve= 0 ,0
Exp/Cntr=0.3,0.1

Type RM Length L Ch R = 1 ,19661   ,425,425,425
BEGIN DESCRIPTION:
UNT009 IN BACR 18.0
END DESCRIPTION:
XS GIS Cut Line= 3
      2435237.72     13127446.86      2435537.72     13127196.85
      2435787.75     13127096.85
#Sta/Elev= 30
  4633.3   58.41    4647   57.24  4654.8   54.45  4675.6   51.25  4704.2   50.33
  4711.4   47.09  4723.9   46.04  4782.3   39.95  4789.5   38.27  4860.5   32.98
  4874.8   30.77  4938.6   29.24  4973.7   29.78  4992.8   23.91  4995.6   23.41
  4998.8   23.91  5002.3   24.24  5010.1   27.51  5023.8   28.89    5110   30.88
  5116.7   33.09  5122.1   32.51  5140.9   35.65  5146.3    35.3  5163.8   39.05
  5175.9    39.4  5197.8   43.97  5224.4   48.08  5271.5   50.82  5293.1   53.34
#Mann= 5 ,-1 , 0
  4633.3     .08       0  4723.9     .05       0  4992.8     .04       0
  4998.8     .05       0  5197.8     .08       0
Bank Sta=4973.7,5023.8
XS Rating Curve= 0 ,0
Exp/Cntr=0.3,0.1

Type RM Length L Ch R = 1 ,19236   ,278,278,278
BEGIN DESCRIPTION:
UNT009 IN BACR 17.0
END DESCRIPTION:
XS GIS Cut Line= 3
      2435492.73     13127753.03      2435690.67     13127629.75
      2436032.67     13127266.91
#Sta/Elev= 30
  4668.9   52.01  4675.9   52.94  4706.6   51.75  4712.5   53.35  4749.1   52.47
  4764.4   49.85  4785.7   48.89    4801   45.99  4816.1   44.97  4822.2   42.69
  4843.5   41.36  4851.5   39.35    4883   36.07  4965.6   27.51  4972.9   21.66
  4979.8   18.72  4998.3   17.29    5001   16.79  5004.3   17.29  5015.4   17.49
  5022.3   18.91  5029.6   22.36  5036.5   22.98  5050.6   26.84  5057.5      27
  5141.8      28  5234.7   31.86  5284.1   37.24  5333.4   40.66  5400.7   47.21
#Mann= 5 ,-1 , 0
  4668.9     .08       0    4883     .05       0  4998.3     .04       0
  5004.3     .05       0  5141.8     .08       0
Bank Sta=4965.6,5057.5
XS Rating Curve= 0 ,0
Exp/Cntr=0.3,0.1

Type RM Length L Ch R = 1 ,18958   ,423,423,423
BEGIN DESCRIPTION:
UNT009 IN BACR 16.0
END DESCRIPTION:
XS GIS Cut Line= 5
      2435353.87     13128084.72      2435583.26     13128006.72
      2436032.94     13127690.11       2436372.5     13127442.33
       2436459.7     13127368.89
#Sta/Elev= 30
  4419.6   46.42  4592.7   43.09  4643.1   37.97  4648.3   39.97  4661.6   37.21
  4671.9   39.12  4686.7   36.25  4707.6   38.03  4811.1   35.34  4838.2    31.5
  4844.4   33.63  4859.2   30.22    4874   30.47  4880.1   33.25  4894.9   29.78
  4915.8   32.02  4945.4   26.31  4984.2   24.59    4987   24.09  4990.2   24.59
  5037.7   30.78  5103.1   32.64  5138.8   38.32  5144.9   41.78  5274.1   43.86
  5360.6   47.58  5412.8   53.59  5464.8   57.33  5731.1   63.72  5746.2   63.91
#Mann= 9 ,-1 , 0
  4419.6     .08       0  4811.1     .05       0  4984.2     .04       0
  4990.2     .05       0  5274.1     .08       0  5360.6     .05       0
  5412.8     .08       0  5464.8     .05       0  5731.1      .1       0
Bank Sta=4984.2,4990.2
XS Rating Curve= 0 ,0
Exp/Cntr=0.3,0.1

Type RM Length L Ch R = 1 ,18535   ,407,407,407
BEGIN DESCRIPTION:
Mapping XS d1834932
END DESCRIPTION:
XS GIS Cut Line= 2
      2435622.23     13128419.53      2436598.82     13127804.93
#Sta/Elev= 30
  4307.6   61.16  4479.5   60.77  4561.2    58.3  4640.1   52.07    4646   49.73
  4691.9   45.45  4740.2   38.47  4770.8   36.55  4776.7   34.64  4813.2   30.48
  4847.6   28.93  4870.9   26.73  4922.7   27.25  4943.9   24.81  4959.2   25.96
  4965.1   21.87  4974.5   21.37  4980.4   18.15  4998.6   14.81  5001.3   14.31
  5004.6   14.81    5023   20.48  5038.1   27.51  5095.4   28.59  5199.4   32.97
  5205.3    34.5  5226.5   33.83  5241.8   35.88  5357.2   41.06  5461.5   47.83
#Mann= 5 ,-1 , 0
  4307.6     .05       0  4847.6     .08       0  4998.6     .07       0
  5004.6     .08       0  5095.4     .05       0
Bank Sta=4998.6,5004.6
XS Rating Curve= 0 ,0
Exp/Cntr=0.3,0.1

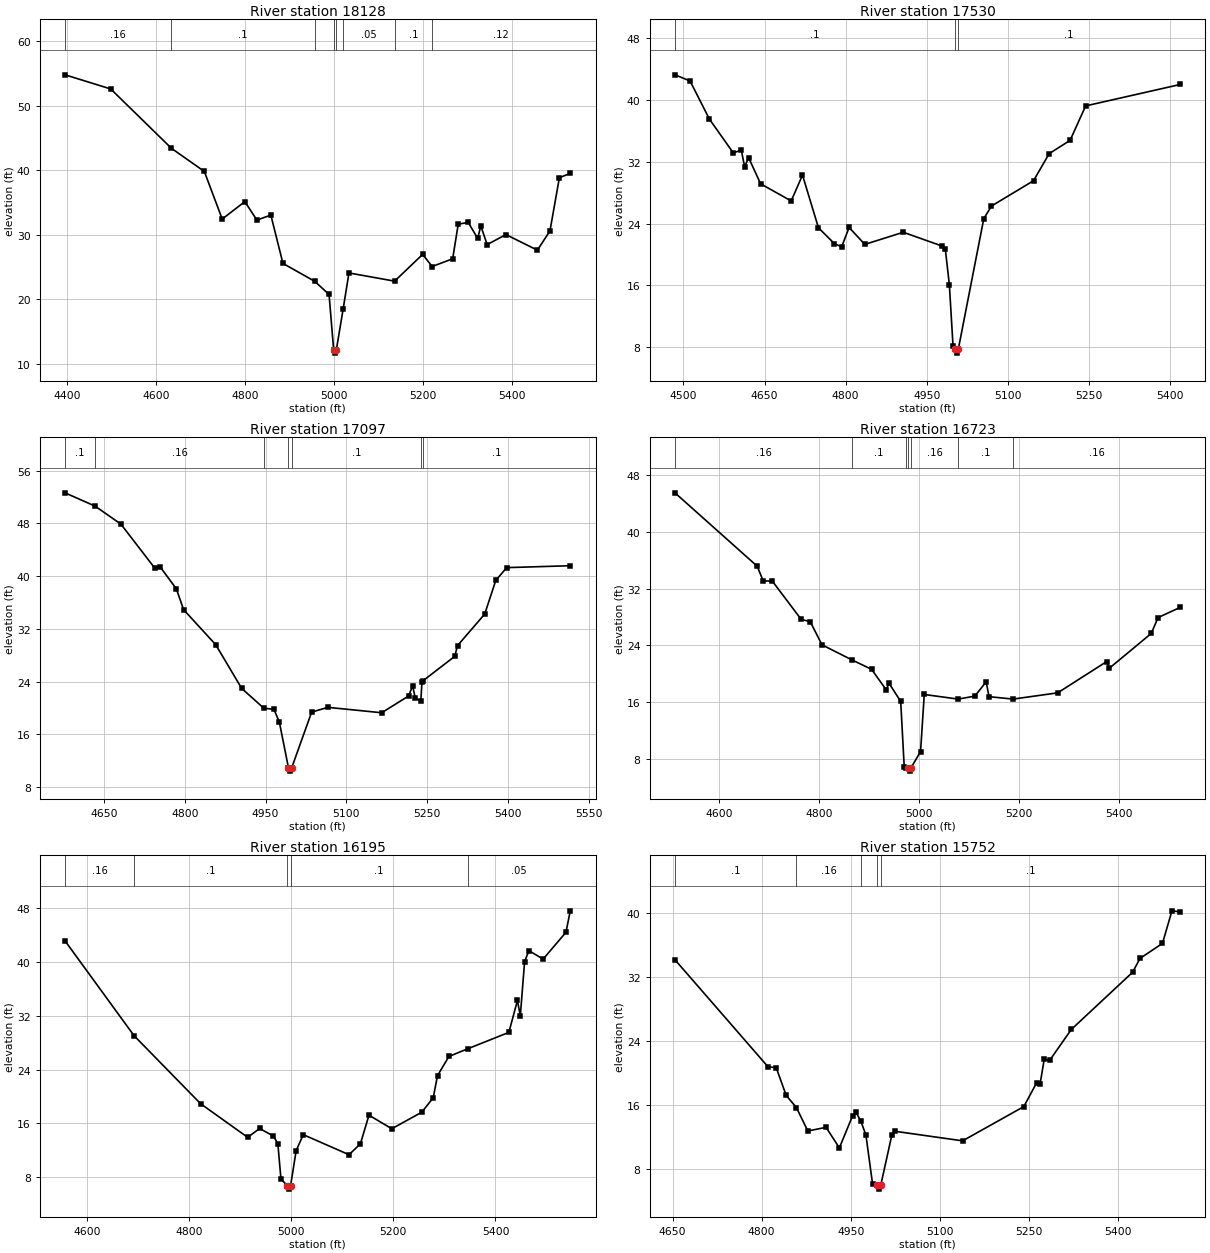
Type RM Length L Ch R = 1 ,18128   ,598,598,598
BEGIN DESCRIPTION:
UNT009 IN BACR 14.0
END DESCRIPTION:
XS GIS Cut Line= 4
      2435936.58     13128483.94      2436308.26     13128438.05
      2436753.35      13128176.5      2436927.69     13128002.16
#Sta/Elev= 30
  4394.9   54.79  4497.7    52.6  4634.5   43.39  4708.4   39.81  4748.7   32.43
  4799.6   35.13  4826.8   32.27  4858.2   33.04  4885.4   25.55  4956.8   22.78
  4989.2   20.74  4999.6   12.14  5002.4   11.64  5005.6   12.14  5021.1   18.55
    5034   24.07  5136.8    22.8  5199.9   26.95  5221.3   25.07  5267.5   26.27
    5280   31.64  5302.6    31.9  5323.8   29.43  5330.9   31.36  5345.1   28.47
  5387.5   30.02  5458.2    27.6  5486.5   30.59  5507.7   38.84  5532.2   39.51
#Mann= 8 ,-1 , 0
  4394.9     .16       0  4634.5      .1       0  4956.8     .12       0
  4999.6     .07       0  5005.6     .12       0  5021.1     .05       0
  5136.8      .1       0  5221.3     .12       0
Bank Sta=4999.6,5005.6
XS Rating Curve= 0 ,0
Exp/Cntr=0.3,0.1

Type RM Length L Ch R = 1 ,17530   ,433,433,433
BEGIN DESCRIPTION:
UNT009 IN BACR 13.0
END DESCRIPTION:
XS GIS Cut Line= 4
      2436436.74     13128965.73      2436707.46     13128773.02
      2436969.01       13128539.      2437079.13     13128314.18
#Sta/Elev= 30
  4484.5   43.25  4512.4   42.46  4548.1   37.53  4592.3   33.15  4607.1   33.51
  4613.2   31.38  4620.7   32.52  4642.8   29.15  4699.3   26.93  4720.2   30.28
  4749.7   23.46  4779.2    21.4  4792.6      21  4806.3    23.5  4835.4   21.31
  4906.5   22.88  4977.5   21.11  4984.2   20.65  4991.6   16.09  4998.4    8.16
  5002.1    7.74  5004.9    7.24  5008.1    7.74  5055.2   24.63  5069.4   26.27
  5147.2   29.55    5176   33.05  5214.7   34.77  5243.5   39.23  5418.1      42
#Mann= 3 ,-1 , 0
  4484.5      .1       0  5002.1     .07       0  5008.1      .1       0
Bank Sta=5002.1,5008.1
XS Rating Curve= 0 ,0
Exp/Cntr=0.3,0.1

Type RM Length L Ch R = 1 ,17097   ,374,374,374
BEGIN DESCRIPTION:
UNT009 IN BACR 12.0
END DESCRIPTION:
XS GIS Cut Line= 4
      2437143.37     13129250.26      2437193.85     13128974.91
      2437203.03     13128594.06      2437157.41     13128320.34
#Sta/Elev= 30
  4577.5   52.63  4633.3   50.61  4681.2   47.89  4744.5   41.18  4753.8   41.44
  4784.3   38.07  4797.6   34.93  4857.4    29.6  4905.5   22.99  4946.7   19.98
  4965.5   19.81  4975.5   17.89  4992.5   10.94  4995.3   10.44  4998.5   10.94
  5035.5   19.38  5065.6   20.11  5165.6   19.29  5215.6   21.83  5223.1   23.36
  5228.1   21.48  5238.3   21.11  5240.5   23.97  5242.3   24.13  5301.3   27.84
  5306.5   29.47    5357   34.25  5377.5   39.34  5397.8   41.29  5515.9   41.58
#Mann= 7 ,-1 , 0
  4577.5      .1       0  4633.3     .16       0  4946.7      .1       0
  4992.5     .07       0  4998.5      .1       0  5238.3     .16       0
  5242.3      .1       0
Bank Sta=4992.5,4998.5
XS Rating Curve= 0 ,0
Exp/Cntr=0.3,0.1

Type RM Length L Ch R = 1 ,16723   ,528,528,528
BEGIN DESCRIPTION:
UNT009 IN BACR 11.0
END DESCRIPTION:
XS GIS Cut Line= 3
       2437344.5     13129317.91      2437573.65      13128786.7
      2437393.11     13128394.37
#Sta/Elev= 30
  4512.5    45.5    4677   35.15    4689   33.07  4707.1   33.06    4765   27.65
  4783.1   27.33  4806.6   24.06  4867.2   21.91  4905.7   20.61  4935.1   17.71
  4940.5   18.66    4964   16.08  4971.1    6.77    4974    6.76  4978.9    6.75
  4981.7    6.25  4984.9    6.75  5003.7       9  5011.1   17.06  5078.9   16.41
  5112.3   16.83  5134.9   18.84  5140.7   16.75  5188.8   16.41    5278   17.29
  5375.9    21.7  5381.4   20.77  5465.1   25.67  5478.8   27.91  5522.9   29.34
#Mann= 7 ,-1 , 0
  4512.5     .16       0  4867.2      .1       0    4974     .16       0
  4978.9     .07       0  4984.9     .16       0  5078.9      .1       0
  5188.8     .16       0
Bank Sta=4978.9,4984.9
XS Rating Curve= 0 ,0
Exp/Cntr=0.3,0.1

Type RM Length L Ch R = 1 ,16195   ,443,443,443
BEGIN DESCRIPTION:
UNT009 IN BACR 10.0
END DESCRIPTION:
XS GIS Cut Line= 3
      2437637.73     13129296.85      2437987.72     13129046.85
       2438487.7     13128796.86
#Sta/Elev= 30
  4557.3   43.13  4692.3   29.04  4822.7   18.91  4914.9   13.91  4938.2   15.23
  4965.3    14.1  4973.9   12.98    4980    7.71  4992.8    6.71  4995.5    6.21
  4998.8    6.71  5009.8   11.95  5023.7   14.31  5113.2   11.33  5135.5   12.94
  5152.3   17.21    5197   15.19  5255.7   17.65  5278.1    19.8  5286.5   23.09
  5308.8   25.94  5345.9   27.09  5426.2   29.52    5443   34.27  5448.6   31.97
    5457   40.03  5465.4   41.68  5493.3   40.42    5538   44.41  5546.4    47.6
#Mann= 5 ,-1 , 0
  4557.3     .16       0  4692.3      .1       0  4992.8     .07       0
  4998.8      .1       0  5345.9     .05       0
Bank Sta=4992.8,4998.8
XS Rating Curve= 0 ,0
Exp/Cntr=0.3,0.1

Type RM Length L Ch R = 1 ,15752   ,226,226,226
BEGIN DESCRIPTION:
UNT009 IN BACR 9.0
END DESCRIPTION:
XS GIS Cut Line= 3
      2437887.75     13129546.84      2438187.72     13129396.85
      2438437.74     13128946.82
#Sta/Elev= 30
  4654.1   34.15  4810.6   20.79  4824.6   20.66  4841.3    17.2  4858.6   15.68
  4877.7   12.76  4908.4   13.22  4930.8   10.65  4953.1   14.67  4958.7   15.09
  4966.8   14.03  4975.5   12.24  4986.7    6.13  4994.5       6  4997.2     5.5
  5000.5       6  5019.2   12.29  5024.9   12.72  5138.2   11.53  5241.2   15.81
  5262.9    18.8  5268.6   18.65  5275.5    21.7  5284.6   21.57  5321.2   25.45
  5424.2   32.58  5436.8   34.32  5474.5   36.19  5490.5   40.26  5504.3   40.13
#Mann= 5 ,-1 , 0
  4654.1      .1       0  4858.6     .16       0  4966.8      .1       0
  4994.5     .07       0  5000.5      .1       0
Bank Sta=4994.5,5000.5
XS Rating Curve= 0 ,0
Exp/Cntr=0.3,0.1