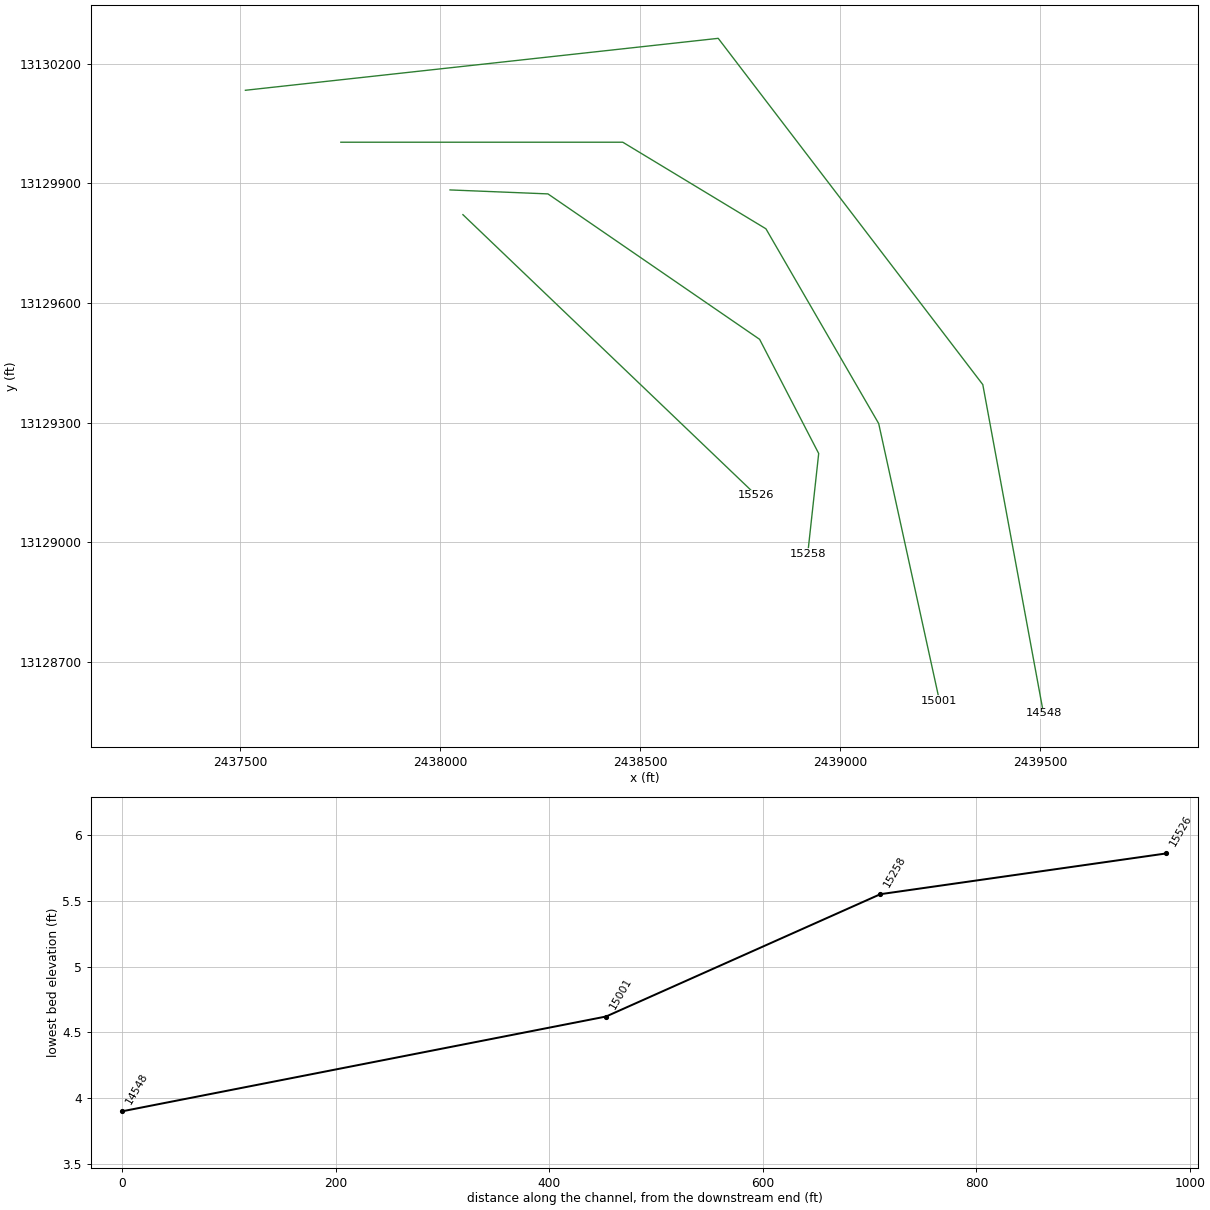
HEC-RAS study UNT009 IN BACR.prj: UNT009 IN BACR Base Level Engineering

--- UNT009 IN BACR.g01 (geometry) --- (continued)

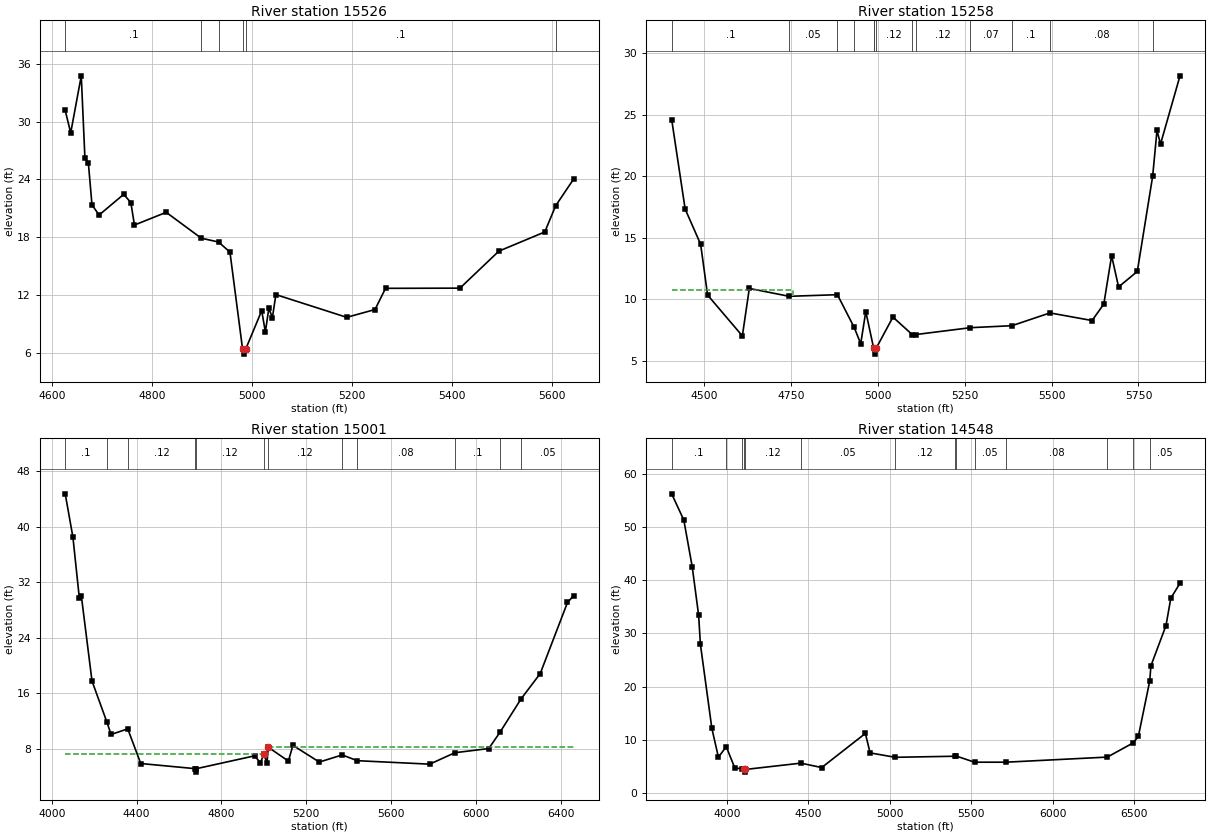
Type RM Length L Ch R = 1 ,15526   ,268,268,268
BEGIN DESCRIPTION:
Mapping XS f79124c4
END DESCRIPTION:
XS GIS Cut Line= 2
      2438056.73     13129821.41      2438790.26     13129118.27
#Sta/Elev= 30
  4626.3   31.16  4637.3   28.83  4658.4   34.75  4665.7   26.21  4672.6    25.7
  4679.8   21.36    4694    20.3  4743.3   22.45  4757.5   21.59  4764.7   19.26
  4828.2   20.58  4898.4   17.89  4932.8    17.5  4955.6   16.45  4980.9    6.36
  4983.7    5.86  4986.9    6.36  5019.1   10.37  5026.4    8.16  5033.3   10.61
  5040.5    9.66  5047.4   12.04    5189    9.68  5245.6   10.49  5266.6   12.69
  5415.4   12.71  5493.1   16.55  5584.9   18.54  5606.8   21.27  5642.4   24.02
#Mann= 6 ,-1 , 0
  4626.3      .1       0  4898.4     .05       0  4932.8      .1       0
  4980.9     .07       0  4986.9      .1       0  5606.8     .08       0
Bank Sta=4980.9,4986.9
XS Rating Curve= 0 ,0
Exp/Cntr=0.3,0.1

Type RM Length L Ch R = 1 ,15258   ,257,257,257
BEGIN DESCRIPTION:
Mapping XS 587e8815
END DESCRIPTION:
XS GIS Cut Line= 5
      2438024.42     13129883.45       2438269.4      13129873.5
      2438798.91     13129508.92      2438946.69      13129222.7
      2438919.24     13128971.08
#Sta/Elev= 30
  4406.3   24.62  4445.1   17.34  4489.7   14.48  4509.7   10.35  4609.8    7.03
  4629.8   10.89  4744.4   10.25  4883.4   10.38  4931.7    7.72  4950.5     6.4
  4965.1    9.01  4987.4    6.08  4989.4    6.05  4992.2    5.55  4995.4    6.05
  5043.2    8.56  5099.1    7.13  5108.8    7.14  5266.4     7.7  5385.7    7.86
  5495.3     8.9  5616.5    8.28  5650.3    9.62  5672.7   13.55  5692.8   11.01
  5746.7   12.27  5790.9   20.01  5803.4   23.74  5813.5   22.62  5869.6   28.17
#Mann= 13 ,-1 , 0
  4406.3      .1       0  4744.4     .05       0  4883.4     .12       0
  4931.7      .1       0  4987.4     .12       0  4989.4     .07       0
  4995.4     .12       0  5099.1      .1       0  5108.8     .12       0
  5266.4     .07       0  5385.7      .1       0  5495.3     .08       0
  5790.9     .05       0
#XS Ineff= 2 , 0
       0 4756.05   10.79               0
Permanent Ineff=
       T       F
Bank Sta=4989.4,4995.4
XS Rating Curve= 0 ,0
Exp/Cntr=0.3,0.1

Type RM Length L Ch R = 1 ,15001   ,453,453,453
BEGIN DESCRIPTION:
UNT009 IN BACR 8.0
END DESCRIPTION:
XS GIS Cut Line= 5
      2437751.31     13130003.06      2438456.61     13130003.06
      2438814.68     13129786.04       2439096.8     13129297.76
      2439248.71     13128603.31
#Sta/Elev= 30
  4062.7   44.75  4099.1    38.5  4129.1    29.8  4139.1   29.97  4189.1   17.76
  4259.7   11.81  4279.1   10.05  4357.8   10.86  4419.1    5.86  4676.1    5.12
  4678.9    4.62  4682.1    5.12  4956.4    6.97  4984.1    5.96  4999.6     7.2
  5014.9    5.96  5020.9    8.21  5115.9    6.21  5137.3    8.48  5261.8    6.07
  5369.9     7.1  5440.7    6.27  5782.9    5.77  5901.6    7.42  6061.4    8.02
  6113.8   10.34  6214.3    15.2  6304.3   18.83  6432.9   29.08  6461.5   30.05
#Mann= 12 ,-1 , 0
  4062.7      .1       0  4259.7     .08       0  4357.8     .12       0
  4676.1     .07       0  4682.1     .12       0  4999.6     .05       0
  5020.9     .12       0  5369.9     .07       0  5440.7     .08       0
  5901.6      .1       0  6113.8     .08       0  6214.3     .05       0
#XS Ineff= 2 , 0
       0 4999.53    7.21 5020.94       0    8.24
Permanent Ineff=
       T       T
Bank Sta=4999.6,5020.9
XS Rating Curve= 0 ,0
Exp/Cntr=0.3,0.1

Type RM Length L Ch R = 1 ,14548   ,0,0,0
BEGIN DESCRIPTION:
UNT009 IN BACR 1.0
END DESCRIPTION:
XS GIS Cut Line= 4
       2437512.6     13130133.27      2438695.33     13130263.47
      2439357.22     13129395.42      2439509.03     13128571.28
#Sta/Elev= 30
  3660.5   56.27    3735   51.33  3786.4   42.59    3826   33.41  3836.7   27.98
  3907.1   12.14  3947.3    6.71  3995.4    8.69    4048    4.68  4093.8    4.52
  4105.9     4.4  4108.7     3.9  4111.9     4.4  4453.2    5.59  4581.2    4.76
  4849.1   11.18  4878.3    7.52  5032.2    6.69  5397.2    6.89  5406.6    6.93
  5518.9    5.77  5712.2    5.77    6334    6.73  6494.3    9.43  6524.8   10.68
  6594.3   21.06  6601.5    23.9    6694   31.48  6723.5   36.61    6780   39.45
#Mann= 14 ,-1 , 0
  3660.5      .1       0  3995.4     .08       0  4093.8     .12       0
  4105.9     .03       0  4111.9     .12       0  4453.2     .05       0
  5032.2     .12       0  5397.2     .05       0  5406.6     .07       0
  5518.9     .05       0  5712.2     .08       0    6334      .1       0
  6494.3     .08       0  6594.3     .05       0
Bank Sta=4105.9,4111.9
XS Rating Curve= 0 ,0
Exp/Cntr=0.3,0.1

Chan Stop Cuts=-1
Use User Specified Reach Order=0
Composite Channel Slope=5