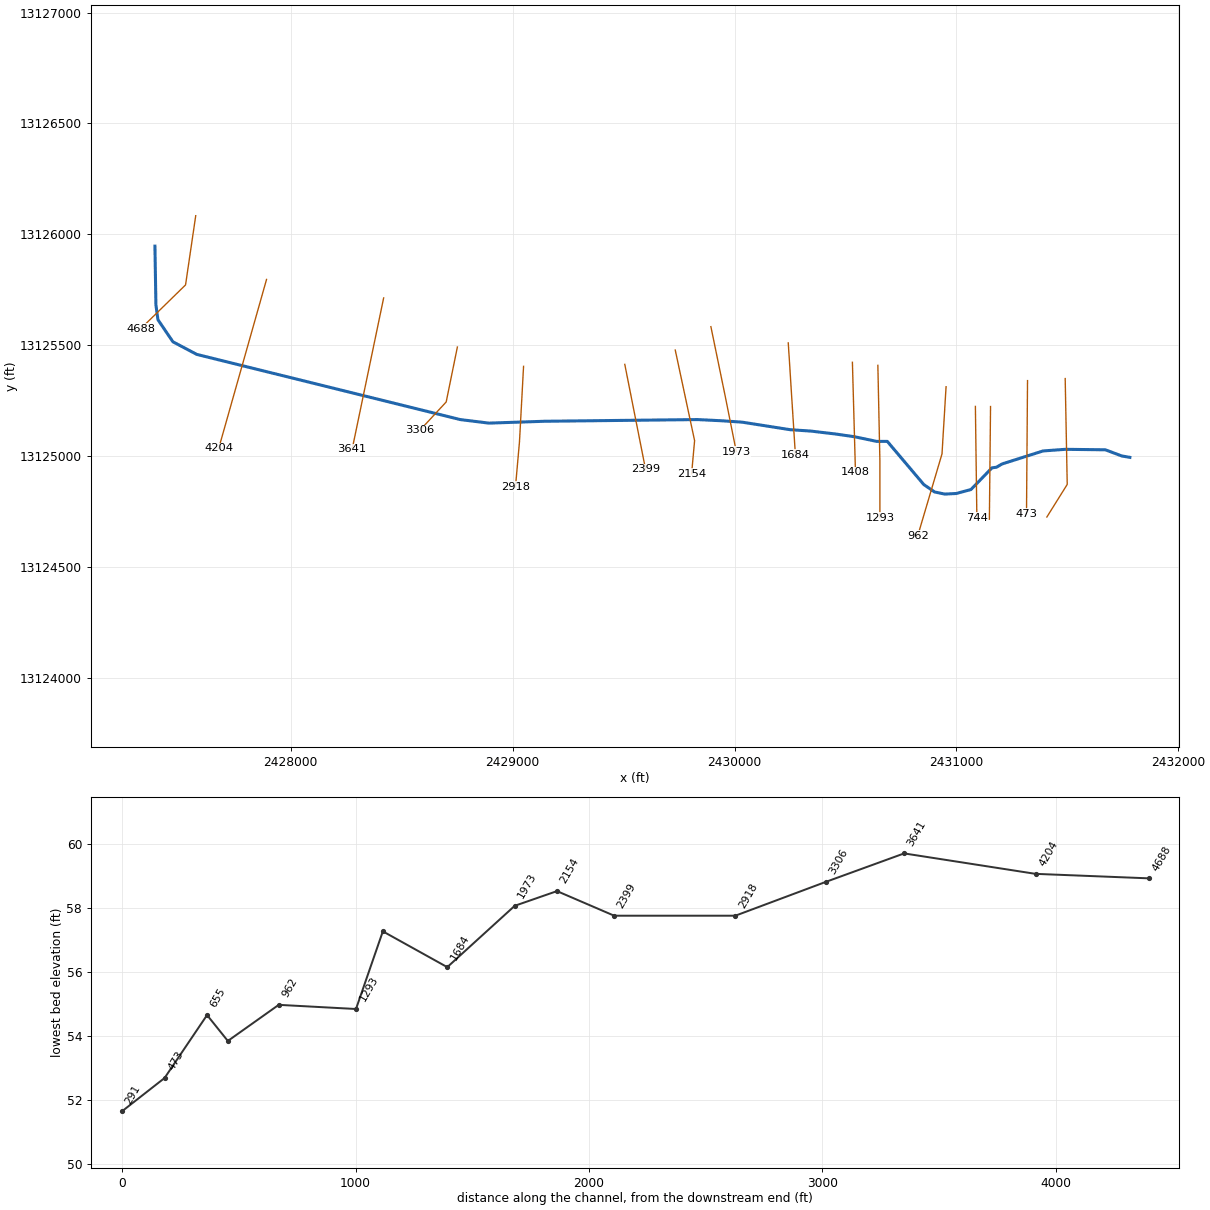
--- UNT010 IN BACR.prj (project) ---

Proj Title=UNT010 IN BACR Base Level Engineering
Current Plan=p01
Default Exp/Contr=0.3,0.1
English Units
Geom File=g01
Flow File=f01
Plan File=p01
BEGIN DESCRIPTION:
UNT010 IN BACR
END DESCRIPTION:

--- UNT010 IN BACR.p01 (plan) ---

Plan Title=Multiple Run
Short Identifier=Multiple
Geom File=g01
Flow File=f01
Subcritical Flow
K Sum by GR= 0
Std Step Tol= 0.01
Critical Tol= 0.01
Num of Std Step Trials= 20
Max Error Tol= 0.3
Flow Tol Ratio= 0.001
Split Flow NTrial= 30
Split Flow Tol= 0.02
Split Flow Ratio= 0.02
Log Output Level= 0
Friction Slope Method= 1
Unsteady Friction Slope Method= 2
Unsteady Bridges Friction Slope Method= 1
Parabolic Critical Depth
Global Vel Dist=  1 , 1 , 1
Global Log Level= 0
CheckData=True
Encroach Param= -1, 0, 0, 0
BEGIN DESCRIPTION:
Multiple Run
END DESCRIPTION:

--- UNT010 IN BACR.f01 (steady flow) ---

Flow Title=Multiple
Number of Profiles=7
Profile Names=10-year,25-year,50-year,1pct_min,100-year,1pct_plu,500-year
River Rch & RM= UNT010 IN BACR,Reach-1,4688
     212     273     320     275     371     502     504
Boundary for River Rch & Prof#=UNT010 IN BACR,Reach-1,1
Up Type=0
Dn Type=3
Dn Slope=0.005
Boundary for River Rch & Prof#=UNT010 IN BACR,Reach-1,2
Up Type=0
Dn Type=3
Dn Slope=0.005
Boundary for River Rch & Prof#=UNT010 IN BACR,Reach-1,3
Up Type=0
Dn Type=3
Dn Slope=0.005
Boundary for River Rch & Prof#=UNT010 IN BACR,Reach-1,4
Up Type=0
Dn Type=3
Dn Slope=0.005
Boundary for River Rch & Prof#=UNT010 IN BACR,Reach-1,5
Up Type=0
Dn Type=3
Dn Slope=0.005
Boundary for River Rch & Prof#=UNT010 IN BACR,Reach-1,6
Up Type=0
Dn Type=3
Dn Slope=0.005
Boundary for River Rch & Prof#=UNT010 IN BACR,Reach-1,7
Up Type=0
Dn Type=3
Dn Slope=0.005

--- UNT010 IN BACR.g01 (geometry) ---

Geom Title=Existing Conditions

River Reach=UNT010 IN BACR,Reach-1
Reach XY= 30
      2427387.72     13125946.85      2427392.16     13125681.78
      2427401.33     13125615.11      2427468.69     13125515.80
      2427576.33     13125458.86      2428763.83     13125165.11
      2428893.00     13125149.14      2429143.69     13125157.47
      2429833.27     13125165.11      2429941.87     13125159.73
      2430034.23     13125153.48      2430250.90     13125119.45
      2430344.65     13125113.20      2430455.76     13125100.00
      2430541.87     13125087.50      2430640.72     13125066.75
      2430688.54     13125066.74      2430852.98     13124872.23
      2430901.59     13124838.89      2430947.42     13124829.17
      2430999.51     13124831.95      2431065.59     13124849.73
      2431160.39     13124947.65      2431180.70     13124950.25
      2431205.18     13124964.84      2431390.49     13125023.70
      2431490.59     13125030.98      2431671.32     13125028.90
      2431745.40     13125001.01      2431781.76     13124994.79

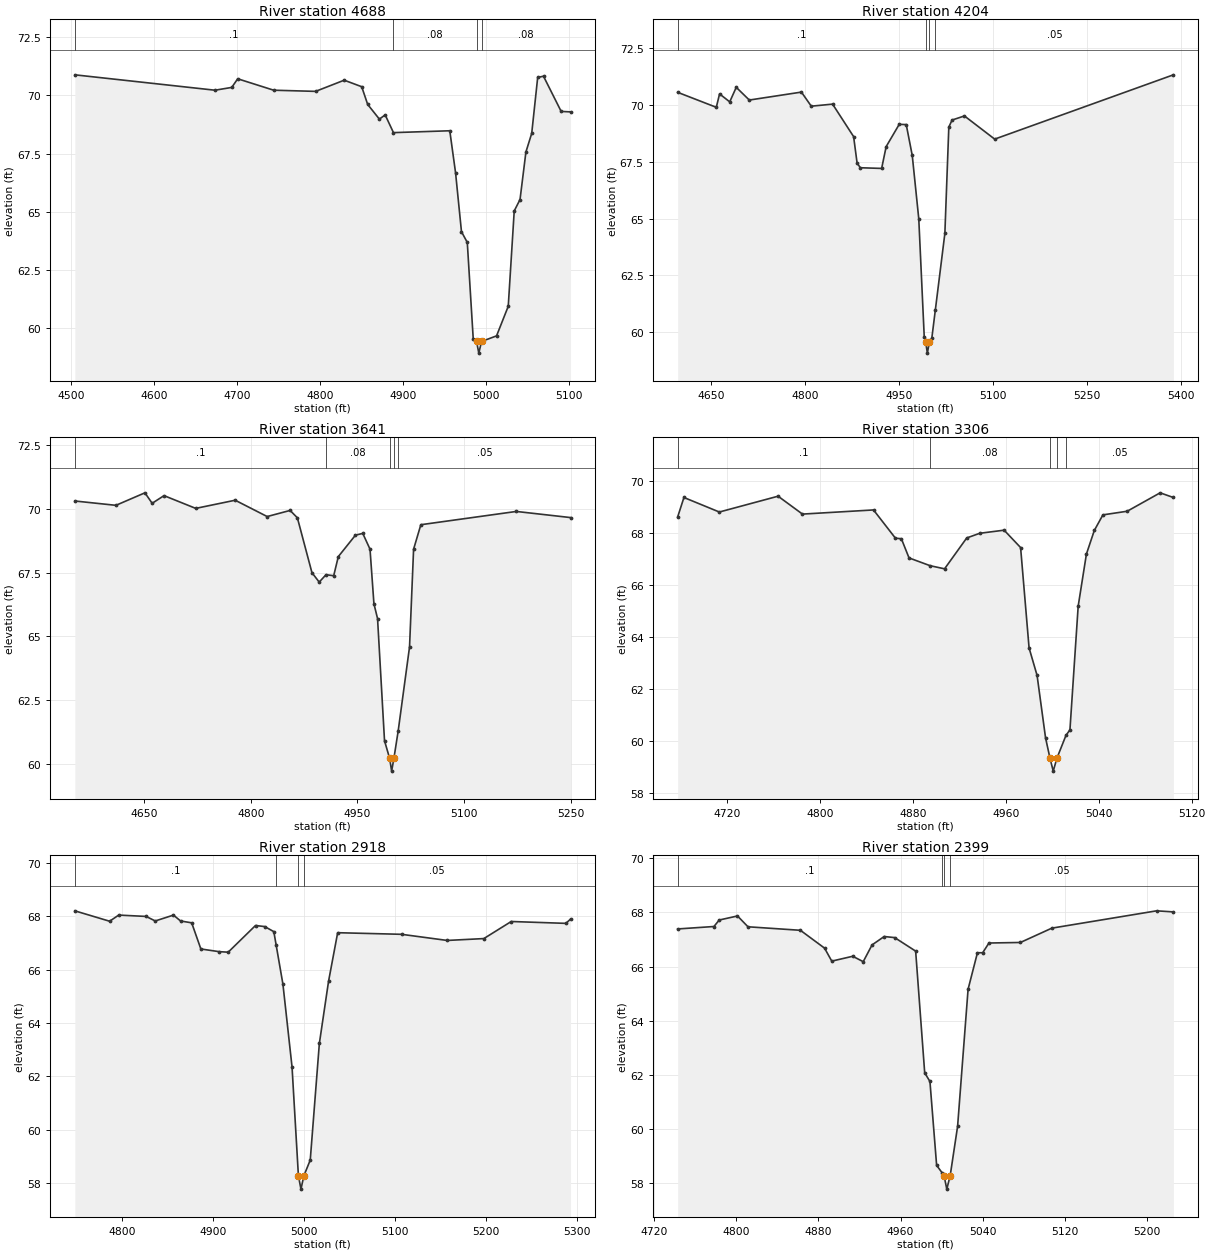
Type RM Length L Ch R = 1,4688,484,484,484
BEGIN DESCRIPTION:
UNT010 IN BACR 5.0
END DESCRIPTION:
XS GIS Cut Line= 3
      2427571.61     13126084.09      2427525.73     13125772.09
      2427323.80     13125574.75
#Sta/Elev= 30
  4504.7   70.88  4673.7   70.22  4693.9   70.34  4701.1   70.71  4744.5   70.22
  4795.0   70.17  4829.5   70.65  4850.6   70.37  4857.8   69.61  4871.9   68.98
  4878.9   69.16  4888.9   68.40  4956.8   68.48  4963.8   66.67  4970.9   64.15
  4977.9   63.69  4985.1   59.54  4989.1   59.44  4991.8   58.94  4995.1   59.44
  5013.2   59.68  5027.3   60.95  5034.5   65.04  5041.5   65.53  5048.6   67.57
  5055.6   68.37  5062.8   70.77  5069.8   70.82  5091.1   69.31  5102.4   69.29
#Mann=4,-1,0
  4504.7     0.1       0  4888.9    0.08       0  4989.1    0.07       0
  4995.1    0.08       0
Bank Sta=4989.1,4995.1
Exp/Cntr=0.3,0.1

Type RM Length L Ch R = 1,4204,563,563,563
BEGIN DESCRIPTION:
UNT010 IN BACR 4.0
END DESCRIPTION:
XS GIS Cut Line= 2
      2427890.76     13125796.73      2427675.49     13125036.32
#Sta/Elev= 30
  4597.0   70.56  4658.6   69.90  4663.8   70.49  4680.0   70.14  4690.4   70.78
  4711.2   70.22  4794.3   70.57  4810.0   69.95  4844.0   70.04  4877.5   68.61
  4883.1   67.44  4888.3   67.24  4922.2   67.21  4929.4   68.17  4950.2   69.15
  4961.4   69.14  4971.0   67.78  4981.4   64.99  4990.1   59.80  4992.3   59.58
  4995.1   59.08  4998.3   59.58  5002.2   59.74  5007.9   61.00  5023.0   64.35
  5029.3   69.03  5034.5   69.34  5054.2   69.52  5102.4   68.50  5387.3   71.33
#Mann=4,-1,0
  4597.0     0.1       0  4992.3    0.07       0  4998.3     0.1       0
  5007.9    0.05       0
Bank Sta=4992.3,4998.3
Exp/Cntr=0.3,0.1

Type RM Length L Ch R = 1,3641,335,335,335
BEGIN DESCRIPTION:
UNT010 IN BACR 3.0
END DESCRIPTION:
XS GIS Cut Line= 2
      2428418.55     13125713.41      2428276.45     13125030.64
#Sta/Elev= 30
  4552.5   70.31  4610.3   70.14  4651.1   70.63  4661.3   70.22  4678.0   70.52
  4722.6   70.02  4778.1   70.34  4823.1   69.70  4855.4   69.94  4865.6   69.65
  4886.1   67.50  4896.3   67.13  4905.9   67.42  4916.7   67.38  4923.2   68.13
  4947.3   68.97  4957.6   69.04  4967.8   68.42  4973.3   66.28  4978.4   65.70
  4988.2   60.91  4995.4   60.22  4998.2   59.72  5001.4   60.22  5007.5   61.31
  5023.4   64.59  5029.1   68.42  5039.3   69.38  5173.6   69.90  5249.9   69.66
#Mann=5,-1,0
  4552.5     0.1       0  4905.9    0.08       0  4995.4    0.07       0
  5001.4    0.08       0  5007.5    0.05       0
Bank Sta=4995.4,5001.4
Exp/Cntr=0.3,0.1

Type RM Length L Ch R = 1,3306,388,388,388
BEGIN DESCRIPTION:
Mapping XS bfffff7f
END DESCRIPTION:
XS GIS Cut Line= 3
      2428750.87     13125492.16      2428700.41     13125244.40
      2428581.90     13125116.78
#Sta/Elev= 30
  4677.2   68.63  4682.6   69.38  4713.1   68.82  4763.7   69.43  4784.7   68.74
  4845.9   68.90  4864.8   67.81  4869.9   67.79  4876.5   67.05  4894.7   66.75
  4907.1   66.63  4926.2   67.82  4937.4   68.00  4958.4   68.12  4972.6   67.45
  4979.9   63.58  4986.8   62.52  4994.1   60.11  4997.9   59.33  5000.7   58.83
  5003.9   59.33  5011.7   60.21  5015.1   60.42  5022.2   65.19  5029.3   67.20
  5036.1   68.11  5043.5   68.71  5064.4   68.85  5092.8   69.56  5104.2   69.38
#Mann=5,-1,0
  4677.2     0.1       0  4894.7    0.08       0  4997.9    0.07       0
  5003.9    0.08       0  5011.7    0.05       0
Bank Sta=4997.9,5003.9
Exp/Cntr=0.3,0.1

Type RM Length L Ch R = 1,2918,519,519,519
BEGIN DESCRIPTION:
UNT010 IN BACR 2.0
END DESCRIPTION:
XS GIS Cut Line= 3
      2429049.14     13125405.01      2429030.78     13125065.45
      2429012.70     13124862.01
#Sta/Elev= 30
  4748.5   68.20  4786.7   67.81  4796.7   68.04  4826.8   67.99  4836.8   67.82
  4856.8   68.04  4864.6   67.82  4876.8   67.75  4886.9   66.77  4906.9   66.67
  4916.9   66.65  4946.9   67.65  4957.0   67.61  4967.0   67.42  4969.6   66.91
  4977.0   65.45  4987.0   62.35  4994.0   58.27  4996.8   57.77  5000.0   58.27
  5007.0   58.86  5017.0   63.23  5027.1   65.56  5037.1   67.38  5107.2   67.32
  5157.4   67.09  5197.6   67.16  5227.7   67.80  5287.7   67.73  5292.8   67.89
#Mann=4,-1,0
  4748.5     0.1       0  4969.6    0.05       0  4994.0    0.04       0
  5000.0    0.05       0
Bank Sta=4994,5000
Exp/Cntr=0.3,0.1

Type RM Length L Ch R = 1,2399,245,245,245
BEGIN DESCRIPTION:
Mapping XS 04ac80f2
END DESCRIPTION:
XS GIS Cut Line= 2
      2429505.36     13125413.95      2429598.93     13124940.91
#Sta/Elev= 30
  4743.2   67.39  4778.5   67.48  4783.6   67.72  4801.4   67.87  4811.6   67.47
  4862.6   67.34  4886.1   66.68  4893.1   66.20  4913.5   66.38  4923.7   66.18
  4932.3   66.80  4944.1   67.11  4954.3   67.07  4974.7   66.57  4983.5   62.07
  4988.6   61.75  4995.1   58.65  5000.5   58.37  5002.3   58.27  5005.0   57.77
  5008.3   58.27  5015.5   60.09  5025.7   65.16  5034.8   66.51  5039.9   66.51
  5046.0   66.87  5076.6   66.89  5107.2   67.42  5209.1   68.06  5225.4   68.02
#Mann=4,-1,0
  4743.2     0.1       0  5000.5    0.05       0  5002.3    0.07       0
  5008.3    0.05       0
Bank Sta=5002.3,5008.3
Exp/Cntr=0.3,0.1

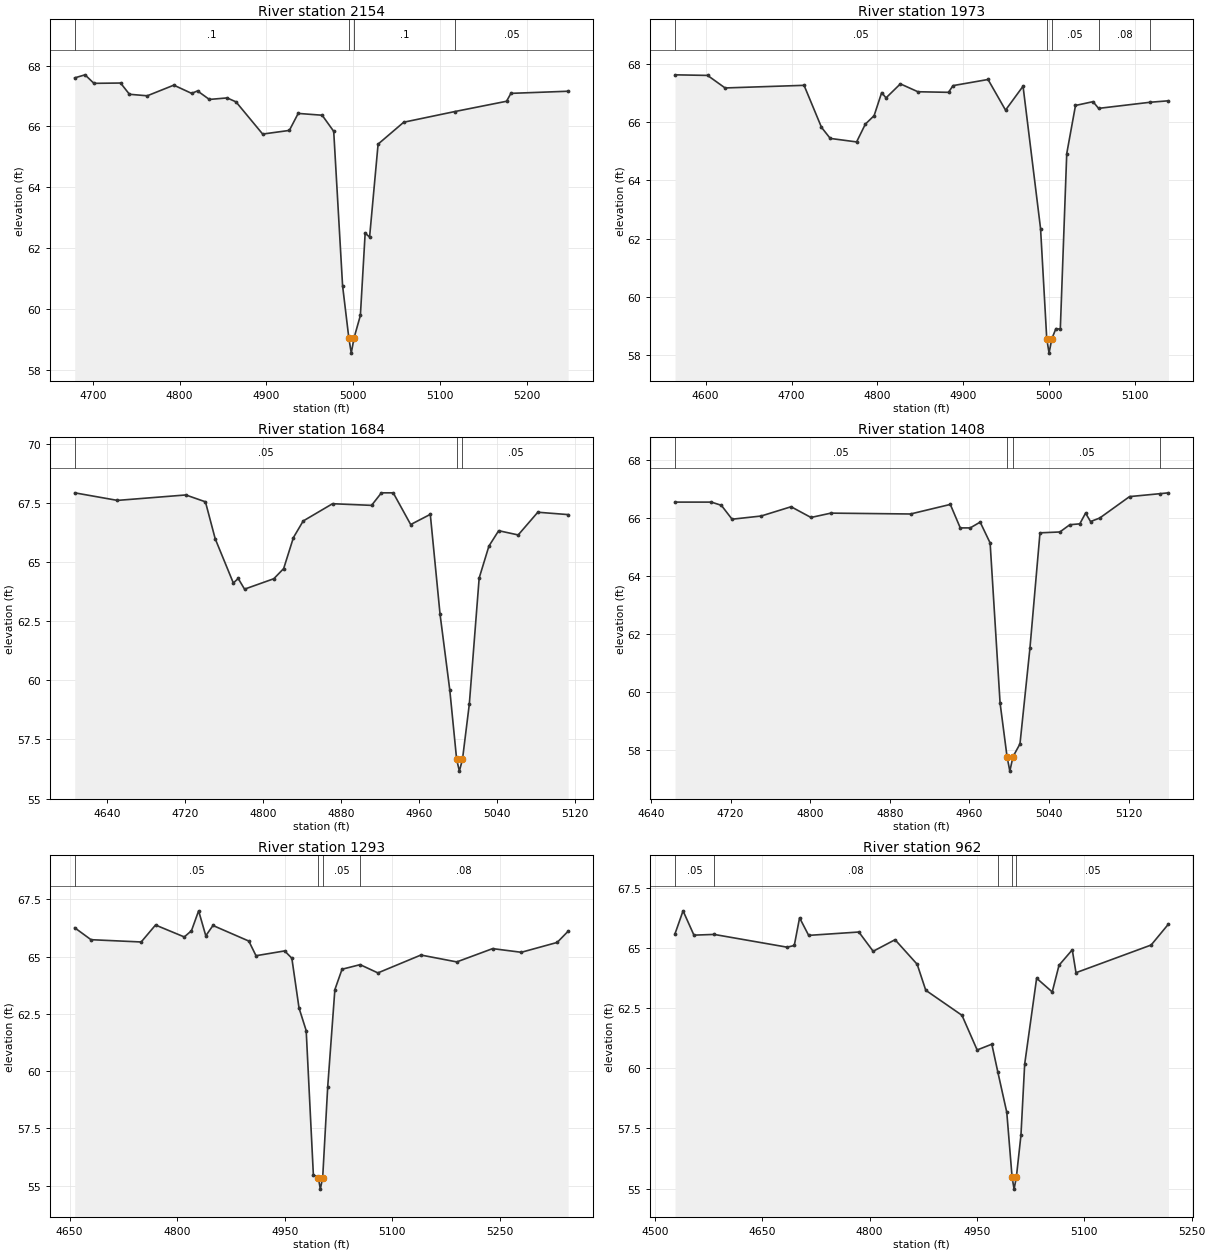
Type RM Length L Ch R = 1,2154,181,181,181
BEGIN DESCRIPTION:
Mapping XS 483ed0e8
END DESCRIPTION:
XS GIS Cut Line= 3
      2429732.82     13125478.47      2429820.02     13125070.04
      2429806.39     13124920.19
#Sta/Elev= 30
  4679.2   67.60  4691.1   67.70  4701.3   67.42  4732.0   67.43  4742.2   67.06
  4762.7   67.01  4793.3   67.36  4813.8   67.09  4820.6   67.17  4834.2   66.89
  4854.7   66.94  4864.9   66.81  4895.6   65.75  4926.3   65.87  4936.5   66.43
  4964.1   66.37  4977.4   65.84  4987.6   60.76  4994.8   59.04  4997.6   58.54
  5000.8   59.04  5008.1   59.78  5013.6   62.49  5018.7   62.36  5028.5   65.42
  5058.0   66.14  5116.6   66.49  5176.4   66.83  5181.4   67.09  5247.3   67.16
#Mann=4,-1,0
  4679.2     0.1       0  4994.8    0.07       0  5000.8     0.1       0
  5116.6    0.05       0
Bank Sta=4994.8,5000.8
Exp/Cntr=0.3,0.1

Type RM Length L Ch R = 1,1973,289,289,289
BEGIN DESCRIPTION:
Mapping XS 9fcdaae5
END DESCRIPTION:
XS GIS Cut Line= 3
      2429893.43     13125583.98      2429957.67     13125271.94
      2430007.92     13125020.70
#Sta/Elev= 30
  4564.3   67.62  4602.2   67.60  4622.6   67.17  4714.6   67.26  4734.9   65.82
  4745.1   65.44  4775.8   65.32  4786.0   65.93  4796.2   66.22  4805.0   67.01
  4810.1   66.83  4826.8   67.31  4847.2   67.04  4882.9   67.02  4888.1   67.25
  4928.9   67.46  4949.3   66.41  4969.7   67.23  4990.1   62.35  4997.3   58.58
  5000.0   58.08  5003.3   58.58  5008.0   58.92  5013.1   58.90  5020.6   64.92
  5030.8   66.57  5051.2   66.70  5057.7   66.47  5117.8   66.68  5139.1   66.73
#Mann=5,-1,0
  4564.3    0.05       0  4997.3    0.04       0  5003.3    0.05       0
  5057.7    0.08       0  5117.8    0.05       0
Bank Sta=4997.3,5003.3
Exp/Cntr=0.3,0.1

Type RM Length L Ch R = 1,1684,276,276,276
BEGIN DESCRIPTION:
Mapping XS 1af76b50
END DESCRIPTION:
XS GIS Cut Line= 2
      2430242.16     13125510.57      2430274.29     13125005.80
#Sta/Elev= 30
  4607.0   67.92  4650.8   67.60  4720.9   67.83  4741.0   67.54  4751.0   65.98
  4769.6   64.11  4774.6   64.30  4781.1   63.85  4811.1   64.29  4821.2   64.72
  4831.2   66.03  4841.2   66.73  4871.3   67.46  4911.3   67.39  4921.4   67.92
  4933.5   67.92  4951.4   66.58  4971.5   67.01  4981.5   62.79  4991.5   59.58
  4998.5   56.66  5001.3   56.16  5004.5   56.66  5011.5   58.99  5021.6   64.32
  5031.6   65.67  5041.6   66.32  5061.6   66.14  5081.7   67.10  5112.8   67.00
#Mann=3,-1,0
  4607.0    0.05       0  4998.5    0.04       0  5004.5    0.05       0
Bank Sta=4998.5,5004.5
Exp/Cntr=0.3,0.1

Type RM Length L Ch R = 1,1408,115,115,115
BEGIN DESCRIPTION:
Mapping XS e4ac7960
END DESCRIPTION:
XS GIS Cut Line= 2
      2430531.25     13125423.36      2430545.01     13124927.76
#Sta/Elev= 30
  4664.2   66.56  4700.7   66.56  4710.7   66.45  4721.5   65.97  4750.7   66.08
  4780.8   66.40  4800.8   66.03  4820.8   66.18  4900.8   66.15  4940.8   66.48
  4950.8   65.67  4960.8   65.67  4970.8   65.87  4980.8   65.15  4990.8   59.63
  4997.8   57.78  5000.6   57.28  5003.8   57.78  5010.8   58.22  5020.8   61.52
  5030.9   65.50  5050.9   65.53  5060.9   65.78  5070.9   65.81  5076.7   66.18
  5081.7   65.89  5090.9   66.01  5120.9   66.75  5151.3   66.85  5160.0   66.88
#Mann=4,-1,0
  4664.2    0.05       0  4997.8    0.04       0  5003.8    0.05       0
  5151.3    0.08       0
Bank Sta=4997.8,5003.8
Exp/Cntr=0.3,0.1

Type RM Length L Ch R = 1,1293,331,331,331
BEGIN DESCRIPTION:
Mapping XS 53e3a1fc
END DESCRIPTION:
XS GIS Cut Line= 3
      2430645.96     13125409.57      2430655.14     13124978.27
      2430655.14     13124721.57
#Sta/Elev= 30
  4657.1   66.26  4679.8   65.74  4749.8   65.64  4769.8   66.38  4809.9   65.86
  4819.9   66.13  4829.9   67.00  4839.9   65.91  4849.9   66.36  4899.9   65.68
  4909.9   65.04  4949.9   65.25  4959.9   64.93  4969.9   62.76  4979.9   61.77
  4989.9   55.48  4996.9   55.35  4999.6   54.85  5002.9   55.35  5009.9   59.31
  5019.9   63.56  5029.9   64.45  5055.1   64.65  5079.9   64.29  5139.9   65.07
  5189.9   64.77  5239.9   65.35  5279.9   65.19  5329.9   65.62  5345.2   66.11
#Mann=4,-1,0
  4657.1    0.05       0  4996.9    0.04       0  5002.9    0.05       0
  5055.1    0.08       0
Bank Sta=4996.9,5002.9
Exp/Cntr=0.3,0.1

Type RM Length L Ch R = 1,962,218,218,218
BEGIN DESCRIPTION:
Mapping XS 10eba6e9
END DESCRIPTION:
XS GIS Cut Line= 3
      2430953.39     13125313.19      2430935.04     13125010.39
      2430825.37     13124640.25
#Sta/Elev= 30
  4528.1   65.59  4539.3   66.54  4554.5   65.53  4582.7   65.56  4684.7   65.03
  4694.7   65.10  4702.1   66.25  4714.8   65.52  4784.9   65.66  4804.9   64.86
  4835.5   65.34  4866.4   64.32  4878.4   63.24  4929.0   62.20  4950.2   60.76
  4970.7   61.00  4979.2   59.83  4991.6   58.17  4999.0   55.48  5001.8   54.98
  5005.0   55.48  5011.4   57.22  5016.6   60.17  5033.3   63.74  5055.1   63.17
  5064.6   64.28  5083.1   64.92  5088.3   63.97  5193.3   65.12  5217.5   65.99
#Mann=5,-1,0
  4528.1    0.05       0  4582.7    0.08       0  4979.2    0.05       0
  4999.0    0.04       0  5005.0    0.05       0
Bank Sta=4999,5005
Exp/Cntr=0.3,0.1

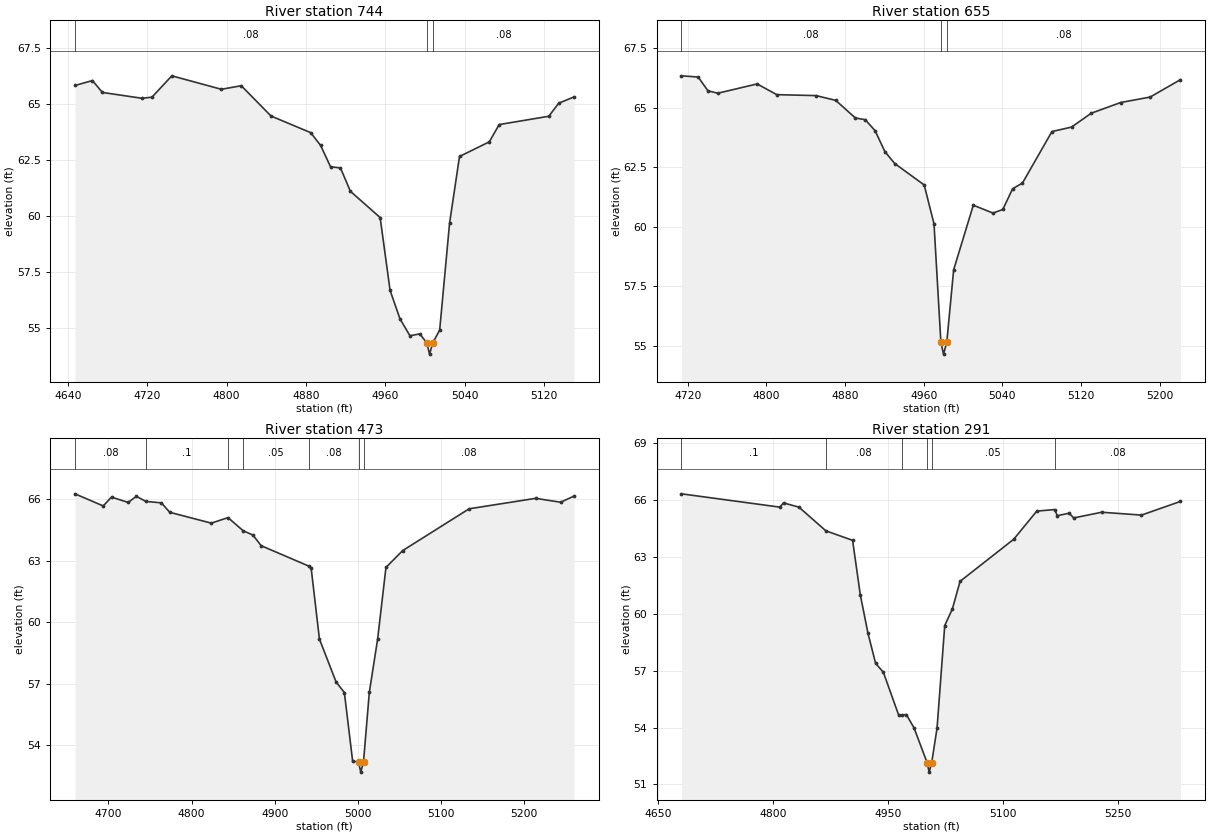
Type RM Length L Ch R = 1,744,89,89,89
BEGIN DESCRIPTION:
Mapping XS 8c64d892
END DESCRIPTION:
XS GIS Cut Line= 2
      2431085.56     13125224.44      2431092.20     13124721.48
#Sta/Elev= 30
  4647.2   65.81  4664.8   66.03  4674.8   65.50  4714.8   65.24  4724.8   65.29
  4744.8   66.24  4794.8   65.64  4814.8   65.80  4844.8   64.45  4884.8   63.71
  4894.8   63.14  4904.8   62.19  4914.8   62.14  4924.8   61.10  4954.8   59.93
  4964.8   56.69  4974.8   55.42  4984.8   54.67  4994.8   54.75  5001.8   54.35
  5004.6   53.85  5007.8   54.35  5014.8   54.92  5024.8   59.69  5034.8   62.65
  5064.8   63.30  5074.8   64.07  5124.8   64.44  5134.8   65.02  5150.2   65.30
#Mann=3,-1,0
  4647.2    0.08       0  5001.8    0.07       0  5007.8    0.08       0
Bank Sta=5001.8,5007.8
Exp/Cntr=0.3,0.1

Type RM Length L Ch R = 1,655,182,182,182
BEGIN DESCRIPTION:
Mapping XS 5e638567
END DESCRIPTION:
XS GIS Cut Line= 2
      2431153.80     13125223.82      2431148.59     13124716.05
#Sta/Elev= 30
  4713.5   66.34  4730.5   66.29  4740.5   65.71  4750.5   65.61  4790.5   66.00
  4810.5   65.55  4850.5   65.51  4870.5   65.31  4890.5   64.57  4900.5   64.50
  4910.5   64.04  4920.5   63.16  4930.5   62.66  4960.5   61.76  4970.5   60.13
  4977.5   55.16  4980.2   54.66  4983.5   55.16  4990.5   58.20  5010.5   60.91
  5030.5   60.58  5040.5   60.73  5050.5   61.60  5060.5   61.84  5090.5   64.00
  5110.5   64.19  5130.5   64.77  5160.5   65.22  5190.5   65.45  5221.3   66.18
#Mann=3,-1,0
  4713.5    0.08       0  4977.5    0.07       0  4983.5    0.08       0
Bank Sta=4977.5,4983.5
Exp/Cntr=0.3,0.1

Type RM Length L Ch R = 1,473,182,182,182
BEGIN DESCRIPTION:
Mapping XS fdda4bc9
END DESCRIPTION:
XS GIS Cut Line= 2
      2431320.48     13125340.73      2431315.90     13124740.74
#Sta/Elev= 30
  4659.9   66.26  4693.8   65.67  4703.8   66.10  4723.8   65.84  4733.8   66.14
  4745.0   65.89  4763.8   65.82  4773.8   65.36  4823.8   64.83  4843.9   65.10
  4862.1   64.46  4873.8   64.25  4883.8   63.73  4940.8   62.74  4943.8   62.66
  4953.8   59.18  4973.8   57.09  4983.8   56.57  4993.8   53.21  5000.8   53.19
  5003.5   52.69  5006.8   53.19  5013.8   56.58  5023.8   59.18  5033.8   62.67
  5053.8   63.49  5133.8   65.53  5213.8   66.04  5243.8   65.85  5259.9   66.15
#Mann=7,-1,0
  4659.9    0.08       0  4745.0     0.1       0  4843.9    0.08       0
  4862.1    0.05       0  4940.8    0.08       0  5000.8    0.07       0
  5006.8    0.08       0
Bank Sta=5000.8,5006.8
Exp/Cntr=0.3,0.1

Type RM Length L Ch R = 1,291,0,0,0
BEGIN DESCRIPTION:
UNT010 IN BACR 1.0
END DESCRIPTION:
XS GIS Cut Line= 3
      2431490.26     13125349.96      2431499.43     13124872.73
      2431407.65     13124725.87
#Sta/Elev= 30
  4680.9   66.31  4809.0   65.61  4814.0   65.83  4834.0   65.61  4869.2   64.36
  4904.0   63.86  4914.0   61.00  4924.0   58.97  4934.0   57.38  4944.1   56.91
  4964.1   54.65  4968.0   54.66  4974.1   54.68  4984.1   53.98  5001.1   52.15
  5003.8   51.65  5007.1   52.15  5014.1   53.97  5024.1   59.37  5034.1   60.25
  5044.1   61.70  5114.1   63.92  5144.1   65.40  5167.2   65.48  5171.0   65.16
  5186.3   65.29  5192.2   65.04  5228.7   65.34  5280.6   65.19  5331.4   65.91
#Mann=6,-1,0
  4680.9     0.1       0  4869.2    0.08       0  4968.0    0.05       0
  5001.1    0.04       0  5007.1    0.05       0  5167.2    0.08       0
Bank Sta=5001.1,5007.1
Exp/Cntr=0.3,0.1

Chan Stop Cuts=-1