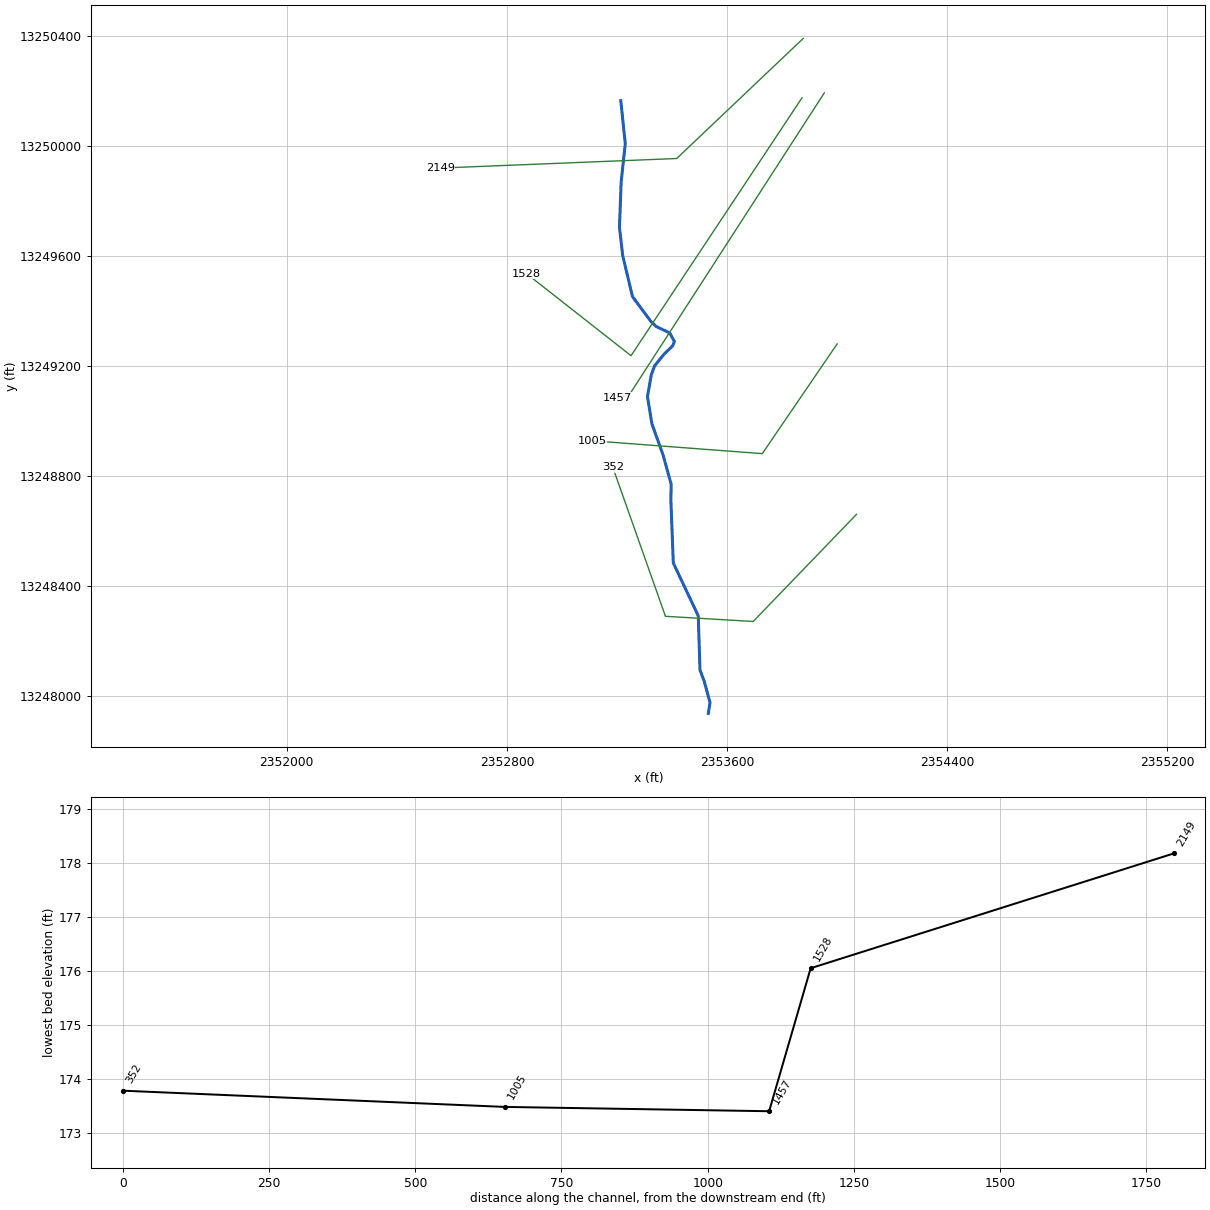
--- UNT012 IN BACR.prj (project) ---

Proj Title=UNT012 IN BACR Base Level Engineering
Current Plan=p01
Default Exp/Contr=0.3,0.1
English Units
Geom File=g01
Flow File=f01
Plan File=p01
Y Axis Title=Elevation
X Axis Title(PF)=Main Channel Distance
X Axis Title(XS)=Station
BEGIN DESCRIPTION:
UNT012 IN BACR
END DESCRIPTION:
DSS Export Rating Curves= 0
DSS Export Rating Curve Sorted= 0
DSS Export Volume Flow Curves= 0
DXF OffsetX= 0
DXF OffsetY= 0
DXF ScaleX= 1
DXF ScaleY= 10

--- UNT012 IN BACR.p01 (plan) ---

Plan Title=Multiple Run
Short Identifier=Multiple
Geom File=g01
Flow File=f01
Subcritical Flow
K Sum by GR= 0
Std Step Tol= 0.01
Critical Tol= 0.01
Num of Std Step Trials= 20
Max Error Tol= 0.3
Flow Tol Ratio= 0.001
Split Flow NTrial= 30
Split Flow Tol= 0.02
Split Flow Ratio= 0.02
Log Output Level= 0
Friction Slope Method= 1
Unsteady Friction Slope Method= 2
Unsteady Bridges Friction Slope Method= 1
Parabolic Critical Depth
Global Vel Dist=  1 , 1 , 1
Global Log Level= 0
CheckData=True
Encroach Param= -1, 0, 0, 0
BEGIN DESCRIPTION:
Multiple Run
END DESCRIPTION:

--- UNT012 IN BACR.f01 (steady flow) ---

Flow Title=Multiple
Number of Profiles=7
Profile Names=10-year,25-year,50-year,1pct_min,100-year,1pct_plu,500-year
River Rch & RM= UNT012 IN BACR,Reach-1,2149
     404     545     657     578     782    1058    1111
River Rch & RM= UNT012 IN BACR,Reach-1,1457
     411     554     667     587     794    1073    1126
Boundary for River Rch & Prof#=UNT012 IN BACR,Reach-1,1
Up Type=0
Dn Type=3
Dn Slope=0.005
Boundary for River Rch & Prof#=UNT012 IN BACR,Reach-1,2
Up Type=0
Dn Type=3
Dn Slope=0.005
Boundary for River Rch & Prof#=UNT012 IN BACR,Reach-1,3
Up Type=0
Dn Type=3
Dn Slope=0.005
Boundary for River Rch & Prof#=UNT012 IN BACR,Reach-1,4
Up Type=0
Dn Type=3
Dn Slope=0.005
Boundary for River Rch & Prof#=UNT012 IN BACR,Reach-1,5
Up Type=0
Dn Type=3
Dn Slope=0.005
Boundary for River Rch & Prof#=UNT012 IN BACR,Reach-1,6
Up Type=0
Dn Type=3
Dn Slope=0.005
Boundary for River Rch & Prof#=UNT012 IN BACR,Reach-1,7
Up Type=0
Dn Type=3
Dn Slope=0.005

--- UNT012 IN BACR.g01 (geometry) ---

Geom Title=Existing Conditions
Program Version=4.10

River Reach=UNT012 IN BACR  ,Reach-1
Reach XY= 25
      2353213.72     13250164.66      2353230.08      13250008.5
      2353215.11     13249869.54      2353208.95     13249703.72
      2353220.71     13249602.21      2353256.14     13249453.08
       2353323.4     13249362.25      2353342.23     13249344.42
      2353391.56      13249320.8      2353408.63     13249289.63
       2353402.2     13249273.98      2353372.38     13249245.19
      2353336.14     13249200.75      2353324.57     13249168.15
      2353310.62     13249089.96      2353326.71     13248991.08
      2353367.61     13248876.69      2353396.75     13248771.36
      2353395.72     13248714.07      2353404.61     13248484.95
      2353495.36     13248292.67      2353501.49     13248096.09
      2353516.88     13248055.07      2353538.07     13247977.39
      2353531.71     13247938.46

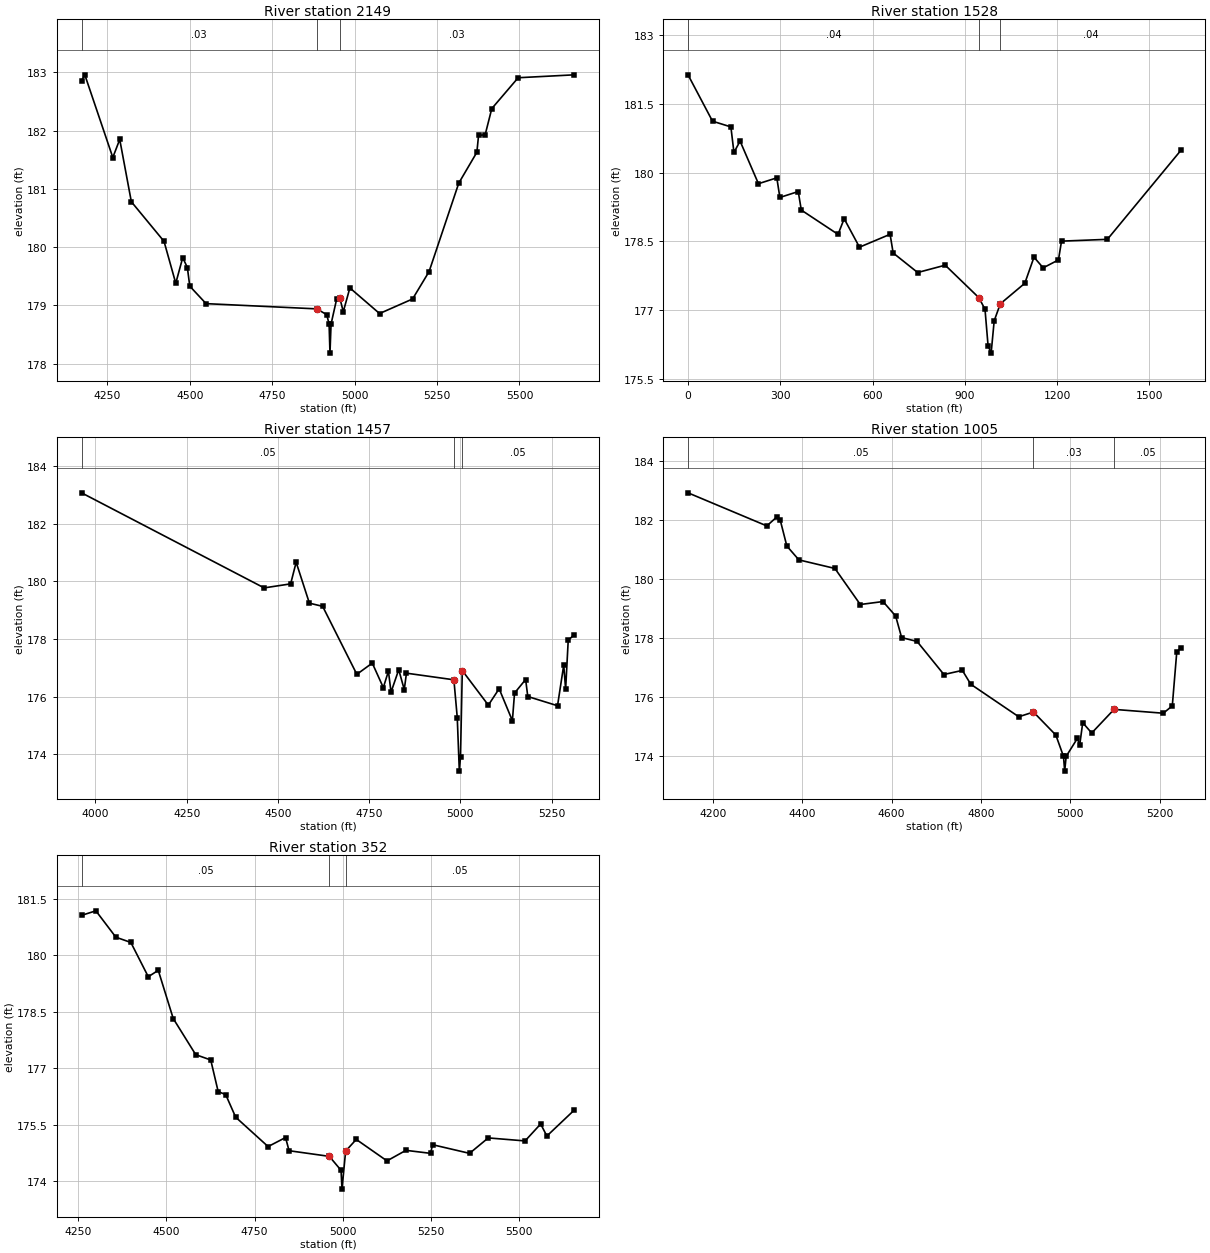
Type RM Length L Ch R = 1 ,2149    ,621,621,621
BEGIN DESCRIPTION:
UNT012 IN BACR 2.0
END DESCRIPTION:
XS GIS Cut Line= 3
      2353877.06      13250391.3      2353416.96     13249954.64
      2352557.58     13249919.92
#Sta/Elev= 30
    4172  182.86  4181.9  182.96  4266.8  181.54  4287.8  181.85    4323  180.78
  4422.1   180.1  4457.7  179.38  4478.8  179.82  4492.9  179.65  4500.2  179.33
  4549.6  179.03  4885.6  178.94  4915.6  178.84  4922.7  178.68  4925.4  178.18
  4928.7  178.68  4945.7  179.11  4955.7  179.12  4965.7  178.89  4985.7   179.3
  5075.8  178.86  5175.9  179.11  5225.9  179.58    5316   181.1  5370.9  181.63
    5376  181.92    5396  181.93  5416.1  182.38  5496.1  182.91  5666.4  182.96
#Mann= 3 , 0 , 0
    4172     .03       0  4885.6     .03       0  4955.7     .03       0
Bank Sta=4885.6,4955.7
XS Rating Curve= 0 ,0
Exp/Cntr=0.3,0.1

Type RM Length L Ch R = 1 ,1528    ,71,71,71
BEGIN DESCRIPTION:
Mapping XS 02ecfec6
END DESCRIPTION:
XS GIS Cut Line= 3
     2353872.511     13250175.57     2353250.984     13249238.07
     2352870.775     13249536.68
#Sta/Elev= 30
       0182.135779.63274181.1229139.3573 180.998149.3114180.4391169.2196180.6883
228.9441179.7572288.6687179.8851298.6228179.4567358.3473179.5859368.3014 179.181
487.7505178.6501507.6587178.9921557.4292178.3705656.9701178.6519666.9242178.2437
746.5569177.8168836.1437177.9772945.6388177.2669965.5469177.0133 975.501176.2189
985.4551176.0559995.4092176.76271015.317177.1329 1094.95177.58221124.813178.1517
1154.638 177.9191204.348178.0921 1214.29178.50241363.419178.54171602.025180.4829
#Mann= 3 , 0 , 0
       0     .04       0945.6388     .03       01015.317     .04       0
Bank Sta=945.6388,1015.317
XS Rating Curve= 0 ,0
Exp/Cntr=0.3,0.1

Type RM Length L Ch R = 1 ,1457    ,452,452,452
BEGIN DESCRIPTION:
Mapping XS c9e6e8ad
END DESCRIPTION:
XS GIS Cut Line= 3
      2353953.43     13250193.38      2353245.79     13249097.56
       2353201.7     13249084.58
#Sta/Elev= 30
    3962  183.07  4462.4  179.77    4535  179.91  4550.1  180.66  4586.4  179.24
  4622.7  179.13  4716.4  176.77  4758.7  177.16    4789  176.31    4803  176.88
  4810.1  176.15  4831.2  176.93  4846.4  176.24  4852.4  176.81  4982.4  176.58
  4991.6  175.27  4997.3  173.41  5000.5  173.91  5005.4   176.9  5076.8   175.7
  5106.4  176.27  5142.7  175.16  5148.6  176.12    5179  176.59  5184.9     176
  5266.4  175.68  5283.4  177.09  5288.6  176.25  5295.7  177.95  5312.4  178.15
#Mann= 3 , 0 , 0
    3962     .05       0  4982.4     .05       0  5005.4     .05       0
Bank Sta=4982.4,5005.4
XS Rating Curve= 0 ,0
Exp/Cntr=0.3,0.1

Type RM Length L Ch R = 1 ,1005    ,653,653,653
BEGIN DESCRIPTION:
Mapping XS cf9bb24e
END DESCRIPTION:
XS GIS Cut Line= 3
      2353999.95     13249280.93      2353727.87      13248882.2
      2353108.76     13248929.11
#Sta/Elev= 30
  4143.9  182.91  4320.4  181.79  4342.5  182.09  4350.2     182  4365.2  181.11
  4392.2  180.64  4472.9  180.35  4529.7  179.13  4580.6  179.23  4608.9  178.74
  4622.3  178.01  4656.9  177.88    4717  176.76  4758.3   176.9  4777.2  176.43
  4884.6  175.33  4917.6  175.49  4967.7  174.71  4984.8  173.99  4987.5  173.49
  4990.8  173.99    5016   174.6    5021  174.36  5027.9  175.13    5048  174.78
  5098.1  175.58  5208.4  175.45  5228.5   175.7  5238.5  177.52  5247.5  177.67
#Mann= 3 , 0 , 0
  4143.9     .05       0  4917.6     .03       0  5098.1     .05       0
Bank Sta=4917.6,5098.1
XS Rating Curve= 0 ,0
Exp/Cntr=0.3,0.1

Type RM Length L Ch R = 1 ,352     ,0,0,0
BEGIN DESCRIPTION:
UNT012 IN BACR 1.0
END DESCRIPTION:
XS GIS Cut Line= 4
       2354070.3     13248661.77      2353695.04     13248272.44
      2353376.09      13248291.2      2353184.39     13248833.58
#Sta/Elev= 30
  4259.5  181.06  4300.1  181.18  4356.7  180.48  4399.2  180.34  4448.6  179.43
  4476.9   179.6  4519.3  178.32  4583.1  177.36  4625.6  177.22  4646.7  176.38
    4668   176.3  4696.3   175.7  4788.2  174.92  4837.6  175.16  4847.6  174.81
  4961.7  174.66  4994.9  174.29  4997.6  173.79  5007.9   174.8    5038  175.11
  5125.1  174.54  5178.8  174.82  5248.8  174.74  5254.1  174.97  5359.1  174.74
  5412.1  175.15  5516.4  175.07  5560.6  175.52  5578.2   175.2    5656  175.89
#Mann= 3 , 0 , 0
  4259.5     .05       0  4961.7     .03       0  5007.9     .05       0
Bank Sta=4961.7,5007.9
XS Rating Curve= 0 ,0
Exp/Cntr=0.3,0.1

Chan Stop Cuts=-1
Use User Specified Reach Order=0
Composite Channel Slope=5