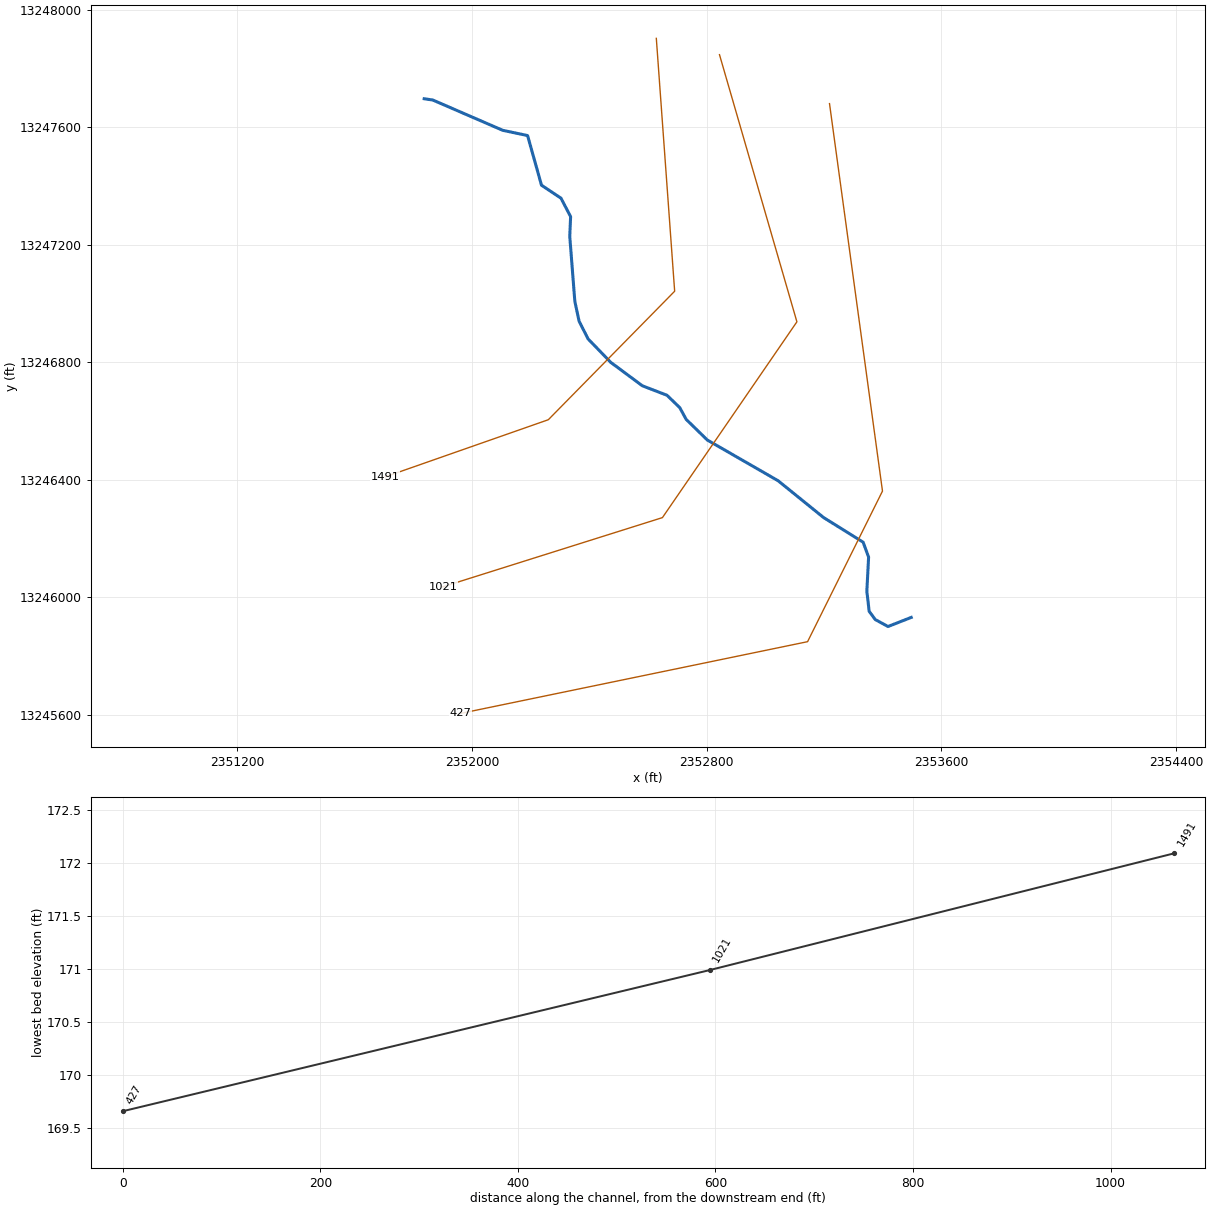
--- UNT013 IN BACR.prj (project) ---

Proj Title=UNT013 IN BACR Base Level Engineering
Current Plan=p01
Default Exp/Contr=0.3,0.1
English Units
Geom File=g01
Flow File=f01
Plan File=p01
Y Axis Title=Elevation
X Axis Title(PF)=Main Channel Distance
X Axis Title(XS)=Station
BEGIN DESCRIPTION:
UNT013 IN BACR
END DESCRIPTION:
DSS File=dss
DSS Export Rating Curves= 0
DSS Export Rating Curve Sorted= 0
DSS Export Volume Flow Curves= 0
DXF OffsetX= 0
DXF OffsetY= 0
DXF ScaleX= 1
DXF ScaleY= 10

--- UNT013 IN BACR.p01 (plan) ---

Plan Title=Multiple Run
Program Version=4.10
Short Identifier=Multiple Run
Geom File=g01
Flow File=f01
Subcritical Flow
K Sum by GR= 0
Std Step Tol= 0.01
Critical Tol= 0.01
Num of Std Step Trials= 20
Max Error Tol= 0.3
Flow Tol Ratio= 0.001
Split Flow NTrial= 30
Split Flow Tol= 0.02
Split Flow Ratio= 0.02
Log Output Level= 0
Friction Slope Method= 1
Unsteady Friction Slope Method= 2
Unsteady Bridges Friction Slope Method= 1
Parabolic Critical Depth
Global Vel Dist= 1 , 1 , 1
Global Log Level= 0
CheckData=True
Encroach Param=-1 ,0,0, 0
BEGIN DESCRIPTION:
Multiple Run
END DESCRIPTION:
Computation Interval=1HOUR
Output Interval=1HOUR
Run HTab= 0
Run UNet= 0
Run PostProcess= 0
Run WQNet= 0
UNET Theta= 1
UNET Theta Warmup= 1
UNET ZTol= 0.02
UNET ZSATol= 0.05
UNET MxIter= 20
UNET MaxInSteps= 0
UNET DtIC= 0
UNET DtMin= 0
UNET MaxCRTS= 20
UNET WFStab= 2
UNET SFStab= 1
UNET WFX= 1
UNET SFX= 1
UNET DSS MLevel= 4
UNET DZMax Abort= 100
UNET Convert EG Bridges= 0
UNET Use Existing IB Tables=-1
UNET Froude Reduction=False
UNET Froude Limit= 1
UNET Froude Power= 10
UNET Time Slicing=0,0, 5
UNET Junction Losses=0
Instantaneous Interval=1HOUR
DSS File=dss
Write IC File= 0
Write IC File at Sim End=0
Echo Input=False
Echo Parameters=False
Echo Output=False
Write Detailed= 0
WQ AD Non Conservative
WQ ULTIMATE=-1
WQ Max Comp Step=1HOUR
WQ Output Interval=15MIN
WQ Output Selected Increments= 0
WQ Output face flow=0
WQ Output face velocity=0
WQ Output face area=0
WQ Output face dispersion=0
WQ Output cell volume=0
WQ Output cell surface area=0
WQ Output cell continuity=0
WQ Output cumulative cell continuity=0
WQ Output face conc=0
WQ Output face dconc_dx=0
WQ Output face courant=0
WQ Output face peclet=0
WQ Output face adv mass=0
WQ Output face disp mass=0
WQ Output cell mass=0
WQ Output cell source sink temp=0
WQ Output cell source sink nsm=0
WQ Output MaxMinRange=-1
WQ Daily Max Min Mean=-1
WQ Daily Range=0
WQ Daily Time=0
WQ Create Restart=0
WQ Fixed Restart=0
WQ System Summary=0
WQ Use Fixed Temperature=0
Sorting and Armoring Iterations= 10
XS Update Threshold= 0.02
Hydraulics Update Threshold= 0.02
Energy Slope Method= 1
Volume Change Method= 0
XS Weighting Method= 0
Number of US Weighted Cross Sections= 1
Number of DS Weighted Cross Sections= 1
Upstream XS Weight=0.25
Main XS Weight=0.5
Downstream XS Weight=0.25
Number of DS XS's Weighted with US Boundary= 1
Upstream Boundary Weight= 1
Weight of XSs Associated with US Boundary= 0
Number of US XS's Weighted with DS Boundary= 1
Downstream Boundary Weight= 0.5
Weight of XSs Associated with DS Boundary= 0.5
Sediment Output Level= 4
Mass or Volume Output= 0
Output Increment Type= 1
Profile and TS Output Increment= 10
XS Output Flag= 0
XS Output Increment= 10
Disregard all LS=0
Disregard all Conn=0
Disregard all Breaches=0
Disregard all Pumps=0

--- UNT013 IN BACR.f01 (steady flow) ---

Flow Title=Multiple
Program Version=4.10
Number of Profiles= 7
Profile Names=10-year,25-year,50-year,1pct_min,100-year,1pct_plu,500-year
River Rch & RM=UNT013 IN BACR,Reach-1         ,1491
     444     601     727     641     866    1172    1236
Boundary for River Rch & Prof#=UNT013 IN BACR,Reach-1         , 1
Up Type= 0
Dn Type= 3
Dn Slope=0.005
Boundary for River Rch & Prof#=UNT013 IN BACR,Reach-1         , 2
Up Type= 0
Dn Type= 3
Dn Slope=0.005
Boundary for River Rch & Prof#=UNT013 IN BACR,Reach-1         , 3
Up Type= 0
Dn Type= 3
Dn Slope=0.005
Boundary for River Rch & Prof#=UNT013 IN BACR,Reach-1         , 4
Up Type= 0
Dn Type= 3
Dn Slope=0.005
Boundary for River Rch & Prof#=UNT013 IN BACR,Reach-1         , 5
Up Type= 0
Dn Type= 3
Dn Slope=0.005
Boundary for River Rch & Prof#=UNT013 IN BACR,Reach-1         , 6
Up Type= 0
Dn Type= 3
Dn Slope=0.005
Boundary for River Rch & Prof#=UNT013 IN BACR,Reach-1         , 7
Up Type= 0
Dn Type= 3
Dn Slope=0.005
DSS Import GetInterval= 0
DSS Import GetPeak= 0
DSS Import FillOption= 0

--- UNT013 IN BACR.g01 (geometry) ---

Geom Title=Existing Conditions
Program Version=4.10

River Reach=UNT013 IN BACR  ,Reach-1
Reach XY= 26
      2351837.72     13247696.85      2351867.08     13247692.44
      2352105.44     13247589.33      2352189.95     13247571.48
      2352237.41     13247402.44       2352303.8     13247358.27
      2352336.65     13247295.49      2352333.71      13247228.2
      2352351.03     13247006.93      2352365.45     13246939.73
      2352396.12     13246879.11      2352473.53     13246799.18
      2352581.33      13246719.4      2352665.03     13246687.24
      2352708.63     13246645.13      2352730.52     13246605.08
      2352802.46     13246534.89        2353044.     13246396.06
      2353198.66     13246270.92       2353333.6     13246186.93
      2353352.29     13246136.02      2353346.32     13246019.89
      2353354.24     13245951.57      2353374.99     13245923.45
       2353418.5     13245899.79      2353497.66     13245930.83

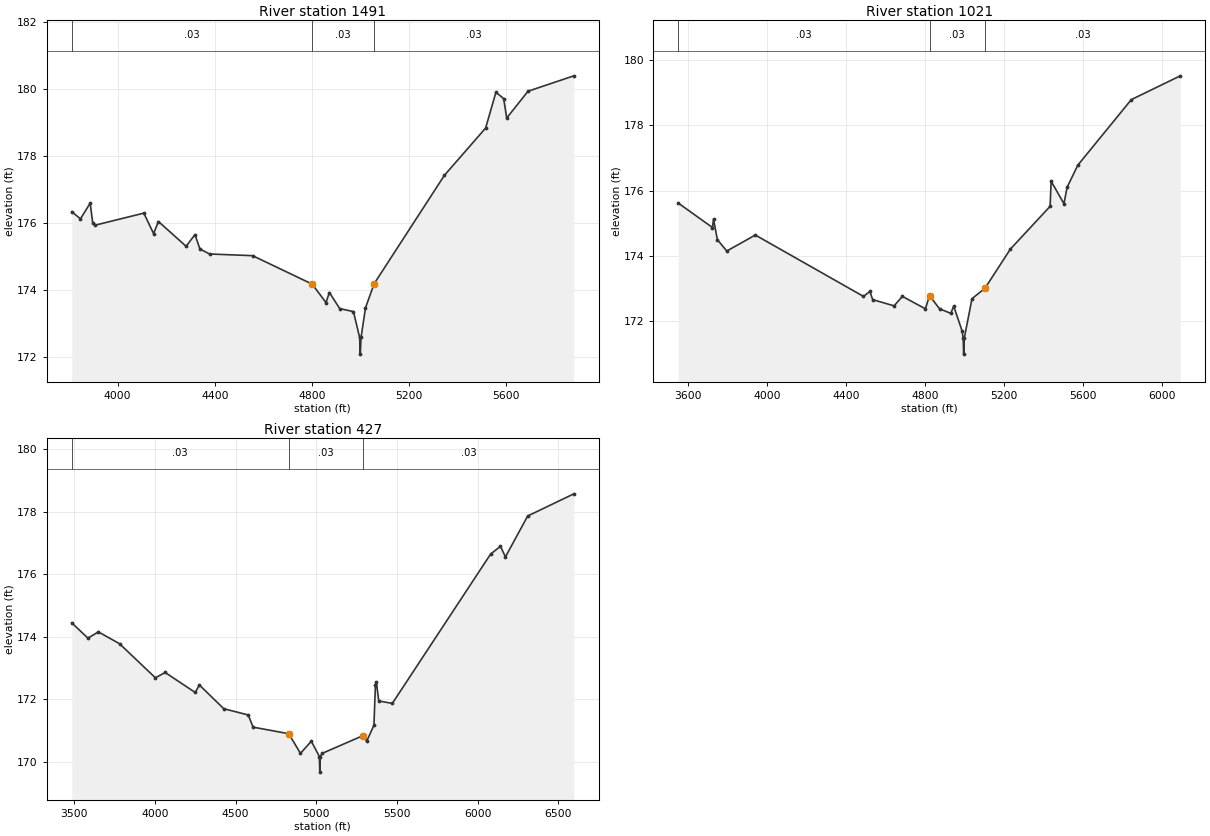
Type RM Length L Ch R = 1 ,1491    ,470,470,470
BEGIN DESCRIPTION:
Mapping XS e0cc9224
END DESCRIPTION:
XS GIS Cut Line= 4
      2352628.77     13247902.54      2352691.26     13247041.44
      2352260.71     13246603.94      2351705.14      13246409.5
#Sta/Elev= 30
  3811.6  176.34  3847.4  176.13  3887.5   176.6  3897.5  176.02  3907.5  175.94
  4108.1   176.3  4148.2  175.69  4168.2  176.05  4282.1  175.31  4318.6  175.66
  4338.7  175.23  4378.8  175.08  4555.6  175.03  4800.9  174.18  4857.5  173.63
  4871.6  173.93  4914.1  173.45  4970.6  173.36  4995.9  172.59  4998.7  172.09
  5001.9  172.59  5020.1  173.47  5055.5  174.19  5344.9  177.43  5514.4  178.84
  5556.8  179.91  5588.6  179.72  5601.2  179.14  5688.9  179.94  5877.4   180.4
#Mann= 3 , 0 , 0
  3811.6     .03       0  4800.9     .03       0  5055.5     .03       0
Bank Sta=4800.9,5055.5
XS Rating Curve= 0 ,0
Exp/Cntr=0.3,0.1

Type RM Length L Ch R = 1 ,1021    ,594,594,594
BEGIN DESCRIPTION:
Mapping XS e8aca559
END DESCRIPTION:
XS GIS Cut Line= 4
      2352844.05     13247846.96      2353107.93     13246937.28
       2352649.6     13246270.61      2351901.11     13246034.98
#Sta/Elev= 30
  3550.1  175.62  3723.4  174.87  3728.6  175.13    3748   174.5  3795.7  174.15
  3940.4  174.64  4487.3  172.76  4520.1  172.91  4534.2  172.66  4642.5  172.47
  4684.4  172.76  4800.8  172.38  4821.8  172.78  4872.5  172.38  4929.4  172.24
  4944.2  172.46  4986.2  171.71    4992  171.49  4994.7  170.99    4998  171.49
  5036.9  172.69  5102.6  173.01  5231.1  174.21  5432.1  175.52  5437.3  176.29
  5502.1   175.6  5517.9   176.1  5572.1  176.78  5842.9  178.79    6091  179.52
#Mann= 3 , 0 , 0
  3550.1     .03       0  4821.8     .03       0  5102.6     .03       0
Bank Sta=4821.8,5102.6
XS Rating Curve= 0 ,0
Exp/Cntr=0.3,0.1

Type RM Length L Ch R = 1 ,427     ,0,0,0
BEGIN DESCRIPTION:
UNT013 IN BACR 1.0
END DESCRIPTION:
XS GIS Cut Line= 4
      2353219.05     13247680.31       2353399.6     13246360.89
      2353144.32     13245848.15      2351962.46     13245604.02
#Sta/Elev= 30
  3484.9  174.44    3585  173.95  3649.9  174.15  3781.1  173.77  4003.1  172.68
  4063.7  172.85    4250  172.21  4275.7  172.45    4427  171.69  4578.4  171.49
  4608.7   171.1  4829.4  170.89  4902.1  170.26  4969.3  170.65  5019.2  170.16
  5021.9  169.66  5025.2  170.16  5036.5  170.26  5290.3  170.83  5312.6  170.65
  5357.3  171.16  5366.7  172.45  5372.3  172.54  5387.3  171.94  5471.3  171.86
  6080.3  176.64  6141.5  176.89  6172.2  176.55  6310.2  177.86  6596.2  178.57
#Mann= 3 , 0 , 0
  3484.9     .03       0  4829.4     .03       0  5290.3     .03       0
Bank Sta=4829.4,5290.3
XS Rating Curve= 0 ,0
Exp/Cntr=0.3,0.1
Stream Node=UNT013 IN BACR  ,Reach-1         , 0 , 0 ,Upstream end
Stream Node=UNT013 IN BACR  ,Reach-1         , 0 , 1 ,Downstream end

Chan Stop Cuts=-1
Use User Specified Reach Order=0
Composite Channel Slope=5