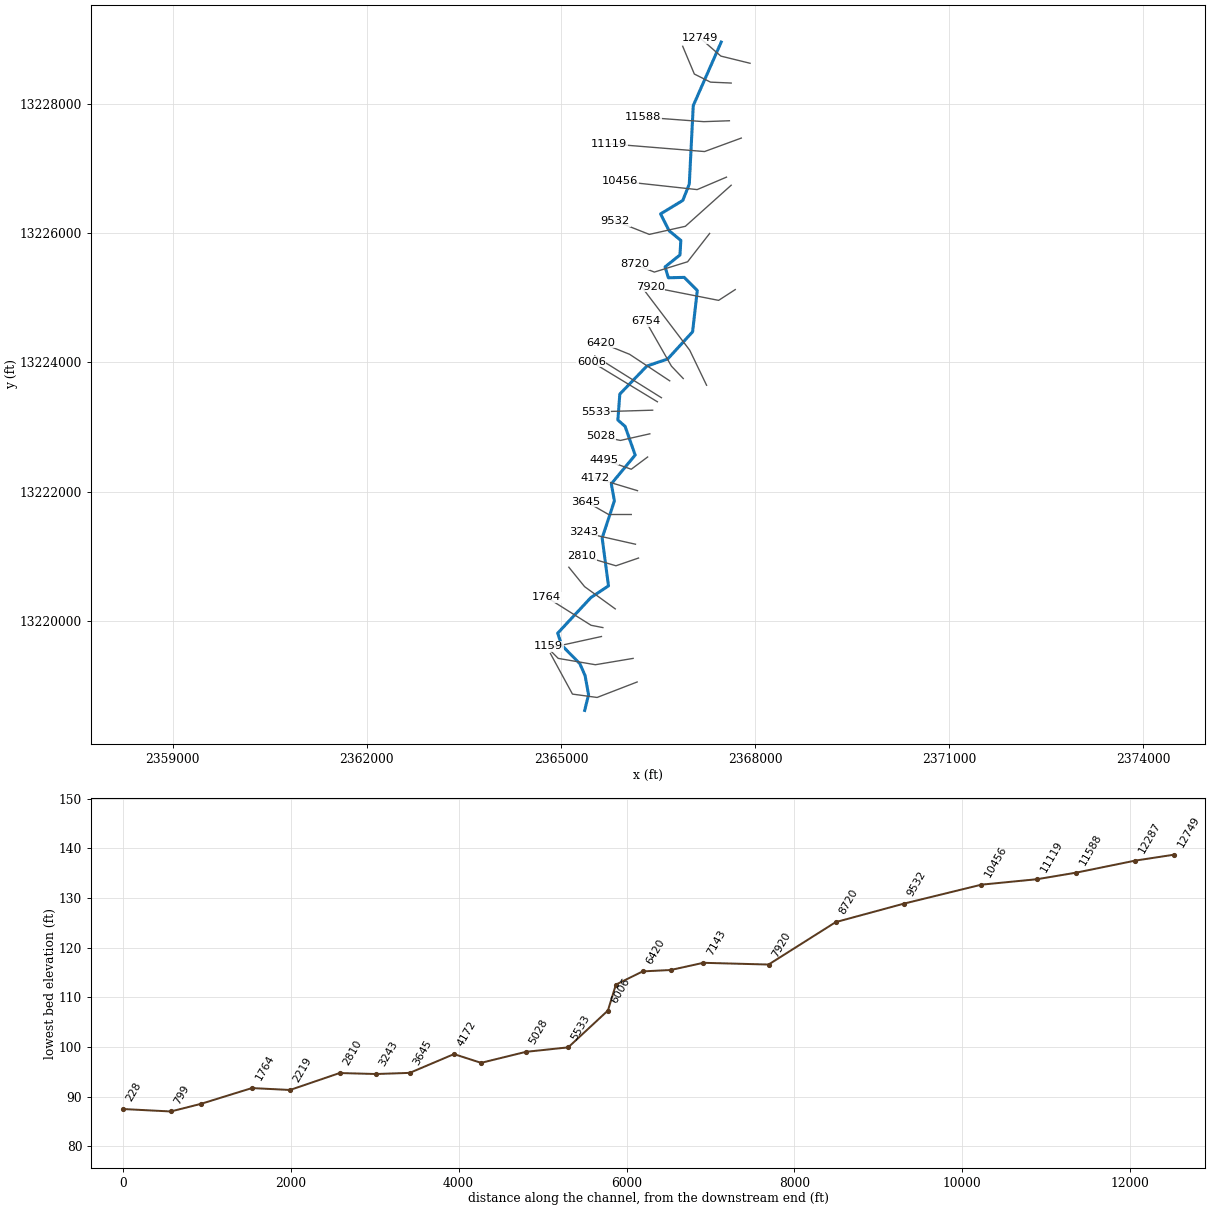
--- UNT016 IN BACR.prj (project) ---

Proj Title=UNT016 IN BACR Base Level Engineering
Current Plan=p01
Default Exp/Contr=0.3,0.1
English Units
Geom File=g01
Flow File=f01
Plan File=p01
Y Axis Title=Elevation
X Axis Title(PF)=Main Channel Distance
X Axis Title(XS)=Station
BEGIN DESCRIPTION:
UNT016 IN BACR
END DESCRIPTION:
DSS Export Rating Curves= 0
DSS Export Rating Curve Sorted= 0
DSS Export Volume Flow Curves= 0
DXF OffsetX= 0
DXF OffsetY= 0
DXF ScaleX= 1
DXF ScaleY= 10

--- UNT016 IN BACR.p01 (plan) ---

Plan Title=Multiple Run
Short Identifier=Multiple
Geom File=g01
Flow File=f01
Subcritical Flow
K Sum by GR= 0
Std Step Tol= 0.01
Critical Tol= 0.01
Num of Std Step Trials= 20
Max Error Tol= 0.3
Flow Tol Ratio= 0.001
Split Flow NTrial= 30
Split Flow Tol= 0.02
Split Flow Ratio= 0.02
Log Output Level= 0
Friction Slope Method= 1
Unsteady Friction Slope Method= 2
Unsteady Bridges Friction Slope Method= 1
Parabolic Critical Depth
Global Vel Dist=  1 , 1 , 1
Global Log Level= 0
CheckData=True
Encroach Param= -1, 0, 0, 0
BEGIN DESCRIPTION:
Multiple Run
END DESCRIPTION:

--- UNT016 IN BACR.f01 (steady flow) ---

Flow Title=Multiple
Number of Profiles=7
Profile Names=10-year,25-year,50-year,1pct_min,100-year,1pct_plu,500-year
River Rch & RM= UNT016 IN BACR,Reach-1,12749
     517     695     835     731     988    1337    1390
River Rch & RM= UNT016 IN BACR,Reach-1,11588
     718     982    1195    1058    1431    1935    2059
River Rch & RM= UNT016 IN BACR,Reach-1,10456
     931    1297    1596    1429    1932    2613    2844
River Rch & RM= UNT016 IN BACR,Reach-1,7143
    1115    1568    1943    1751    2368    3203    3531
River Rch & RM= UNT016 IN BACR,Reach-1,6006
    1272    1806    2253    2043    2763    3736    4172
Boundary for River Rch & Prof#=UNT016 IN BACR,Reach-1,1
Up Type=0
Dn Type=3
Dn Slope=0.005
Boundary for River Rch & Prof#=UNT016 IN BACR,Reach-1,2
Up Type=0
Dn Type=3
Dn Slope=0.005
Boundary for River Rch & Prof#=UNT016 IN BACR,Reach-1,3
Up Type=0
Dn Type=3
Dn Slope=0.005
Boundary for River Rch & Prof#=UNT016 IN BACR,Reach-1,4
Up Type=0
Dn Type=3
Dn Slope=0.005
Boundary for River Rch & Prof#=UNT016 IN BACR,Reach-1,5
Up Type=0
Dn Type=3
Dn Slope=0.005
Boundary for River Rch & Prof#=UNT016 IN BACR,Reach-1,6
Up Type=0
Dn Type=3
Dn Slope=0.005
Boundary for River Rch & Prof#=UNT016 IN BACR,Reach-1,7
Up Type=0
Dn Type=3
Dn Slope=0.005

--- UNT016 IN BACR.g01 (geometry) ---

Geom Title=Existing Conditions
Program Version=4.10

River Reach=UNT016 IN BACR  ,Reach-1
Reach XY= 30
       2367477.5     13228952.43      2367045.72     13227970.25
       2366984.6     13226758.14      2366884.23     13226504.13
      2366540.53     13226295.45      2366672.74     13226034.48
      2366853.68     13225886.31      2366840.46      13225660.6
       2366610.2     13225475.79      2366661.13     13225307.84
      2366906.32     13225313.86      2367107.82     13225111.44
      2367035.68      13224472.7      2366649.92     13224051.11
      2366329.42     13223942.99       2365910.7     13223509.23
      2365880.39     13223107.88      2365992.21     13223009.72
       2366147.8     13222566.03       2365779.4     13222121.08
       2365826.8     13221857.42      2365637.58     13221283.22
       2365735.8      13220542.7      2365464.61     13220363.11
      2364950.42     13219811.41       2365012.7     13219624.28
      2365292.92     13219339.82      2365373.83     13219155.24
      2365427.49     13218859.58      2365367.72     13218616.85

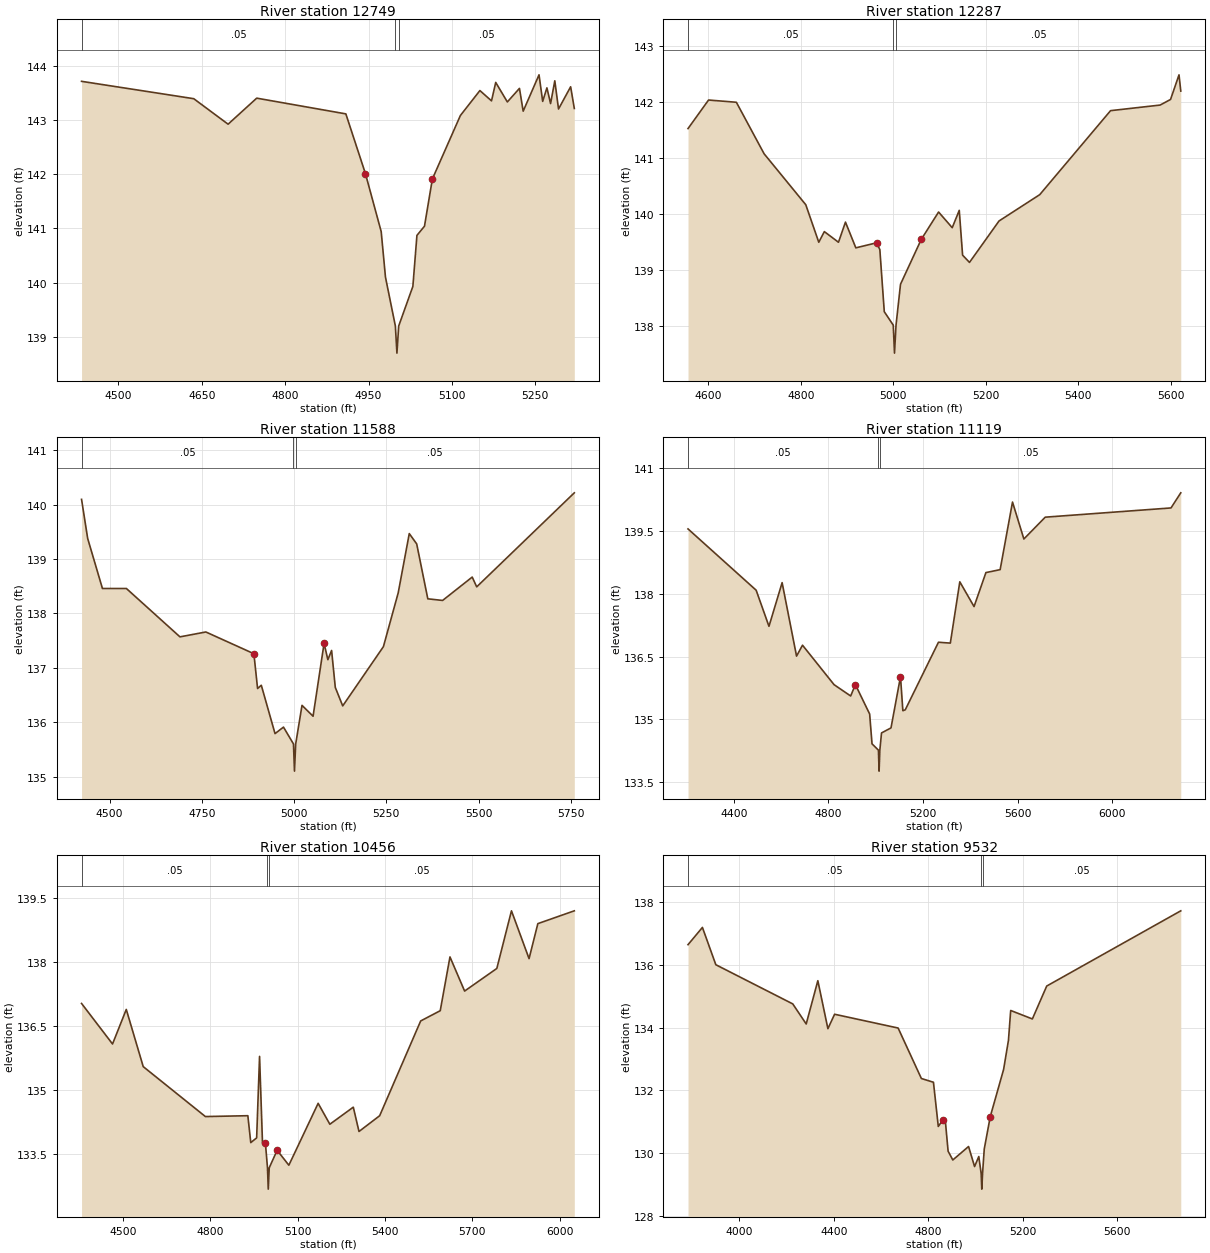
Type RM Length L Ch R = 1 ,12749   ,462,462,462
BEGIN DESCRIPTION:
UNT016 IN BACR 19.0
END DESCRIPTION:
XS GIS Cut Line= 3
      2367923.74       13228625.      2367472.34     13228736.11
      2367154.03      13229012.9
#Sta/Elev= 30
  4433.6  143.71  4635.5  143.39  4697.3  142.92  4748.8   143.4  4909.2  143.11
  4944.4  142.01  4972.8  140.94  4980.5   140.1  4998.3   139.2  5001.1   138.7
  5004.3   139.2  5029.8  139.93  5037.1  140.87  5050.7  141.04  5064.9  141.91
  5115.3  143.08  5150.4  143.54  5171.3  143.35  5178.9  143.69  5199.8  143.33
  5221.6  143.58  5228.3  143.16  5256.8  143.83  5263.4  143.34    5271  143.59
  5277.6   143.3  5285.2  143.72  5291.9   143.2  5313.7  143.61  5320.3  143.21
#Mann= 3 ,-1 , 0
  4433.6     .05       0  4998.3    .035       0  5004.3     .05       0
Bank Sta=4944.4,5064.9
XS Rating Curve= 0 ,0
Exp/Cntr=0.3,0.1

Type RM Length L Ch R = 1 ,12287   ,699,699,699
BEGIN DESCRIPTION:
UNT016 IN BACR 18.0
END DESCRIPTION:
XS GIS Cut Line= 4
      2367632.11     13228319.44      2367312.61     13228333.34
      2367062.61     13228458.34       2366882.4     13228888.07
#Sta/Elev= 30
  4556.4  141.52  4600.8  142.03  4660.9  141.99  4720.9  141.07    4811  140.16
  4839.1  139.49  4851.1  139.68  4881.7  139.49  4896.8  139.85  4919.2  139.39
  4963.9  139.48  4971.1  139.36  4980.7  138.25  5000.1  138.01  5002.8  137.51
  5006.1  138.01  5015.8  138.74  5060.6  139.54  5098.1  140.03  5127.6  139.75
  5142.8  140.06    5150  139.26  5164.9  139.13  5228.8  139.87  5316.8  140.34
  5469.9  141.84    5577  141.94  5599.6  142.04  5617.9  142.48  5621.7  142.19
#Mann= 3 ,-1 , 0
  4556.4     .05       0  5000.1    .035       0  5006.1     .05       0
Bank Sta=4963.9,5060.6
XS Rating Curve= 0 ,0
Exp/Cntr=0.3,0.1

Type RM Length L Ch R = 1 ,11588   ,469,469,469
BEGIN DESCRIPTION:
UNT016 IN BACR 17.0
END DESCRIPTION:
XS GIS Cut Line= 3
      2367604.28     13227736.11      2367208.45     13227722.22
      2366271.79     13227791.61
#Sta/Elev= 30
    4424   140.1  4440.6  139.38  4480.6  138.46  4545.5  138.46  4690.7  137.57
  4760.8  137.66    4891  137.26    4901  136.62  4911.1  136.68  4948.3  135.79
  4971.2  135.91  4998.3   135.6    5001   135.1  5004.3   135.6  5021.4  136.31
  5051.4  136.11  5081.2  137.45  5091.5  137.15  5101.6  137.32  5111.6  136.64
  5131.7   136.3    5242  137.39  5282.1  138.38  5312.1  139.47  5332.2  139.28
  5362.3  138.27  5402.4  138.24  5482.6  138.67  5494.8  138.49  5759.3  140.22
#Mann= 3 ,-1 , 0
    4424     .05       0  4998.3    .035       0  5004.3     .05       0
Bank Sta=4891,5081.2
XS Rating Curve= 0 ,0
Exp/Cntr=0.3,0.1

Type RM Length L Ch R = 1 ,11119   ,663,663,663
BEGIN DESCRIPTION:
Mapping XS f4269552
END DESCRIPTION:
XS GIS Cut Line= 3
      2367788.15     13227468.27      2367220.48     13227259.95
      2365746.53     13227379.74
#Sta/Elev= 30
  4206.3  139.54  4494.4  138.08  4548.6  137.22  4604.2  138.26  4665.2  136.51
  4690.4  136.77  4823.8  135.83    4894  135.56  4914.1  135.83  4974.3  135.13
  4984.3  134.42  5011.4  134.27  5014.2  133.77  5017.4  134.27  5024.5  134.68
  5064.6   134.8  5104.7  136.02  5114.7  135.21  5124.8  135.23  5265.2  136.84
  5315.4  136.82  5355.5  138.28  5415.7  137.69  5465.9   138.5  5526.1  138.57
  5578.3  140.18  5626.4   139.3  5716.7  139.82  6248.5  140.04  6289.8   140.4
#Mann= 3 ,-1 , 0
  4206.3     .05       0  5011.4    .035       0  5017.4     .05       0
Bank Sta=4914.1,5104.7
XS Rating Curve= 0 ,0
Exp/Cntr=0.3,0.1

Type RM Length L Ch R = 1 ,10456   ,924,924,924
BEGIN DESCRIPTION:
Mapping XS 80b2a293
END DESCRIPTION:
XS GIS Cut Line= 3
      2367559.06     13226864.13       2367105.9     13226671.41
      2365913.22     13226801.61
#Sta/Elev= 30
  4358.1  137.02  4464.5  136.07  4511.7  136.88  4569.9  135.54  4783.4  134.37
  4929.2  134.39  4939.2  133.76  4959.4  133.87  4969.4  135.78  4979.5  133.75
  4989.5  133.75  4996.6  133.17  4999.3  132.67  5002.6  133.17  5029.8  133.58
    5070  133.23  5170.6  134.68  5210.8  134.19  5291.3  134.59  5310.9  134.02
  5381.9  134.39  5522.7  136.61  5589.9  136.85  5623.3  138.11  5673.6  137.31
  5784.2  137.84  5834.5  139.19  5894.9  138.07  5925.1  138.89  6050.3  139.19
#Mann= 3 ,-1 , 0
  4358.1     .05       0  4996.6    .035       0  5002.6     .05       0
Bank Sta=4989.5,5029.8
XS Rating Curve= 0 ,0
Exp/Cntr=0.3,0.1

Type RM Length L Ch R = 1 ,9532    ,812,812,812
BEGIN DESCRIPTION:
UNT016 IN BACR 16.0
END DESCRIPTION:
XS GIS Cut Line= 4
      2367631.95     13226739.12      2366923.61      13226103.7
      2366366.32      13225978.7       2365841.5     13226186.55
#Sta/Elev= 30
  3782.8  136.65  3843.8   137.2  3900.6  136.01  4226.5  134.76  4283.4  134.12
  4332.7   135.5  4375.3  133.97  4403.7  134.43  4672.8  133.99  4771.2  132.38
  4822.4  132.26  4842.9  130.85  4863.4  131.07  4873.7  130.95  4884.5  130.06
  4904.4  129.78  4971.1  130.21  4996.6  129.57  5014.5  129.89  5024.4  129.35
  5027.1  128.85  5030.4  129.35  5037.6  130.13  5062.9  131.16  5119.6  132.67
  5140.1   133.6  5149.6  134.55  5241.4  134.28  5302.2  135.33    5870  137.73
#Mann= 3 ,-1 , 0
  3782.8     .05       0  5024.4    .035       0  5030.4     .05       0
Bank Sta=4863.4,5062.9
XS Rating Curve= 0 ,0
Exp/Cntr=0.3,0.1

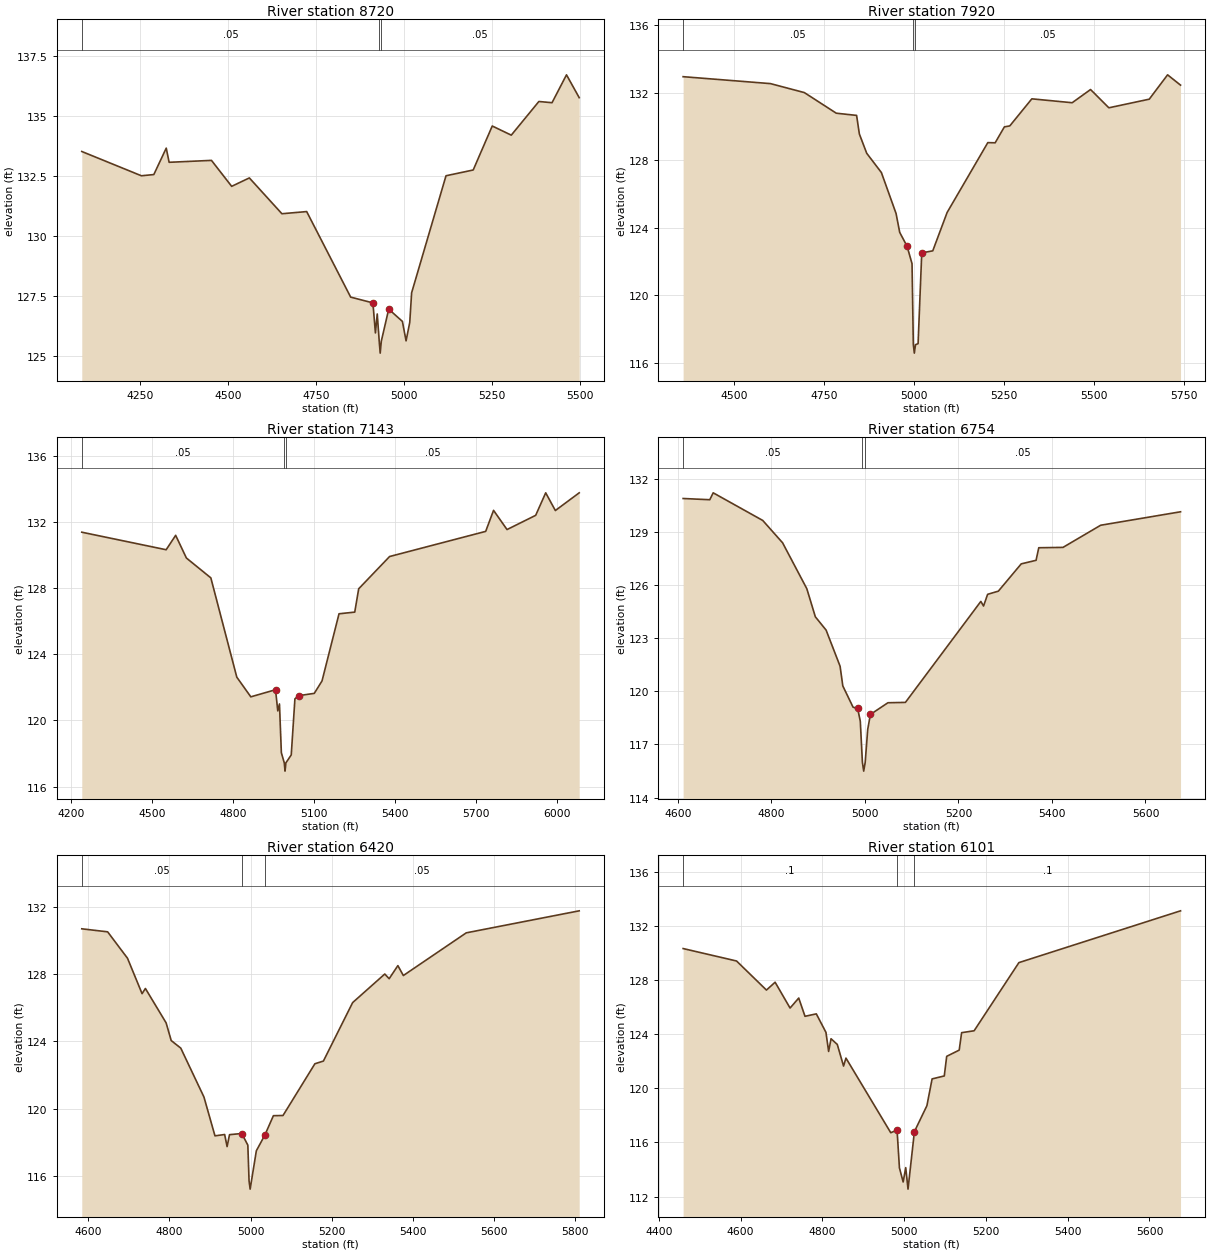
Type RM Length L Ch R = 1 ,8720    ,800,800,800
BEGIN DESCRIPTION:
UNT016 IN BACR 15.0
END DESCRIPTION:
XS GIS Cut Line= 4
      2367298.73     13225993.07      2366958.45     13225555.56
      2366444.56     13225395.84      2366145.95     13225513.89
#Sta/Elev= 30
  4083.8  133.52  4253.2  132.51  4288.5  132.56  4323.8  133.66    4332  133.07
  4452.3  133.15  4509.7  132.07    4560  132.42  4652.5  130.93  4722.9  131.02
  4847.9  127.46  4911.1  127.22  4918.2  125.97  4923.4  126.76    4929  125.63
  4931.8  125.13    4935  125.63    4956  126.96  4994.9  126.45  5005.3  125.64
  5015.8  126.41  5021.1  127.64  5118.8  132.51  5196.1  132.75  5250.2  134.58
  5304.3   134.2  5382.7   135.6  5420.1  135.55  5461.2  136.71  5497.3  135.76
#Mann= 3 ,-1 , 0
  4083.8     .05       0    4929    .035       0    4935     .05       0
Bank Sta=4911.1,4956
XS Rating Curve= 0 ,0
Exp/Cntr=0.3,0.1

Type RM Length L Ch R = 1 ,7920    ,777,777,777
BEGIN DESCRIPTION:
UNT016 IN BACR 14.0
END DESCRIPTION:
XS GIS Cut Line= 3
      2367694.55     13225124.99      2367437.61     13224958.34
      2366382.42      13225166.6
#Sta/Elev= 30
  4357.6  132.94  4600.2  132.53  4694.3     132  4783.1  130.78  4839.5  130.65
  4847.2  129.55  4867.6  128.41  4908.4  127.27  4949.1  124.85  4959.3  123.73
  4979.7  122.91  4993.5  121.88  4997.1  117.09  4999.9  116.59  5003.1  117.09
  5010.3  117.15  5020.5  122.52  5051.1  122.64    5091  124.91    5204  129.04
  5224.4  129.03    5250  129.97  5265.1  130.03  5326.3  131.63  5438.4   131.4
  5489.4  132.18  5540.3   131.1  5652.5  131.61  5703.4  133.05  5739.4  132.44
#Mann= 3 ,-1 , 0
  4357.6     .05       0  4997.1    .035       0  5003.1     .05       0
Bank Sta=4979.7,5020.5
XS Rating Curve= 0 ,0
Exp/Cntr=0.3,0.1

Type RM Length L Ch R = 1 ,7143    ,389,389,389
BEGIN DESCRIPTION:
UNT016 IN BACR 13.0
END DESCRIPTION:
XS GIS Cut Line= 3
      2367251.75     13223645.32      2366991.32     13224187.03
      2366242.01      13225175.7
#Sta/Elev= 30
  4239.4  131.38  4551.8  130.32    4587  131.19  4626.7  129.82  4717.2  128.62
  4813.3  122.62  4865.2  121.43  4956.7  121.86    4965  120.58  4971.3     121
  4978.3  118.05  4989.1  117.44  4991.9  116.94  4995.1  117.44  5014.9  117.92
  5028.5  121.31    5042   121.5  5100.2  121.64  5128.8  122.39  5191.8  126.45
    5250  126.55  5264.6  127.96    5379  129.91  5734.8  131.43  5763.9   132.7
  5813.8  131.54  5919.9   132.4    5957  133.76  5992.7  132.69    6081  133.76
#Mann= 3 ,-1 , 0
  4239.4     .05       0  4989.1    .035       0  4995.1     .05       0
Bank Sta=4956.7,5042
XS Rating Curve= 0 ,0
Exp/Cntr=0.3,0.1

Type RM Length L Ch R = 1 ,6754    ,334,334,334
BEGIN DESCRIPTION:
UNT016 IN BACR 12.0
END DESCRIPTION:
XS GIS Cut Line= 3
      2366891.09     13223749.54      2366708.54       13223941.
      2366312.48     13224635.22
#Sta/Elev= 30
  4611.2  130.88  4668.2  130.81  4675.5   131.2  4781.5  129.64  4823.9  128.38
  4875.7  125.79    4894   124.2    4917  123.45  4946.9  121.41  4952.7   120.3
  4974.6   119.1  4984.4  119.03  4990.1  118.31  4994.6  115.99  4997.4  115.49
  5000.6  115.99    5006  117.85  5011.7  118.69  5049.2  119.35  5086.6  119.37
  5247.9  125.07  5253.7  124.81  5262.4  125.47  5285.4  125.65  5334.3  127.19
    5366  127.39  5371.8   128.1  5423.6  128.12  5504.2  129.37    5675  130.13
#Mann= 3 ,-1 , 0
  4611.2     .05       0  4994.6    .035       0  5000.6     .05       0
Bank Sta=4984.4,5011.7
XS Rating Curve= 0 ,0
Exp/Cntr=0.3,0.1

Type RM Length L Ch R = 1 ,6420    ,319,319,319
BEGIN DESCRIPTION:
Mapping XS 96edd296
END DESCRIPTION:
XS GIS Cut Line= 3
      2366681.79     13223713.93      2366062.89     13224123.56
      2365613.12     13224306.14
#Sta/Elev= 30
  4583.6   130.7  4647.4  130.52  4696.4  128.95  4732.4  126.84  4740.6  127.15
  4791.8   125.1  4804.3  124.05  4827.9   123.6  4885.1  120.69  4912.3  118.38
  4936.2  118.46  4942.2  117.74  4948.2  118.45  4978.3  118.52  4993.4  117.83
  4996.4  115.71  4999.1  115.21  5014.4  117.49  5035.5  118.43  5056.5  119.58
  5080.2  119.59  5158.9  122.67  5179.9  122.83  5252.1  126.31  5331.4  128.01
  5342.2  127.73  5363.7  128.51  5377.2  127.92  5532.5  130.46  5811.2  131.77
#Mann= 3 , 0 , 0
  4583.6     .05       0  4978.3    .035       0  5035.5     .05       0
Bank Sta=4978.3,5035.5
XS Rating Curve= 0 ,0
Exp/Cntr=0.3,0.1

Type RM Length L Ch R = 1 ,6101    ,95,95,95
BEGIN DESCRIPTION:
UNT016 IN BACR 11.0
END DESCRIPTION:
XS GIS Cut Line= 2
      2366553.82     13223452.65      2365522.65     13224098.44
#Sta/Elev= 30
  4459.3  130.34    4590  129.42  4663.1  127.27  4684.3  127.85  4720.9  125.94
  4742.1  126.68  4757.4  125.33  4785.1  125.51  4808.7  124.14  4815.2  122.73
  4821.1  123.67  4836.4  123.25  4851.7  121.65  4857.6  122.24  4967.2  116.72
  4982.6  116.92  4988.4  114.12  4997.5  113.08  5003.8  114.14  5009.4  112.55
    5025   116.8  5055.6  118.72  5068.3   120.7  5098.1  120.92    5104  122.37
  5134.6  122.83  5140.5  124.12  5171.1  124.26  5280.6   129.3    5676  133.13
#Mann= 3 , 0 , 0
  4459.3      .1       0  4982.6     .07       0    5025      .1       0
Bank Sta=4982.6,5025
XS Rating Curve= 0 ,0
Exp/Cntr=0.3,0.1

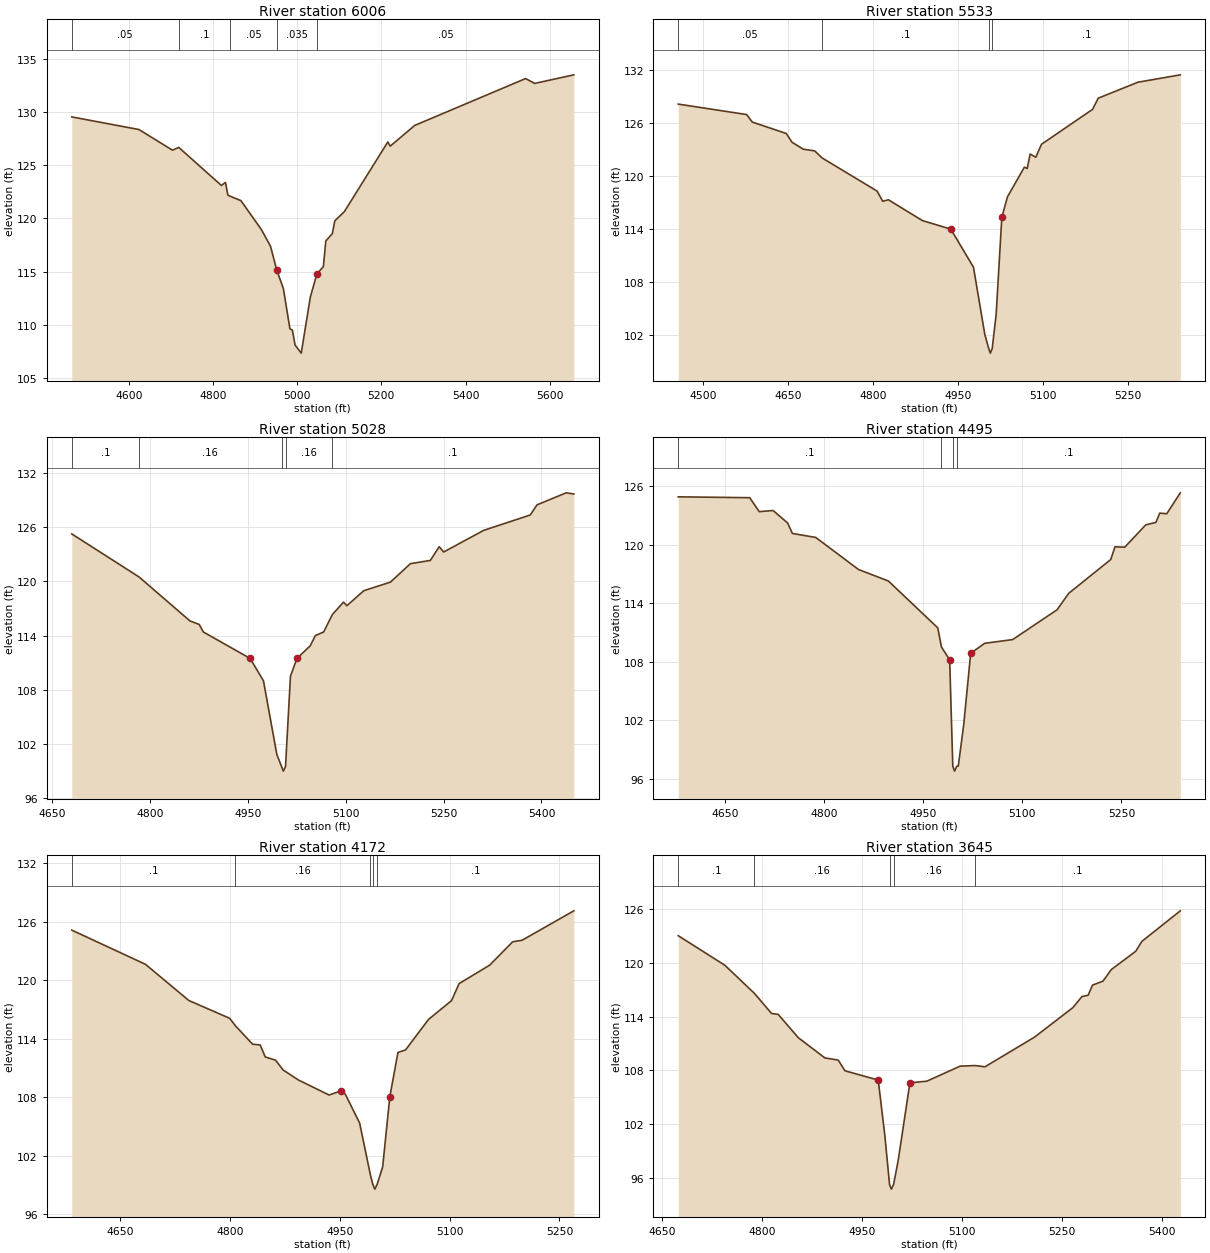
Type RM Length L Ch R = 1 ,6006    ,473,473,473
BEGIN DESCRIPTION:
UNT016 IN BACR 10.0
END DESCRIPTION:
XS GIS Cut Line= 2
      2366491.29     13223390.17      2365471.61     13224009.26
#Sta/Elev= 30
  4464.4  129.56  4624.1  128.37  4703.6  126.43  4718.6  126.69  4819.9  123.11
  4829.6  123.39  4835.4  122.19  4840.5   122.1  4866.3  121.68  4914.9  118.96
  4936.5   117.4  4951.7  115.11  4967.2   113.4  4982.7  109.62  4988.5   109.5
    4995  108.09  5009.6  107.33  5031.2   112.6  5046.7  114.78  5062.2  115.47
    5068  117.88  5083.5  118.58  5089.3  119.78    5112  120.64  5215.3   127.2
  5221.1  126.81  5279.3  128.76  5542.8  133.17  5564.2  132.71  5657.3  133.52
#Mann= 5 ,-1 , 0
  4464.4     .05       0  4718.6      .1       0  4840.5     .05       0
  4951.7    .035       0  5046.7     .05       0
Bank Sta=4951.7,5046.7
XS Rating Curve= 0 ,0
Exp/Cntr=0.3,0.1

Type RM Length L Ch R = 1 ,5533    ,505,505,505
BEGIN DESCRIPTION:
UNT016 IN BACR 9.0
END DESCRIPTION:
XS GIS Cut Line= 2
      2366418.37     13223259.95      2365532.95     13223233.91
#Sta/Elev= 30
  4456.2  128.18  4576.9  126.99  4586.9  126.14  4646.9  124.84  4656.9  123.85
  4676.9  123.06  4696.9  122.87    4710  122.07    4807  118.31    4817  117.15
    4827  117.32    4887  114.96  4937.1  113.99  4977.1  109.67  4997.1  102.04
  5004.1  100.42  5006.8   99.92  5010.1  100.42  5017.1   104.3  5027.1  115.33
  5037.1  117.66  5066.9  121.02  5071.9  120.87  5077.1  122.51  5087.1  122.15
  5097.1  123.62  5187.2  127.58  5197.2  128.85  5267.2  130.66    5342   131.5
#Mann= 4 ,-1 , 0
  4456.2     .05       0    4710      .1       0  5004.1     .07       0
  5010.1      .1       0
Bank Sta=4937.1,5027.1
XS Rating Curve= 0 ,0
Exp/Cntr=0.3,0.1

Type RM Length L Ch R = 1 ,5028    ,533,533,533
BEGIN DESCRIPTION:
UNT016 IN BACR 8.0
END DESCRIPTION:
XS GIS Cut Line= 3
      2366374.54      13222894.6       2365920.4      13222792.2
      2365622.38     13222854.47
#Sta/Elev= 30
  4679.7  125.23  4782.9  120.47    4861  115.61  4875.2  115.22  4881.5  114.39
  4953.2  111.47  4973.7  108.99  4994.2  100.86  5001.5   99.51  5004.2   99.01
  5007.5   99.51  5015.1   109.5    5025  111.46  5045.5  112.87  5053.2  113.99
    5066  114.39  5079.4  116.32  5096.5  117.69  5101.6  117.29  5127.5  118.95
  5168.4   119.9  5199.1  121.94  5229.7   122.3  5243.2  123.82  5250.1  123.23
  5311.4  125.62  5382.9  127.32  5393.2  128.44    5438  129.77  5449.7  129.64
#Mann= 5 ,-1 , 0
  4679.7      .1       0  4782.9     .16       0  5001.5     .07       0
  5007.5     .16       0  5079.4      .1       0
Bank Sta=4953.2,5025
XS Rating Curve= 0 ,0
Exp/Cntr=0.3,0.1

Type RM Length L Ch R = 1 ,4495    ,323,323,323
BEGIN DESCRIPTION:
UNT016 IN BACR 7.0
END DESCRIPTION:
XS GIS Cut Line= 3
      2366340.25     13222535.97      2366087.72     13222346.85
      2365668.39     13222494.33
#Sta/Elev= 30
  4579.2  124.89  4687.4   124.8  4701.9  123.37  4722.8  123.49  4744.8  122.21
    4752  121.14  4787.4  120.73    4852  117.45  4897.3  116.27  4972.1  111.47
  4977.6  109.52  4990.1  108.19  4994.8    97.3  4997.5    96.8  5000.8    97.3
  5003.1   97.31  5011.3  101.53  5021.9  108.87  5043.1  109.89  5085.4  110.27
  5152.6  113.32  5170.3  115.01  5233.9  118.47  5240.3  119.77  5255.1  119.73
  5286.9  122.02  5302.2  122.27  5308.1  123.22  5318.7  123.16  5339.2   125.3
#Mann= 4 ,-1 , 0
  4579.2      .1       0  4977.6     .16       0  4994.8     .07       0
  5000.8      .1       0
Bank Sta=4990.1,5021.9
XS Rating Curve= 0 ,0
Exp/Cntr=0.3,0.1

Type RM Length L Ch R = 1 ,4172    ,527,527,527
BEGIN DESCRIPTION:
UNT016 IN BACR 6.0
END DESCRIPTION:
XS GIS Cut Line= 2
      2366184.03     13222015.16      2365527.82     13222213.06
#Sta/Elev= 30
  4584.2  125.15  4684.8  121.64  4744.1  117.92  4799.7   116.1  4807.6  115.33
    4831  113.44  4841.5  113.36  4848.3  112.13  4862.4   111.8  4872.8  110.79
  4893.7  109.76  4935.5  108.22  4952.4  108.67  4957.7  108.29  4977.2  105.34
  4991.9  100.01  4995.1   99.06  4997.9   98.56  5001.1   99.06  5008.6  100.84
  5018.4  108.05  5029.5  112.59  5039.9  112.85  5071.2  115.98  5102.6  117.91
    5113  119.66  5154.8  121.56  5186.1  123.95    5199  124.11  5269.6  127.13
#Mann= 5 ,-1 , 0
  4584.2      .1       0  4807.6     .16       0  4991.9      .1       0
  4995.1     .07       0  5001.1      .1       0
Bank Sta=4952.4,5018.4
XS Rating Curve= 0 ,0
Exp/Cntr=0.3,0.1

Type RM Length L Ch R = 1 ,3645    ,402,402,402
BEGIN DESCRIPTION:
UNT016 IN BACR 5.0
END DESCRIPTION:
XS GIS Cut Line= 3
      2366087.72     13221646.85      2365737.72     13221646.85
      2365387.73     13221846.85
#Sta/Elev= 30
  4674.7  123.02  4744.7  119.72  4788.9   116.6  4814.7  114.35  4824.7  114.25
  4854.7  111.66  4894.7   109.4  4914.7  109.16  4924.7  107.97  4974.7  106.93
  4984.7  100.69  4991.7   95.28  4994.4   94.78  4997.7   95.28  5004.7   98.01
  5022.2  106.62  5047.7  106.81  5097.4  108.48  5119.9  108.55  5134.8  108.41
    5209  111.71  5266.6     115  5280.2  116.23  5289.6  116.39  5296.1  117.51
  5311.9  117.96  5324.2  119.24  5360.9  121.28  5370.2  122.39  5427.8  125.79
#Mann= 5 ,-1 , 0
  4674.7      .1       0  4788.9     .16       0  4991.7     .07       0
  4997.7     .16       0  5119.9      .1       0
Bank Sta=4974.7,5022.2
XS Rating Curve= 0 ,0
Exp/Cntr=0.3,0.1

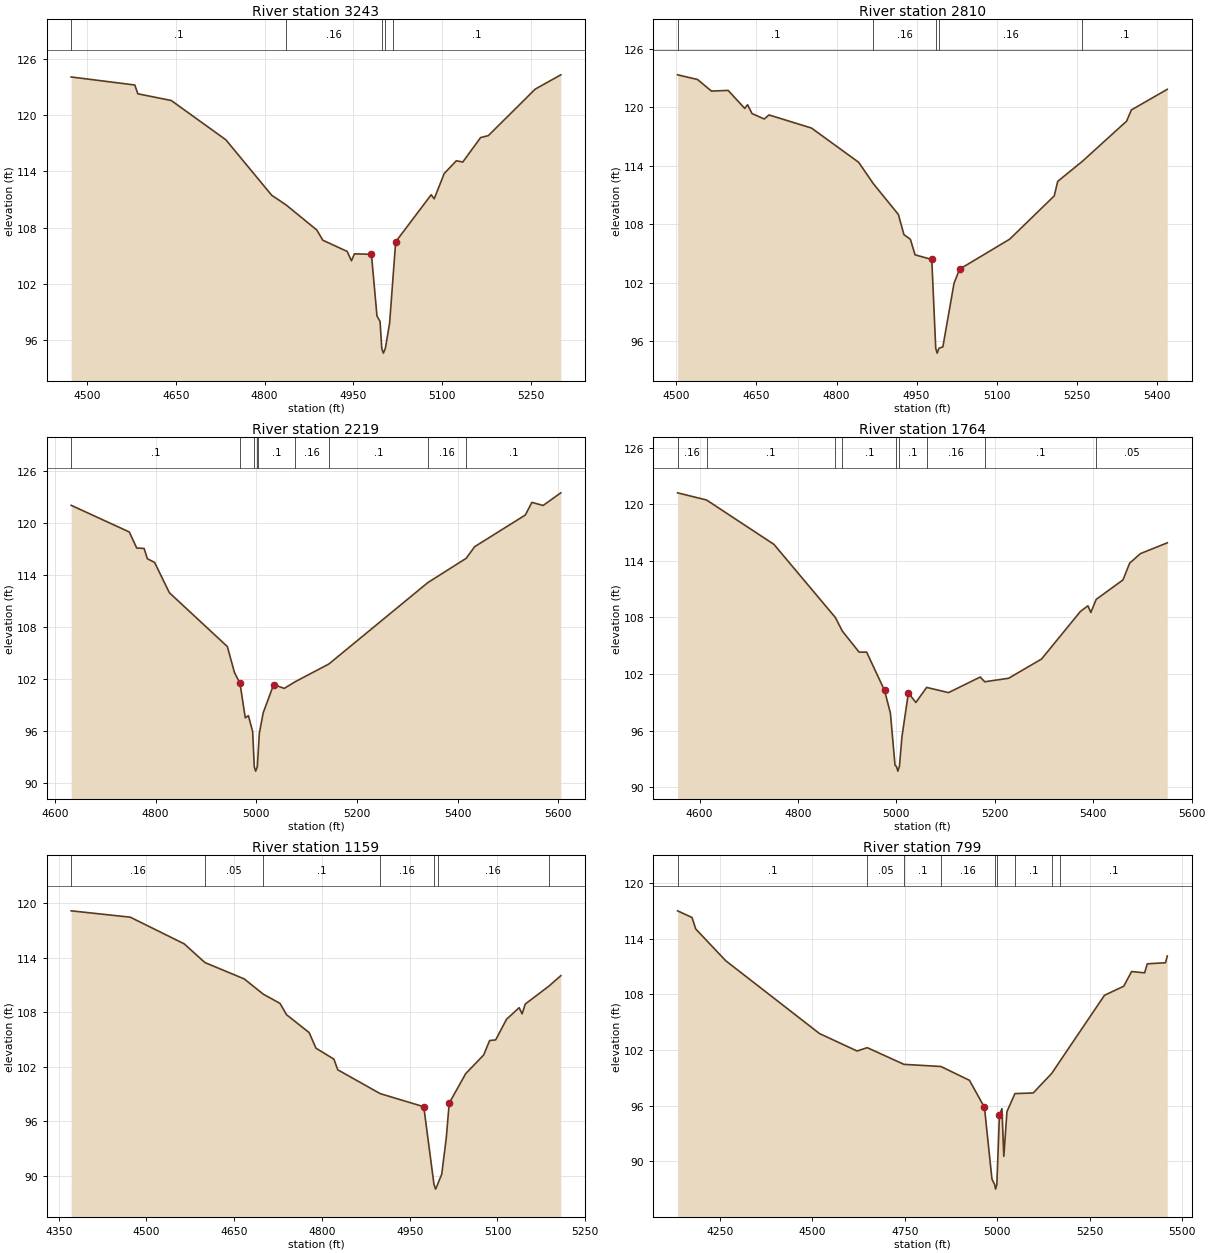
Type RM Length L Ch R = 1 ,3243    ,433,433,433
BEGIN DESCRIPTION:
UNT016 IN BACR 4.0
END DESCRIPTION:
XS GIS Cut Line= 2
      2366152.75     13221187.04      2365345.47     13221369.33
#Sta/Elev= 30
  4473.1  124.12  4580.7  123.26  4585.8  122.32  4642.3   121.6  4734.5   117.4
  4812.1  111.45  4836.6  110.41  4888.3  107.73  4898.5  106.64  4939.6  105.44
  4946.8  104.44    4952  105.18  4980.6  105.13    4990   98.52  4995.2   97.94
  4998.1   95.05  5000.8   94.55  5004.1   95.05  5011.3   97.75  5017.3  102.83
  5021.6  106.47  5081.6  111.51  5086.7  111.08  5103.6  113.78  5124.1  115.15
    5135  115.01  5165.1  117.63  5178.2  117.84  5257.4  122.82  5300.7  124.35
#Mann= 5 ,-1 , 0
  4473.1      .1       0  4836.6     .16       0  4998.1     .07       0
  5004.1     .16       0  5017.3      .1       0
Bank Sta=4980.6,5021.6
XS Rating Curve= 0 ,0
Exp/Cntr=0.3,0.1

Type RM Length L Ch R = 1 ,2810    ,591,591,591
BEGIN DESCRIPTION:
UNT016 IN BACR 3.0
END DESCRIPTION:
XS GIS Cut Line= 3
      2366199.65     13220973.49      2365850.69      13220853.7
      2365324.65     13221009.95
#Sta/Elev= 30
  4502.1  123.35  4539.5  122.87  4565.5  121.68  4596.8  121.75    4628   119.9
  4633.3  120.28  4641.6  119.37  4664.6  118.81  4673.3  119.23  4753.1  117.88
  4841.5  114.36  4868.9  112.17  4915.9     109  4926.3  106.93  4938.4  106.45
  4947.2  104.85  4978.5  104.38  4985.9   95.25  4988.6   94.75  4991.9   95.25
  4999.3    95.4  5020.2  101.93  5030.6  103.38  5124.5  106.46    5208  110.91
  5214.5   112.4  5260.9  114.47  5343.6  118.59  5352.5  119.74  5419.8  121.86
#Mann= 5 ,-1 , 0
  4502.1      .1       0  4868.9     .16       0  4985.9     .07       0
  4991.9     .16       0  5260.9      .1       0
Bank Sta=4978.5,5030.6
XS Rating Curve= 0 ,0
Exp/Cntr=0.3,0.1

Type RM Length L Ch R = 1 ,2219    ,455,455,455
BEGIN DESCRIPTION:
UNT016 IN BACR 2.0
END DESCRIPTION:
XS GIS Cut Line= 3
      2365840.29     13220187.02      2365366.32     13220530.78
      2365122.55      13220831.6
#Sta/Elev= 30
  4632.3  122.03  4747.8  118.95  4762.5   117.1  4777.2  117.05  4783.7  115.86
    4798  115.44  4827.4  111.94  4942.6  105.72  4956.7  102.73  4967.7  101.48
  4978.2   97.49  4984.4   97.75  4992.9   95.89  4996.1   91.84  4998.8   91.34
  5002.1   91.84  5003.9   93.58  5006.1   95.71  5013.8   98.08  5034.6  101.34
  5055.5  100.89  5077.6  101.67  5144.3  103.71  5340.7   113.1    5417  115.91
    5434  117.26  5534.5  120.91  5547.5  122.37  5569.8  122.01    5605  123.47
#Mann= 9 ,-1 , 0
  4632.3      .1       0  4967.7     .16       0  4996.1     .07       0
  5002.1     .16       0  5003.9      .1       0  5077.6     .16       0
  5144.3      .1       0  5340.7     .16       0    5417      .1       0
Bank Sta=4967.7,5034.6
XS Rating Curve= 0 ,0
Exp/Cntr=0.3,0.1

Type RM Length L Ch R = 1 ,1764    ,605,605,605
BEGIN DESCRIPTION:
Mapping XS 7287fa96
END DESCRIPTION:
XS GIS Cut Line= 3
      2365648.75     13219897.92      2365466.22     13219933.54
      2364781.59     13220364.77
#Sta/Elev= 30
  4555.3  121.21  4614.2  120.45  4751.1  115.75  4876.1  107.99  4890.1  106.56
  4924.2  104.33  4939.5  104.33  4975.9  100.27  4987.8   97.87  4997.2   92.33
  5000.1   92.22  5002.9   91.72  5006.1   92.22  5011.3   95.38  5024.3   99.99
  5039.6      99  5061.4  100.59  5105.9  100.04  5170.3  101.69  5179.5  101.19
    5228  101.56    5295   103.6  5373.9  108.64  5389.2  109.24  5395.1  108.53
    5406  109.92  5460.4  111.98    5474  113.76  5495.9  114.77  5550.4  115.91
#Mann= 9 ,-1 , 0
  4555.3     .16       0  4614.2      .1       0  4876.1     .05       0
  4890.1      .1       0  5000.1     .07       0  5006.1      .1       0
  5061.4     .16       0  5179.5      .1       0    5406     .05       0
Bank Sta=4975.9,5024.3
XS Rating Curve= 0 ,0
Exp/Cntr=0.3,0.1

Type RM Length L Ch R = 1 ,1159    ,360,360,360
BEGIN DESCRIPTION:
Mapping XS 229ff06f
END DESCRIPTION:
XS GIS Cut Line= 3
      2365626.52     13219759.88      2364896.27     13219599.58
      2364807.25     13219608.49
#Sta/Elev= 30
  4371.2  119.15  4472.3  118.45  4564.5  115.52  4599.9  113.46  4666.9  111.67
  4699.8  109.98  4728.3  108.97  4739.4  107.73  4778.1  105.76  4789.7  104.05
  4820.4  102.84    4827  101.67  4899.5   99.05    4974   97.61  4991.5   89.05
  4994.2   88.55  4997.5   89.05  5004.7   90.19  5012.4   94.13  5017.5   98.01
  5045.7  101.25  5076.4   103.3  5086.6  104.89  5096.9  104.96  5115.5  107.23
  5137.1   108.5  5142.1  107.82  5147.5   108.9  5187.7  110.86  5208.3  112.02
#Mann= 7 ,-1 , 0
  4371.2     .16       0  4599.9     .05       0  4699.8      .1       0
  4899.5     .16       0  4991.5     .07       0  4997.5     .16       0
  5187.7      .1       0
Bank Sta=4974,5017.5
XS Rating Curve= 0 ,0
Exp/Cntr=0.3,0.1

Type RM Length L Ch R = 1 ,799     ,571,571,571
BEGIN DESCRIPTION:
Mapping XS 1d2ecba7
END DESCRIPTION:
XS GIS Cut Line= 4
      2366116.29     13219421.47      2365533.01     13219323.51
      2364958.61     13219421.47      2364852.22     13219527.86
#Sta/Elev= 30
  4135.4  116.99  4174.5  116.27  4184.6  115.03  4265.8  111.61  4519.3  103.77
  4620.9  101.89  4648.5  102.25  4747.8  100.45  4847.8  100.22    4925   98.73
  4965.5   95.82  4985.8   88.09    4993   87.51  4995.7   87.01    4999   87.51
  5006.1   95.02  5012.8   95.68  5017.9   90.54  5026.4   95.37    5048    97.3
  5097.4   97.37    5148    99.5  5169.3  100.77  5290.2  107.89  5342.3  108.87
  5363.5  110.45  5398.8  110.31  5405.9  111.28  5455.4   111.4    5460  112.13
#Mann= 9 ,-1 , 0
  4135.4      .1       0  4648.5     .05       0  4747.8      .1       0
  4847.8     .16       0    4993     .07       0    4999     .16       0
    5048      .1       0    5148     .16       0  5169.3      .1       0
Bank Sta=4965.5,5006.1
XS Rating Curve= 0 ,0
Exp/Cntr=0.3,0.1

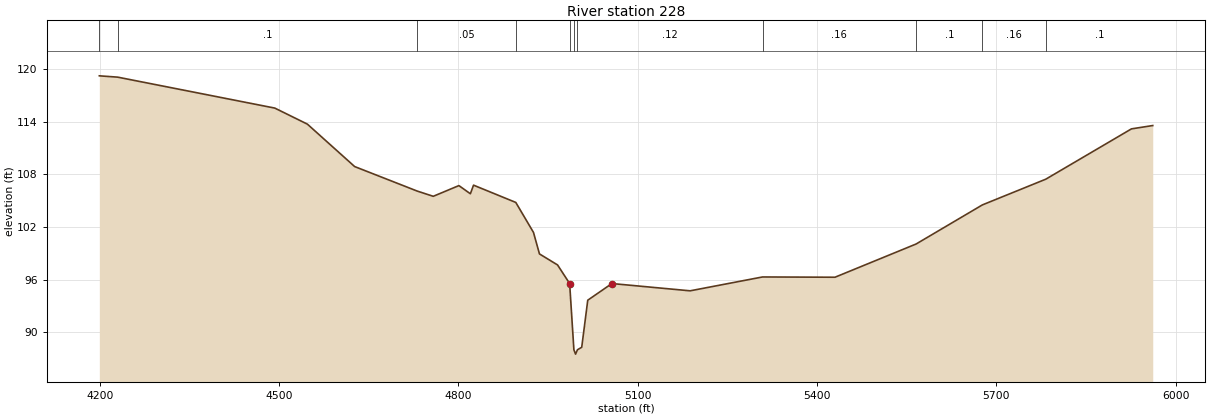
Type RM Length L Ch R = 1 ,228     ,0,0,0
BEGIN DESCRIPTION:
UNT016 IN BACR 1.0
END DESCRIPTION:
XS GIS Cut Line= 4
      2366178.81     13219056.82      2365559.03     13218817.24
      2365178.82     13218869.32      2364837.71     13219496.87
#Sta/Elev= 30
  4199.4  119.24    4230  119.09    4493  115.56  4547.5  113.73  4626.6  108.89
  4731.1   106.1  4758.1   105.5    4801  106.72  4820.2  105.79  4825.5  106.77
  4896.2   104.8  4925.8  101.38  4935.8   98.93  4966.1   97.67  4986.3   95.55
  4986.9   94.91  4993.4      88  4996.2    87.5  4999.4      88  5006.5   88.28
  5016.6   93.65    5057   95.55  5187.9   94.72    5309    96.3  5430.3   96.27
    5566  100.06  5676.9  104.52  5782.9  107.45  5926.3  113.19  5961.9  113.57
#Mann= 11 ,-1 , 0
  4199.4     .05       0    4230      .1       0  4731.1     .05       0
  4896.2     .16       0  4986.9     .12       0  4993.4     .07       0
  4999.4     .12       0    5309     .16       0    5566      .1       0
  5676.9     .16       0  5782.9      .1       0
Bank Sta=4986.3,5057
XS Rating Curve= 0 ,0
Exp/Cntr=0.3,0.1

Chan Stop Cuts=-1
Use User Specified Reach Order=0
Composite Channel Slope=5