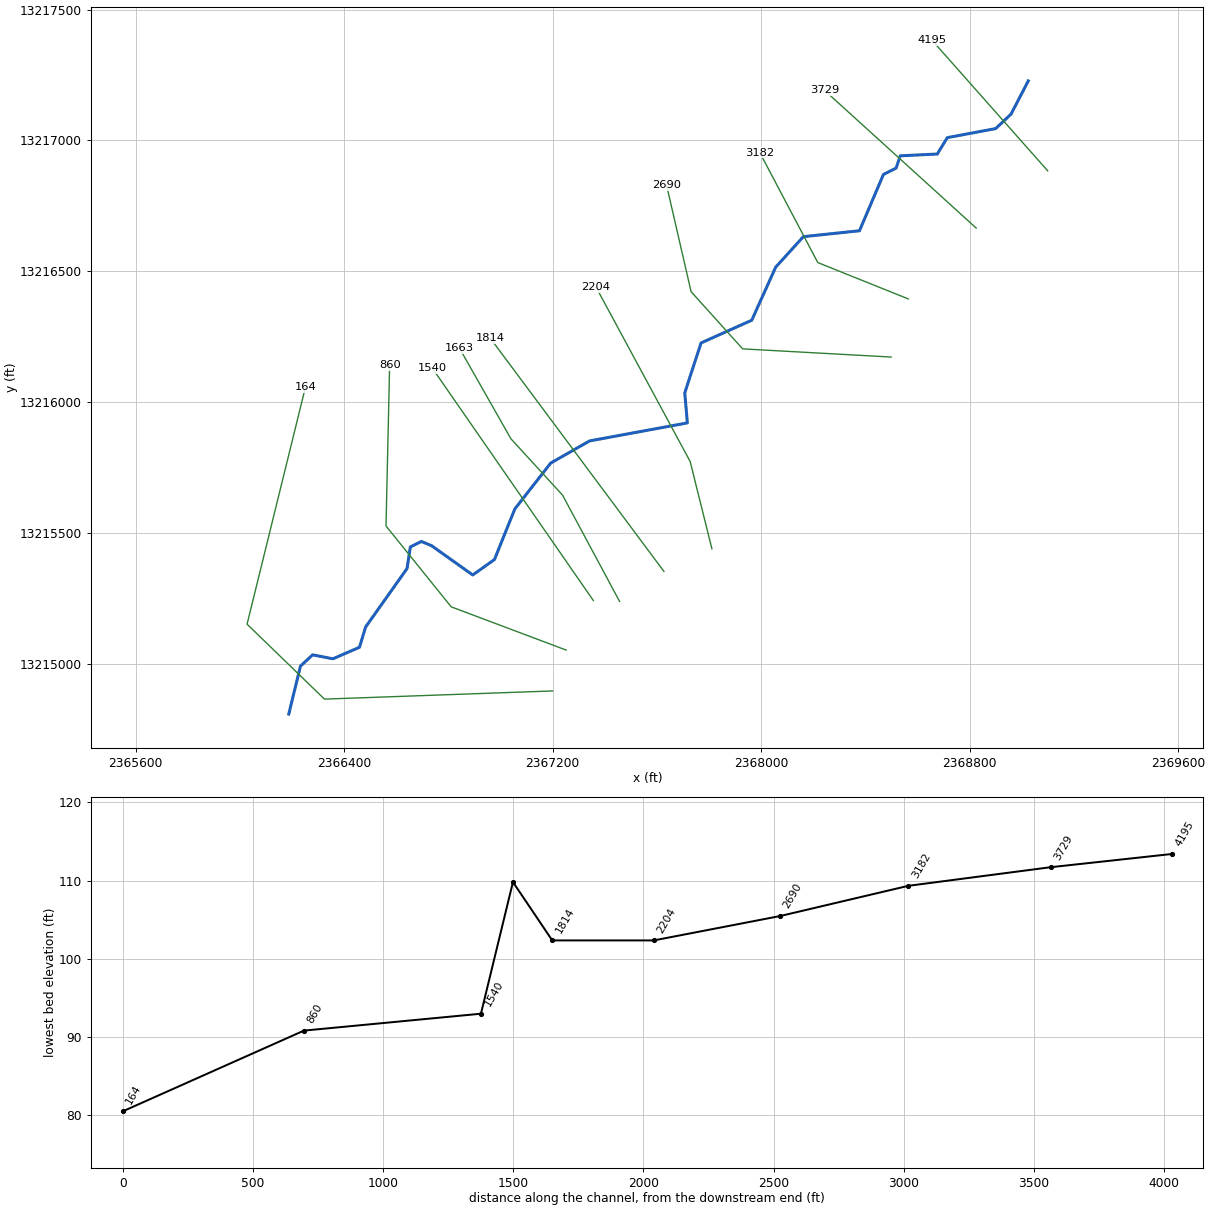
--- UNT017 IN BACR.prj (project) ---

Proj Title=UNT017 IN BACR Base Level Engineering
Current Plan=p01
Default Exp/Contr=0.3,0.1
English Units
Geom File=g01
Flow File=f01
Plan File=p01
BEGIN DESCRIPTION:
UNT017 IN BACR
END DESCRIPTION:

--- UNT017 IN BACR.p01 (plan) ---

Plan Title=Multiple Run
Short Identifier=Multiple
Geom File=g01
Flow File=f01
Subcritical Flow
K Sum by GR= 0
Std Step Tol= 0.01
Critical Tol= 0.01
Num of Std Step Trials= 20
Max Error Tol= 0.3
Flow Tol Ratio= 0.001
Split Flow NTrial= 30
Split Flow Tol= 0.02
Split Flow Ratio= 0.02
Log Output Level= 0
Friction Slope Method= 1
Unsteady Friction Slope Method= 2
Unsteady Bridges Friction Slope Method= 1
Parabolic Critical Depth
Global Vel Dist=  1 , 1 , 1
Global Log Level= 0
CheckData=True
Encroach Param= -1, 0, 0, 0
BEGIN DESCRIPTION:
Multiple Run
END DESCRIPTION:

--- UNT017 IN BACR.f01 (steady flow) ---

Flow Title=Multiple
Number of Profiles=7
Profile Names=10-year,25-year,50-year,1pct_min,100-year,1pct_plu,500-year
River Rch & RM= UNT017 IN BACR,Reach-1,4195
     568     774     941     833    1127    1524    1622
Boundary for River Rch & Prof#=UNT017 IN BACR,Reach-1,1
Up Type=0
Dn Type=3
Dn Slope=0.005
Boundary for River Rch & Prof#=UNT017 IN BACR,Reach-1,2
Up Type=0
Dn Type=3
Dn Slope=0.005
Boundary for River Rch & Prof#=UNT017 IN BACR,Reach-1,3
Up Type=0
Dn Type=3
Dn Slope=0.005
Boundary for River Rch & Prof#=UNT017 IN BACR,Reach-1,4
Up Type=0
Dn Type=3
Dn Slope=0.005
Boundary for River Rch & Prof#=UNT017 IN BACR,Reach-1,5
Up Type=0
Dn Type=3
Dn Slope=0.005
Boundary for River Rch & Prof#=UNT017 IN BACR,Reach-1,6
Up Type=0
Dn Type=3
Dn Slope=0.005
Boundary for River Rch & Prof#=UNT017 IN BACR,Reach-1,7
Up Type=0
Dn Type=3
Dn Slope=0.005

--- UNT017 IN BACR.g01 (geometry) ---

Geom Title=Existing Conditions

River Reach=UNT017 IN BACR,Reach-1
Reach XY= 30
      2369024.41     13217227.41      2368958.44     13217100.68
      2368899.41     13217045.12      2368713.64     13217010.40
      2368675.45     13216947.90      2368533.09     13216940.95
      2368517.46     13216894.08      2368468.85     13216869.77
      2368376.84     13216654.49      2368161.56     13216631.93
      2368055.66     13216515.61      2367963.64     13216312.48
      2367769.20     13216225.68      2367706.70     13216034.70
      2367716.72     13215920.01      2367341.90     13215851.17
      2367192.60     13215766.56      2367054.92     13215591.09
      2366976.63     13215397.57      2366893.35     13215338.58
      2366735.48     13215450.68      2366696.34     13215466.77
      2366654.12     13215445.96      2366641.42     13215363.30
      2366482.39     13215139.58      2366459.02     13215062.28
      2366357.08     13215018.28      2366279.11     13215033.37
      2366232.48     13214989.91      2366187.72     13214806.86

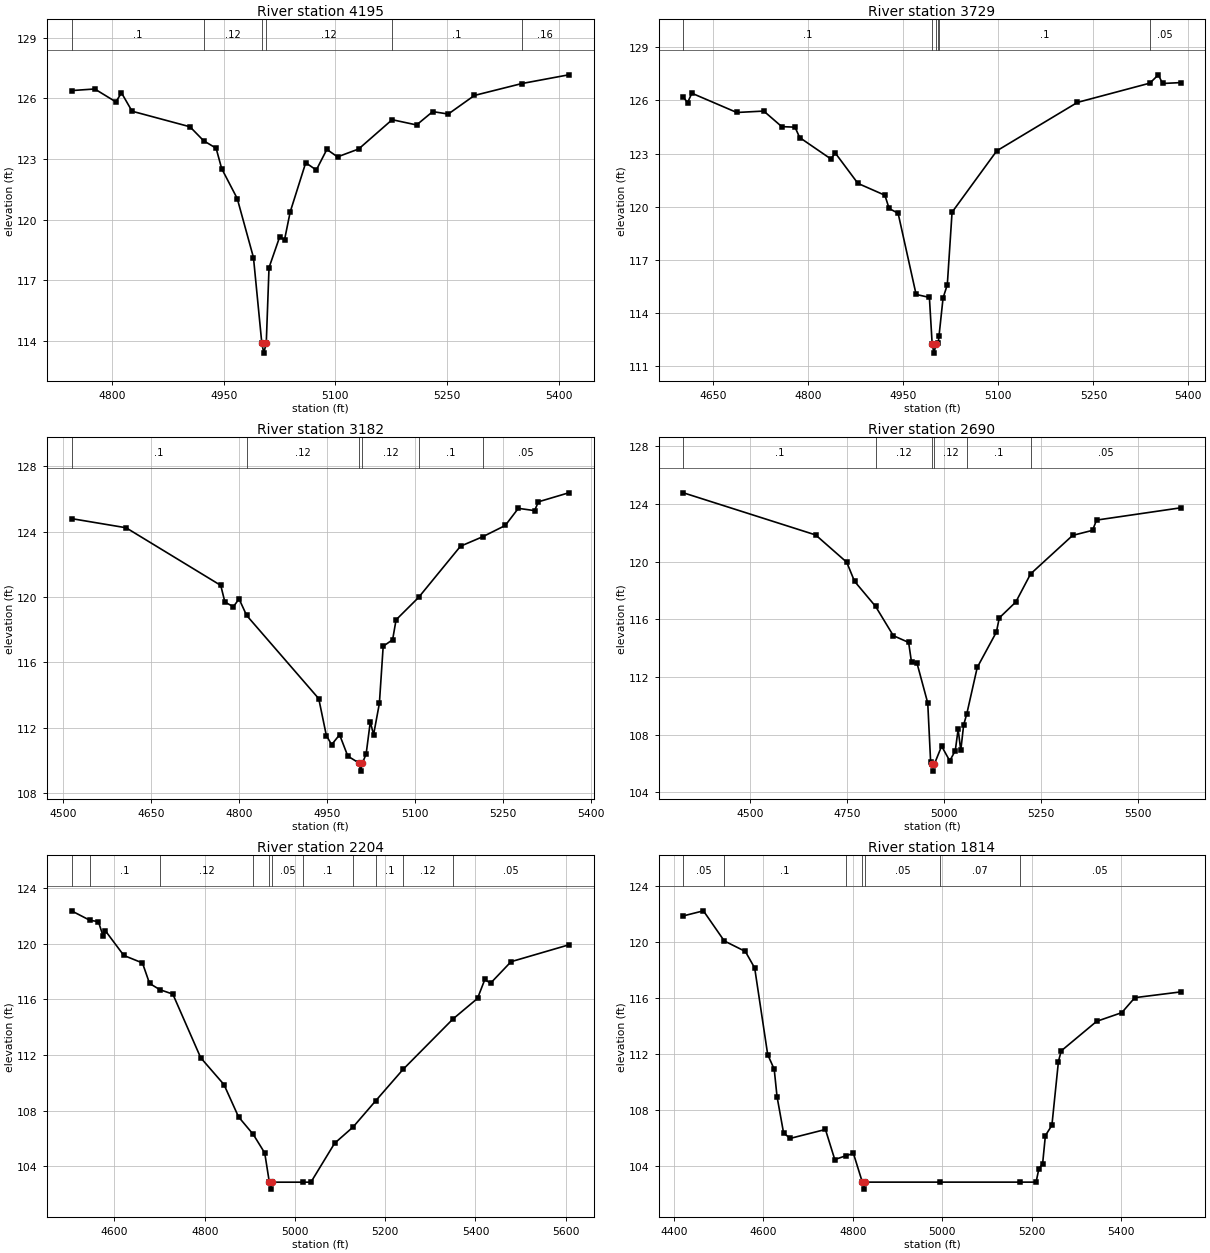
Type RM Length L Ch R = 1,4195,466,466,466
BEGIN DESCRIPTION:
UNT017 IN BACR 8.0
END DESCRIPTION:
XS GIS Cut Line= 2
      2369098.95     13216883.57      2368655.28     13217382.69
#Sta/Elev= 30
  4745.5  126.39  4776.7  126.47  4805.1  125.83  4812.6  126.28  4826.8  125.37
  4904.6  124.60  4922.9  123.91  4939.7  123.54  4947.2  122.53  4968.1  121.05
  4989.9  118.13  5001.1  113.90  5003.8  113.40  5007.1  113.90  5010.8  117.63
  5025.0  119.14  5031.7  119.02  5039.2  120.38  5060.1  122.82  5074.3  122.46
  5088.5  123.48  5102.8  123.11  5131.2  123.50  5176.2  124.95  5209.0  124.69
  5230.7  125.35  5251.6  125.23  5286.7  126.15  5350.6  126.74  5413.3  127.17
#Mann=6,-1,0
  4745.5     0.1       0  4922.9    0.12       0  5001.1    0.07       0
  5007.1    0.12       0  5176.2     0.1       0  5350.6    0.16       0
Bank Sta=5001.1,5007.1
Exp/Cntr=0.3,0.1

Type RM Length L Ch R = 1,3729,547,547,547
BEGIN DESCRIPTION:
UNT017 IN BACR 7.0
END DESCRIPTION:
XS GIS Cut Line= 2
      2368824.69     13216664.78      2368242.43     13217191.58
#Sta/Elev= 30
  4602.5  126.18  4609.1  125.88  4615.8  126.41  4686.8  125.32  4729.4  125.40
  4757.8  124.52  4778.7  124.49  4786.2  123.90  4835.5  122.69  4842.3  123.03
  4878.1  121.31  4920.7  120.64  4927.4  119.89  4941.6  119.62  4970.0  115.03
  4991.0  114.86  4995.4  112.21  4998.2  111.71  5001.4  112.21  5005.0  112.31
  5006.2  112.68  5012.6  114.83  5019.3  115.58  5026.8  119.68  5097.4  123.15
  5224.8  125.89  5339.2  126.98  5352.6  127.45  5359.3  126.96  5387.7  127.01
#Mann=6,-1,0
  4602.5     0.1       0  4995.4    0.07       0  5001.4     0.1       0
  5005.0    0.12       0  5006.2     0.1       0  5339.2    0.05       0
Bank Sta=4995.4,5001.4
Exp/Cntr=0.3,0.1

Type RM Length L Ch R = 1,3182,492,492,492
BEGIN DESCRIPTION:
UNT017 IN BACR 6.0
END DESCRIPTION:
XS GIS Cut Line= 3
      2368564.19     13216393.99      2368217.01     13216532.87
      2367995.08     13216952.46
#Sta/Elev= 30
  4513.9  124.80  4607.0  124.24  4768.6  120.71  4775.7  119.69  4790.1  119.40
  4799.9  119.88  4812.8  118.87  4935.9  113.77  4948.9  111.51  4957.9  110.95
  4971.5  111.56  4985.5  110.25  5004.5  109.83  5007.3  109.33  5010.5  109.83
  5016.8  110.38  5023.9  112.35  5029.5  111.56  5039.4  113.48  5045.9  116.98
  5062.0  117.38  5067.9  118.60  5106.3  119.97  5177.9  123.11  5216.4  123.70
  5254.3  124.38  5276.6  125.43  5304.3  125.29  5310.9  125.83  5362.5  126.38
#Mann=6,-1,0
  4513.9     0.1       0  4812.8    0.12       0  5004.5    0.07       0
  5010.5    0.12       0  5106.3     0.1       0  5216.4    0.05       0
Bank Sta=5004.5,5010.5
Exp/Cntr=0.3,0.1

Type RM Length L Ch R = 1,2690,486,486,486
BEGIN DESCRIPTION:
UNT017 IN BACR 5.0
END DESCRIPTION:
XS GIS Cut Line= 4
      2368498.31     13216171.75      2367928.82     13216203.00
      2367730.90     13216421.75      2367637.15     13216828.03
#Sta/Elev= 30
  4327.2  124.76  4668.3  121.84  4748.4  119.95  4768.5  118.63  4822.8  116.89
  4868.6  114.86  4908.1  114.39  4915.5  113.02  4929.7  112.95  4957.4  110.19
  4964.8  106.13  4968.6  105.97  4971.3  105.47  4974.6  105.97  4993.2  107.20
  5014.2  106.18  5028.4  106.89  5035.8  108.37  5042.6  106.90  5050.0  108.67
  5058.2  109.45  5085.1  112.66  5134.5  115.11  5141.9  116.09  5184.5  117.19
  5222.7  119.14  5331.2  121.81  5382.5  122.16  5392.8  122.87  5609.5  123.72
#Mann=6,-1,0
  4327.2     0.1       0  4822.8    0.12       0  4968.6    0.07       0
  4974.6    0.12       0  5058.2     0.1       0  5222.7    0.05       0
Bank Sta=4968.6,4974.6
Exp/Cntr=0.3,0.1

Type RM Length L Ch R = 1,2204,390,390,390
BEGIN DESCRIPTION:
UNT017 IN BACR 4.0
END DESCRIPTION:
XS GIS Cut Line= 3
      2367810.77     13215439.08      2367727.43     13215772.45
      2367366.32     13216439.11
#Sta/Elev= 30
  4504.8  122.37  4546.0  121.68  4564.3  121.60  4574.4  120.59  4579.5  120.95
  4620.7  119.16  4662.0  118.62  4677.7  117.15  4700.4  116.70  4729.3  116.38
  4791.1  111.80  4842.7  109.87  4874.9  107.55  4907.7  106.28  4933.0  104.95
  4943.2  102.85  4945.9  102.35  4949.2  102.85  5018.3  102.85  5035.4  102.85
  5087.9  105.65  5128.9  106.82  5178.8  108.70  5239.5  110.96  5350.2  114.59
  5404.6  116.07  5420.8  117.43  5433.4  117.16  5478.9  118.71  5606.6  119.92
#Mann=11,-1,0
  4504.8    0.05       0  4546.0     0.1       0  4700.4    0.12       0
  4907.7    0.05       0  4943.2   0.033       0  4949.2    0.05       0
  5018.3     0.1       0  5128.9    0.12       0  5178.8     0.1       0
  5239.5    0.12       0  5350.2    0.05       0
Bank Sta=4943.2,4949.2
Exp/Cntr=0.3,0.1

Type RM Length L Ch R = 1,1814,151,151,151
BEGIN DESCRIPTION:
UNT017 IN BACR 3.0
END DESCRIPTION:
XS GIS Cut Line= 2
      2367626.71     13215352.34      2366961.11     13216243.27
#Sta/Elev= 30
  4421.0  121.86  4465.7  122.22  4512.4  120.07  4559.5  119.32  4580.4  118.14
  4609.5  111.96  4624.1  110.91  4630.4  108.96  4645.0  106.37  4659.6  105.97
  4738.7  106.61  4759.6  104.46  4784.0  104.73  4801.3  104.90  4821.2  102.85
  4824.0  102.35  4827.2  102.85  4995.2  102.85  5173.6  102.85  5209.9  102.85
  5216.1  103.80  5224.5  104.15  5230.7  106.17  5245.3  106.91  5259.9  111.46
  5266.1  112.22  5345.4  114.33  5401.6  114.95  5430.8  116.02  5533.1  116.43
#Mann=7,-1,0
  4421.0    0.05       0  4512.4     0.1       0  4784.0    0.05       0
  4821.2    0.07       0  4827.2    0.05       0  4995.2    0.07       0
  5173.6    0.05       0
Bank Sta=4821.2,4827.2
Exp/Cntr=0.3,0.1

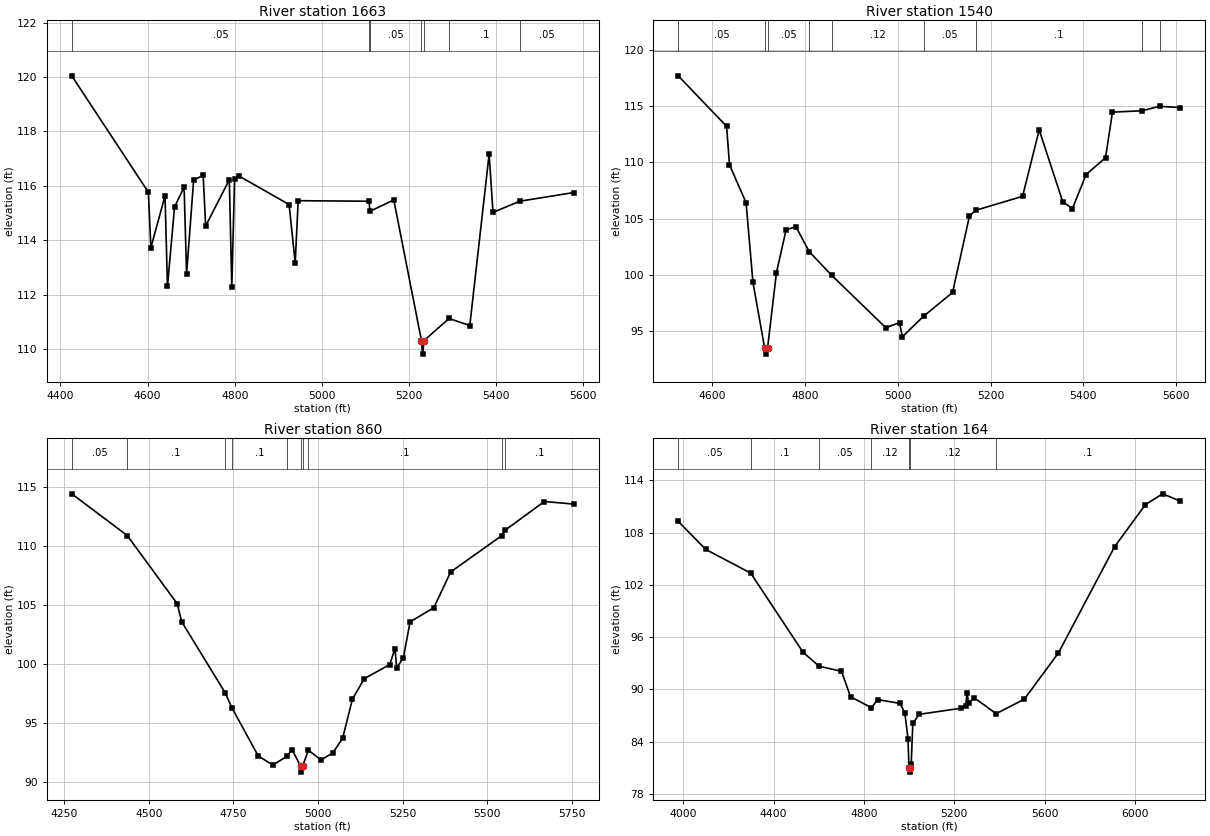
Type RM Length L Ch R = 1,1663,123,123,123
BEGIN DESCRIPTION:
Mapping XS 503a2a3e
END DESCRIPTION:
XS GIS Cut Line= 4
      2367456.57     13215237.77      2367237.85     13215643.98
      2367039.93     13215859.25      2366842.39     13216205.82
#Sta/Elev= 30
  4425.9  120.04  4601.8  115.76  4607.5  113.72  4640.0  115.63  4645.6  112.30
  4661.9  115.22  4683.8  115.95  4689.5  112.76  4705.7  116.21  4727.6  116.38
  4733.3  114.52  4787.6  116.22  4793.3  112.27  4799.7  116.26  4809.5  116.36
  4924.8  115.31  4938.9  113.17  4945.7  115.45  5108.3  115.43  5110.6  115.06
  5165.2  115.48  5228.7  110.31  5231.4  109.81  5234.7  110.31  5292.1  111.12
  5339.7  110.86  5384.1  117.16  5393.0  115.02  5454.1  115.43  5578.6  115.75
#Mann=7,-1,0
  4425.9    0.05       0  5108.3    0.07       0  5110.6    0.05       0
  5228.7    0.04       0  5234.7    0.05       0  5292.1     0.1       0
  5454.1    0.05       0
Bank Sta=5228.7,5234.7
Exp/Cntr=0.3,0.1

Type RM Length L Ch R = 1,1540,680,680,680
BEGIN DESCRIPTION:
UNT017 IN BACR 2.0
END DESCRIPTION:
XS GIS Cut Line= 2
      2367355.88     13215241.23      2366737.85     13216130.08
#Sta/Elev= 30
  4526.4  117.67  4630.7  113.19  4636.9  109.78  4672.7  106.41  4687.5   99.34
  4712.9   93.48  4715.7   92.98  4718.9   93.48  4738.2  100.22  4759.1  104.02
  4780.1  104.29  4809.0  102.06  4856.9   99.99  4973.8   95.33  5003.5   95.77
  5009.6   94.52  5055.4   96.34  5117.9   98.45  5154.4  105.24  5167.8  105.74
  5268.9  106.98  5304.7  112.87  5355.3  106.52  5376.2  105.88  5405.9  108.91
  5447.8  110.41  5462.7  114.45  5526.6  114.57  5564.5  114.97  5609.0  114.85
#Mann=9,-1,0
  4526.4    0.05       0  4712.9    0.07       0  4718.9    0.05       0
  4809.0     0.1       0  4856.9    0.12       0  5055.4    0.05       0
  5167.8     0.1       0  5526.6    0.05       0  5564.5     0.1       0
Bank Sta=4712.9,4718.9
Exp/Cntr=0.3,0.1

Type RM Length L Ch R = 1,860,696,696,696
BEGIN DESCRIPTION:
Mapping XS 8d235824
END DESCRIPTION:
XS GIS Cut Line= 4
      2367251.77     13215051.60      2366810.76     13215216.89
      2366560.76     13215525.92      2366574.65     13216140.51
#Sta/Elev= 30
  4272.7  114.39  4436.5  110.86  4584.1  105.09  4597.4  103.56  4725.9   97.54
  4745.9   96.26  4823.6   92.19  4866.8   91.42  4907.7   92.15  4923.7   92.73
  4948.6   91.32  4951.3   90.82  4954.6   91.32  4971.7   92.68  5009.1   91.85
  5044.3   92.46  5073.0   93.70  5101.8   97.01  5137.0   98.74  5212.1   99.93
  5227.5  101.29  5232.5   99.67  5252.1  100.48  5272.1  103.55  5342.1  104.74
  5392.2  107.78  5543.0  110.85  5552.6  111.30  5668.8  113.74  5755.9  113.52
#Mann=10,-1,0
  4272.7    0.05       0  4436.5     0.1       0  4725.9    0.05       0
  4745.9     0.1       0  4907.7    0.12       0  4948.6    0.07       0
  4954.6    0.12       0  4971.7     0.1       0  5543.0    0.05       0
  5552.6     0.1       0
Bank Sta=4948.6,4954.6
Exp/Cntr=0.3,0.1

Type RM Length L Ch R = 1,164,0,0,0
BEGIN DESCRIPTION:
UNT017 IN BACR 1.0
END DESCRIPTION:
XS GIS Cut Line= 4
      2367199.60     13214895.36      2366324.65     13214864.12
      2366027.78     13215150.57      2366251.74     13216056.86
#Sta/Elev= 30
  3978.4  109.30  4100.4  106.07  4298.9  103.36  4530.6   94.27  4601.7   92.66
  4700.7   92.08  4740.8   89.16  4833.4   87.89  4860.8   88.83  4959.9   88.39
  4981.0   87.31  4995.1   84.31  4999.3   81.00  5002.1   80.50  5005.3   81.00
  5009.3   81.47  5016.4   86.09  5044.5   87.14  5228.4   87.83  5249.8   88.12
  5256.7   89.59  5263.0   88.42  5287.7   89.05  5385.0   87.21  5509.8   88.88
  5660.7   94.19  5909.4  106.39  6045.5  111.22  6121.7  112.46  6200.0  111.63
#Mann=7,-1,0
  3978.4    0.05       0  4298.9     0.1       0  4601.7    0.05       0
  4833.4    0.12       0  4999.3    0.07       0  5005.3    0.12       0
  5385.0     0.1       0
Bank Sta=4999.3,5005.3
Exp/Cntr=0.3,0.1

Chan Stop Cuts=-1