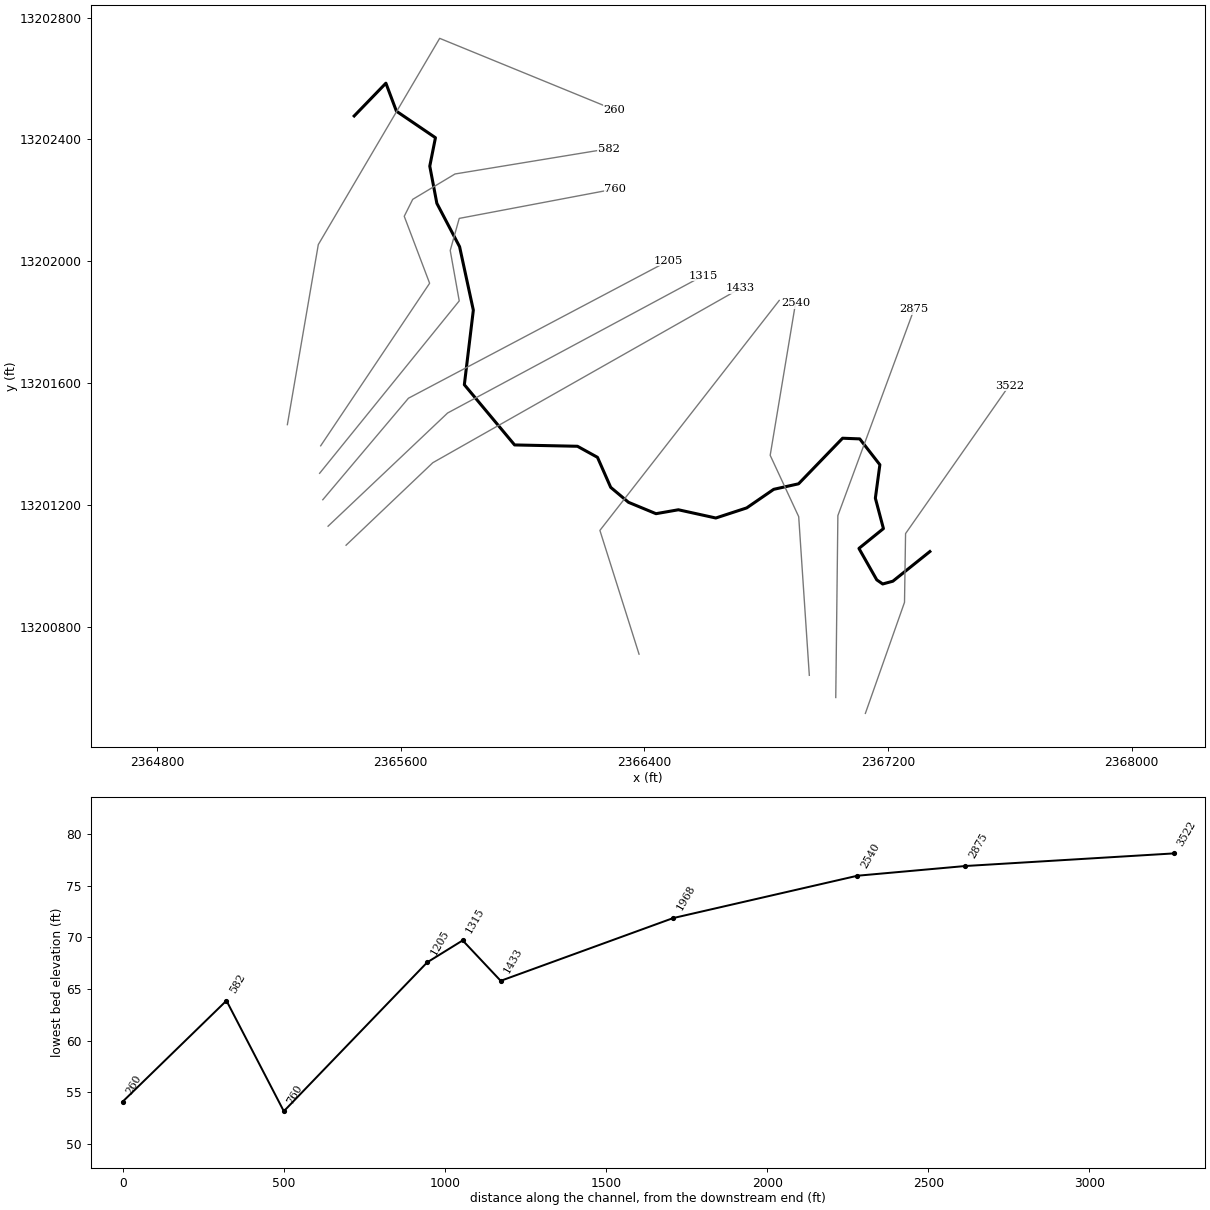
--- UNT019 IN BACR.prj (project) ---

Proj Title=UNT019 IN BACR Base Level Engineering
Current Plan=p01
Default Exp/Contr=0.3,0.1
English Units
Geom File=g01
Flow File=f01
Plan File=p01
BEGIN DESCRIPTION:
UNT019 IN BACR
END DESCRIPTION:

--- UNT019 IN BACR.p01 (plan) ---

Plan Title=Multiple Run
Short Identifier=Multiple
Geom File=g01
Flow File=f01
Subcritical Flow
K Sum by GR= 0
Std Step Tol= 0.01
Critical Tol= 0.01
Num of Std Step Trials= 20
Max Error Tol= 0.3
Flow Tol Ratio= 0.001
Split Flow NTrial= 30
Split Flow Tol= 0.02
Split Flow Ratio= 0.02
Log Output Level= 0
Friction Slope Method= 1
Unsteady Friction Slope Method= 2
Unsteady Bridges Friction Slope Method= 1
Parabolic Critical Depth
Global Vel Dist=  1 , 1 , 1
Global Log Level= 0
CheckData=True
Encroach Param= -1, 0, 0, 0
BEGIN DESCRIPTION:
Multiple Run
END DESCRIPTION:

--- UNT019 IN BACR.f01 (steady flow) ---

Flow Title=Multiple
Number of Profiles=7
Profile Names=10-year,25-year,50-year,1pct_min,100-year,1pct_plu,500-year
River Rch & RM= UNT019 IN BACR,Reach-1,3522
     546     749     914     814    1100    1488    1600
Boundary for River Rch & Prof#=UNT019 IN BACR,Reach-1,1
Up Type=0
Dn Type=3
Dn Slope=0.005
Boundary for River Rch & Prof#=UNT019 IN BACR,Reach-1,2
Up Type=0
Dn Type=3
Dn Slope=0.005
Boundary for River Rch & Prof#=UNT019 IN BACR,Reach-1,3
Up Type=0
Dn Type=3
Dn Slope=0.005
Boundary for River Rch & Prof#=UNT019 IN BACR,Reach-1,4
Up Type=0
Dn Type=3
Dn Slope=0.005
Boundary for River Rch & Prof#=UNT019 IN BACR,Reach-1,5
Up Type=0
Dn Type=3
Dn Slope=0.005
Boundary for River Rch & Prof#=UNT019 IN BACR,Reach-1,6
Up Type=0
Dn Type=3
Dn Slope=0.005
Boundary for River Rch & Prof#=UNT019 IN BACR,Reach-1,7
Up Type=0
Dn Type=3
Dn Slope=0.005

--- UNT019 IN BACR.g01 (geometry) ---

Geom Title=Existing Conditions

River Reach=UNT019 IN BACR,Reach-1
Reach XY= 30
      2367337.72     13201046.85      2367216.13     13200949.47
      2367182.83     13200940.39      2367163.32     13200953.94
      2367104.82     13201057.13      2367185.23     13201122.27
      2367158.73     13201222.09      2367173.54     13201331.79
      2367107.49     13201416.72      2367051.13     13201418.90
      2366906.65     13201269.27      2366825.04     13201251.13
      2366736.39     13201190.14      2366634.99     13201156.98
      2366512.10     13201184.01      2366438.53     13201171.16
      2366348.35     13201208.48      2366289.85     13201257.63
      2366246.49     13201356.16      2366180.71     13201392.47
      2365974.33     13201396.86      2365809.40     13201594.55
      2365838.91     13201839.34      2365793.78     13202047.67
      2365719.12     13202190.04      2365695.90     13202312.09
      2365714.54     13202405.47      2365586.44     13202492.50
      2365551.87     13202584.47      2365447.72     13202476.86

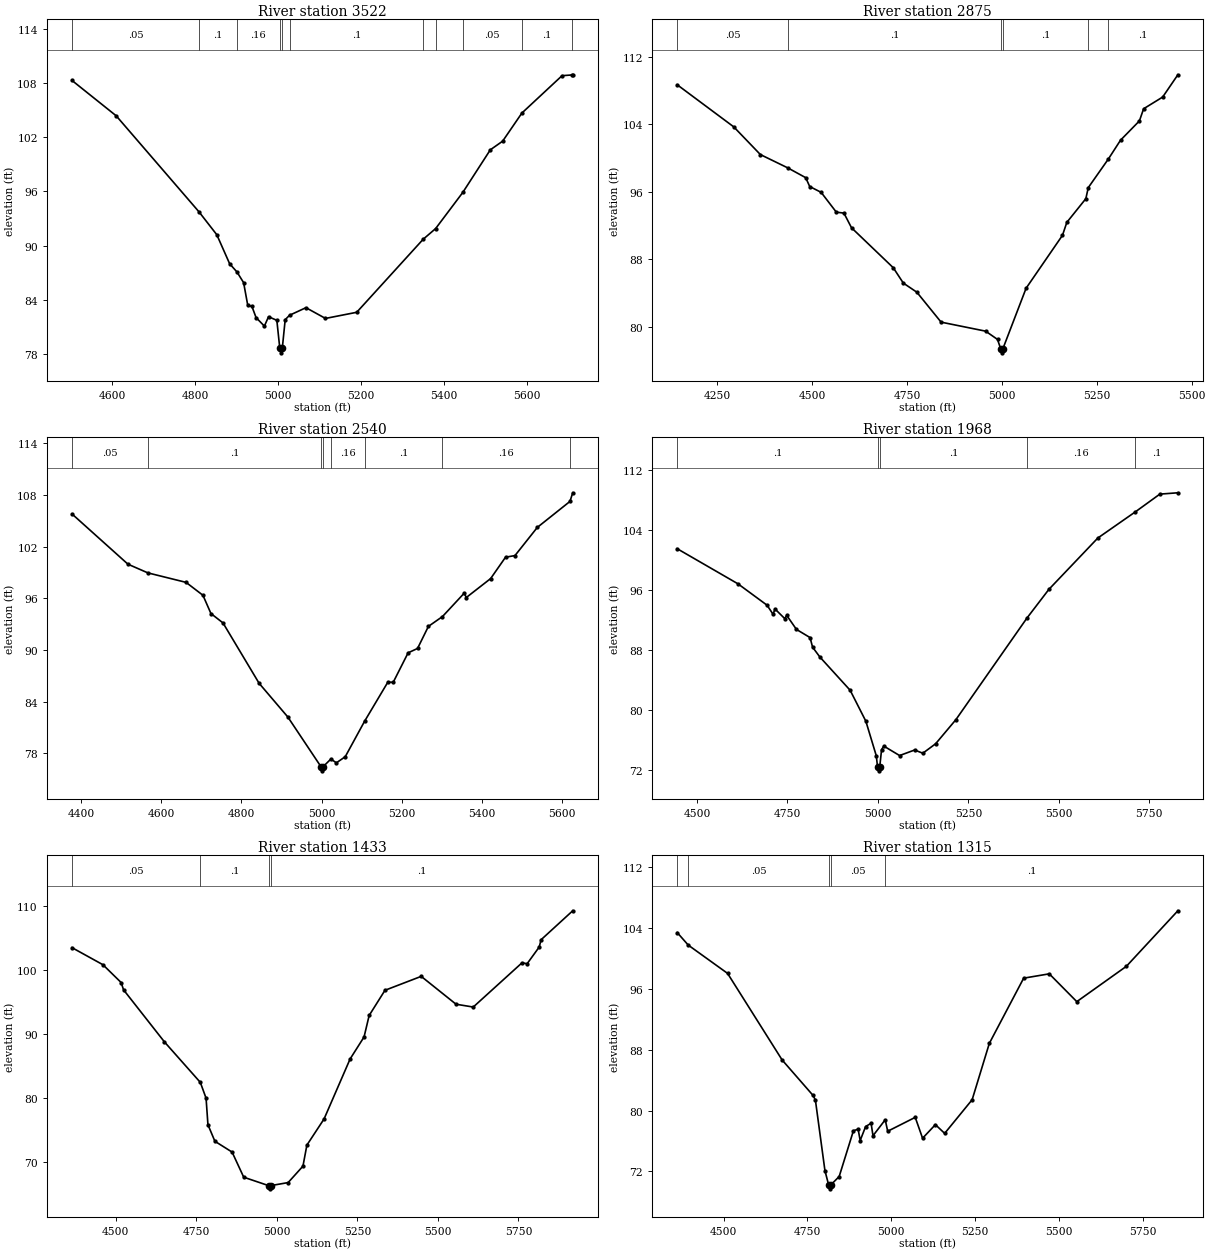
Type RM Length L Ch R = 1,3522,647,647,647
BEGIN DESCRIPTION:
UNT019 IN BACR 7.0
END DESCRIPTION:
XS GIS Cut Line= 4
      2367125.97     13200515.59      2367254.43     13200880.15
      2367257.90     13201105.84      2367598.17     13201591.93
#Sta/Elev= 30
  4504.0  108.28  4610.3  104.37  4809.8   93.73  4852.6   91.20  4883.6   87.98
  4901.1   87.08  4917.2   85.89  4927.2   83.37  4937.2   83.26  4947.2   82.02
  4967.2   81.08  4977.2   82.12  4997.2   81.72  5004.3   78.62  5007.0   78.12
  5010.3   78.62  5017.3   81.79  5027.7   82.28  5067.3   83.12  5114.3   81.93
  5189.5   82.61  5349.6   90.70  5379.5   91.88  5444.9   95.88  5511.2  100.60
  5540.9  101.56  5587.2  104.67  5683.9  108.81  5708.1  108.89  5709.6  108.91
#Mann=11,-1,0
  4504.0    0.05       0  4809.8     0.1       0  4901.1    0.16       0
  5004.3    0.07       0  5010.3    0.16       0  5027.7     0.1       0
  5349.6    0.05       0  5379.5     0.1       0  5444.9    0.05       0
  5587.2     0.1       0  5708.1    0.05       0
Bank Sta=5004.3,5010.3
Exp/Cntr=0.3,0.1

Type RM Length L Ch R = 1,2875,335,335,335
BEGIN DESCRIPTION:
Mapping XS 212eefb5
END DESCRIPTION:
XS GIS Cut Line= 3
      2367028.73     13200567.63      2367035.68     13201164.87
      2367285.66     13201841.91
#Sta/Elev= 30
  4144.7  108.69  4293.9  103.69  4363.9  100.41  4436.6   98.82  4483.3   97.67
  4493.9   96.62  4524.0   95.93  4564.0   93.58  4584.0   93.47  4604.0   91.73
  4714.0   86.99  4740.5   85.17  4776.1   84.09  4840.0   80.54  4957.3   79.47
  4988.6   78.49  4996.9   77.40  4999.7   76.90  5002.9   77.40  5063.9   84.56
  5159.8   90.84  5171.2   92.37  5221.3   95.18  5227.7   96.49  5280.9   99.90
  5312.6  102.11  5362.4  104.40  5373.5  105.84  5423.7  107.23  5463.7  109.87
#Mann=6,-1,0
  4144.7    0.05       0  4436.6     0.1       0  4996.9    0.07       0
  5002.9     0.1       0  5227.7    0.05       0  5280.9     0.1       0
Bank Sta=4996.9,5002.9
Exp/Cntr=0.3,0.1

Type RM Length L Ch R = 1,2540,572,572,572
BEGIN DESCRIPTION:
UNT019 IN BACR 6.0
END DESCRIPTION:
XS GIS Cut Line= 4
      2366941.93     13200640.58      2366907.07     13201161.38
      2366813.46     13201362.78      2366896.71     13201862.33
#Sta/Elev= 30
  4376.9  105.78  4516.6   99.95  4566.4   98.94  4661.7   97.84  4703.9   96.34
  4723.9   94.22  4754.0   93.13  4844.2   86.12  4915.9   82.21  4998.4   76.46
  5001.1   75.96  5004.4   76.46  5023.4   77.33  5037.2   76.89  5059.3   77.60
  5107.4   81.70  5165.6   86.25  5179.1   86.24  5216.3   89.66  5239.9   90.17
  5267.0   92.73  5302.1   93.87  5356.5   96.59  5361.6   96.08  5422.4   98.28
  5459.6  100.76  5483.2  100.95  5539.0  104.22  5620.6  107.24  5627.4  108.24
#Mann=8,-1,0
  4376.9    0.05       0  4566.4     0.1       0  4998.4    0.07       0
  5004.4     0.1       0  5023.4    0.16       0  5107.4     0.1       0
  5302.1    0.16       0  5620.6     0.1       0
Bank Sta=4998.4,5004.4
Exp/Cntr=0.3,0.1

Type RM Length L Ch R = 1,1968,535,535,535
BEGIN DESCRIPTION:
UNT019 IN BACR 5.0
END DESCRIPTION:
XS GIS Cut Line= 3
      2366382.89     13200710.03      2366254.43     13201116.26
      2366843.20     13201871.27
#Sta/Elev= 30
  4445.4  101.50  4613.5   96.81  4693.8   93.96  4710.4   92.75  4715.7   93.46
  4742.7   92.17  4748.0   92.61  4775.0   90.73  4812.6   89.64  4819.6   88.36
  4839.7   87.05  4923.4   82.61  4966.8   78.48  4995.7   73.86  4999.1   72.36
  5001.8   71.86  5005.1   72.36  5010.2   74.69  5016.5   75.16  5060.0   73.90
  5101.6   74.64  5124.2   74.21  5159.5   75.47  5215.6   78.69  5412.0   92.25
  5472.5   96.07  5607.7  102.92  5711.6  106.42  5779.1  108.78  5828.9  108.96
#Mann=5,-1,0
  4445.4     0.1       0  4999.1    0.07       0  5005.1     0.1       0
  5412.0    0.16       0  5711.6     0.1       0
Bank Sta=4999.1,5005.1
Exp/Cntr=0.3,0.1

Type RM Length L Ch R = 1,1433,118,118,118
BEGIN DESCRIPTION:
UNT019 IN BACR 4.0
END DESCRIPTION:
XS GIS Cut Line= 3
      2365421.11     13201067.66      2365705.82     13201338.48
      2366716.25     13201911.41
#Sta/Elev= 30
  4364.2  103.52  4460.2  100.85  4516.8   98.06  4524.1   96.93  4651.1   88.78
  4762.5   82.45  4780.4   79.97  4786.2   75.82  4807.8   73.23  4861.2   71.54
  4897.3   67.61  4974.7   66.29  4977.5   65.79  4980.7   66.29  5035.2   66.77
  5081.2   69.34  5093.4   72.63  5146.8   76.73  5227.6   86.11  5270.9   89.55
  5286.7   92.91  5335.8   96.85  5448.3   99.03  5556.5   94.67  5609.9   94.23
  5761.3  101.15  5777.2  101.01  5814.7  103.62  5820.5  104.76  5918.7  109.29
#Mann=4,-1,0
  4364.2    0.05       0  4762.5     0.1       0  4974.7    0.07       0
  4980.7     0.1       0
Bank Sta=4974.7,4980.7
Exp/Cntr=0.3,0.1

Type RM Length L Ch R = 1,1315,110,110,110
BEGIN DESCRIPTION:
Mapping XS f67192b5
END DESCRIPTION:
XS GIS Cut Line= 3
      2365362.03     13201130.11      2365754.43     13201501.67
      2366592.55     13201951.91
#Sta/Elev= 30
  4361.9  103.44  4395.0  101.78  4512.1   98.06  4674.7   86.66  4766.9   81.99
  4773.8   81.38  4802.2   72.10  4813.3   70.20  4816.1   69.70  4819.3   70.20
  4844.6   71.32  4887.1   77.35  4901.1   77.55  4907.2   76.06  4923.4   77.90
  4939.7   78.33  4945.4   76.69  4981.8   78.79  4989.2   77.28  5071.2   79.11
  5093.1   76.36  5131.3   78.15  5158.9   77.00  5240.8   81.43  5292.0   88.85
  5394.3   97.43  5470.6   98.00  5552.6   94.34  5700.3   98.99  5853.7  106.30
#Mann=5,-1,0
  4361.9     0.1       0  4395.0    0.05       0  4813.3    0.07       0
  4819.3    0.05       0  4981.8     0.1       0
Bank Sta=4813.3,4819.3
Exp/Cntr=0.3,0.1

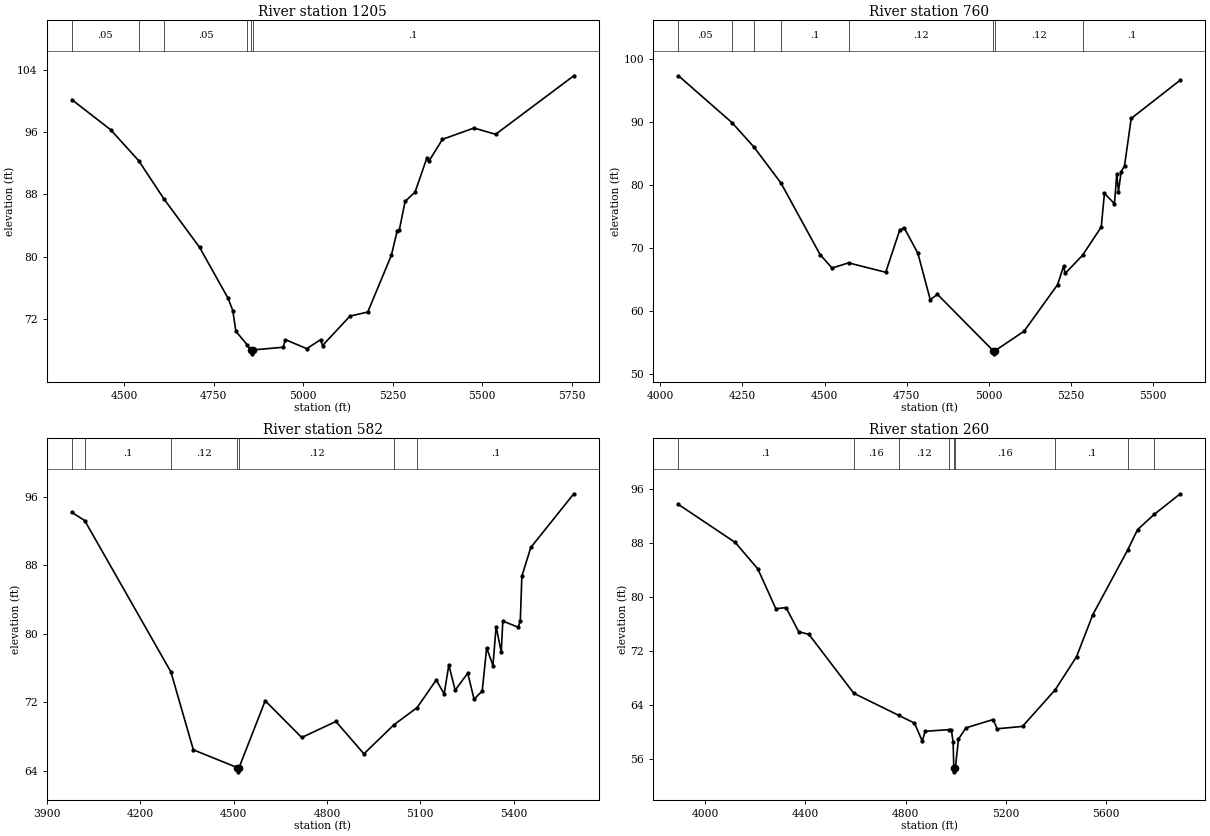
Type RM Length L Ch R = 1,1205,445,445,445
BEGIN DESCRIPTION:
UNT019 IN BACR 3.0
END DESCRIPTION:
XS GIS Cut Line= 3
      2365344.71     13201216.96      2365625.96     13201550.28
      2366480.10     13202001.66
#Sta/Elev= 30
  4354.1  100.13  4462.4   96.28  4540.6   92.32  4611.4   87.41  4710.7   81.22
  4790.2   74.71  4803.5   73.13  4812.1   70.48  4843.4   68.75  4853.1   68.08
  4855.9   67.58  4859.1   68.08  4944.2   68.42  4950.6   69.40  5010.2   68.24
  5048.6   69.39  5054.2   68.64  5131.0   72.42  5180.6   72.93  5246.7   80.22
  5263.0   83.35  5268.7   83.42  5285.0   87.11  5312.7   88.29  5345.4   92.61
  5351.1   92.23  5389.4   95.06  5477.5   96.51  5537.9   95.70  5756.3  103.20
#Mann=6,-1,0
  4354.1    0.05       0  4540.6     0.1       0  4611.4    0.05       0
  4843.4     0.1       0  4853.1    0.07       0  4859.1     0.1       0
Bank Sta=4853.1,4859.1
Exp/Cntr=0.3,0.1

Type RM Length L Ch R = 1,760,178,178,178
BEGIN DESCRIPTION:
Mapping XS e09b566d
END DESCRIPTION:
XS GIS Cut Line= 5
      2365334.28     13201303.74      2365792.62     13201869.73
      2365763.05     13202035.33      2365792.62     13202140.56
      2366304.61     13202237.42
#Sta/Elev= 30
  4055.5   97.28  4218.5   89.84  4284.8   86.00  4367.4   80.26  4486.3   68.92
  4522.8   66.78  4573.1   67.60  4686.1   66.11  4728.6   72.79  4742.1   73.17
  4783.8   69.14  4821.5   61.77  4843.5   62.60  5012.9   53.67  5015.7   53.17
  5018.9   53.67  5107.2   56.77  5209.0   64.15  5227.0   67.05  5232.1   65.92
  5284.9   68.81  5341.8   73.29  5351.5   78.62  5382.0   76.99  5389.1   81.74
  5394.2   78.91  5402.4   82.07  5412.6   82.98  5432.9   90.51  5582.4   96.60
#Mann=8,-1,0
  4055.5    0.05       0  4218.5     0.1       0  4284.8    0.05       0
  4367.4     0.1       0  4573.1    0.12       0  5012.9    0.07       0
  5018.9    0.12       0  5284.9     0.1       0
Bank Sta=5012.9,5018.9
Exp/Cntr=0.3,0.1

Type RM Length L Ch R = 1,582,322,322,322
BEGIN DESCRIPTION:
UNT019 IN BACR 2.0
END DESCRIPTION:
XS GIS Cut Line= 6
      2365337.76     13201394.03      2365695.39     13201927.61
      2365612.07     13202147.51      2365639.85     13202203.06
      2365778.73     13202286.40      2366284.16     13202369.48
#Sta/Elev= 30
  3980.0   94.16  4021.1   93.21  4298.2   75.54  4370.4   66.44  4511.4   64.37
  4514.2   63.87  4517.4   64.37  4601.5   72.17  4718.8   67.88  4828.8   69.75
  4918.9   65.97  5015.6   69.37  5090.0   71.37  5151.5   74.60  5176.9   72.97
  5192.0   76.35  5212.3   73.40  5252.8   75.39  5273.1   72.35  5299.3   73.31
  5313.6   78.35  5333.9   76.28  5344.0   80.84  5360.5   77.84  5365.6   81.48
  5415.0   80.75  5421.8   81.51  5426.8   86.71  5455.5   90.07  5593.8   96.34
#Mann=7,-1,0
  3980.0    0.05       0  4021.1     0.1       0  4298.2    0.12       0
  4511.4    0.07       0  4517.4    0.12       0  5015.6    0.16       0
  5090.0     0.1       0
Bank Sta=4511.4,4517.4
Exp/Cntr=0.3,0.1

Type RM Length L Ch R = 1,260,0,0,0
BEGIN DESCRIPTION:
UNT019 IN BACR 1.0
END DESCRIPTION:
XS GIS Cut Line= 4
      2365228.39     13201463.47      2365329.95     13202054.63
      2365728.39     13202731.71      2366301.27     13202497.35
#Sta/Elev= 30
  3892.7   93.65  4119.4   88.03  4209.6   84.12  4281.7   78.22  4322.3   78.40
  4373.0   74.82  4413.6   74.44  4593.0   65.72  4773.2   62.44  4835.3   61.31
  4866.4   58.65  4878.2   60.10  4972.9   60.34  4982.4   60.33  4989.6   58.54
  4992.4   54.60  4995.1   54.10  4998.4   54.60  5011.0   58.93  5040.4   60.60
  5149.7   61.84  5165.3   60.47  5266.8   60.82  5397.7   66.25  5482.7   71.14
  5547.5   77.34  5686.5   86.90  5726.3   89.92  5792.5   92.18  5897.1   95.23
#Mann=9,-1,0
  3892.7     0.1       0  4593.0    0.16       0  4773.2    0.12       0
  4972.9    0.16       0  4992.4    0.07       0  4998.4    0.16       0
  5397.7     0.1       0  5686.5    0.05       0  5792.5     0.1       0
Bank Sta=4992.4,4998.4
Exp/Cntr=0.3,0.1

Chan Stop Cuts=-1