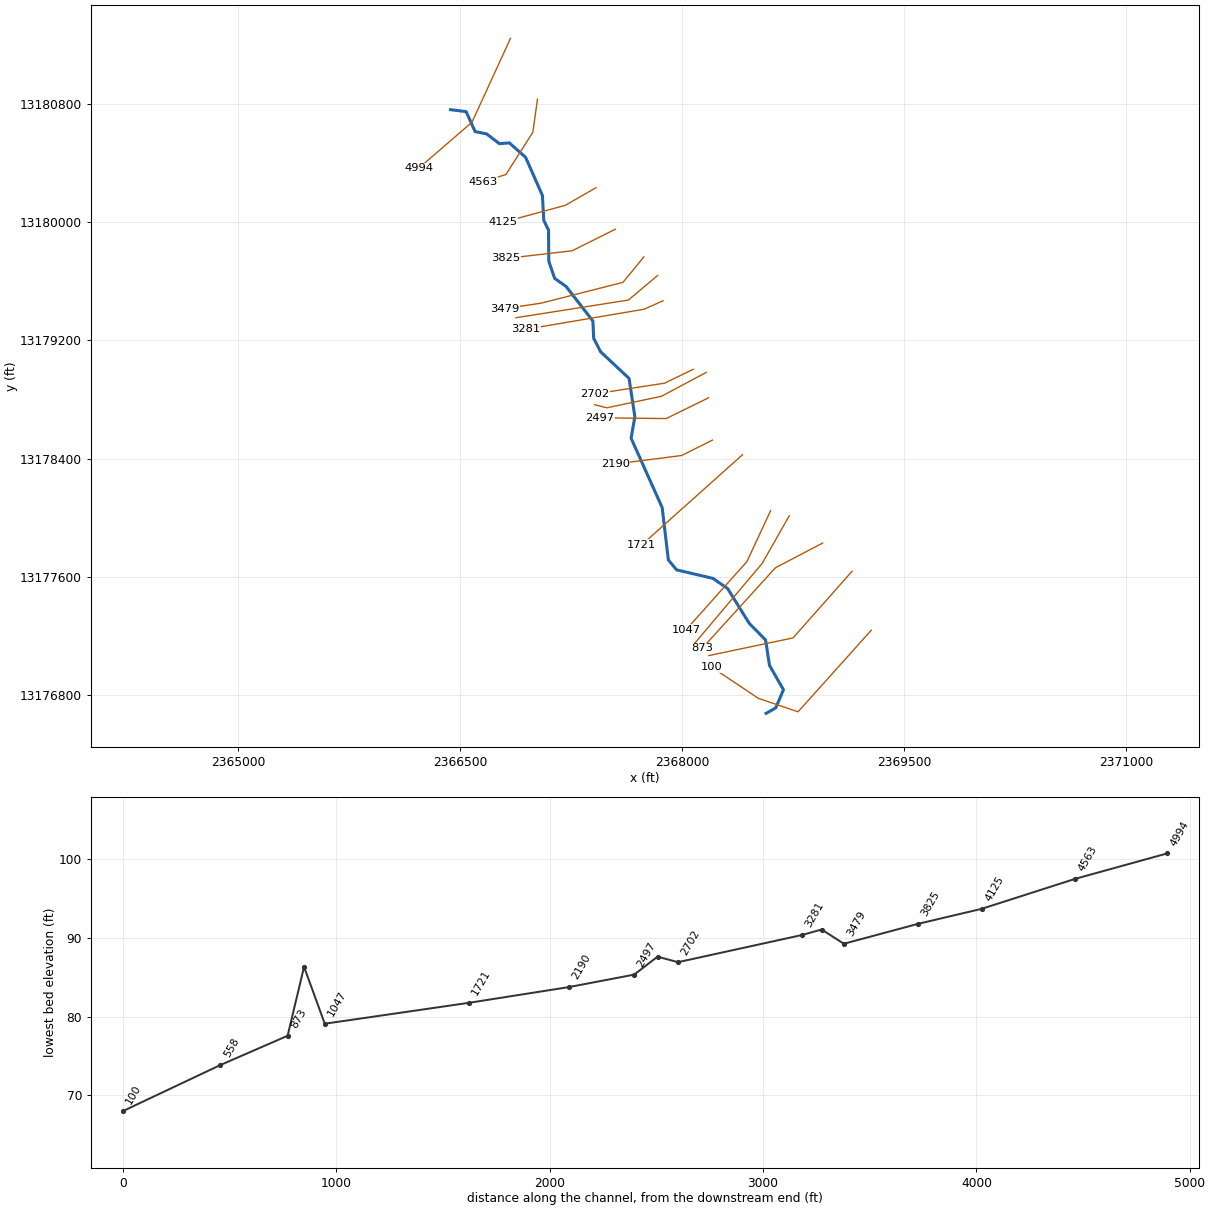
--- UNT022 IN BACR.prj (project) ---

Proj Title=UNT022 IN BACR Base Level Engineering
Current Plan=p01
Default Exp/Contr=0.3,0.1
English Units
Geom File=g01
Flow File=f01
Plan File=p01
Y Axis Title=Elevation
X Axis Title(PF)=Main Channel Distance
X Axis Title(XS)=Station
BEGIN DESCRIPTION:
UNT022 IN BACR
END DESCRIPTION:
DSS Export Rating Curves= 0
DSS Export Rating Curve Sorted= 0
DSS Export Volume Flow Curves= 0
DXF OffsetX= 0
DXF OffsetY= 0
DXF ScaleX= 1
DXF ScaleY= 10

--- UNT022 IN BACR.p01 (plan) ---

Plan Title=Multiple Run
Short Identifier=Multiple
Geom File=g01
Flow File=f01
Subcritical Flow
K Sum by GR= 0
Std Step Tol= 0.01
Critical Tol= 0.01
Num of Std Step Trials= 20
Max Error Tol= 0.3
Flow Tol Ratio= 0.001
Split Flow NTrial= 30
Split Flow Tol= 0.02
Split Flow Ratio= 0.02
Log Output Level= 0
Friction Slope Method= 1
Unsteady Friction Slope Method= 2
Unsteady Bridges Friction Slope Method= 1
Parabolic Critical Depth
Global Vel Dist=  1 , 1 , 1
Global Log Level= 0
CheckData=True
Encroach Param= -1, 0, 0, 0
BEGIN DESCRIPTION:
Multiple Run
END DESCRIPTION:

--- UNT022 IN BACR.f01 (steady flow) ---

Flow Title=Multiple
Number of Profiles=7
Profile Names=10-year,25-year,50-year,1pct_min,100-year,1pct_plu,500-year
River Rch & RM= UNT022 IN BACR,Reach-1,4994
     280     369     438     381     515     697     717
Boundary for River Rch & Prof#=UNT022 IN BACR,Reach-1,1
Up Type=0
Dn Type=3
Dn Slope=0.005
Boundary for River Rch & Prof#=UNT022 IN BACR,Reach-1,2
Up Type=0
Dn Type=3
Dn Slope=0.005
Boundary for River Rch & Prof#=UNT022 IN BACR,Reach-1,3
Up Type=0
Dn Type=3
Dn Slope=0.005
Boundary for River Rch & Prof#=UNT022 IN BACR,Reach-1,4
Up Type=0
Dn Type=3
Dn Slope=0.005
Boundary for River Rch & Prof#=UNT022 IN BACR,Reach-1,5
Up Type=0
Dn Type=3
Dn Slope=0.005
Boundary for River Rch & Prof#=UNT022 IN BACR,Reach-1,6
Up Type=0
Dn Type=3
Dn Slope=0.005
Boundary for River Rch & Prof#=UNT022 IN BACR,Reach-1,7
Up Type=0
Dn Type=3
Dn Slope=0.005

--- UNT022 IN BACR.g01 (geometry) ---

Geom Title=Existing Conditions
Program Version=4.10

River Reach=UNT022 IN BACR  ,Reach-1
Reach XY= 30
      2366435.05     13180761.74      2366540.16      13180748.9
      2366601.08     13180613.67      2366679.58     13180597.53
      2366764.83     13180531.86      2366832.52      13180536.9
      2366942.24     13180439.39      2367055.99     13180181.19
      2367065.04     13180013.02      2367097.44     13179946.82
      2367098.77     13179737.29      2367138.68     13179620.39
      2367215.53     13179565.76      2367397.01     13179331.96
      2367402.56     13179214.84      2367448.86     13179124.09
      2367641.45     13178943.54       2367680.8     13178684.28
      2367655.34     13178538.91      2367865.25     13178069.31
      2367907.02     13177715.24      2367962.72     13177647.97
      2368208.67      13177590.1      2368307.77     13177521.37
      2368453.89     13177285.69       2368564.4     13177173.58
      2368590.18     13177002.62      2368685.12     13176836.88
      2368633.02     13176713.94      2368567.72     13176676.85

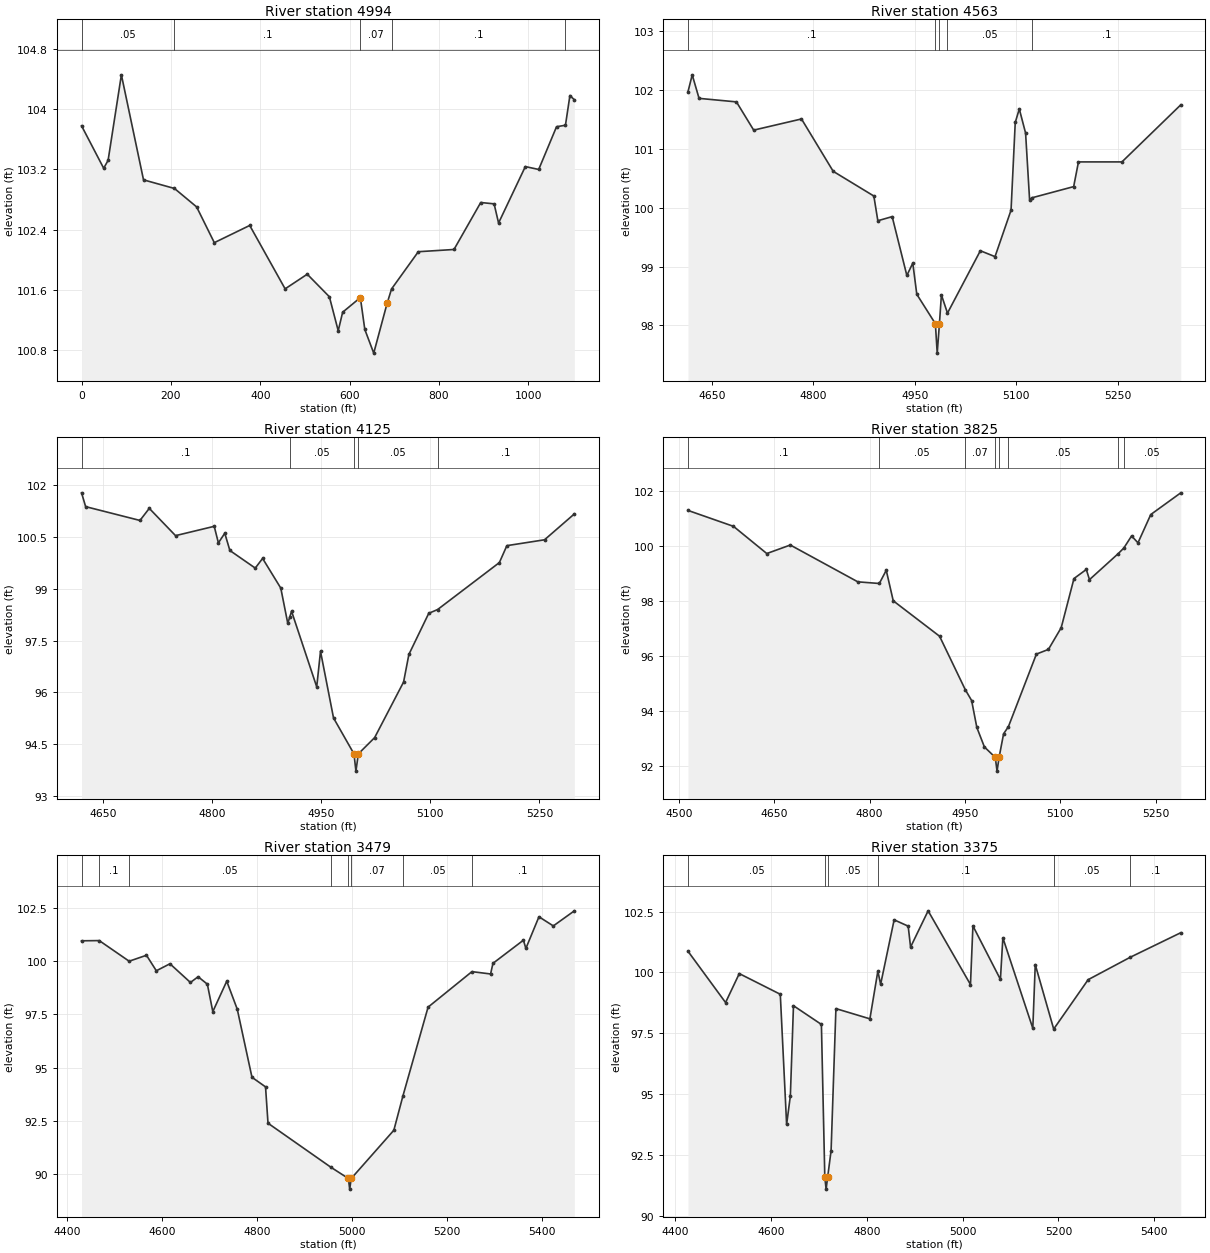
Type RM Length L Ch R = 1 ,4994    ,431,431,431
BEGIN DESCRIPTION:
UNT022 IN BACR 8.0
END DESCRIPTION:
XS GIS Cut Line= 3
     2366840.305     13181244.56     2366579.888     13180676.85
     2366219.018     13180365.04
#Sta/Elev= 30
       0103.779149.52744103.215459.43293103.3205 89.1494104.4562138.6768103.0615
208.0153102.9468257.5427102.7022297.1646102.2272376.4086102.4558455.6525101.6139
505.1799101.8083554.7073101.5088574.5183101.0572584.4238101.3034624.0458101.4977
634.0262101.0745653.9872100.7602683.9285101.4215 693.909101.6126753.7918 102.107
833.6355102.1367893.5183102.7606923.4597102.7427933.4401102.4882993.3229103.2376
1023.264103.19941063.186103.76691083.147103.78671093.128104.18131103.108104.1248
#Mann= 5 ,-1 , 0
       0     .05       0208.0153      .1       0624.0458     .07       0
 693.909      .1       01083.147     .05       0
Bank Sta=624.0458,683.9285
XS Rating Curve= 0 ,0
Exp/Cntr=0.3,0.1

Type RM Length L Ch R = 1 ,4563    ,438,438,438
BEGIN DESCRIPTION:
UNT022 IN BACR 7.0
END DESCRIPTION:
XS GIS Cut Line= 4
       2367022.6     13180833.12      2366991.35     13180609.14
      2366809.06     13180322.68      2366652.82     13180275.81
#Sta/Elev= 30
  4614.5  101.97  4620.8  102.26  4630.9  101.86  4686.2   101.8  4711.7  101.32
  4782.4  101.51  4829.3  100.62  4889.4   100.2  4895.3   99.78  4916.5   99.85
  4938.2   98.85    4947   99.06  4952.9   98.53  4980.4   98.03  4983.1   97.53
  4986.4   98.03  4989.3   98.52  4998.3   98.21  5046.9   99.27  5068.6   99.17
  5092.3   99.96  5098.5  101.45  5104.5  101.68  5113.8  101.27  5119.7  100.14
  5123.2  100.17  5184.9  100.36    5192  100.78  5256.3  100.78  5343.3  101.75
#Mann= 5 ,-1 , 0
  4614.5      .1       0  4980.4     .03       0  4986.4      .1       0
  4998.3     .05       0  5123.2      .1       0
Bank Sta=4980.4,4986.4
XS Rating Curve= 0 ,0
Exp/Cntr=0.3,0.1

Type RM Length L Ch R = 1 ,4125    ,300,300,300
BEGIN DESCRIPTION:
UNT022 IN BACR 6.0
END DESCRIPTION:
XS GIS Cut Line= 3
      2367418.42     13180234.13       2367210.1     13180114.35
      2366788.19     13179999.75
#Sta/Elev= 30
  4620.5  101.78  4626.1  101.38  4700.8  100.98  4713.6  101.33  4749.7  100.54
  4802.9  100.81  4808.6  100.33  4817.4  100.61  4824.4  100.11  4859.3    99.6
  4869.4   99.88  4894.4   99.02    4904      98  4906.7   98.18  4909.2   98.35
  4943.8   96.16    4949   97.19  4966.9   95.26    4995   94.22  4997.7   93.72
    5001   94.22  5023.4   94.69  5063.2    96.3  5070.5    97.1  5097.8   98.29
    5110    98.4  5194.9   99.76  5205.2  100.25    5257  100.42    5298  101.17
#Mann= 5 ,-1 , 0
  4620.5      .1       0  4906.7     .05       0    4995     .03       0
    5001     .05       0    5110      .1       0
Bank Sta=4995,5001
XS Rating Curve= 0 ,0
Exp/Cntr=0.3,0.1

Type RM Length L Ch R = 1 ,3825    ,346,346,346
BEGIN DESCRIPTION:
Mapping XS 3c93f54c
END DESCRIPTION:
XS GIS Cut Line= 3
      2367548.65     13179952.89      2367256.97     13179807.06
      2366810.88     13179755.18
#Sta/Elev= 30
  4514.3  101.29  4585.9  100.71  4638.3   99.72  4675.3  100.03  4781.5   98.69
  4815.3   98.63  4826.2   99.11  4837.2      98  4910.1   96.71  4950.4   94.77
  4960.5   94.37  4968.7   93.39  4980.6   92.68  4997.7    92.3  5000.5    91.8
  5003.7    92.3  5010.8   93.16  5018.4   93.42  5062.4   96.06  5081.3   96.23
  5101.4   97.02  5121.5   98.81  5140.9   99.14  5145.9   98.77  5190.8   99.71
  5199.9   99.92  5212.1  100.36  5222.2  100.11  5242.3  101.14  5289.5  101.93
#Mann= 8 ,-1 , 0
  4514.3      .1       0  4815.3     .05       0  4950.4     .07       0
  4997.7     .07       0  5003.7     .07       0  5018.4     .05       0
  5190.8      .1       0  5199.9     .05       0
Bank Sta=4997.7,5003.7
XS Rating Curve= 0 ,0
Exp/Cntr=0.3,0.1

Type RM Length L Ch R = 1 ,3479    ,104,104,104
BEGIN DESCRIPTION:
UNT022 IN BACR 5.0
END DESCRIPTION:
XS GIS Cut Line= 4
      2367741.37     13179765.41      2367600.72     13179593.51
      2367048.64     13179452.89      2366803.85     13179416.43
#Sta/Elev= 30
  4429.7  100.96    4467  100.97  4530.1     100  4566.6  100.28  4587.4   99.55
  4616.1   99.88  4659.3      99  4675.5   99.27    4695   98.92  4706.5   97.63
  4735.9   99.06  4758.1   97.74  4789.1   94.54  4817.7   94.09  4822.9   92.38
  4954.8   90.32  4992.4   89.78  4995.2   89.28  4998.4   89.78  5088.3   92.05
  5107.4   93.66  5160.5   97.84    5253   99.51  5292.3    99.4  5297.3    99.9
  5361.6  100.99  5366.7   100.6  5394.3  102.09  5424.6  101.66    5469  102.37
#Mann= 8 ,-1 , 0
  4429.7     .05       0    4467      .1       0  4530.1     .05       0
  4954.8     .07       0  4992.4     .07       0  4998.4     .07       0
  5107.4     .05       0    5253      .1       0
Bank Sta=4992.4,4998.4
XS Rating Curve= 0 ,0
Exp/Cntr=0.3,0.1

Type RM Length L Ch R = 1 ,3375    ,94,94,94
BEGIN DESCRIPTION:
Mapping XS 0d713a3b
END DESCRIPTION:
XS GIS Cut Line= 3
       2367835.1     13179640.39      2367637.18     13179473.72
      2366876.81     13179353.94
#Sta/Elev= 30
  4426.7  100.87  4505.2   98.76  4533.8   99.95  4619.4    99.1  4632.6   93.75
  4640.4   94.92  4646.9   98.63  4705.2   97.86  4712.3   91.59    4715   91.09
  4718.3   91.59  4725.4   92.67  4735.5   98.51  4806.4   98.09    4823  100.05
  4828.8   99.51    4857  102.16  4886.3   101.9  4891.3  101.04  4927.9  102.53
  5016.3    99.5  5021.4  101.91  5078.8   99.71  5083.9  101.42  5146.4    97.7
  5151.5  100.32    5190   97.67  5261.9    99.7  5349.6  100.62  5455.2  101.63
#Mann= 6 ,-1 , 0
  4426.7     .05       0  4712.3     .07       0  4718.3     .05       0
    4823      .1       0    5190     .05       0  5349.6      .1       0
Bank Sta=4712.3,4718.3
XS Rating Curve= 0 ,0
Exp/Cntr=0.3,0.1

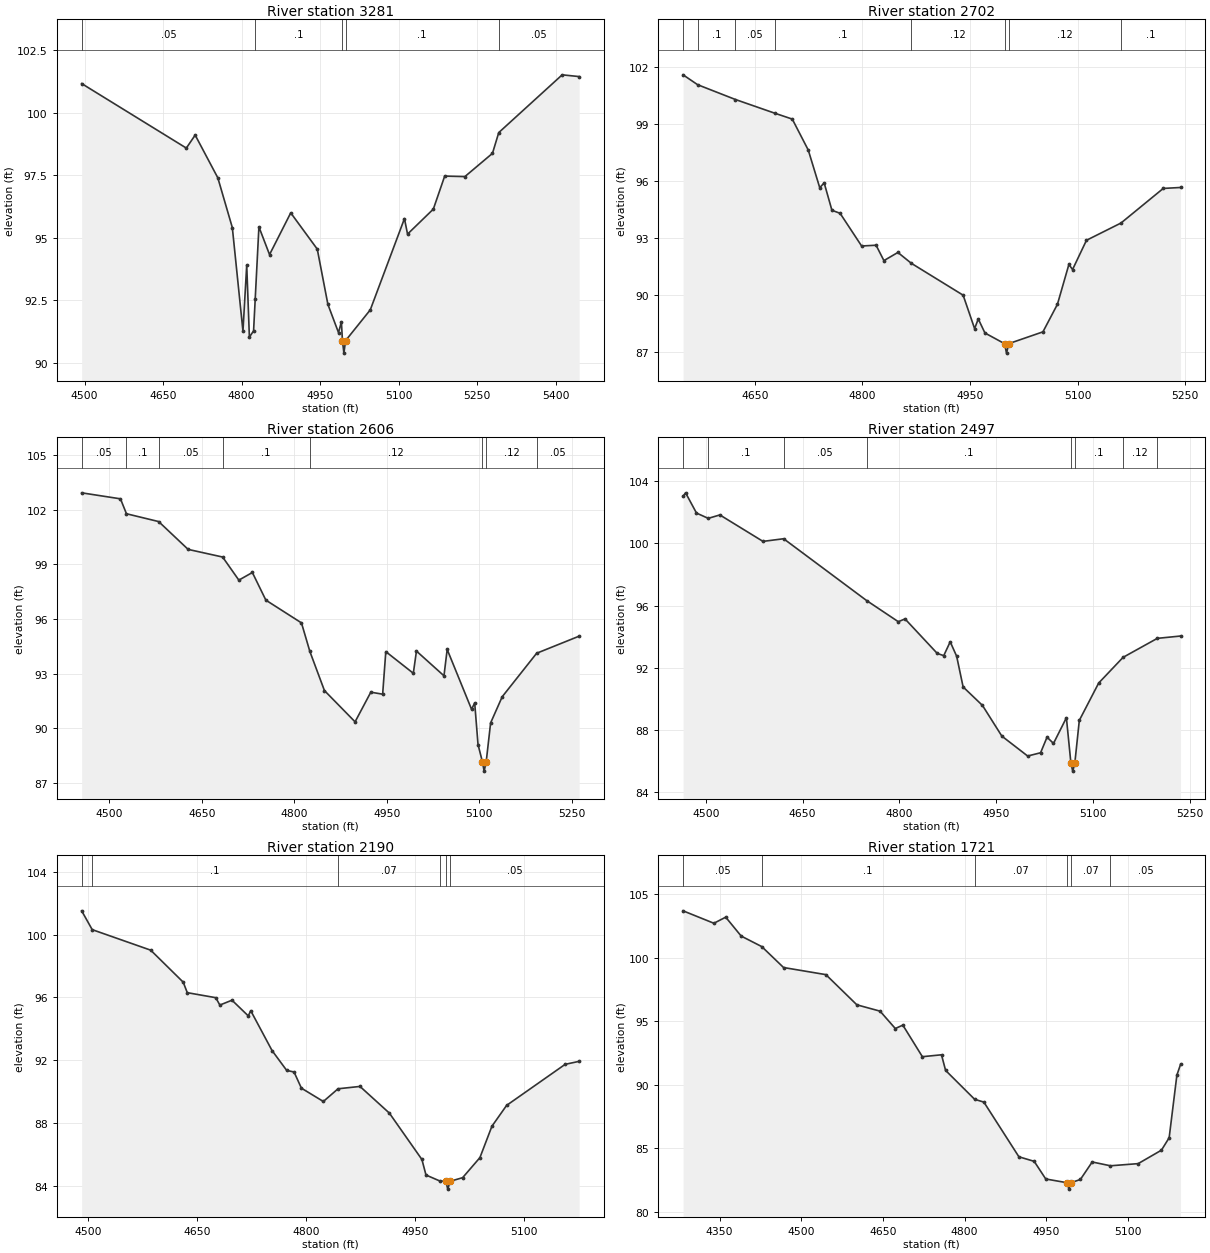
Type RM Length L Ch R = 1 ,3281    ,579,579,579
BEGIN DESCRIPTION:
UNT022 IN BACR 4.0
END DESCRIPTION:
XS GIS Cut Line= 3
      2367871.56     13179468.52      2367741.35     13179411.22
      2366944.43      13179275.8
#Sta/Elev= 30
  4494.3  101.16  4694.3   98.58  4711.2    99.1  4754.5   97.39  4782.2    95.4
  4802.5   91.26  4809.7    93.9  4814.8   91.02  4822.8   91.27  4825.9   92.53
    4833   95.43  4853.3   94.32  4893.8   95.99  4944.5   94.54  4964.8   92.33
  4985.1    91.2  4990.6   91.63  4992.6   90.88  4995.4   90.38  4998.6   90.88
  5045.8   92.11  5111.1   95.76    5117   95.14  5166.3   96.14    5188   97.46
  5226.6   97.44  5279.3   98.37  5291.3    99.2  5412.5  101.51  5444.9  101.44
#Mann= 5 ,-1 , 0
  4494.3     .05       0  4825.9      .1       0  4992.6     .07       0
  4998.6      .1       0  5291.3     .05       0
Bank Sta=4992.6,4998.6
XS Rating Curve= 0 ,0
Exp/Cntr=0.3,0.1

Type RM Length L Ch R = 1 ,2702    ,96,96,96
BEGIN DESCRIPTION:
Mapping XS 87b865c2
END DESCRIPTION:
XS GIS Cut Line= 3
      2368074.69     13179004.97      2367881.97     13178911.22
      2367408.06     13178838.31
#Sta/Elev= 30
  4549.8  101.59  4570.1  101.07  4622.9  100.29  4677.7   99.57  4702.1   99.26
  4724.4   97.63  4740.4   95.65  4746.6    95.9  4757.4   94.46  4768.8    94.3
  4798.8   92.58    4819   92.62  4829.9   91.81  4849.4   92.24  4868.1   91.67
  4940.4   89.99  4956.4   88.23  4961.5   88.74  4970.8      88  4998.1   87.44
  5000.9   86.94  5004.1   87.44  5051.7   88.06  5071.9   89.51  5087.9   91.61
    5093   91.34  5112.4   92.88  5160.6   93.79  5219.5   95.61  5243.6   95.66
#Mann= 8 ,-1 , 0
  4549.8     .05       0  4570.1      .1       0  4622.9     .05       0
  4677.7      .1       0  4868.1     .12       0  4998.1     .07       0
  5004.1     .12       0  5160.6      .1       0
Bank Sta=4998.1,5004.1
XS Rating Curve= 0 ,0
Exp/Cntr=0.3,0.1

Type RM Length L Ch R = 1 ,2606    ,109,109,109
BEGIN DESCRIPTION:
UNT022 IN BACR 3.0
END DESCRIPTION:
XS GIS Cut Line= 4
      2368163.26     13178984.16      2367861.14     13178822.68
      2367491.35     13178744.56      2367408.03     13178765.38
#Sta/Elev= 30
  4455.3  102.94  4518.2  102.61  4527.9  101.79  4580.1  101.36  4627.9   99.83
  4683.8   99.41  4710.1   98.14    4732   98.56  4753.9   97.04  4811.6   95.79
  4825.2   94.22  4848.8   92.07  4898.5   90.35    4924   91.98  4943.2   91.87
  4948.3   94.21  4992.9   93.02    4998   94.24  5042.6   92.88  5047.8   94.33
  5087.3   91.04  5092.4   91.39  5097.8    89.1    5105   88.14  5107.7   87.64
    5111   88.14  5118.2   90.29    5137   91.73  5192.8   94.12  5261.7   95.06
#Mann= 8 ,-1 , 0
  4455.3     .05       0  4527.9      .1       0  4580.1     .05       0
  4683.8      .1       0  4825.2     .12       0    5105     .07       0
    5111     .12       0  5192.8     .05       0
Bank Sta=5105,5111
XS Rating Curve= 0 ,0
Exp/Cntr=0.3,0.1

Type RM Length L Ch R = 1 ,2497    ,307,307,307
BEGIN DESCRIPTION:
Mapping XS 21f23360
END DESCRIPTION:
XS GIS Cut Line= 3
      2368178.86     13178812.27      2367892.39     13178671.64
      2367440.95     13178676.83
#Sta/Elev= 30
  4464.8  103.02  4468.7  103.24  4485.6  101.94  4503.8   101.6  4521.8  101.82
  4588.6  100.12  4620.6  100.29  4749.1   96.32  4798.2   94.96  4808.6   95.14
  4858.6   92.92  4868.6   92.78  4878.6   93.67  4888.6   92.74  4898.6   90.77
  4928.6   89.58  4958.6   87.61  4998.6   86.33  5018.6   86.54  5028.6   87.54
  5038.6   87.14  5058.6   88.79  5065.6   85.86  5068.4   85.36  5071.6   85.86
  5078.6   88.62  5108.6   91.02  5146.4   92.67  5199.4   93.89  5235.4   94.04
#Mann= 8 ,-1 , 0
  4464.8     .05       0  4503.8      .1       0  4620.6     .05       0
  4749.1      .1       0  5065.6     .07       0  5071.6      .1       0
  5146.4     .12       0  5199.4     .05       0
Bank Sta=5065.6,5071.6
XS Rating Curve= 0 ,0
Exp/Cntr=0.3,0.1

Type RM Length L Ch R = 1 ,2190    ,469,469,469
BEGIN DESCRIPTION:
Mapping XS e84767d9
END DESCRIPTION:
XS GIS Cut Line= 3
      2368204.85     13178525.79      2367996.56     13178421.64
      2367548.68     13178364.35
#Sta/Elev= 30
  4491.4  101.52  4505.9  100.32  4586.4   99.01  4631.1   96.97  4636.7    96.3
  4675.9   95.98  4681.5   95.51  4698.2   95.82  4720.6   94.82    4724   95.15
  4753.3   92.61  4773.5   91.34  4783.6   91.24  4793.7   90.21  4823.9   89.36
  4844.1   90.17  4874.3   90.32  4914.7   88.62  4959.5   85.66  4965.1   84.67
  4984.1   84.29  4992.3   84.27  4995.1   83.77  4998.3   84.27  5015.5    84.5
  5039.3   85.78  5055.8   87.78    5076   89.11  5156.6   91.73  5175.8   91.92
#Mann= 6 ,-1 , 0
  4491.4     .05       0  4505.9      .1       0  4844.1     .07       0
  4984.1     .05       0  4992.3     .03       0  4998.3     .05       0
Bank Sta=4992.3,4998.3
XS Rating Curve= 0 ,0
Exp/Cntr=0.3,0.1

Type RM Length L Ch R = 1 ,1721    ,674,674,674
BEGIN DESCRIPTION:
Mapping XS 695b0b82
END DESCRIPTION:
XS GIS Cut Line= 2
      2368408.01     13178426.842367727.5755805213177817.4966185
#Sta/Elev= 30
  4283.1  103.71  4339.7  102.73  4361.4  103.21  4389.8  101.72  4427.6  100.89
  4467.6   99.24  4545.3   98.68  4602.2    96.3  4644.8    95.8  4672.8   94.43
  4686.6    94.7  4722.5   92.21  4757.6   92.36  4765.1   91.13  4818.5   88.85
  4835.4   88.63  4899.7   84.32  4927.8   83.96    4949   82.57  4988.7   82.27
  4991.4   81.77  4994.7   82.27  5012.6   82.53  5034.3   83.91  5067.8   83.61
  5118.7   83.78  5161.4   84.84  5175.6   85.82  5189.8   90.76  5196.5    91.6
#Mann= 6 ,-1 , 0
  4283.1     .05       0  4427.6      .1       0  4818.5     .07       0
  4988.7     .07       0  4994.7     .07       0  5067.8     .05       0
Bank Sta=4988.7,4994.7
XS Rating Curve= 0 ,0
Exp/Cntr=0.3,0.1

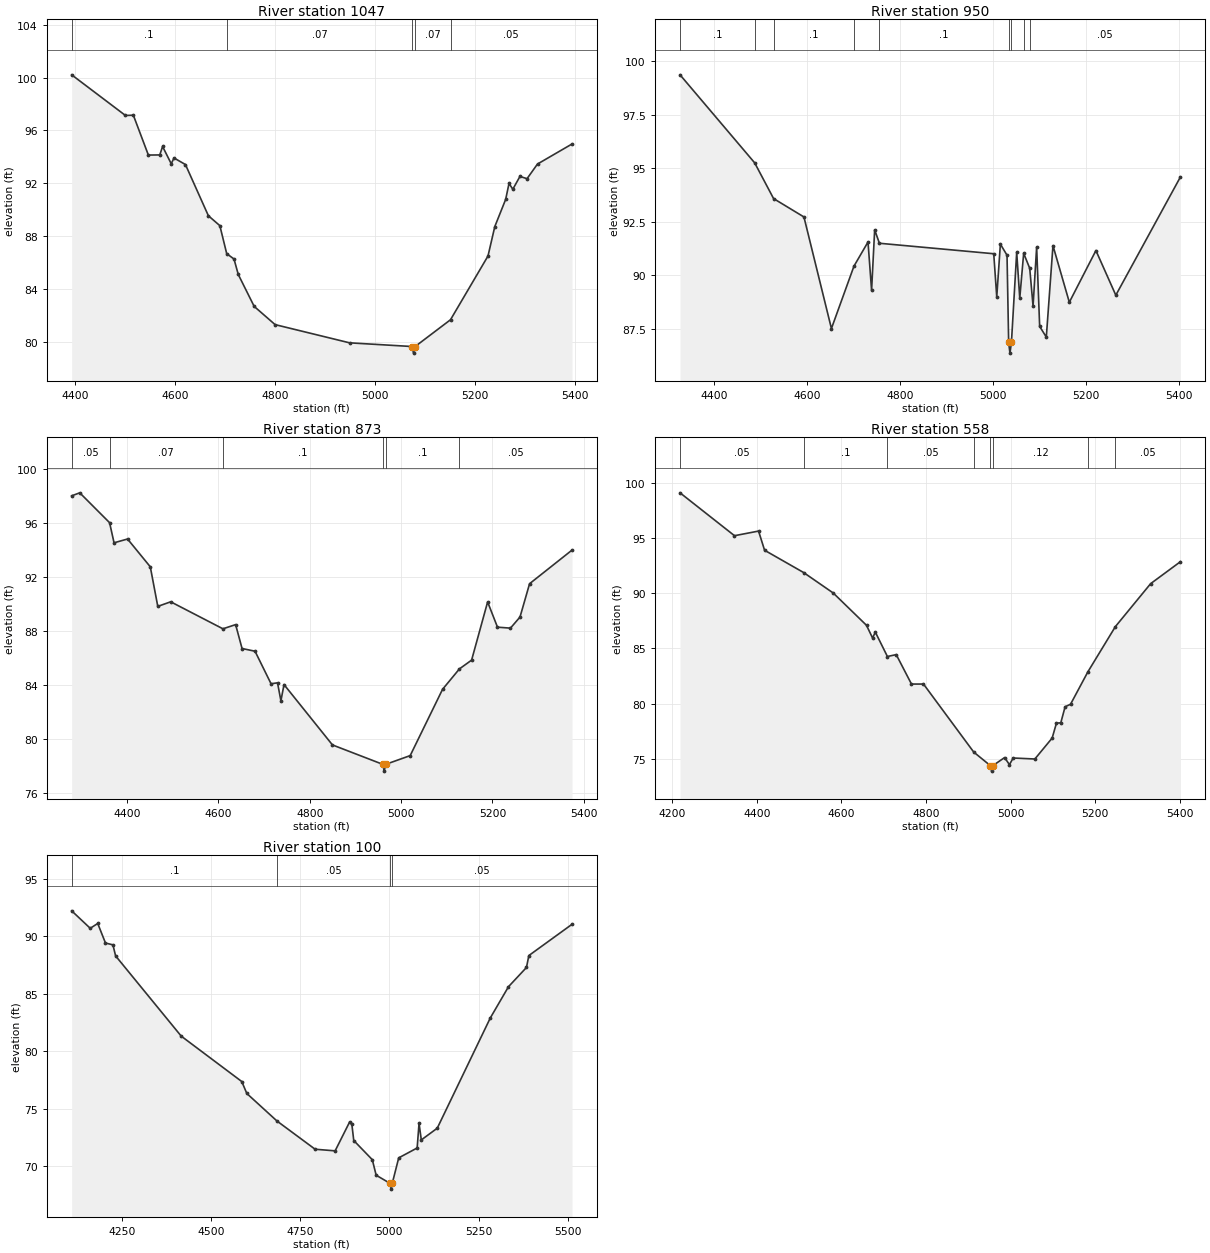
Type RM Length L Ch R = 1 ,1047    ,97,97,97
BEGIN DESCRIPTION:
Mapping XS 5203dd4a
END DESCRIPTION:
XS GIS Cut Line= 3
      2368598.35     13178048.54      2368437.74     13177703.45
      2368025.72     13177241.55
#Sta/Elev= 30
    4394  100.21  4501.4   97.13  4517.2   97.15  4547.2   94.13    4570   94.14
  4575.6   94.78  4592.9   93.47  4598.4   93.91  4621.3   93.41  4667.1   89.53
    4690   88.78  4703.7   86.66  4718.3   86.25  4726.8   85.08  4758.6   82.66
  4800.4   81.28  4949.2    79.9  5074.1   79.62  5076.9   79.12  5080.1   79.62
  5150.8   81.65  5225.7   86.48  5239.3   88.71    5261   90.77  5267.7   91.98
  5275.3   91.54  5289.5   92.51  5303.7   92.34  5324.6   93.45  5393.6   94.97
#Mann= 5 ,-1 , 0
    4394      .1       0  4703.7     .07       0  5074.1     .07       0
  5080.1     .07       0  5150.8     .05       0
Bank Sta=5074.1,5080.1
XS Rating Curve= 0 ,0
Exp/Cntr=0.3,0.1

Type RM Length L Ch R = 1 ,950     ,77,77,77
BEGIN DESCRIPTION:
UNT022 IN BACR 2.0
END DESCRIPTION:
XS GIS Cut Line= 3
      2368724.19     13178013.76      2368541.91      13177692.6
      2368086.16     13177152.21
#Sta/Elev= 30
  4327.2   99.37  4487.8   95.25  4528.4   93.58  4593.7   92.72  4652.8    87.5
  4701.3   90.42  4731.5   91.55  4739.2   89.29  4745.8   92.12    4756   91.49
  5001.9      91  5008.4   88.98  5016.2   91.45  5030.5   90.93    5034   86.85
  5036.8   86.35    5040   86.85  5051.3   91.07  5057.9   88.92  5066.3   91.02
  5079.3   90.32  5086.5   88.55  5094.2   91.31  5100.7    87.6    5115    87.1
  5129.3   91.38  5164.5   88.73  5221.7   91.15  5264.5   89.06  5403.4   94.59
#Mann= 9 ,-1 , 0
  4327.2      .1       0  4487.8     .07       0  4528.4      .1       0
  4701.3     .07       0    4756      .1       0    5034     .07       0
    5040      .1       0  5066.3     .07       0  5079.3     .05       0
Bank Sta=5034,5040
XS Rating Curve= 0 ,0
Exp/Cntr=0.3,0.1

Type RM Length L Ch R = 1 ,873     ,315,315,315
BEGIN DESCRIPTION:
Mapping XS 7ec2a8a7
END DESCRIPTION:
XS GIS Cut Line= 3
      2368949.89     13177829.31      2368630.88     13177662.21
      2368136.09     13177117.51
#Sta/Elev= 30
  4278.5   97.98  4296.2    98.2  4361.5   95.99  4371.3    94.5  4400.9   94.78
  4450.7   92.72  4467.1   89.79  4495.4   90.13  4609.8   88.13  4637.6   88.44
  4651.7   86.67  4680.1   86.47  4715.2   84.06  4729.4   84.13  4736.8    82.8
  4743.6      84  4849.7   79.53  4960.2   78.09    4963   77.59  4966.2   78.09
    5020   78.74  5090.9   83.65  5127.8   85.16  5154.5   85.81  5189.6   90.12
  5211.2   88.25  5239.6   88.18  5260.5      89  5281.5   91.47  5374.5   93.96
#Mann= 6 ,-1 , 0
  4278.5     .05       0  4361.5     .07       0  4609.8      .1       0
  4960.2     .07       0  4966.2      .1       0  5127.8     .05       0
Bank Sta=4960.2,4966.2
XS Rating Curve= 0 ,0
Exp/Cntr=0.3,0.1

Type RM Length L Ch R = 1 ,558     ,458,458,458
BEGIN DESCRIPTION:
Mapping XS 897df736
END DESCRIPTION:
XS GIS Cut Line= 3
      2369148.25     13177637.99      2368749.81     13177187.46
      2368181.06       13177068.
#Sta/Elev= 30
  4218.7   99.12  4347.4   95.23  4404.3   95.65  4418.5   93.91  4510.7   91.89
  4580.8   90.03  4659.4    87.1  4673.7   85.95  4680.3   86.48  4708.8   84.27
  4729.7   84.44  4765.7   81.77  4794.1   81.77  4912.8    75.6  4952.1   74.37
  4954.9   73.87  4958.1   74.37  4985.8    75.1  4997.2   74.46  5006.2   75.06
  5057.3   74.97  5098.2   76.87  5108.4   78.23  5118.6   78.25  5128.8   79.71
  5141.7   79.94  5182.8   82.89  5247.6   86.98    5331   90.88  5401.3   92.87
#Mann= 8 ,-1 , 0
  4218.7     .05       0  4510.7      .1       0  4708.8     .05       0
  4912.8     .12       0  4952.1     .07       0  4958.1     .12       0
  5182.8      .1       0  5247.6     .05       0
Bank Sta=4952.1,4958.1
XS Rating Curve= 0 ,0
Exp/Cntr=0.3,0.1

Type RM Length L Ch R = 1 ,100     ,0,0,0
BEGIN DESCRIPTION:
UNT022 IN BACR 1.0
END DESCRIPTION:
XS GIS Cut Line= 4
      2369278.43     13177239.51      2368783.66     13176687.46
      2368515.43     13176778.61      2368201.49     13176988.76
#Sta/Elev= 30
  4109.7   92.21  4161.7   90.69  4182.7   91.11  4204.4   89.41  4225.3   89.25
  4232.8   88.29  4416.7   81.31  4586.4   77.36  4600.6   76.32  4685.3   73.92
    4792   71.47  4848.1   71.33    4889   73.86    4895   73.63  4900.3   72.23
  4952.3   70.56  4963.1   69.21  5002.2    68.5  5004.9      68  5008.2    68.5
  5026.3   70.72    5078   71.58  5083.3   73.73  5089.6   72.28  5134.3    73.3
    5283   82.89    5334   85.61  5384.3   87.28  5391.1   88.32  5512.1   91.04
#Mann= 4 ,-1 , 0
  4109.7      .1       0  4685.3     .05       0  5002.2     .03       0
  5008.2     .05       0
Bank Sta=5002.2,5008.2
XS Rating Curve= 0 ,0
Exp/Cntr=0.3,0.1

Chan Stop Cuts=-1
Use User Specified Reach Order=0
Composite Channel Slope=5