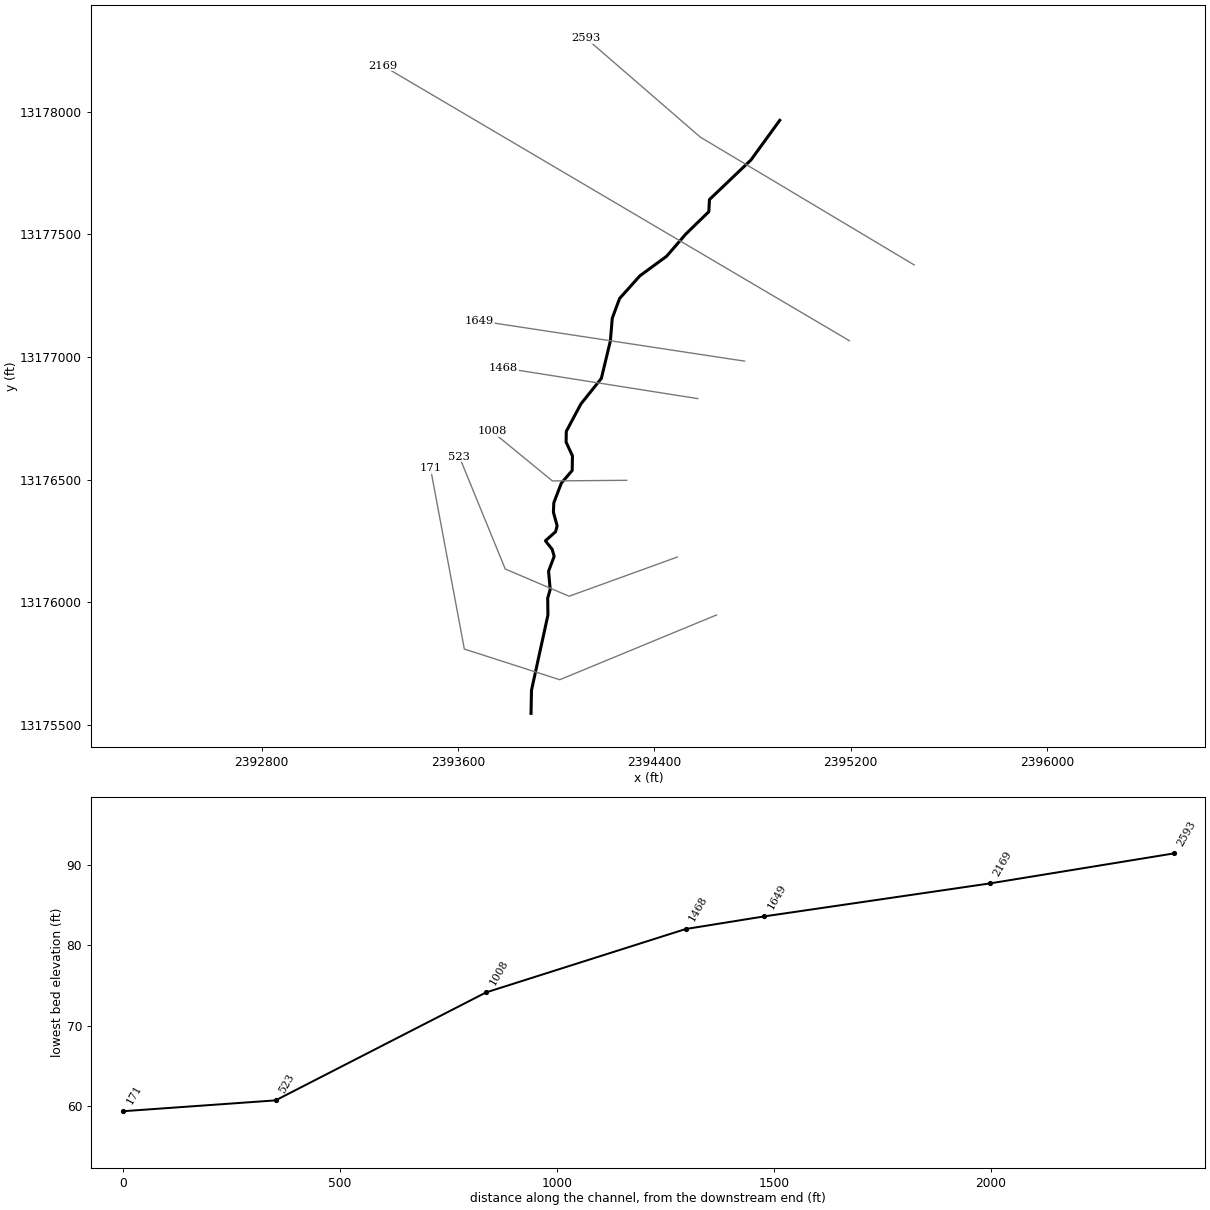
--- UNT027 IN BACR.prj (project) ---

Proj Title=UNT027 IN BACR Base Level Engineering
Current Plan=p01
Default Exp/Contr=0.3,0.1
English Units
Geom File=g01
Flow File=f01
Plan File=p01
Y Axis Title=Elevation
X Axis Title(PF)=Main Channel Distance
X Axis Title(XS)=Station
BEGIN DESCRIPTION:
UNT027 IN BACR
END DESCRIPTION:
DSS Export Rating Curves= 0
DSS Export Rating Curve Sorted= 0
DSS Export Volume Flow Curves= 0
DXF OffsetX= 0
DXF OffsetY= 0
DXF ScaleX= 1
DXF ScaleY= 10

--- UNT027 IN BACR.p01 (plan) ---

Plan Title=Multiple Run
Short Identifier=Multiple
Geom File=g01
Flow File=f01
Subcritical Flow
K Sum by GR= 0
Std Step Tol= 0.01
Critical Tol= 0.01
Num of Std Step Trials= 20
Max Error Tol= 0.3
Flow Tol Ratio= 0.001
Split Flow NTrial= 30
Split Flow Tol= 0.02
Split Flow Ratio= 0.02
Log Output Level= 0
Friction Slope Method= 1
Unsteady Friction Slope Method= 2
Unsteady Bridges Friction Slope Method= 1
Parabolic Critical Depth
Global Vel Dist=  1 , 1 , 1
Global Log Level= 0
CheckData=True
Encroach Param= -1, 0, 0, 0
BEGIN DESCRIPTION:
Multiple Run
END DESCRIPTION:

--- UNT027 IN BACR.f01 (steady flow) ---

Flow Title=Multiple
Program Version=4.10
Number of Profiles= 7
Profile Names=10-year,25-year,50-year,1pct_min,100-year,1pct_plu,500-year
River Rch & RM=UNT027 IN BACR,Reach-1         ,2593
     238     309     363     312     423     572     578
River Rch & RM=UNT027 IN BACR,Reach-1         ,1468
     338     455     549     486     657     888     946
Boundary for River Rch & Prof#=UNT027 IN BACR,Reach-1         , 1
Up Type= 0
Dn Type= 3
Dn Slope=0.003
Boundary for River Rch & Prof#=UNT027 IN BACR,Reach-1         , 2
Up Type= 0
Dn Type= 3
Dn Slope=0.003
Boundary for River Rch & Prof#=UNT027 IN BACR,Reach-1         , 3
Up Type= 0
Dn Type= 3
Dn Slope=0.003
Boundary for River Rch & Prof#=UNT027 IN BACR,Reach-1         , 4
Up Type= 0
Dn Type= 3
Dn Slope=0.003
Boundary for River Rch & Prof#=UNT027 IN BACR,Reach-1         , 5
Up Type= 0
Dn Type= 3
Dn Slope=0.003
Boundary for River Rch & Prof#=UNT027 IN BACR,Reach-1         , 6
Up Type= 0
Dn Type= 3
Dn Slope=0.003
Boundary for River Rch & Prof#=UNT027 IN BACR,Reach-1         , 7
Up Type= 0
Dn Type= 3
Dn Slope=0.003
DSS Import GetInterval= 0
DSS Import GetPeak= 0
DSS Import FillOption= 0

--- UNT027 IN BACR.g01 (geometry) ---

Geom Title=Existing Conditions
Program Version=4.10

River Reach=UNT027 IN BACR  ,Reach-1
Reach XY= 30
      2394911.49     13177964.25       2394794.3     13177802.79
      2394625.03     13177641.33      2394622.42     13177591.85
      2394528.67     13177500.71       2394450.3     13177410.16
      2394341.28      13177330.3      2394258.64     13177237.94
      2394228.78     13177157.39      2394221.14     13177065.02
      2394184.33     13176912.25        2394101.     13176808.08
      2394041.36     13176696.28      2394040.71     13176652.54
      2394066.55     13176596.29      2394065.49     13176536.99
       2394021.3     13176485.48      2393990.62     13176405.49
      2393988.93      13176366.5      2394004.12     13176311.51
      2393997.56     13176286.99      2393956.28     13176250.38
      2393983.95     13176215.46        2393992.     13176187.09
       2393969.2     13176126.24      2393975.82     13176051.78
      2393965.65     13176016.93      2393966.54     13175947.55
      2393899.58     13175641.19      2393897.72     13175546.86

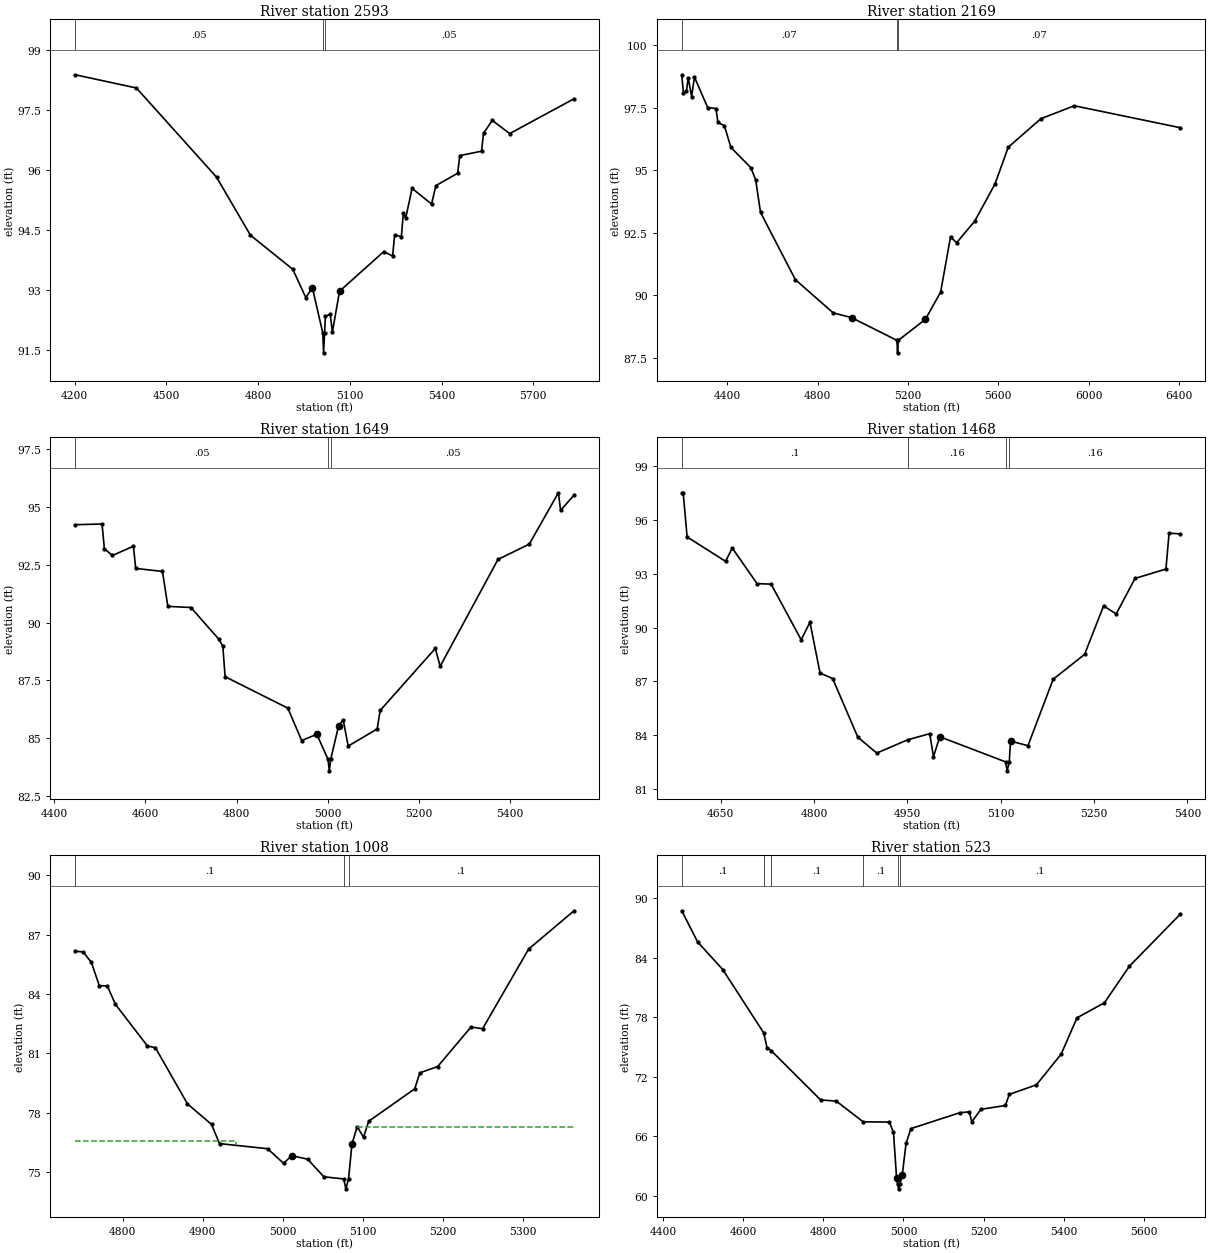
Type RM Length L Ch R = 1 ,2593    ,424,424,424
BEGIN DESCRIPTION:
UNT027 IN BACR 5.0
END DESCRIPTION:
XS GIS Cut Line= 3
      2395459.27     13177374.99       2394587.7     13177895.85
      2394122.61     13178298.47
#Sta/Elev= 30
  4202.5   98.37  4402.3   98.04  4664.4   95.81  4775.1   94.36  4913.4   93.51
  4956.2    92.8  4977.6   93.05  5011.5   91.92  5014.3   91.42  5017.5   91.92
  5020.4   92.34  5035.9   92.38  5043.1   91.94  5066.4   92.96    5211   93.95
    5240   93.84  5246.6   94.37  5268.5   94.32  5275.1   94.92  5282.7   94.79
  5303.6   95.53  5367.2   95.14  5381.5    95.6  5452.7   95.91  5459.4   96.35
  5530.6   96.46  5537.2   96.91  5565.7   97.23  5622.7    96.9    5833   97.77
#Mann= 3 ,-1 , 0
  4202.5     .05       0  5011.5    .035       0  5017.5     .05       0
Bank Sta=4977.6,5066.4
XS Rating Curve= 0 ,0
Exp/Cntr=0.3,0.1

Type RM Length L Ch R = 1 ,2169    ,520,520,520
BEGIN DESCRIPTION:
Mapping XS b52de543
END DESCRIPTION:
XS GIS Cut Line= 2
      2395195.38     13177065.96      2393292.61     13178187.48
#Sta/Elev= 30
  4198.3   98.82  4205.7   98.09  4218.8   98.16  4227.1   98.69    4242   97.95
  4254.4   98.73  4312.9   97.51    4350   97.47  4358.1   96.92  4387.1   96.78
  4416.1   95.91  4504.3    95.1  4525.7   94.61  4547.2   93.31  4701.4   90.62
  4868.8   89.29  4950.1    89.1  5151.2   88.19    5154   87.69  5157.2   88.19
  5277.1   89.03  5344.8   90.12  5388.5   92.33  5415.7    92.1  5495.7   92.96
  5585.6   94.45  5644.2   95.92  5788.5   97.06  5936.8   97.58    6407    96.7
#Mann= 3 ,-1 , 0
  4198.3     .07       0  5151.2    .035       0  5157.2     .07       0
Bank Sta=4950.1,5277.1
XS Rating Curve= 0 ,0
Exp/Cntr=0.3,0.1

Type RM Length L Ch R = 1 ,1649    ,181,181,181
BEGIN DESCRIPTION:
UNT027 IN BACR 4.0
END DESCRIPTION:
XS GIS Cut Line= 2
      2394768.22     13176982.66      2393687.72     13177146.85
#Sta/Elev= 30
  4446.7   94.23  4505.4   94.26  4510.4   93.19  4528.1    92.9  4574.1    93.3
  4579.1   92.34  4637.7   92.21  4649.5    90.7  4700.1   90.65  4760.8   89.29
    4770   88.98    4775   87.66  4912.5    86.3  4942.8    84.9    4976   85.17
  5000.5   84.09  5003.3   83.59  5006.5   84.09  5023.7   85.54  5033.9   85.79
  5044.7   84.66  5108.3    85.4  5114.8    86.2  5235.6   88.88  5246.3   88.11
    5373   92.73  5441.6   93.39  5505.3   95.61  5510.3   94.85  5539.6   95.51
#Mann= 3 ,-1 , 0
  4446.7     .05       0  5000.5     .04       0  5006.5     .05       0
Bank Sta=4976,5023.7
XS Rating Curve= 0 ,0
Exp/Cntr=0.3,0.1

Type RM Length L Ch R = 1 ,1468    ,460,460,460
BEGIN DESCRIPTION:
UNT027 IN BACR 3.0
END DESCRIPTION:
XS GIS Cut Line= 2
      2394577.25     13176829.88      2393785.65     13176954.87
#Sta/Elev= 30
  4587.6   97.51  4589.9   97.51  4596.2   95.05    4658   93.69  4668.8   94.43
  4708.6   92.45  4731.2   92.42  4779.5   89.32  4793.6    90.3  4809.8   87.47
  4830.1   87.16  4870.6   83.89    4901   83.01  4950.7   83.75    4986   84.09
  4992.1   82.81  5002.2   83.92  5107.9   82.52  5110.6   82.02  5113.9   82.52
  5115.9   83.68  5143.9   83.42  5184.4   87.12    5235   88.51  5265.4   91.21
  5285.7   90.76    5316   92.74  5365.6   93.26  5370.7   95.26    5389   95.22
#Mann= 4 ,-1 , 0
  4587.6      .1       0  4950.7     .16       0  5107.9     .07       0
  5113.9     .16       0
Bank Sta=5002.2,5115.9
XS Rating Curve= 0 ,0
Exp/Cntr=0.3,0.1

Type RM Length L Ch R = 1 ,1008    ,485,485,485
BEGIN DESCRIPTION:
UNT027 IN BACR 2.0
END DESCRIPTION:
XS GIS Cut Line= 3
      2394287.76     13176496.86      2393984.73     13176494.46
       2393737.7     13176696.87
#Sta/Elev= 30
  4740.9   86.17  4750.9   86.12  4760.9    85.6  4770.9   84.42  4780.9   84.41
  4790.9   83.48  4830.9   81.37  4840.9   81.28  4880.9   78.44  4910.9    77.4
  4920.9   76.43  4980.9   76.17  5000.9   75.43  5010.9   75.82  5030.9   75.64
  5051.1   74.75  5075.9   74.64  5078.6   74.14  5081.9   74.64  5086.2   76.41
  5092.7   77.29  5100.6   76.75  5107.1   77.56  5164.5    79.2  5170.9   80.01
  5193.2   80.33  5234.8   82.33  5249.2   82.24  5306.6   86.27  5363.3   88.21
#Mann= 3 ,-1 , 0
  4740.9      .1       0  5075.9    .035       0  5081.9      .1       0
#XS Ineff= 2 , 0
       0 4940.86   76.54 5092.56       0   77.28
Permanent Ineff=
       T       T
Bank Sta=5010.9,5086.2
XS Rating Curve= 0 ,0
Exp/Cntr=0.3,0.1

Type RM Length L Ch R = 1 ,523     ,352,352,352
BEGIN DESCRIPTION:
Mapping XS d5fac7c5
END DESCRIPTION:
XS GIS Cut Line= 4
      2394493.97     13176184.05      2394052.98     13176024.32
      2393792.56     13176135.43      2393605.46     13176592.78
#Sta/Elev= 30
  4445.9   88.74  4485.7   85.59  4548.3   82.82  4650.5   76.45  4658.9   74.96
  4669.1   74.66  4792.9   69.68  4832.1   69.56  4899.4   67.47  4964.6   67.45
    4975   66.41  4982.8   61.77  4985.2   61.22    4988   60.72  4991.2   61.22
  4996.8   62.07  5006.4    65.3  5018.5   66.79  5140.8   68.39  5164.4   68.48
  5170.7   67.47  5193.4   68.73  5254.7   69.12  5264.4   70.24  5332.2    71.2
  5394.1    74.3  5433.6   77.95  5502.1   79.47  5564.5   83.15  5692.2   88.42
#Mann= 6 ,-1 , 0
  4445.9      .1       0  4650.5     .05       0  4669.1      .1       0
  4899.4      .1       0  4985.2    .035       0  4991.2      .1       0
Bank Sta=4982.8,4996.8
XS Rating Curve= 0 ,0
Exp/Cntr=0.3,0.1

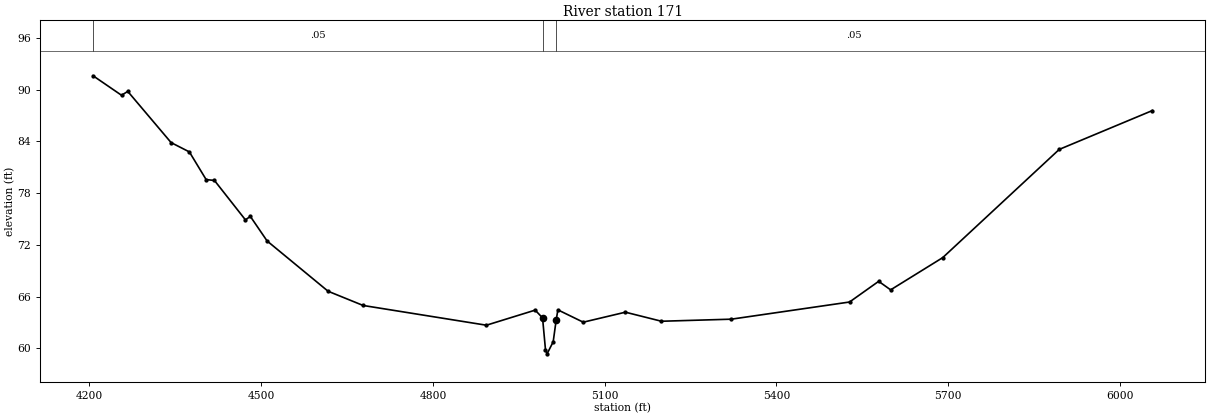
Type RM Length L Ch R = 1 ,171     ,0,0,0
BEGIN DESCRIPTION:
UNT027 IN BACR 1.0
END DESCRIPTION:
XS GIS Cut Line= 4
      2394653.69     13175947.93      2394014.79     13175684.04
       2393625.9     13175809.04      2393487.72     13176546.87
#Sta/Elev= 30
  4206.3   91.62    4256   89.36  4266.9   89.81  4342.6   83.87  4374.5   82.79
  4403.8   79.58  4418.3   79.48  4472.4   74.91    4481   75.31  4510.3   72.46
  4616.8   66.63    4678   64.98  4893.3   62.69  4978.5   64.44  4991.4   63.54
  4996.5   59.87  4999.3   59.37    5010   60.77 5015.16   63.28  5018.2   64.47
  5062.5   63.04  5136.1    64.2  5199.1   63.15  5321.2   63.39  5527.6   65.38
  5578.5   67.78  5599.4   66.79  5690.4   70.53  5893.9   83.08  6056.7   87.59
#Mann= 3 , 0 , 0
  4206.3     .05       0  4991.4    .035       0 5015.16     .05       0
Bank Sta=4991.4,5015.16
XS Rating Curve= 0 ,0
Exp/Cntr=0.3,0.1

Chan Stop Cuts=-1
Use User Specified Reach Order=0
Composite Channel Slope=5