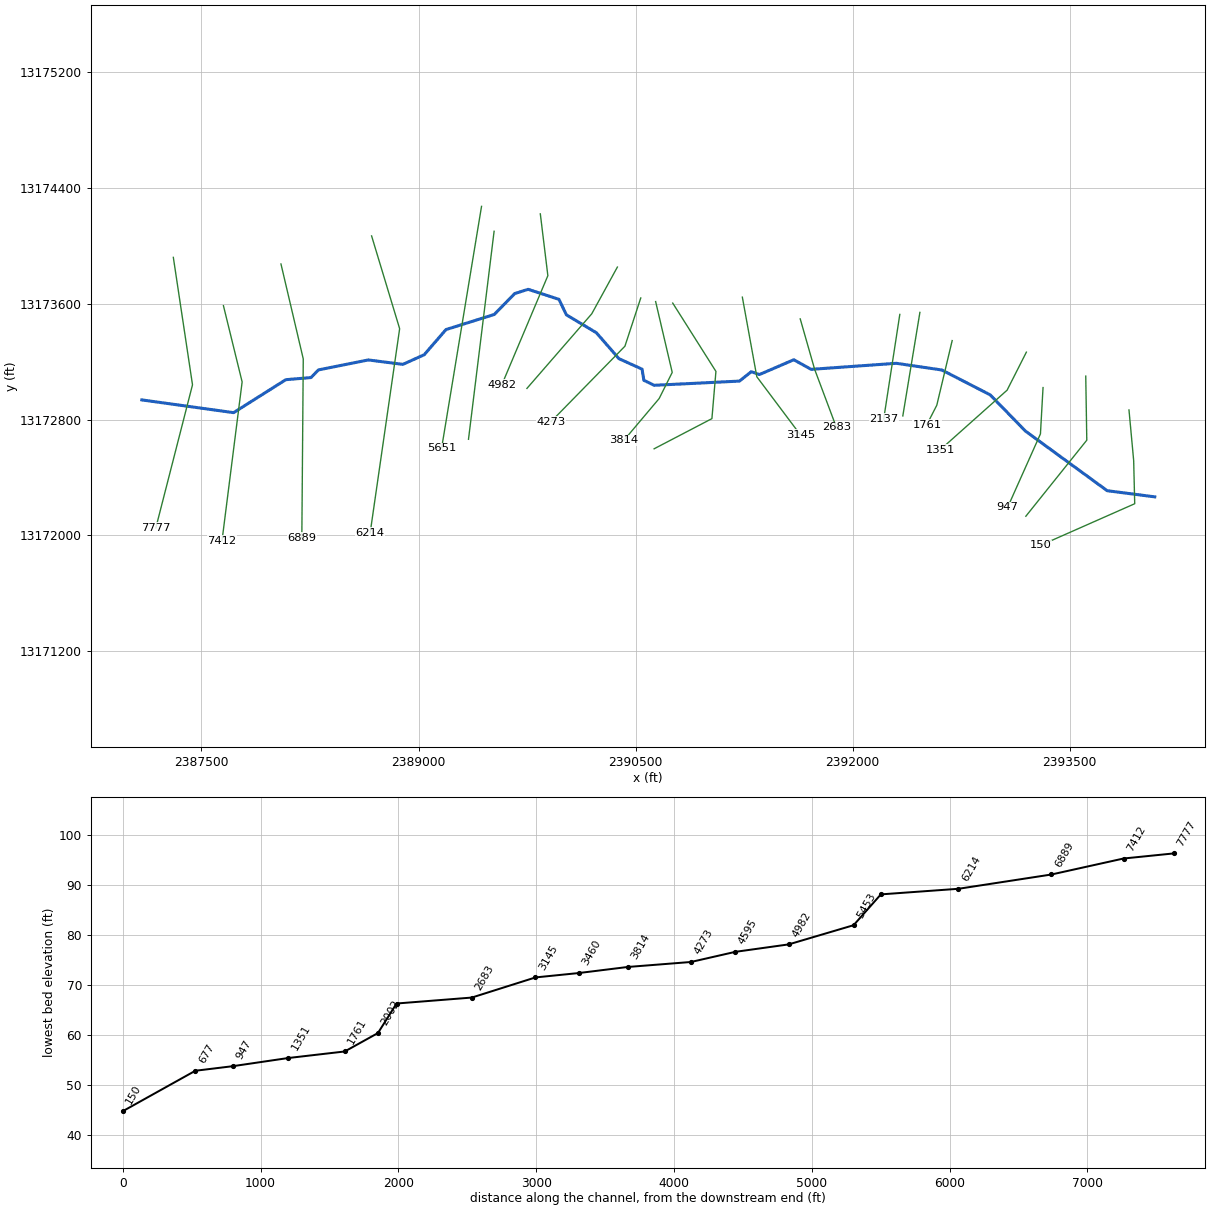
--- UNT028 IN BACR.prj (project) ---

Proj Title=UNT028 IN BACR Base Level Engineering
Current Plan=p01
Default Exp/Contr=0.3,0.1
English Units
Geom File=g01
Flow File=f01
Plan File=p01
Y Axis Title=Elevation
X Axis Title(PF)=Main Channel Distance
X Axis Title(XS)=Station
BEGIN DESCRIPTION:
UNT028 IN BACR
END DESCRIPTION:
DSS Export Rating Curves= 0
DSS Export Rating Curve Sorted= 0
DSS Export Volume Flow Curves= 0
DXF OffsetX= 0
DXF OffsetY= 0
DXF ScaleX= 1
DXF ScaleY= 10

--- UNT028 IN BACR.p01 (plan) ---

Plan Title=Multiple Run
Short Identifier=Multiple
Geom File=g01
Flow File=f01
Subcritical Flow
K Sum by GR= 0
Std Step Tol= 0.01
Critical Tol= 0.01
Num of Std Step Trials= 20
Max Error Tol= 0.3
Flow Tol Ratio= 0.001
Split Flow NTrial= 30
Split Flow Tol= 0.02
Split Flow Ratio= 0.02
Log Output Level= 0
Friction Slope Method= 1
Unsteady Friction Slope Method= 2
Unsteady Bridges Friction Slope Method= 1
Parabolic Critical Depth
Global Vel Dist=  1 , 1 , 1
Global Log Level= 0
CheckData=True
Encroach Param= -1, 0, 0, 0
BEGIN DESCRIPTION:
Multiple Run
END DESCRIPTION:

--- UNT028 IN BACR.f01 (steady flow) ---

Flow Title=Multiple
Number of Profiles=7
Profile Names=10-year,25-year,50-year,1pct_min,100-year,1pct_plu,500-year
River Rch & RM= UNT028 IN BACR,Reach-1,7777
     417     555     664     580     785    1061    1105
River Rch & RM= UNT028 IN BACR,Reach-1,3145
     624     855    1044     930    1257    1701    1843
Boundary for River Rch & Prof#=UNT028 IN BACR,Reach-1,1
Up Type=0
Dn Type=3
Dn Slope=0.005
Boundary for River Rch & Prof#=UNT028 IN BACR,Reach-1,2
Up Type=0
Dn Type=3
Dn Slope=0.005
Boundary for River Rch & Prof#=UNT028 IN BACR,Reach-1,3
Up Type=0
Dn Type=3
Dn Slope=0.005
Boundary for River Rch & Prof#=UNT028 IN BACR,Reach-1,4
Up Type=0
Dn Type=3
Dn Slope=0.005
Boundary for River Rch & Prof#=UNT028 IN BACR,Reach-1,5
Up Type=0
Dn Type=3
Dn Slope=0.005
Boundary for River Rch & Prof#=UNT028 IN BACR,Reach-1,6
Up Type=0
Dn Type=3
Dn Slope=0.005
Boundary for River Rch & Prof#=UNT028 IN BACR,Reach-1,7
Up Type=0
Dn Type=3
Dn Slope=0.005

--- UNT028 IN BACR.g01 (geometry) ---

Geom Title=Existing Conditions
Program Version=4.10

River Reach=UNT028 IN BACR  ,Reach-1
Reach XY= 30
      2387087.72     13172936.86      2387721.96     13172848.77
       2388082.9     13173076.67       2388256.8     13173091.14
      2388308.33     13173144.11      2388652.67       13173213.
      2388891.83     13173182.44      2389039.36     13173249.18
      2389189.67     13173422.97      2389522.78     13173527.03
      2389665.19     13173671.99       2389757.6     13173701.07
      2389970.32     13173631.81      2390021.78     13173524.66
      2390229.13     13173400.88      2390384.99     13173221.72
      2390544.59     13173149.41      2390557.18     13173072.55
      2390627.93     13173037.79      2391217.72     13173066.85
      2391299.53     13173131.81      2391356.08     13173112.21
      2391593.23     13173214.45      2391713.15     13173148.01
      2392301.62     13173189.81      2392616.34     13173143.53
      2392950.36     13172971.84      2393193.79      13172721.6
       2393758.8     13172309.46      2394087.72     13172266.86

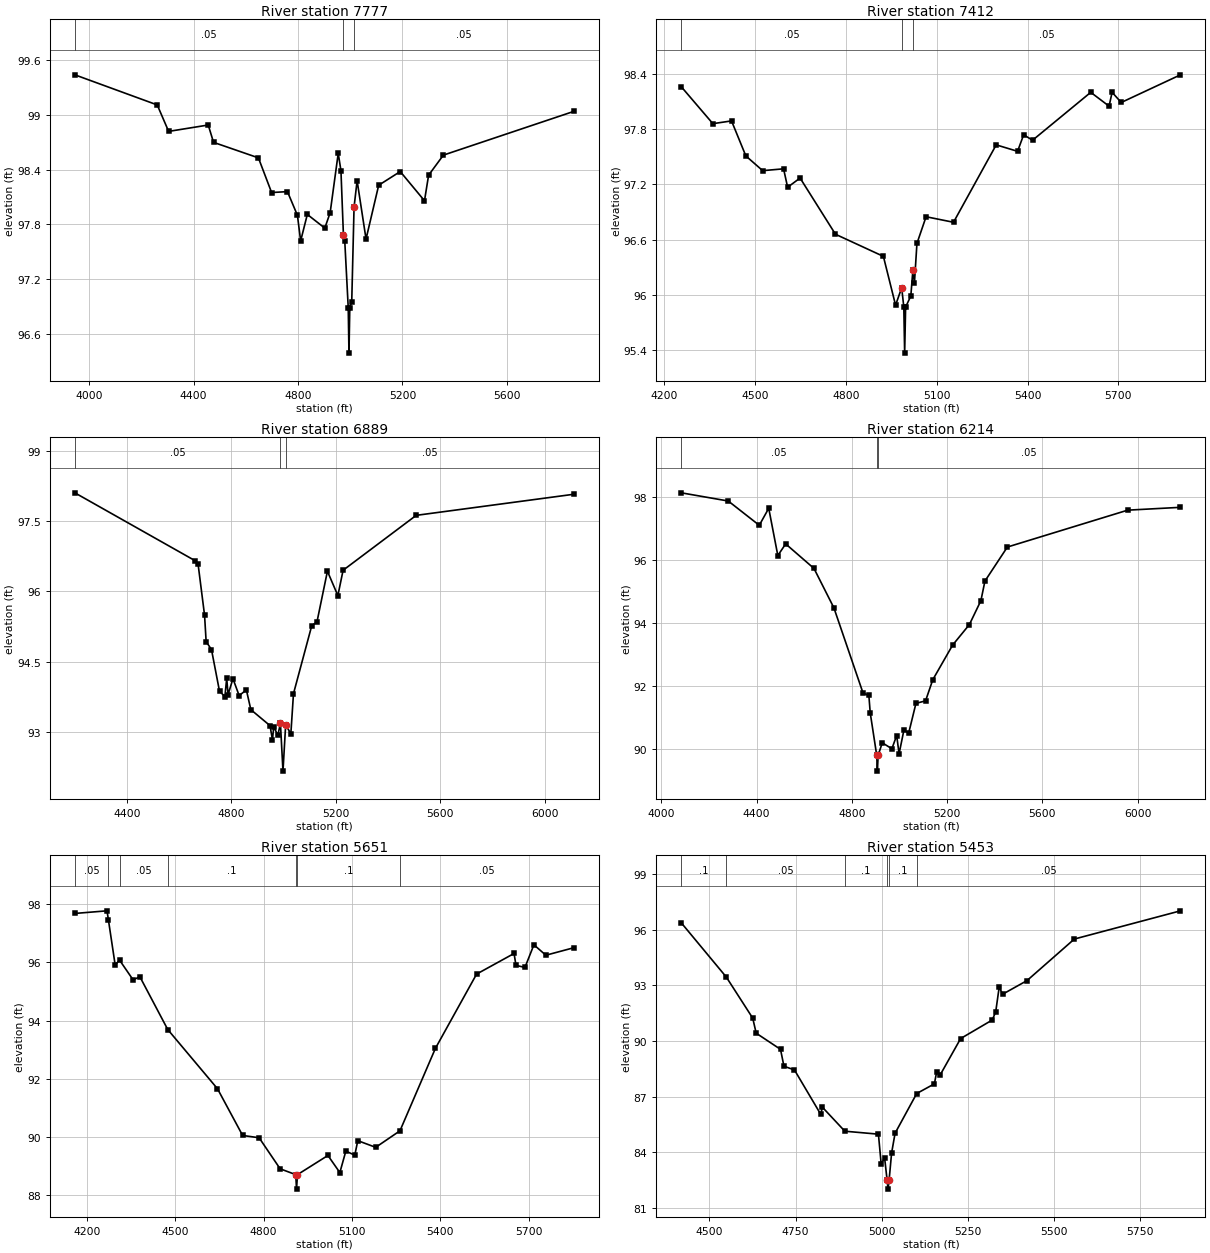
Type RM Length L Ch R = 1 ,7777    ,365,365,365
BEGIN DESCRIPTION:
UNT028 IN BACR 17.0
END DESCRIPTION:
XS GIS Cut Line= 3
      2387305.51       13173922.        2387438.     13173041.25
      2387184.52     13172052.17
#Sta/Elev= 30
  3945.6   99.44  4261.1   99.11  4304.7   98.82  4456.4   98.89  4476.7    98.7
  4648.6   98.53  4699.1   98.15  4759.8   98.16    4798    97.9  4810.4   97.62
  4835.9   97.91  4902.9   97.76  4923.4   97.93  4954.3   98.58  4964.7   98.39
  4974.1   97.69  4979.3   97.62  4992.6   96.89  4995.4   96.39  4998.6   96.89
    5006   96.95  5014.9   97.99  5026.6   98.28  5060.8   97.64  5109.2   98.23
  5191.8   98.38  5284.7   98.06  5300.4   98.34    5357   98.56  5857.3   99.04
#Mann= 3 , 0 , 0
  3945.6     .05       0  4974.1    .035       0  5014.9     .05       0
Bank Sta=4974.1,5014.9
XS Rating Curve= 0 ,0
Exp/Cntr=0.3,0.1

Type RM Length L Ch R = 1 ,7412    ,523,523,523
BEGIN DESCRIPTION:
UNT028 IN BACR 16.0
END DESCRIPTION:
XS GIS Cut Line= 3
      2387651.72     13173588.02      2387780.95     13173061.13
      2387641.79     13171962.72
#Sta/Elev= 30
  4255.7   98.26  4359.9   97.86  4421.6   97.89  4468.9   97.51  4524.6   97.35
  4593.6   97.37    4607   97.17  4648.2   97.27  4765.1   96.66  4923.5   96.42
  4963.8   95.89    4984   96.08    4991   95.87  4993.8   95.37    4997   95.87
  5014.2   95.99    5021   96.27  5026.1   96.13  5034.4   96.56  5064.6   96.85
  5155.3   96.79  5296.4   97.63    5367   97.56  5387.2   97.74  5416.5   97.68
  5608.9    98.2  5669.4   98.05  5679.5    98.2  5709.7   98.09  5905.4   98.39
#Mann= 3 , 0 , 0
  4255.7     .05       0    4984    .035       0    5021     .05       0
Bank Sta=4984,5021
XS Rating Curve= 0 ,0
Exp/Cntr=0.3,0.1

Type RM Length L Ch R = 1 ,6889    ,675,675,675
BEGIN DESCRIPTION:
UNT028 IN BACR 15.0
END DESCRIPTION:
XS GIS Cut Line= 3
      2388049.35     13173876.21      2388203.42     13173220.18
      2388193.48      13171982.6
#Sta/Elev= 30
  4200.6    98.1  4662.2   96.65  4672.5   96.58  4697.3   95.49  4703.3   94.93
  4723.8   94.76  4754.6   93.87  4775.2   93.76  4782.1   94.15  4787.3    93.8
    4806   94.14  4829.7   93.78  4857.4    93.9  4874.5   93.48  4947.8   93.14
  4957.3   92.84  4962.3   93.12  4977.8   92.93  4987.8   93.19  4997.6   92.17
  5007.8   93.15  5027.8   92.97  5037.8   93.82  5107.8   95.27  5127.8   95.35
  5167.8   96.43  5207.8   95.91  5227.8   96.45  5507.8   97.62  6112.1   98.07
#Mann= 3 ,-1 , 0
  4200.6     .05       0  4987.8    .035       0  5007.8     .05       0
Bank Sta=4987.8,5007.8
XS Rating Curve= 0 ,0
Exp/Cntr=0.3,0.1

Type RM Length L Ch R = 1 ,6214    ,563,563,563
BEGIN DESCRIPTION:
UNT028 IN BACR 14.0
END DESCRIPTION:
XS GIS Cut Line= 3
      2388675.59     13174070.11      2388869.43     13173428.93
      2388665.66     13172017.41
#Sta/Elev= 30
  4084.3   98.14  4281.4   97.88  4411.6   97.11  4451.3   97.65  4489.5   96.15
  4522.4   96.52  4641.4   95.74    4725   94.49  4847.2   91.79  4871.8   91.71
  4877.5   91.16  4904.8   89.81  4907.5   89.31  4910.8   89.81    4928   90.21
  4968.4   90.02  4988.6   90.44  4998.7   89.86  5018.9   90.61  5039.1   90.52
  5069.5   91.46  5109.9   91.54  5140.2   92.21  5223.6   93.31  5293.9   93.96
  5342.3   94.72  5359.2   95.34  5453.4   96.42  5958.6   97.59  6180.3   97.68
#Mann= 3 ,-1 , 0
  4084.3     .05       0  4904.8    .035       0  4910.8     .05       0
Bank Sta=4904.8,4910.8
XS Rating Curve= 0 ,0
Exp/Cntr=0.3,0.1

Type RM Length L Ch R = 1 ,5651    ,198,198,198
BEGIN DESCRIPTION:
UNT028 IN BACR 13.0
END DESCRIPTION:
XS GIS Cut Line= 2
      2389435.36     13174274.48      2389159.32     13172602.61
#Sta/Elev= 30
    4159   97.69  4268.1   97.78    4273   97.46  4295.7   95.92  4310.8   96.08
  4356.8    95.4  4379.6   95.51  4474.3   93.69  4643.1   91.65  4728.5   90.04
  4784.5   89.96  4855.9   88.89  4908.8   88.69  4911.5   88.19  4914.8   88.69
  5018.1   89.35  5058.6   88.76  5078.9    89.5  5109.3   89.36  5119.5   89.86
  5180.3   89.63  5262.7    90.2    5383   93.04  5522.8    95.6    5650   96.31
  5656.6    95.9    5687   95.83  5717.4   96.61    5758   96.25  5853.5   96.51
#Mann= 7 ,-1 , 0
    4159     .05       0    4273      .1       0  4310.8     .05       0
  4474.3      .1       0  4908.8     .07       0  4914.8      .1       0
  5262.7     .05       0
Bank Sta=4908.8,4914.8
XS Rating Curve= 0 ,0
Exp/Cntr=0.3,0.1

Type RM Length L Ch R = 1 ,5453    ,471,471,471
BEGIN DESCRIPTION:
UNT028 IN BACR 12.0
END DESCRIPTION:
XS GIS Cut Line= 2
      2389522.25     13174102.46      2389345.26     13172664.72
#Sta/Elev= 30
  4418.6   96.36  4549.2   93.44  4625.8   91.23  4635.8   90.42  4706.4   89.55
  4716.4   88.64  4746.9   88.44  4823.1   86.05  4828.1   86.43  4893.1   85.14
  4990.6   84.98  4998.6   83.37  5008.6    83.7  5015.7   82.52  5018.5   82.02
  5021.7   82.52  5028.8   83.96  5038.9   85.03  5101.7   87.17    5153   87.69
  5159.8   88.35  5169.8   88.17  5229.2   90.13    5321   91.13    5331   91.57
  5341.1    92.9  5351.2   92.52  5421.7   93.25  5559.2   95.49  5867.2   97.01
#Mann= 6 ,-1 , 0
  4418.6      .1       0  4549.2     .05       0  4893.1      .1       0
  5015.7     .07       0  5021.7      .1       0  5101.7     .05       0
Bank Sta=5015.7,5021.7
XS Rating Curve= 0 ,0
Exp/Cntr=0.3,0.1

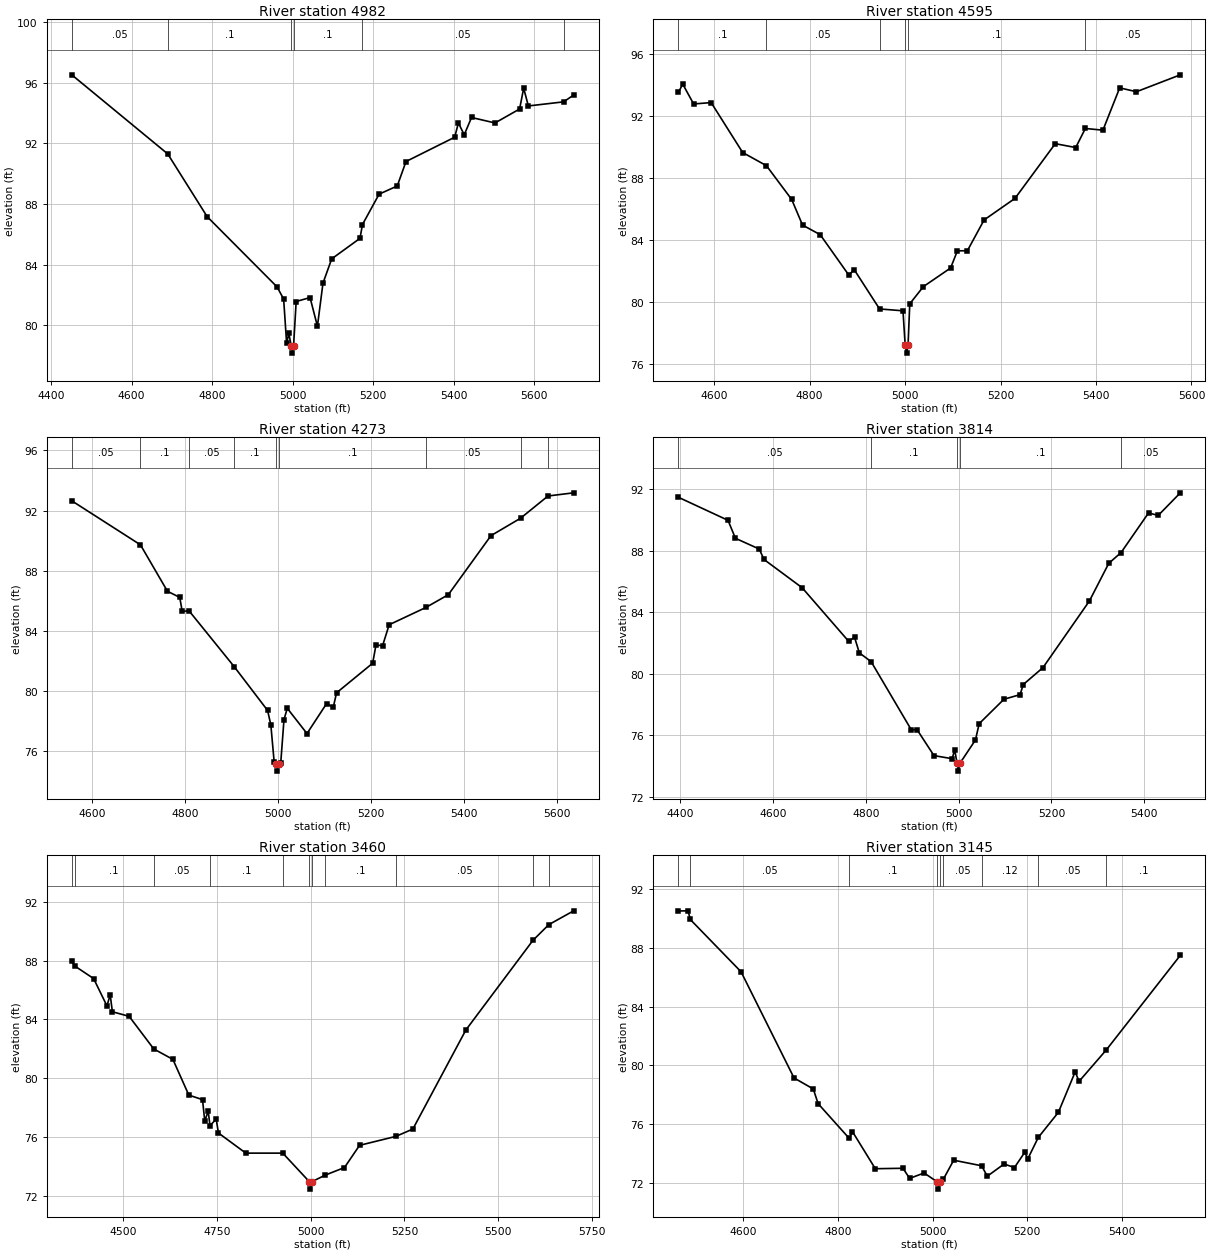
Type RM Length L Ch R = 1 ,4982    ,387,387,387
BEGIN DESCRIPTION:
UNT028 IN BACR 11.0
END DESCRIPTION:
XS GIS Cut Line= 3
      2389841.61     13174222.41      2389893.69      13173795.3
      2389576.23     13173043.12
#Sta/Elev= 30
  4451.2   96.51  4689.6    91.3  4787.5   87.17  4961.2   82.54  4977.5   81.74
  4984.9   78.82  4990.3   79.48  4996.2   78.68  4998.9   78.18  5002.2   78.68
  5008.6   81.58  5043.1   81.84  5061.4   79.95  5075.2   82.79  5096.9   84.39
  5167.1   85.74  5173.3   86.65  5214.6   88.65  5259.7   89.19  5281.4    90.8
  5402.3    92.4  5411.6   93.34    5426   92.56  5444.2    93.7  5502.5   93.34
  5563.6   94.26  5573.7   95.63  5585.3   94.46  5672.9   94.73  5697.9   95.18
#Mann= 6 ,-1 , 0
  4451.2     .05       0  4689.6      .1       0  4996.2     .07       0
  5002.2      .1       0  5173.3     .05       0  5672.9      .1       0
Bank Sta=4996.2,5002.2
XS Rating Curve= 0 ,0
Exp/Cntr=0.3,0.1

Type RM Length L Ch R = 1 ,4595    ,322,322,322
BEGIN DESCRIPTION:
UNT028 IN BACR 10.0
END DESCRIPTION:
XS GIS Cut Line= 3
      2390374.16     13173854.84      2390197.08     13173531.94
      2389749.15     13173016.29
#Sta/Elev= 30
  4525.3   93.51  4534.4   94.04  4557.2   92.76  4593.9   92.85  4659.9   89.63
  4709.7   88.78  4762.6    86.6  4785.3   84.95  4822.3   84.33  4882.1   81.73
  4893.6   82.07  4946.6   79.54  4995.7   79.42  5000.3   77.19  5003.1   76.69
  5006.3   77.19  5009.9   79.87  5038.4   80.98  5095.4   82.18  5109.7   83.29
  5130.5   83.29  5165.6   85.28  5230.3   86.67  5314.7    90.2  5357.5   89.95
  5377.7   91.18  5414.5   91.07  5449.6    93.8  5484.7   93.55  5576.6   94.64
#Mann= 6 ,-1 , 0
  4525.3      .1       0  4709.7     .05       0  4946.6      .1       0
  5000.3     .07       0  5006.3      .1       0  5377.7     .05       0
Bank Sta=5000.3,5006.3
XS Rating Curve= 0 ,0
Exp/Cntr=0.3,0.1

Type RM Length L Ch R = 1 ,4273    ,459,459,459
BEGIN DESCRIPTION:
Mapping XS 9724fc39
END DESCRIPTION:
XS GIS Cut Line= 3
      2390535.63     13173641.33      2390426.25     13173307.98
      2389915.82     13172787.13
#Sta/Elev= 30
  4556.3   92.65  4704.1   89.72  4762.2   86.63  4788.7   86.22    4794   85.29
  4808.6   85.33  4905.9   81.61  4977.7    78.7  4984.7   77.74  4991.8   75.29
  4995.8   75.16  4998.6   74.66  5001.8   75.16    5006    75.2    5013   78.09
  5020.1   78.84  5062.5   77.16  5104.8   79.16    5119    78.9  5126.1   79.87
  5203.8   81.84    5211   83.06  5225.1      83  5239.3    84.4  5318.3   85.55
  5366.6    86.4  5458.4   90.33  5522.1   91.49  5581.2   92.97  5636.4   93.18
#Mann= 9 ,-1 , 0
  4556.3     .05       0  4704.1      .1       0  4808.6     .05       0
  4905.9      .1       0  4995.8     .07       0  5001.8      .1       0
  5318.3     .05       0  5522.1      .1       0  5581.2     .05       0
Bank Sta=4995.8,5001.8
XS Rating Curve= 0 ,0
Exp/Cntr=0.3,0.1

Type RM Length L Ch R = 1 ,3814    ,354,354,354
BEGIN DESCRIPTION:
UNT028 IN BACR 9.0
END DESCRIPTION:
XS GIS Cut Line= 4
      2390638.48      13173616.5      2390753.07     13173126.89
      2390662.79     13172946.34      2390419.74     13172658.15
#Sta/Elev= 30
  4396.1   91.49    4503   89.99    4519   88.82  4570.3   88.12  4580.6   87.44
  4662.8    85.6  4763.1   82.11  4775.7   82.38    4786   81.36  4811.4   80.79
  4898.2   76.34  4910.2   76.37  4946.9   74.67    4986   74.47  4991.6   75.05
  4996.6   74.16  4999.4   73.66  5002.6   74.16  5036.3   75.69  5044.3   76.75
  5097.7   78.34  5132.4   78.64  5139.4    79.3  5181.8    80.4  5281.9   84.74
  5323.6   87.19  5350.1   87.89  5409.3   90.47  5430.2   90.31  5477.8   91.78
#Mann= 5 ,-1 , 0
  4396.1     .05       0  4811.4      .1       0  4996.6     .07       0
  5002.6      .1       0  5350.1     .05       0
Bank Sta=4996.6,5002.6
XS Rating Curve= 0 ,0
Exp/Cntr=0.3,0.1

Type RM Length L Ch R = 1 ,3460    ,315,315,315
BEGIN DESCRIPTION:
UNT028 IN BACR 8.0
END DESCRIPTION:
XS GIS Cut Line= 4
      2390756.56     13173606.02      2391055.15     13173133.84
      2391027.37     13172807.45      2390628.09     13172599.13
#Sta/Elev= 30
    4364   87.98  4371.7   87.64  4422.2   86.78  4457.7   84.92  4466.3   85.68
  4472.2   84.52  4516.8   84.21  4582.4   81.99  4633.3   81.28  4675.7   78.85
  4712.2   78.54  4718.1    77.1  4727.4   77.74  4732.1   76.77  4748.6   77.22
  4754.6   76.27  4827.5    74.9  4925.9    74.9  4996.9   72.95  4999.7   72.45
  5002.9   72.95  5039.6   73.41  5090.3   73.92  5130.4   75.43  5227.2   76.04
  5272.4   76.54  5413.5   83.28  5592.1   89.38  5634.4   90.45  5700.6   91.39
#Mann= 11 ,-1 , 0
    4364     .05       0  4371.7      .1       0  4582.4     .05       0
  4732.1      .1       0  4925.9     .05       0  4996.9     .03       0
  5002.9     .05       0  5039.6      .1       0  5227.2     .05       0
  5592.1      .1       0  5634.4     .05       0
Bank Sta=4996.9,5002.9
XS Rating Curve= 0 ,0
Exp/Cntr=0.3,0.1

Type RM Length L Ch R = 1 ,3145    ,462,462,462
BEGIN DESCRIPTION:
UNT028 IN BACR 7.0
END DESCRIPTION:
XS GIS Cut Line= 3
      2391237.71      13173646.9      2391337.72     13173096.85
      2391637.74     13172696.83
#Sta/Elev= 30
  4463.8   90.51  4484.2   90.52  4488.9   89.93    4596   86.37  4707.8   79.14
  4748.4   78.39  4758.6   77.39  4824.4   75.02    4831   75.49  4879.3   72.96
  4937.7   72.99  4951.7    72.3  4982.2   72.67  5009.7   72.07  5012.5   71.57
  5015.7   72.07  5022.6   72.23  5044.7   73.54  5103.6   73.16  5115.6   72.45
    5151   73.28  5172.9   73.04  5194.7   74.08    5201   73.63  5223.2   75.09
  5265.6    76.8    5301   79.55  5309.3   78.91    5367   81.06  5522.9   87.49
#Mann= 9 ,-1 , 0
  4463.8      .1       0  4488.9     .05       0  4824.4      .1       0
  5009.7     .07       0  5015.7      .1       0  5022.6     .05       0
  5103.6     .12       0  5223.2     .05       0    5367      .1       0
Bank Sta=5009.7,5015.7
XS Rating Curve= 0 ,0
Exp/Cntr=0.3,0.1

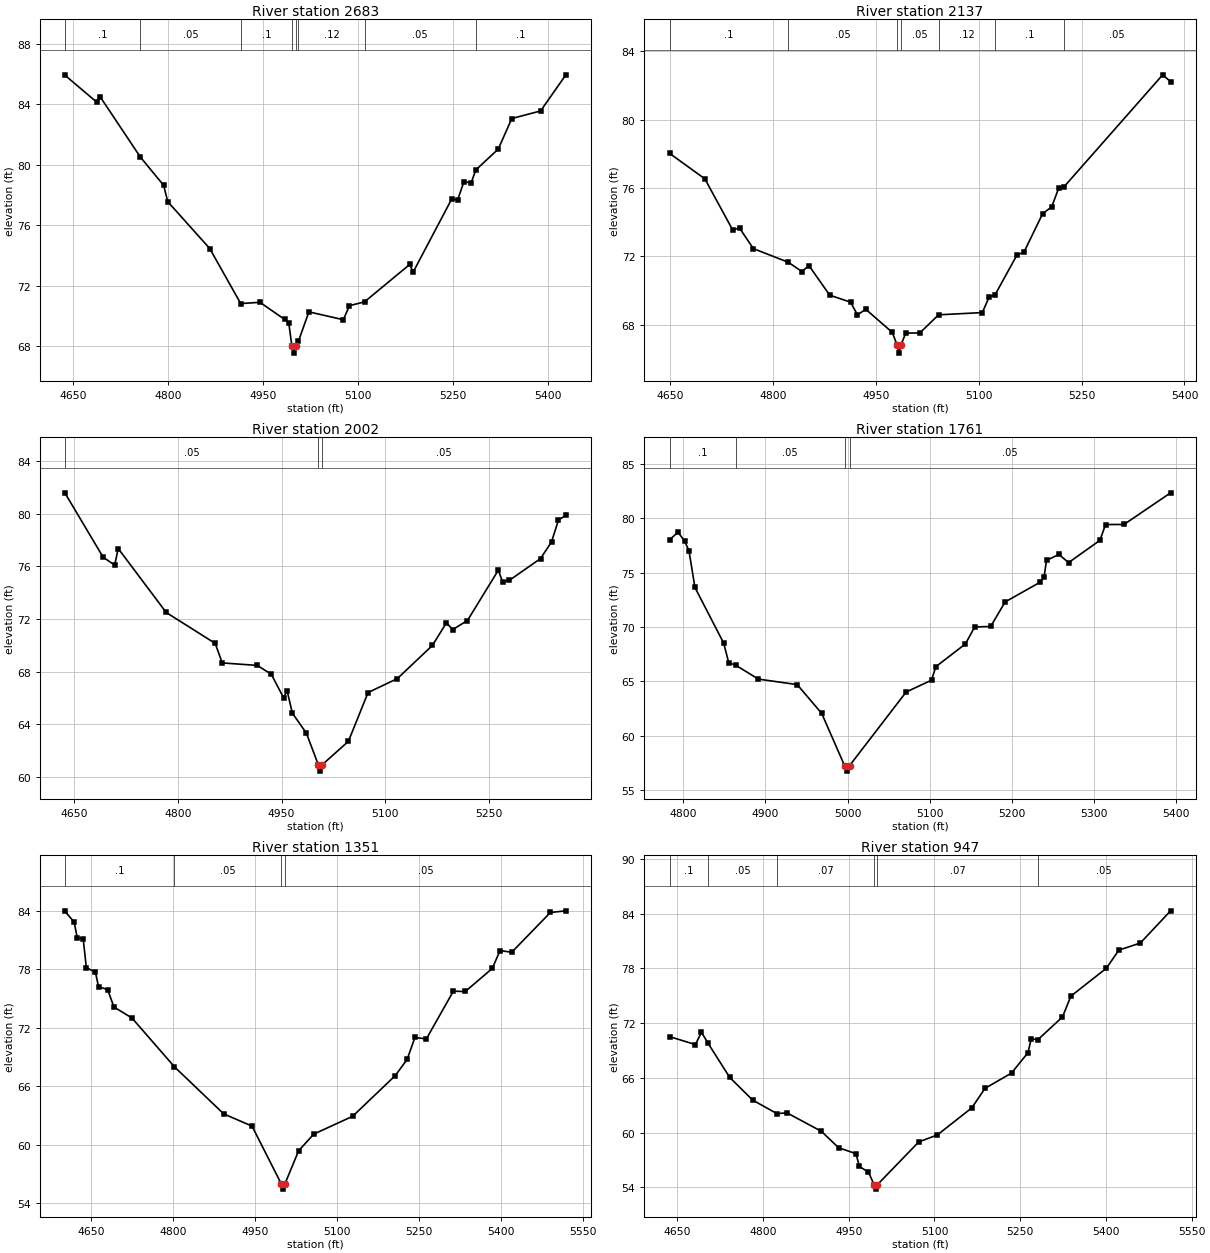
Type RM Length L Ch R = 1 ,2683    ,546,546,546
BEGIN DESCRIPTION:
UNT028 IN BACR 6.0
END DESCRIPTION:
XS GIS Cut Line= 3
      2391637.71     13173496.88      2391737.72     13173146.85
      2391887.71     13172746.88
#Sta/Elev= 30
  4636.7   85.93  4687.4   84.13  4692.6   84.49  4755.8   80.52  4792.7   78.64
  4799.2   77.56  4865.5   74.46  4914.4   70.82  4944.8    70.9  4983.8   69.77
  4990.3   69.54  4995.1   68.04  4997.9   67.54  5001.1   68.04  5005.4   68.31
  5022.1   70.27  5076.4   69.75  5086.2   70.68  5109.9   70.93  5181.4   73.41
  5186.7    72.9  5247.3   77.71  5257.1   77.69  5266.8   78.87  5278.4   78.81
  5285.5   79.65  5321.1   81.04  5342.5   83.06  5387.9   83.56  5427.9   85.95
#Mann= 8 ,-1 , 0
  4636.7      .1       0  4755.8     .05       0  4914.4      .1       0
  4995.1     .07       0  5001.1      .1       0  5005.4     .12       0
  5109.9     .05       0  5285.5      .1       0
Bank Sta=4995.1,5001.1
XS Rating Curve= 0 ,0
Exp/Cntr=0.3,0.1

Type RM Length L Ch R = 1 ,2137    ,135,135,135
BEGIN DESCRIPTION:
UNT028 IN BACR 5.0
END DESCRIPTION:
XS GIS Cut Line= 2
      2392325.82     13173527.75      2392214.69     13172805.45
#Sta/Elev= 30
  4648.9   78.03  4700.4   76.54  4740.9   73.56    4751   73.66  4771.2   72.46
  4822.2   71.66    4842   71.12  4852.2   71.47  4882.5   69.74  4912.9   69.33
    4923   68.59  4935.2   68.91  4973.6   67.57  4980.7   66.85  4983.4   66.35
  4986.7   66.85  4993.4   67.52    5014   67.53  5041.3   68.59  5105.1   68.72
  5115.2   69.64  5123.6   69.75  5155.7   72.09  5165.8   72.25  5193.2   74.51
  5206.3    74.9  5216.4   75.98    5224   76.06  5368.2   82.62  5379.7   82.22
#Mann= 7 ,-1 , 0
  4648.9      .1       0  4822.2     .05       0  4980.7     .04       0
  4986.7     .05       0  5041.3     .12       0  5123.6      .1       0
    5224     .05       0
Bank Sta=4980.7,4986.7
XS Rating Curve= 0 ,0
Exp/Cntr=0.3,0.1

Type RM Length L Ch R = 1 ,2002    ,241,241,241
BEGIN DESCRIPTION:
Mapping XS 1d88fb23
END DESCRIPTION:
XS GIS Cut Line= 2
      2392464.69     13173541.56      2392346.65     13172826.34
#Sta/Elev= 30
  4636.4   81.58  4691.8   76.69  4708.5   76.09  4713.6   77.35  4783.1   72.49
    4854   70.14  4864.1   68.66  4914.8   68.47  4935.1    67.8  4952.9   66.01
    4958   66.55  4965.5   64.85  4985.8   63.33    5003   60.94  5005.8   60.44
    5009   60.94  5046.6    62.7  5075.1   66.41  5117.5   67.47  5168.2   69.99
  5188.5   71.71  5197.4   71.19  5218.9   71.88  5263.5    75.7  5269.6   74.84
  5279.7   74.94  5324.7   76.59  5340.5   77.85  5350.6   79.52  5361.3   79.87
#Mann= 3 ,-1 , 0
  4636.4     .05       0    5003    .035       0    5009     .05       0
Bank Sta=5003,5009
XS Rating Curve= 0 ,0
Exp/Cntr=0.3,0.1

Type RM Length L Ch R = 1 ,1761    ,410,410,410
BEGIN DESCRIPTION:
UNT028 IN BACR 4.0
END DESCRIPTION:
XS GIS Cut Line= 3
      2392687.73     13173346.88      2392581.31     13172899.73
       2392512.9     13172766.51
#Sta/Elev= 30
  4783.5   78.03  4793.8   78.74    4802    77.9  4807.2   77.01  4814.4   73.65
  4849.3   68.54  4855.5   66.73  4864.2   66.49  4891.5   65.22  4938.8   64.71
  4968.6   62.06  4996.4   57.25  4999.1   56.75  5002.4   57.25  5071.3   64.03
  5102.2   65.12  5107.4   66.36  5143.3   68.45  5154.7   70.02  5174.1   70.06
  5191.7   72.32  5233.9   74.12    5239   74.59    5242   76.14    5257   76.69
  5268.9   75.94    5307   77.99  5313.8   79.44  5336.3   79.45  5392.9   82.36
#Mann= 4 ,-1 , 0
  4783.5      .1       0  4864.2     .05       0  4996.4    .035       0
  5002.4     .05       0
Bank Sta=4996.4,5002.4
XS Rating Curve= 0 ,0
Exp/Cntr=0.3,0.1

Type RM Length L Ch R = 1 ,1351    ,404,404,404
BEGIN DESCRIPTION:
UNT028 IN BACR 3.0
END DESCRIPTION:
XS GIS Cut Line= 3
      2393200.43     13173266.89      2393067.24     13173004.11
      2392603.85     13172591.01
#Sta/Elev= 30
  4602.6   83.93  4619.6   82.82  4625.2   81.22  4636.2   81.08  4641.8   78.15
  4658.5   77.67  4664.1    76.2  4680.8   75.89  4692.3   74.11  4725.3   72.98
  4802.8   67.98  4892.9   63.15  4944.6    61.9  4998.4   55.94  5001.2   55.44
  5004.4   55.94  5029.8   59.38  5057.4   61.08  5128.5   62.91  5206.3   67.08
    5228   68.74  5242.2   70.99  5263.1   70.84  5312.4   75.73  5334.2    75.7
  5383.5   78.06  5397.7    79.9    5419   79.72  5489.7    83.8    5518   83.97
#Mann= 4 ,-1 , 0
  4602.6      .1       0  4802.8     .05       0  4998.4    .035       0
  5004.4     .05       0
Bank Sta=4998.4,5004.4
XS Rating Curve= 0 ,0
Exp/Cntr=0.3,0.1

Type RM Length L Ch R = 1 ,947     ,270,270,270
BEGIN DESCRIPTION:
UNT028 IN BACR 2.0
END DESCRIPTION:
XS GIS Cut Line= 3
       2393315.6     13173022.08      2393297.61     13172701.75
      2393070.85     13172194.24
#Sta/Elev= 30
  4636.4   70.52  4681.7   69.65  4692.3      71  4703.9   69.78  4741.8   66.04
  4781.9   63.56  4824.3   62.08    4842   62.16    4902   60.14  4932.1   58.35
  4962.7   57.68  4968.6   56.29  4984.5   55.66  4994.3    54.3  4997.1    53.8
  5000.3    54.3  5072.4   58.97    5105   59.74  5165.3   62.71  5188.5   64.85
  5234.9   66.53  5263.6   68.76  5269.3    70.3  5280.7   70.17    5324   72.68
  5338.7   74.96  5400.7   78.01  5422.6      80  5460.2   80.78  5513.1   84.31
#Mann= 6 ,-1 , 0
  4636.4      .1       0  4703.9     .05       0  4824.3     .07       0
  4994.3     .07       0  5000.3     .07       0  5280.7     .05       0
Bank Sta=4994.3,5000.3
XS Rating Curve= 0 ,0
Exp/Cntr=0.3,0.1

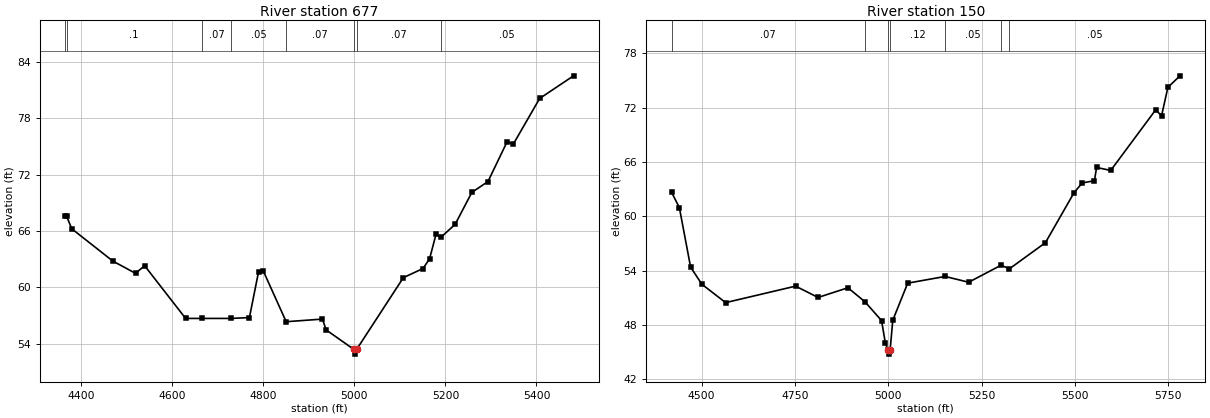
Type RM Length L Ch R = 1 ,677     ,527,527,527
BEGIN DESCRIPTION:
Mapping XS 3c0732d7
END DESCRIPTION:
XS GIS Cut Line= 3
      2393610.77     13173101.26      2393617.97     13172658.56
      2393196.83     13172133.04
#Sta/Elev= 30
  4365.2   67.55  4368.4   67.55  4379.6   66.23  4469.6    62.8  4519.6   61.49
  4539.6    62.3  4629.6   56.69  4664.8   56.69  4729.9   56.69  4769.7   56.78
  4789.7   61.64  4799.7   61.79  4850.4   56.34  4930.1   56.62  4938.1   55.47
  4999.1   53.39  5001.8   52.89  5005.1   53.39  5107.7   61.03  5150.9      62
  5165.3   63.04  5179.7   65.69  5189.8   65.31  5221.4    66.7  5258.2   70.11
  5293.4   71.25  5335.5   75.49  5349.4   75.26    5407    80.1  5481.4   82.51
#Mann= 8 ,-1 , 0
  4365.2     .05       0  4368.4      .1       0  4664.8     .07       0
  4729.9     .05       0  4850.4     .07       0  4999.1     .07       0
  5005.1     .07       0  5189.8     .05       0
Bank Sta=4999.1,5005.1
XS Rating Curve= 0 ,0
Exp/Cntr=0.3,0.1

Type RM Length L Ch R = 1 ,150     ,0,0,0
BEGIN DESCRIPTION:
UNT028 IN BACR 1.0
END DESCRIPTION:
XS GIS Cut Line= 4
      2393909.52     13172867.35      2393941.92     13172518.18
      2393949.12     13172219.42      2393298.09     13171931.67
#Sta/Elev= 30
  4419.8   62.65  4440.4   60.97  4470.5    54.4  4500.6   52.51  4564.3   50.48
  4751.7    52.3  4811.8   51.05  4891.8   52.12  4937.3   50.58  4981.9   48.49
  4991.9   46.04  4998.9   45.29  5001.6   44.79  5004.9   45.29  5011.9   48.53
  5051.9   52.63  5152.1   53.37  5215.1   52.73    5302   54.61  5324.2   54.21
  5420.7    57.1  5497.2   62.61  5519.1    63.7  5551.9   63.94  5557.7   65.41
  5595.6   65.08  5715.9   71.77  5731.7   71.12  5748.7   74.26  5781.1   75.53
#Mann= 7 ,-1 , 0
  4419.8     .07       0  4937.3     .12       0  4998.9     .07       0
  5004.9     .12       0  5152.1     .05       0    5302     .07       0
  5324.2     .05       0
Bank Sta=4998.9,5004.9
XS Rating Curve= 0 ,0
Exp/Cntr=0.3,0.1

Chan Stop Cuts=-1
Use User Specified Reach Order=0
Composite Channel Slope=5