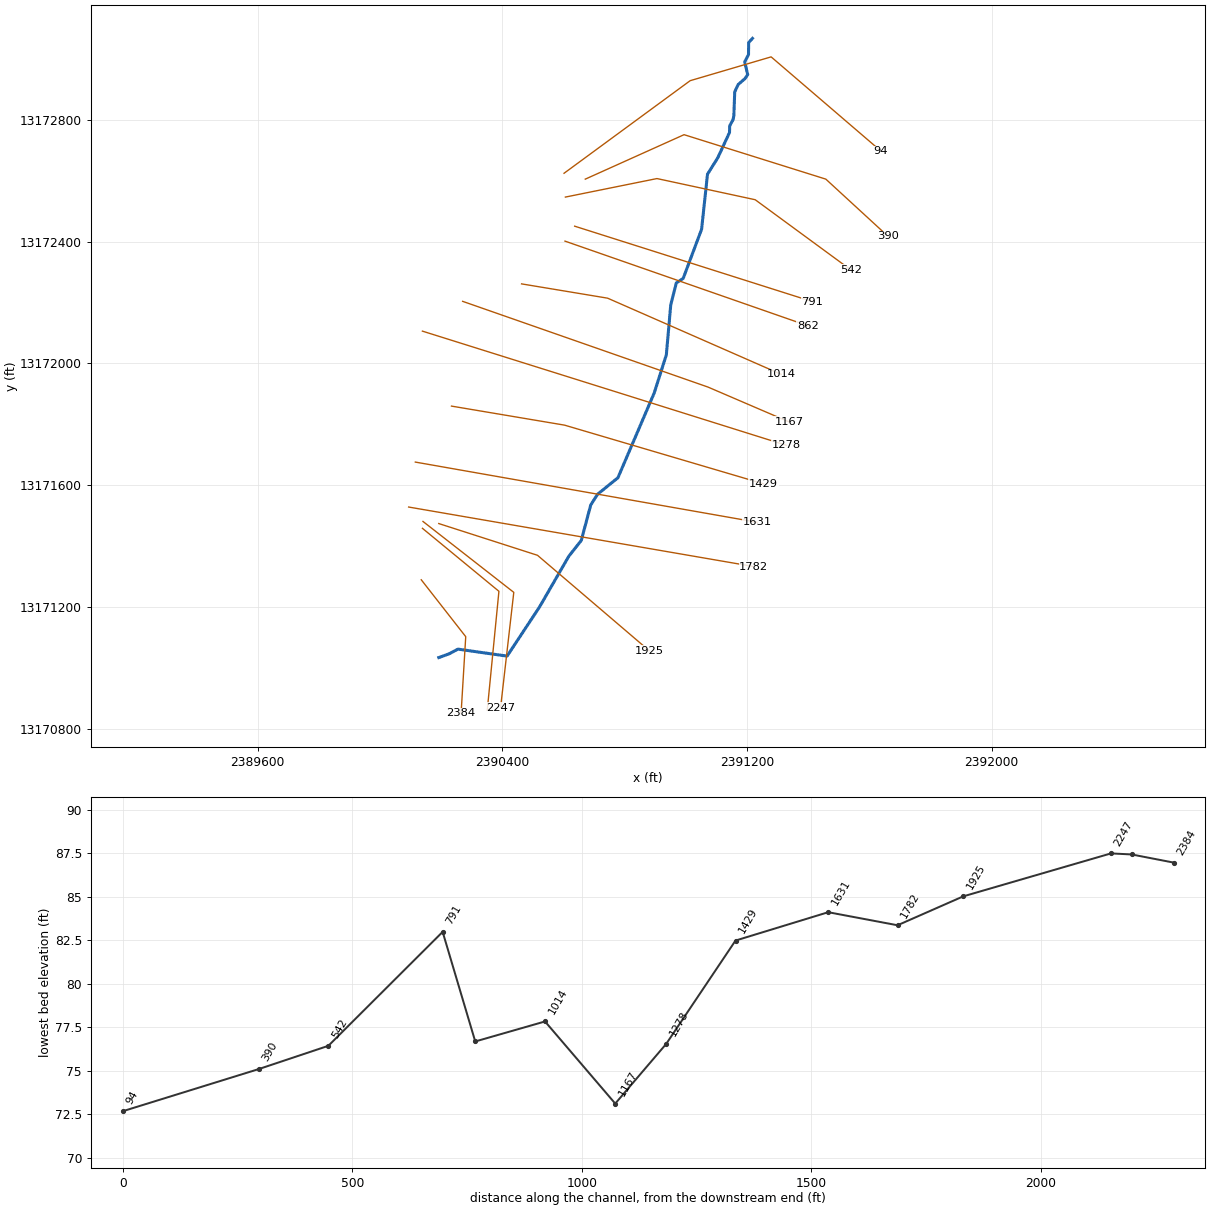
--- UNT029 IN BACR.prj (project) ---

Proj Title=UNT029 IN BACR Base Level Engineering
Current Plan=p01
Default Exp/Contr=0.3,0.1
English Units
Geom File=g01
Flow File=f01
Plan File=p01
BEGIN DESCRIPTION:
UNT029 IN BACR
END DESCRIPTION:

--- UNT029 IN BACR.p01 (plan) ---

Plan Title=Multiple Run
Short Identifier=Multiple
Geom File=g01
Flow File=f01
Subcritical Flow
K Sum by GR= 0
Std Step Tol= 0.01
Critical Tol= 0.01
Num of Std Step Trials= 20
Max Error Tol= 0.3
Flow Tol Ratio= 0.001
Split Flow NTrial= 30
Split Flow Tol= 0.02
Split Flow Ratio= 0.02
Log Output Level= 0
Friction Slope Method= 1
Unsteady Friction Slope Method= 2
Unsteady Bridges Friction Slope Method= 1
Parabolic Critical Depth
Global Vel Dist=  1 , 1 , 1
Global Log Level= 0
CheckData=True
Encroach Param= -1, 0, 0, 0
BEGIN DESCRIPTION:
Multiple Run
END DESCRIPTION:

--- UNT029 IN BACR.f01 (steady flow) ---

Flow Title=Multiple
Number of Profiles=7
Profile Names=10-year,25-year,50-year,1pct_min,100-year,1pct_plu,500-year
River Rch & RM= UNT029 IN BACR,Reach-1,2384
     198     256     300     258     349     471     474
Boundary for River Rch & Prof#=UNT029 IN BACR,Reach-1,1
Up Type=0
Dn Type=3
Dn Slope=0.005
Boundary for River Rch & Prof#=UNT029 IN BACR,Reach-1,2
Up Type=0
Dn Type=3
Dn Slope=0.005
Boundary for River Rch & Prof#=UNT029 IN BACR,Reach-1,3
Up Type=0
Dn Type=3
Dn Slope=0.005
Boundary for River Rch & Prof#=UNT029 IN BACR,Reach-1,4
Up Type=0
Dn Type=3
Dn Slope=0.005
Boundary for River Rch & Prof#=UNT029 IN BACR,Reach-1,5
Up Type=0
Dn Type=3
Dn Slope=0.005
Boundary for River Rch & Prof#=UNT029 IN BACR,Reach-1,6
Up Type=0
Dn Type=3
Dn Slope=0.005
Boundary for River Rch & Prof#=UNT029 IN BACR,Reach-1,7
Up Type=0
Dn Type=3
Dn Slope=0.005

--- UNT029 IN BACR.g01 (geometry) ---

Geom Title=Existing Conditions

River Reach=UNT029 IN BACR,Reach-1
Reach XY= 30
      2390192.09     13171034.90      2390226.13     13171047.33
      2390254.60     13171062.61      2390415.28     13171039.71
      2390521.11     13171200.54      2390616.89     13171367.04
      2390657.88     13171419.32      2390688.80     13171535.59
      2390711.24     13171570.95      2390777.61     13171624.77
      2390896.48     13171903.38      2390936.04     13172028.37
      2390950.45     13172192.30      2390968.55     13172264.01
      2390991.27     13172279.32      2391051.27     13172440.21
      2391070.61     13172621.06      2391103.67     13172673.84
      2391142.60     13172757.89      2391143.12     13172779.92
      2391153.80     13172799.07      2391156.73     13172812.23
      2391159.61     13172891.18      2391170.85     13172915.13
      2391193.42     13172934.97      2391202.11     13172948.10
      2391192.02     13172989.48      2391204.67     13173013.12
      2391205.20     13173053.11      2391217.72     13173066.85

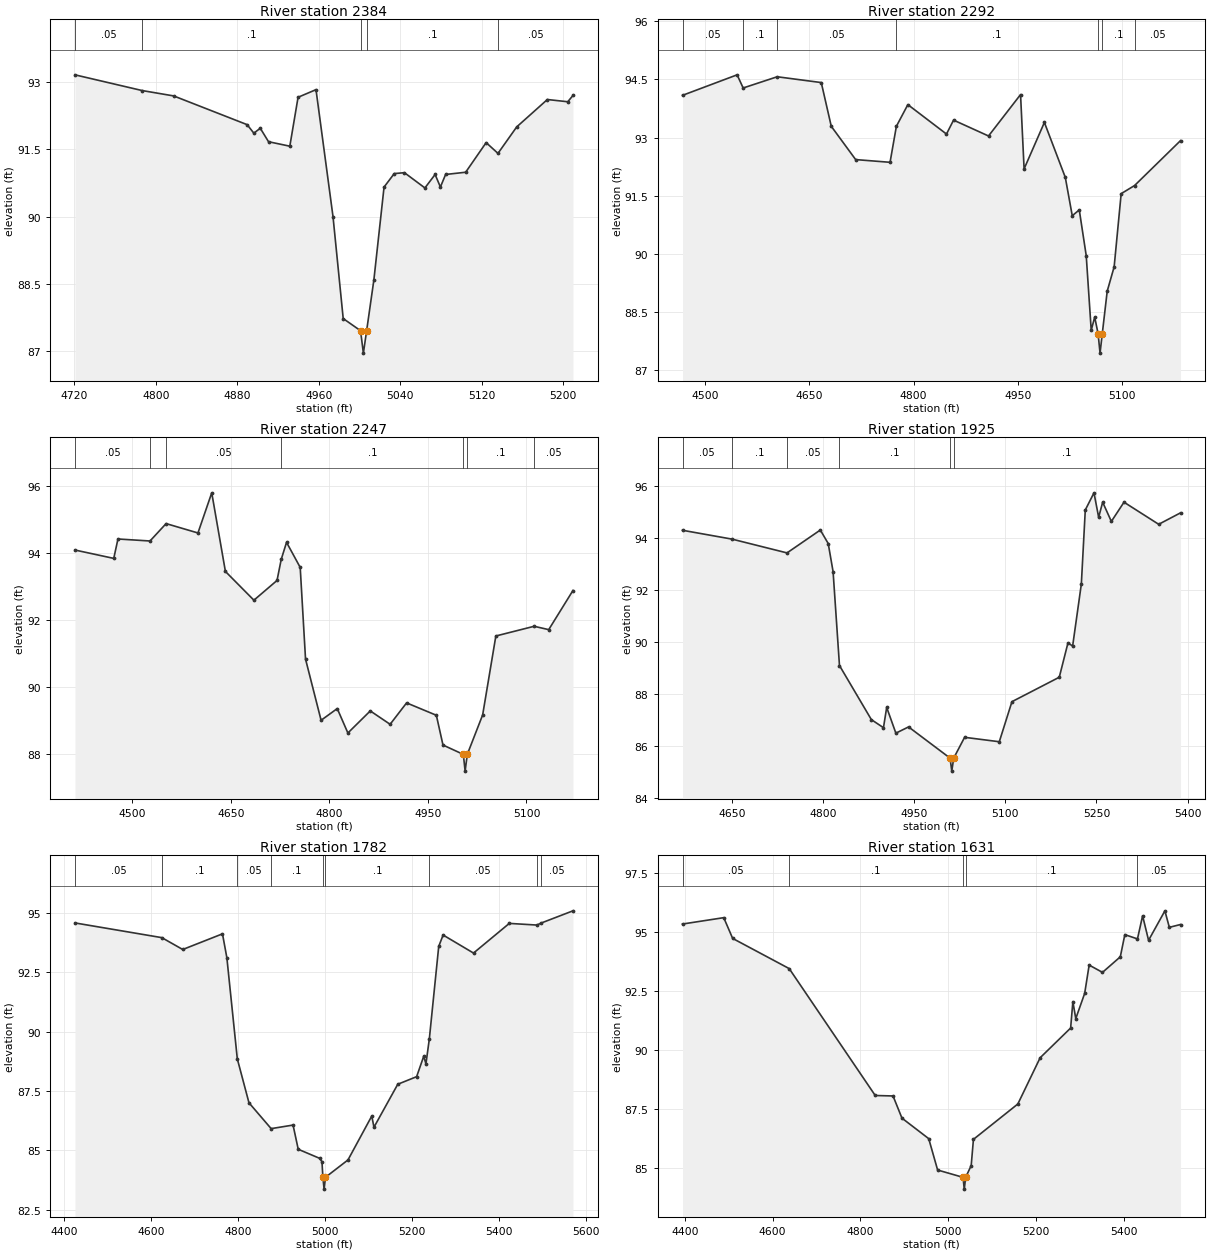
Type RM Length L Ch R = 1,2384,92,92,92
BEGIN DESCRIPTION:
UNT029 IN BACR 4.0
END DESCRIPTION:
XS GIS Cut Line= 3
      2390134.67     13171290.15      2390280.09     13171103.48
      2390264.90     13170851.77
#Sta/Elev= 30
  4720.7   93.16  4786.6   92.81  4817.6   92.69  4889.7   92.05  4896.3   91.86
  4902.6   91.97  4910.7   91.67  4931.6   91.57  4939.7   92.66  4957.3   92.83
  4974.0   90.00  4984.0   87.73  5001.0   87.46  5003.8   86.96  5007.0   87.46
  5014.1   88.59  5024.1   90.66  5034.1   90.96  5044.1   90.98  5064.2   90.64
  5074.2   90.94  5079.4   90.66  5084.5   90.94  5104.2   90.99  5124.3   91.65
  5135.9   91.41  5154.3   92.00  5184.4   92.61  5204.4   92.56  5209.5   92.70
#Mann=5,-1,0
  4720.7    0.05       0  4786.6     0.1       0  5001.0    0.07       0
  5007.0     0.1       0  5135.9    0.05       0
Bank Sta=5001,5007
Exp/Cntr=0.3,0.1

Type RM Length L Ch R = 1,2292,45,45,45
BEGIN DESCRIPTION:
Mapping XS 4fdfeab4
END DESCRIPTION:
XS GIS Cut Line= 3
      2390138.60     13171458.95      2390388.60     13171252.36
      2390350.41     13170861.84
#Sta/Elev= 30
  4467.5   94.09  4546.1   94.62  4554.8   94.28  4603.8   94.57  4667.2   94.42
  4681.6   93.29  4716.7   92.43  4766.2   92.36  4775.3   93.29  4791.8   93.85
  4847.4   93.09  4857.6   93.45  4907.9   93.04  4954.0   94.11  4959.1   92.19
  4988.3   93.39  5018.4   91.97  5028.4   90.98  5038.5   91.13  5048.5   89.95
  5055.7   88.02  5060.7   88.36  5065.6   87.93  5068.4   87.43  5071.6   87.93
  5078.7   89.03  5088.7   89.66  5098.8   91.55  5118.1   91.76  5184.2   92.92
#Mann=7,-1,0
  4467.5    0.05       0  4554.8     0.1       0  4603.8    0.05       0
  4775.3     0.1       0  5065.6    0.07       0  5071.6     0.1       0
  5118.1    0.05       0
Bank Sta=5065.6,5071.6
Exp/Cntr=0.3,0.1

Type RM Length L Ch R = 1,2247,322,322,322
BEGIN DESCRIPTION:
Mapping XS 5b24db12
END DESCRIPTION:
XS GIS Cut Line= 3
      2390140.31     13171481.54      2390437.21     13171248.88
      2390393.99     13170870.24
#Sta/Elev= 30
  4412.5   94.10  4471.6   93.85  4478.0   94.43  4526.8   94.37  4551.3   94.89
  4599.8   94.61  4620.8   95.81  4641.6   93.46  4685.0   92.60  4720.2   93.19
  4726.6   93.82  4734.7   94.33  4755.5   93.58  4763.6   90.84  4787.3   89.01
  4811.9   89.36  4828.1   88.63  4862.2   89.29  4892.4   88.89  4917.5   89.53
  4962.8   89.16  4972.9   88.27  5003.9   87.99  5006.6   87.49  5009.9   87.99
  5033.3   89.17  5053.4   91.53  5111.7   91.82  5133.9   91.72  5170.8   92.89
#Mann=7,-1,0
  4412.5    0.05       0  4526.8     0.1       0  4551.3    0.05       0
  4726.6     0.1       0  5003.9    0.07       0  5009.9     0.1       0
  5111.7    0.05       0
Bank Sta=5003.9,5009.9
Exp/Cntr=0.3,0.1

Type RM Length L Ch R = 1,1925,143,143,143
BEGIN DESCRIPTION:
Mapping XS 76836b05
END DESCRIPTION:
XS GIS Cut Line= 3
      2390191.89     13171474.64      2390514.79     13171370.48
      2390879.39     13171057.96
#Sta/Elev= 30
  4568.9   94.28  4650.4   93.94  4740.9   93.41  4795.7   94.29  4808.7   93.77
  4816.7   92.69  4827.2   89.08  4879.7   87.00  4899.6   86.69  4904.9   87.47
  4920.0   86.48  4940.9   86.72  5009.2   85.52  5012.0   85.02  5015.2   85.52
  5033.1   86.32  5090.2   86.15  5111.0   87.69  5188.9   88.63  5203.2   89.95
  5210.9   89.83  5225.2   92.21  5231.7   95.06  5246.0   95.72  5253.7   94.78
  5260.3   95.36  5274.6   94.62  5295.4   95.36  5352.5   94.51  5388.4   94.95
#Mann=6,-1,0
  4568.9    0.05       0  4650.4     0.1       0  4740.9    0.05       0
  4827.2     0.1       0  5009.2    0.07       0  5015.2     0.1       0
Bank Sta=5009.2,5015.2
Exp/Cntr=0.3,0.1

Type RM Length L Ch R = 1,1782,151,151,151
BEGIN DESCRIPTION:
Mapping XS 5d3a5a9f
END DESCRIPTION:
XS GIS Cut Line= 2
      2390093.42     13171528.84      2391221.95     13171333.52
#Sta/Elev= 30
  4424.1   94.58  4623.9   93.96  4672.0   93.46  4763.4   94.12  4773.5   93.11
  4797.5   88.85  4824.3   87.00  4875.3   85.91  4925.7   86.06  4937.6   85.04
  4986.6   84.66  4992.2   84.52  4994.3   83.86  4997.1   83.36  5000.3   83.86
  5052.0   84.59  5106.7   86.44  5111.8   85.97  5166.5   87.78  5209.9   88.10
  5226.2   88.96  5231.3   88.64  5239.1   89.69  5260.7   93.59  5270.8   94.07
  5340.7   93.31  5423.0   94.56  5486.7   94.49  5495.6   94.57  5569.4   95.09
#Mann=9,-1,0
  4424.1    0.05       0  4623.9     0.1       0  4797.5    0.05       0
  4875.3     0.1       0  4994.3    0.07       0  5000.3     0.1       0
  5239.1    0.05       0  5486.7     0.1       0  5495.6    0.05       0
Bank Sta=4994.3,5000.3
Exp/Cntr=0.3,0.1

Type RM Length L Ch R = 1,1631,202,202,202
BEGIN DESCRIPTION:
UNT029 IN BACR 3.0
END DESCRIPTION:
XS GIS Cut Line= 2
      2390115.20     13171676.39      2391232.79     13171478.92
#Sta/Elev= 30
  4394.6   95.35  4488.6   95.62  4508.9   94.74  4637.8   93.46  4833.8   88.08
  4874.4   88.06  4894.7   87.12  4955.7   86.25  4976.0   84.92  5033.9   84.61
  5036.7   84.11  5039.9   84.61  5052.5   85.11  5057.6   86.22  5158.8   87.72
  5209.6   89.68  5279.1   90.94  5284.2   92.06  5290.8   91.34  5311.1   92.41
  5321.3   93.61  5351.7   93.30  5392.3   93.96  5402.6   94.90  5431.4   94.72
  5443.1   95.70  5456.7   94.66  5493.9   95.91  5504.0   95.21  5529.5   95.33
#Mann=5,-1,0
  4394.6    0.05       0  4637.8     0.1       0  5033.9    0.07       0
  5039.9     0.1       0  5431.4    0.05       0
Bank Sta=5033.9,5039.9
Exp/Cntr=0.3,0.1

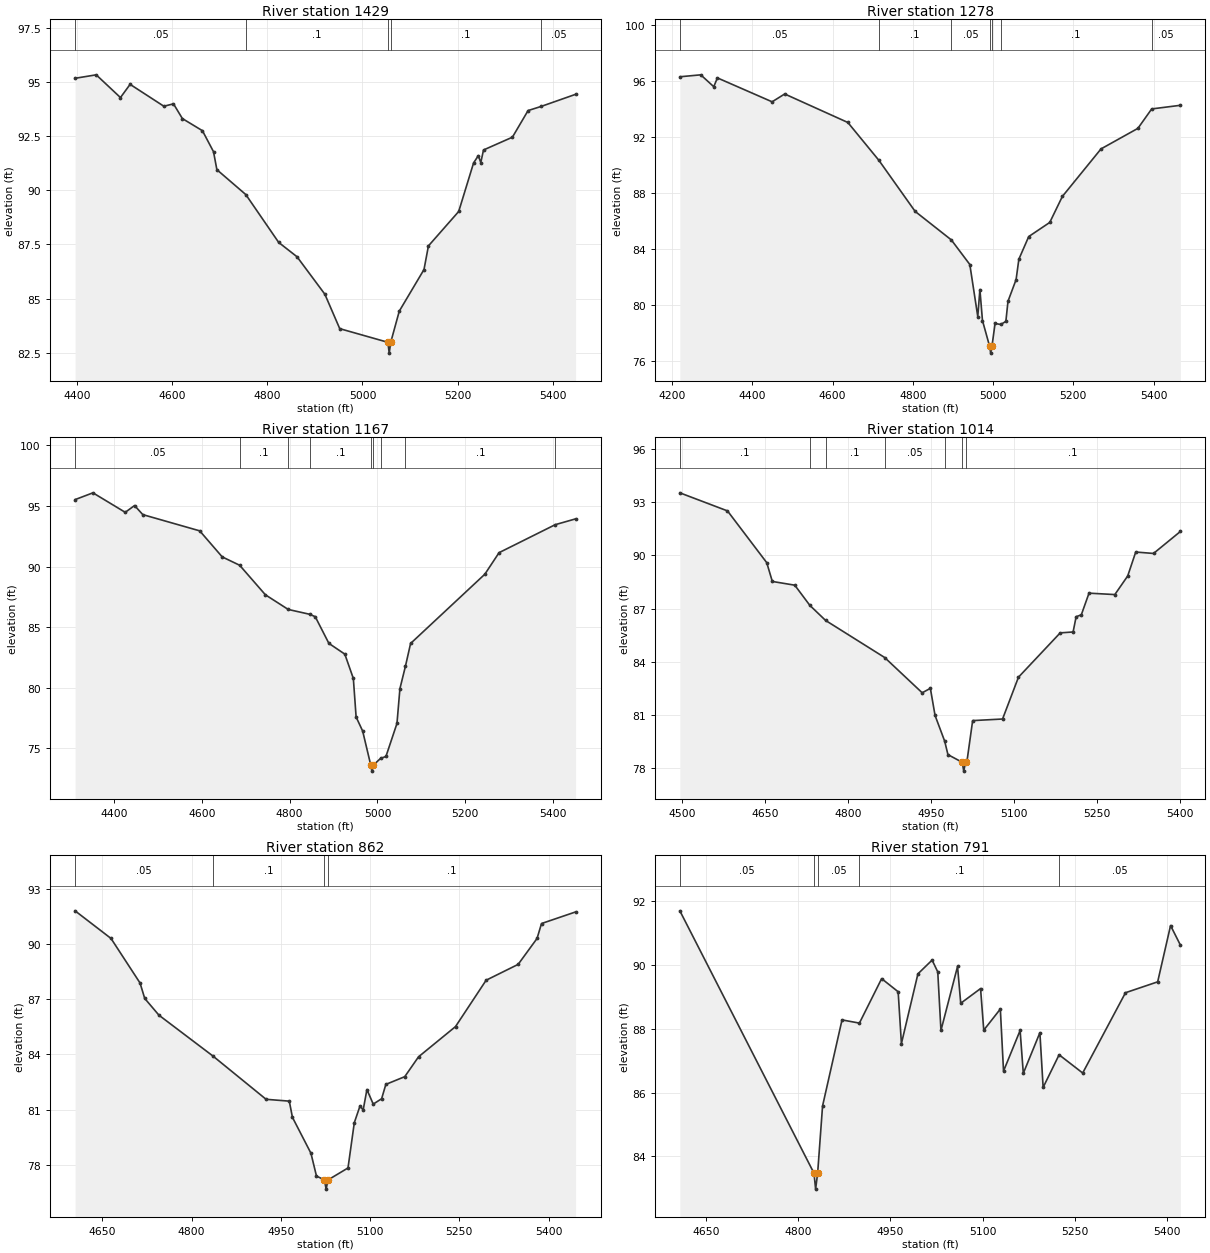
Type RM Length L Ch R = 1,1429,151,151,151
BEGIN DESCRIPTION:
Mapping XS 3fd51b9d
END DESCRIPTION:
XS GIS Cut Line= 3
      2390233.51     13171860.07      2390603.33     13171797.56
      2391253.58     13171605.09
#Sta/Elev= 30
  4395.3   95.17  4439.8   95.33  4490.8   94.28  4511.1   94.89  4582.1   93.88
  4602.4   93.99  4621.1   93.31  4663.3   92.75  4686.6   91.78  4693.7   90.95
  4754.6   89.80  4823.8   87.59  4862.3   86.93  4920.9   85.20  4952.2   83.61
  5053.5   82.98  5056.3   82.48  5059.5   82.98  5077.5   84.42  5129.5   86.34
  5138.8   87.43  5202.5   89.02  5233.8   91.26  5243.8   91.60  5249.0   91.28
  5254.7   91.86  5315.5   92.45  5348.5   93.68  5375.9   93.87  5448.5   94.43
#Mann=5,-1,0
  4395.3    0.05       0  4754.6     0.1       0  5053.5    0.07       0
  5059.5     0.1       0  5375.9    0.05       0
Bank Sta=5053.5,5059.5
Exp/Cntr=0.3,0.1

Type RM Length L Ch R = 1,1278,111,111,111
BEGIN DESCRIPTION:
Mapping XS 3afafcb2
END DESCRIPTION:
XS GIS Cut Line= 2
      2390138.48     13172106.06      2391328.20     13171731.46
#Sta/Elev= 30
  4219.5   96.31  4271.6   96.45  4304.0   95.60  4313.1   96.23  4449.4   94.52
  4480.8   95.08  4638.2   93.04  4715.6   90.33  4805.8   86.68  4896.0   84.64
  4942.1   82.88  4961.9   79.16  4967.2   81.09  4973.6   78.87  4991.3   77.04
  4994.1   76.54  4997.3   77.04  5005.0   78.66  5019.1   78.59  5031.9   78.81
  5037.2   80.25  5057.4   81.80  5064.3   83.26  5088.9   84.88  5141.3   85.89
  5172.7   87.75  5269.0   91.15  5360.9   92.62  5395.3   94.01  5466.8   94.27
#Mann=7,-1,0
  4219.5    0.05       0  4715.6     0.1       0  4896.0    0.05       0
  4991.3   0.035       0  4997.3    0.05       0  5019.1     0.1       0
  5395.3    0.05       0
Bank Sta=4991.3,4997.3
Exp/Cntr=0.3,0.1

Type RM Length L Ch R = 1,1167,153,153,153
BEGIN DESCRIPTION:
Mapping XS 681558e3
END DESCRIPTION:
XS GIS Cut Line= 3
      2390269.96     13172203.83      2391072.08     13171922.56
      2391337.72     13171807.98
#Sta/Elev= 30
  4311.7   95.53  4352.4   96.09  4425.9   94.48  4447.1   95.04  4465.9   94.29
  4595.4   92.95  4646.6   90.80  4686.3   90.11  4744.9   87.67  4796.9   86.46
  4845.9   86.06  4858.4   85.86  4889.4   83.66  4925.7   82.77  4945.1   80.76
  4951.4   77.58  4966.3   76.42  4984.7   73.61  4987.4   73.11  4990.7   73.61
  5007.0   74.16  5019.3   74.32  5044.4   77.05  5051.1   79.92  5063.6   81.76
  5075.4   83.65  5244.4   89.37  5276.8   91.15  5404.6   93.46  5451.0   93.94
#Mann=9,-1,0
  4311.7    0.05       0  4686.3     0.1       0  4796.9    0.05       0
  4845.9     0.1       0  4984.7    0.07       0  4990.7     0.1       0
  5007.0    0.05       0  5063.6     0.1       0  5404.6    0.05       0
Bank Sta=4984.7,4990.7
Exp/Cntr=0.3,0.1

Type RM Length L Ch R = 1,1014,152,152,152
BEGIN DESCRIPTION:
Mapping XS ced6e2e9
END DESCRIPTION:
XS GIS Cut Line= 3
      2390462.68     13172261.11      2390743.96     13172214.23
      2391311.69     13171964.22
#Sta/Elev= 30
  4495.6   93.53  4581.8   92.51  4652.8   89.59  4662.9   88.53  4703.5   88.32
  4730.8   87.18  4759.3   86.33  4866.1   84.24  4934.0   82.25  4948.8   82.50
  4957.3   80.97  4974.7   79.52  4980.6   78.76  5006.4   78.33  5009.2   77.83
  5012.4   78.33  5014.9   78.36  5025.3   80.68  5079.4   80.77  5108.2   83.13
  5183.7   85.63  5207.0   85.68  5212.5   86.54  5221.9   86.65  5235.8   87.87
  5282.5   87.79  5305.8   88.84  5320.3   90.19  5352.5   90.11  5401.1   91.35
#Mann=7,-1,0
  4495.6     0.1       0  4730.8    0.05       0  4759.3     0.1       0
  4866.1    0.05       0  4974.7     0.1       0  5006.4    0.07       0
  5012.4     0.1       0
Bank Sta=5006.4,5012.4
Exp/Cntr=0.3,0.1

Type RM Length L Ch R = 1,862,71,71,71
BEGIN DESCRIPTION:
UNT029 IN BACR 2.0
END DESCRIPTION:
XS GIS Cut Line= 2
      2390604.63     13172401.40      2391398.86     13172123.63
#Sta/Elev= 30
  4604.0   91.80  4664.4   90.30  4713.2   87.88  4721.1   87.04  4745.0   86.13
  4835.4   83.92  4925.1   81.56  4964.1   81.46  4969.4   80.58  5000.5   78.63
  5009.8   77.39  5023.2   77.18  5026.0   76.68  5029.2   77.18  5062.8   77.83
  5073.4   80.29  5083.0   81.20  5088.3   80.98  5094.6   82.09  5105.2   81.30
  5119.3   81.59  5126.4   82.37  5158.2   82.79  5181.4   83.87  5243.5   85.51
  5295.0   88.03  5348.8   88.89  5380.6   90.30  5388.1   91.11  5445.4   91.74
#Mann=4,-1,0
  4604.0    0.05       0  4835.4     0.1       0  5023.2    0.07       0
  5029.2     0.1       0
Bank Sta=5023.2,5029.2
Exp/Cntr=0.3,0.1

Type RM Length L Ch R = 1,791,249,249,249
BEGIN DESCRIPTION:
Mapping XS b719ba54
END DESCRIPTION:
XS GIS Cut Line= 2
      2390636.26     13172450.46      2391412.93     13172203.14
#Sta/Elev= 30
  4607.1   91.68  4825.5   83.48  4828.2   82.98  4831.5   83.48  4839.5   85.58
  4871.2   88.27  4899.5   88.17  4935.7   89.56  4962.6   89.15  4967.9   87.53
  4994.8   89.71  5017.9   90.14  5027.1   89.77  5032.3   87.94  5059.3   89.94
  5064.5   88.79  5096.8   89.25  5102.0   87.95  5129.0   88.61  5134.2   86.67
  5161.2   87.94  5166.4   86.60  5193.4   87.87  5198.7   86.16  5224.7   87.18
  5263.1   86.61  5332.8   89.12  5385.2   89.46  5406.2   91.22  5422.2   90.61
#Mann=5,-1,0
  4607.1    0.05       0  4825.5    0.07       0  4831.5    0.05       0
  4899.5     0.1       0  5224.7    0.05       0
Bank Sta=4825.5,4831.5
Exp/Cntr=0.3,0.1

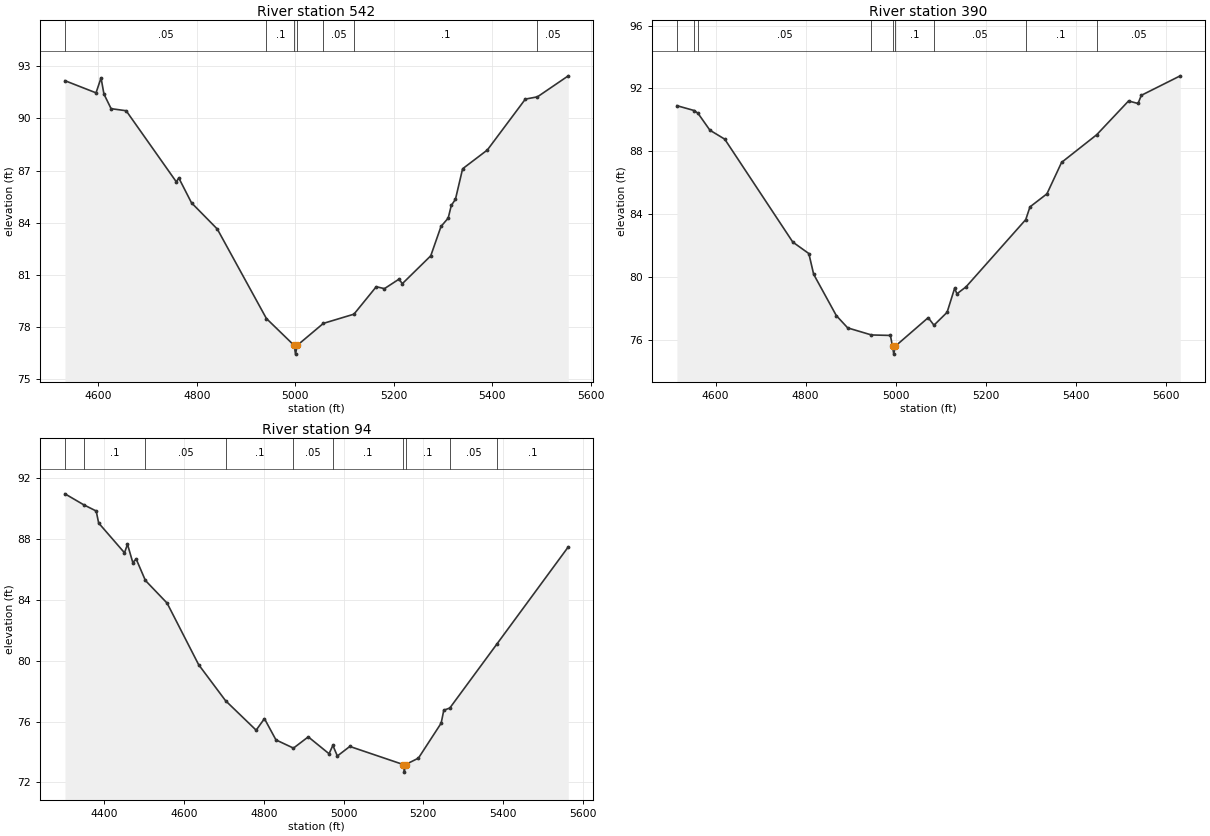
Type RM Length L Ch R = 1,542,152,152,152
BEGIN DESCRIPTION:
Mapping XS 6e0813db
END DESCRIPTION:
XS GIS Cut Line= 4
      2390605.89     13172545.94      2390905.38     13172606.70
      2391226.56     13172537.26      2391539.03     13172307.25
#Sta/Elev= 30
  4532.3   92.17  4595.4   91.47  4605.6   92.33  4611.5   91.40  4626.0   90.56
  4656.6   90.44  4758.4   86.35  4763.5   86.57  4789.3   85.14  4841.7   83.63
  4941.4   78.48  4997.8   76.93  5000.6   76.43  5003.8   76.93  5057.1   78.20
  5119.2   78.73  5164.5   80.31  5181.1   80.20  5210.4   80.74  5217.6   80.49
  5275.2   82.09  5296.0   83.78  5310.6   84.26  5316.9   84.99  5325.3   85.34
  5339.9   87.10  5390.1   88.18  5467.3   91.11  5491.8   91.24  5554.5   92.45
#Mann=7,-1,0
  4532.3    0.05       0  4941.4     0.1       0  4997.8    0.07       0
  5003.8     0.1       0  5057.1    0.05       0  5119.2     0.1       0
  5491.8    0.05       0
Bank Sta=4997.8,5003.8
Exp/Cntr=0.3,0.1

Type RM Length L Ch R = 1,390,296,296,296
BEGIN DESCRIPTION:
Mapping XS 1dc20ed4
END DESCRIPTION:
XS GIS Cut Line= 4
      2390671.00     13172604.84      2390993.96     13172750.69
      2391457.50     13172604.85      2391660.59     13172417.38
#Sta/Elev= 30
  4514.4   90.90  4552.9   90.59  4561.3   90.41  4587.6   89.34  4620.5   88.77
  4771.5   82.22  4807.1   81.49  4817.8   80.17  4868.1   77.54  4893.3   76.76
  4946.0   76.31  4988.0   76.28  4992.7   75.59  4995.5   75.09  4998.7   75.59
  5071.9   77.41  5084.7   76.93  5113.8   77.75  5130.5   79.28  5135.7   78.93
  5155.8   79.37  5288.3   83.65  5297.7   84.46  5335.3   85.29  5367.8   87.29
  5445.7   89.05  5516.4   91.20  5537.4   91.04  5544.8   91.56  5631.1   92.80
#Mann=9,-1,0
  4514.4    0.05       0  4552.9     0.1       0  4561.3    0.05       0
  4946.0     0.1       0  4992.7    0.07       0  4998.7     0.1       0
  5084.7    0.05       0  5288.3     0.1       0  5445.7    0.05       0
Bank Sta=4992.7,4998.7
Exp/Cntr=0.3,0.1

Type RM Length L Ch R = 1,94,0,0,0
BEGIN DESCRIPTION:
UNT029 IN BACR 1.0
END DESCRIPTION:
XS GIS Cut Line= 4
      2390601.52     13172624.04      2391013.89     13172927.88
      2391278.65     13173006.01      2391637.73     13172696.85
#Sta/Elev= 30
  4301.5   90.98  4348.5   90.26  4379.8   89.85  4386.0   89.06  4450.8   87.10
  4458.3   87.66  4471.6   86.46  4480.1   86.69  4503.2   85.28  4557.6   83.79
  4636.7   79.74  4704.2   77.37  4780.9   75.43  4801.7   76.19  4830.6   74.79
  4874.5   74.25  4911.6   74.99  4963.7   73.88  4973.3   74.43  4984.5   73.73
  5015.8   74.36  5149.7   73.17  5152.4   72.67  5155.7   73.17  5187.8   73.59
  5244.8   75.89  5251.4   76.74  5266.6   76.89  5385.2   81.12  5563.6   87.49
#Mann=10,-1,0
  4301.5    0.05       0  4348.5     0.1       0  4503.2    0.05       0
  4704.2     0.1       0  4874.5    0.05       0  4973.3     0.1       0
  5149.7    0.07       0  5155.7     0.1       0  5266.6    0.05       0
  5385.2     0.1       0
Bank Sta=5149.7,5155.7
Exp/Cntr=0.3,0.1

Chan Stop Cuts=-1