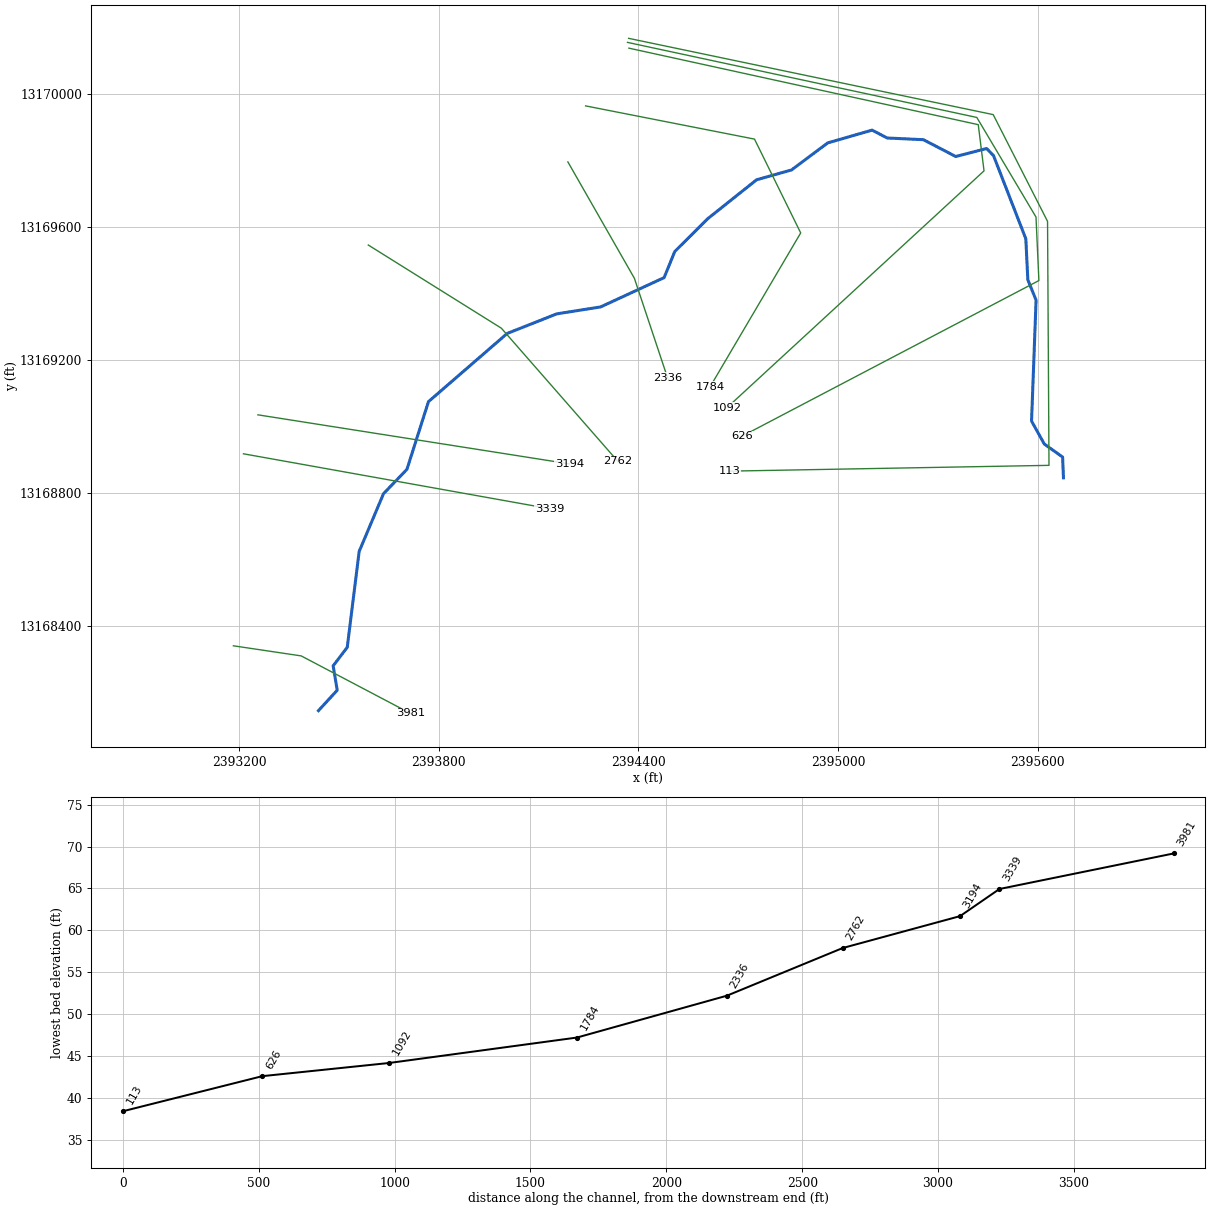
--- UNT030 IN BACR.prj (project) ---

Proj Title=UNT030 IN BACR Base Level Engineering
Current Plan=p01
Default Exp/Contr=0.3,0.1
English Units
Geom File=g01
Flow File=f01
Plan File=p01
Y Axis Title=Elevation
X Axis Title(PF)=Main Channel Distance
X Axis Title(XS)=Station
BEGIN DESCRIPTION:
UNT030 IN BACR
END DESCRIPTION:
DSS Export Rating Curves= 0
DSS Export Rating Curve Sorted= 0
DSS Export Volume Flow Curves= 0
DXF OffsetX= 0
DXF OffsetY= 0
DXF ScaleX= 1
DXF ScaleY= 10

--- UNT030 IN BACR.p01 (plan) ---

Plan Title=Multiple Run
Short Identifier=Multiple
Geom File=g01
Flow File=f01
Subcritical Flow
K Sum by GR= 0
Std Step Tol= 0.01
Critical Tol= 0.01
Num of Std Step Trials= 20
Max Error Tol= 0.3
Flow Tol Ratio= 0.001
Split Flow NTrial= 30
Split Flow Tol= 0.02
Split Flow Ratio= 0.02
Log Output Level= 0
Friction Slope Method= 1
Unsteady Friction Slope Method= 2
Unsteady Bridges Friction Slope Method= 1
Parabolic Critical Depth
Global Vel Dist=  1 , 1 , 1
Global Log Level= 0
CheckData=True
Encroach Param= -1, 0, 0, 0
BEGIN DESCRIPTION:
Multiple Run
END DESCRIPTION:

--- UNT030 IN BACR.f01 (steady flow) ---

Flow Title=Multiple
Program Version=4.10
Number of Profiles= 7
Profile Names=10-year,25-year,50-year,1pct_min,100-year,1pct_plu,500-year
River Rch & RM=UNT030 IN BACR,Reach-1         ,3981
     205     266     313     270     364     493     499
River Rch & RM=UNT030 IN BACR,Reach-1         ,3194
     284     379     454     398     538     728     765
River Rch & RM=UNT030 IN BACR,Reach-1         ,113
    2301    3317    4187    3844    5199    7030    8073
Boundary for River Rch & Prof#=UNT030 IN BACR,Reach-1         , 1
Up Type= 0
Dn Type= 3
Dn Slope=0.008
Boundary for River Rch & Prof#=UNT030 IN BACR,Reach-1         , 2
Up Type= 0
Dn Type= 3
Dn Slope=0.008
Boundary for River Rch & Prof#=UNT030 IN BACR,Reach-1         , 3
Up Type= 0
Dn Type= 3
Dn Slope=0.008
Boundary for River Rch & Prof#=UNT030 IN BACR,Reach-1         , 4
Up Type= 0
Dn Type= 3
Dn Slope=0.008
Boundary for River Rch & Prof#=UNT030 IN BACR,Reach-1         , 5
Up Type= 0
Dn Type= 3
Dn Slope=0.008
Boundary for River Rch & Prof#=UNT030 IN BACR,Reach-1         , 6
Up Type= 0
Dn Type= 3
Dn Slope=0.008
Boundary for River Rch & Prof#=UNT030 IN BACR,Reach-1         , 7
Up Type= 0
Dn Type= 3
Dn Slope=0.008
DSS Import GetInterval= 0
DSS Import GetPeak= 0
DSS Import FillOption= 0

--- UNT030 IN BACR.g01 (geometry) ---

Geom Title=Existing Conditions
Program Version=4.10

River Reach=UNT030 IN BACR  ,Reach-1
Reach XY= 30
      2393437.72     13168146.85      2393494.22     13168208.32
      2393482.12     13168281.69       2393524.4     13168337.57
      2393560.24      13168625.7      2393633.46     13168799.33
      2393703.82      13168872.4      2393768.55     13169075.94
      2394005.17     13169280.97      2394154.18      13169339.9
      2394286.14     13169360.75      2394477.07     13169448.85
      2394509.01     13169527.11      2394607.51     13169625.49
      2394755.02     13169743.02      2394860.17     13169772.64
      2394968.93     13169853.93       2395102.5     13169892.39
      2395147.73      13169868.7      2395256.58     13169863.66
      2395353.92     13169813.04      2395446.69     13169837.09
      2395467.46     13169815.74      2395564.59     13169565.58
      2395570.64     13169442.37      2395595.45     13169381.13
      2395581.81     13169017.53       2395620.3     13168948.43
      2395675.21     13168909.49      2395677.72     13168846.86

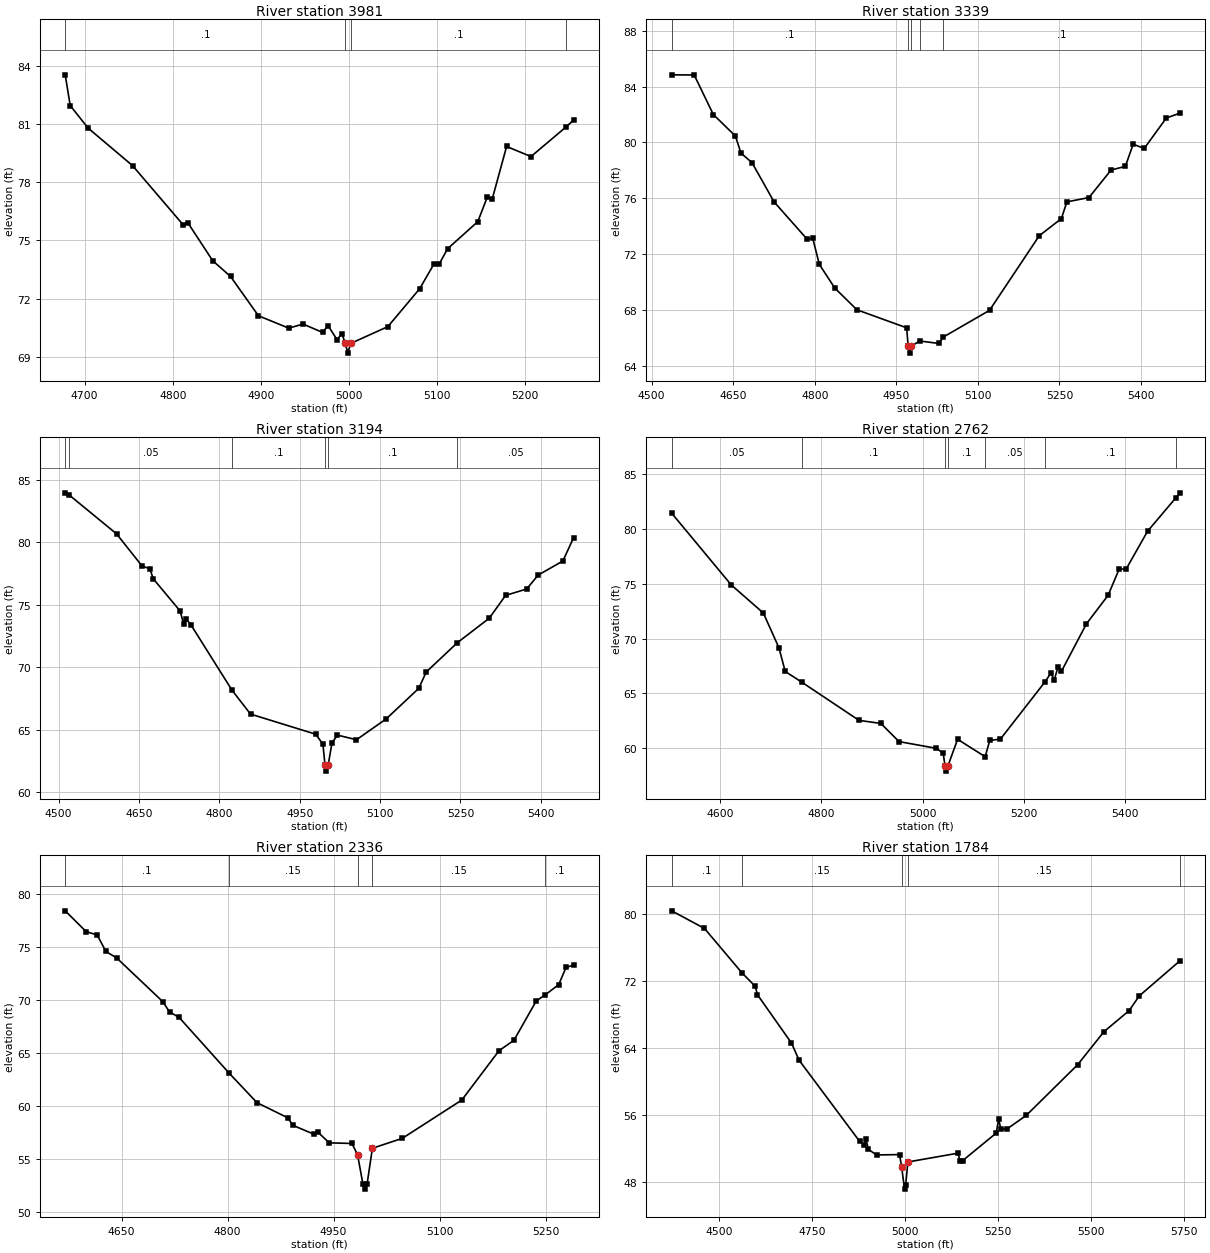
Type RM Length L Ch R = 1 ,3981    ,642,642,642
BEGIN DESCRIPTION:
UNT030 IN BACR 5.0
END DESCRIPTION:
XS GIS Cut Line= 3
      2393182.05     13168341.94        2393386.     13168311.56
       2393714.3     13168138.77
#Sta/Elev= 30
  4677.9   83.55  4683.6   81.96  4703.9    80.8  4754.4   78.86  4812.1   75.79
  4817.2   75.91  4845.4   73.95  4865.6   73.14  4897.3   71.11  4931.7   70.47
    4948   70.68  4970.1   70.25  4976.4    70.6  4986.5   69.88  4992.1   70.18
    4996   69.68  4998.8   69.18    5002   69.68  5044.3   70.55  5080.3    72.5
  5096.6   73.78  5102.3   73.76  5112.1   74.57  5146.4   75.97  5157.1   77.23
  5162.8   77.14  5179.1   79.85  5206.8   79.33  5246.9   80.87  5255.1   81.21
#Mann= 4 ,-1 , 0
  4677.9      .1       0    4996     .07       0    5002      .1       0
  5246.9     .05       0
Bank Sta=4996,5002
XS Rating Curve= 0 ,0
Exp/Cntr=0.3,0.1

Type RM Length L Ch R = 1 ,3339    ,145,145,145
BEGIN DESCRIPTION:
Mapping XS 8d5af2de
END DESCRIPTION:
XS GIS Cut Line= 2
      2393212.34     13168919.21      2394132.48     13168754.28
#Sta/Elev= 30
  4536.8   84.84  4578.2   84.83  4613.4      82    4654   80.46  4664.2   79.24
  4684.5   78.56  4725.1   75.75  4786.1   73.07  4796.2   73.15  4808.3   71.28
  4836.9   69.58  4877.5   68.03    4969   66.74  4971.6   65.43  4974.4   64.93
  4977.6   65.43  4992.9    65.8  5028.4   65.62  5035.9   66.07  5121.3   67.99
  5212.8   73.33  5253.4   74.55  5263.6   75.75  5304.2   76.06  5344.9   78.03
  5371.1   78.29  5385.5   79.88  5405.8   79.57  5446.4   81.75  5471.6    82.1
#Mann= 5 ,-1 , 0
  4536.8      .1       0  4971.6     .04       0  4977.6      .1       0
  4992.9     .05       0  5035.9      .1       0
Bank Sta=4971.6,4977.6
XS Rating Curve= 0 ,0
Exp/Cntr=0.3,0.1

Type RM Length L Ch R = 1 ,3194    ,432,432,432
BEGIN DESCRIPTION:
UNT030 IN BACR 4.0
END DESCRIPTION:
XS GIS Cut Line= 2
      2393255.83     13169036.38      2394192.99     13168888.87
#Sta/Elev= 30
  4512.4   83.94  4518.9    83.8  4608.2   80.66    4656   78.08  4670.7   77.87
  4676.3   77.09  4726.9   74.49  4733.2   73.49  4738.3   73.84  4747.1   73.38
  4823.7   68.16  4858.3   66.25    4980   64.64  4993.4   63.84  4997.2   62.19
    5000   61.69  5003.2   62.19  5010.3   63.95  5020.5   64.57    5056    64.2
  5111.6   65.87  5172.3   68.31  5186.1   69.61  5244.3   71.96  5303.9   73.92
  5334.3   75.74  5373.6   76.25    5395   77.36  5441.2   78.49  5461.1   80.34
#Mann= 6 ,-1 , 0
  4512.4      .1       0  4518.9     .05       0  4823.7      .1       0
  4997.2     .07       0  5003.2      .1       0  5244.3     .05       0
Bank Sta=4997.2,5003.2
XS Rating Curve= 0 ,0
Exp/Cntr=0.3,0.1

Type RM Length L Ch R = 1 ,2762    ,426,426,426
BEGIN DESCRIPTION:
UNT030 IN BACR 3.0
END DESCRIPTION:
XS GIS Cut Line= 3
       2393587.7     13169546.87      2393987.72     13169296.85
       2394337.7     13168896.88
#Sta/Elev= 30
  4504.8   81.46  4622.2   74.91  4685.8   72.33  4716.5   69.15  4728.9   66.99
  4762.3   65.99  4874.5   62.52  4917.6   62.24  4953.5   60.58  5026.4   59.97
  5040.6   59.54  5044.2   58.38    5047   57.88  5050.2   58.38  5069.1   60.79
  5123.4    59.2  5132.7   60.69  5153.5    60.8  5242.1   66.07  5253.2   66.85
  5259.8    66.2  5267.4   67.44  5274.1   67.01  5323.4   71.35  5366.1   73.95
    5388   76.36  5401.7   76.35    5444   79.81  5499.7   82.86    5508   83.32
#Mann= 7 ,-1 , 0
  4504.8     .05       0  4762.3      .1       0  5044.2     .07       0
  5050.2      .1       0  5123.4     .05       0  5242.1      .1       0
  5499.7     .05       0
Bank Sta=5044.2,5050.2
XS Rating Curve= 0 ,0
Exp/Cntr=0.3,0.1

Type RM Length L Ch R = 1 ,2336    ,552,552,552
BEGIN DESCRIPTION:
UNT030 IN BACR 2.0
END DESCRIPTION:
XS GIS Cut Line= 3
      2394187.72     13169796.85      2394387.72     13169446.85
      2394487.71     13169146.89
#Sta/Elev= 30
  4570.3    78.4  4599.8   76.45  4615.6   76.12  4627.9   74.57    4643   73.97
  4708.5   69.84  4717.9   68.88  4731.5   68.36  4801.9   63.14  4841.7   60.33
  4884.9   58.92  4892.8   58.19  4922.3   57.36  4928.1   57.54  4943.9   56.55
    4976   56.49    4984   55.43  4991.5   52.69  4994.2   52.19  4997.5   52.69
    5005   56.04  5047.2   56.97  5131.5   60.58  5184.2   65.23  5205.3   66.21
  5236.9   69.92  5249.4   70.48  5268.6   71.45  5279.1   73.08  5289.6   73.28
#Mann= 5 ,-1 , 0
  4570.3      .1       0  4801.9     .15       0    4984     .07       0
    5005     .15       0  5249.4      .1       0
Bank Sta=4984,5005
XS Rating Curve= 0 ,0
Exp/Cntr=0.3,0.1

Type RM Length L Ch R = 1 ,1784    ,692,692,692
BEGIN DESCRIPTION:
Mapping XS d9e5669f
END DESCRIPTION:
XS GIS Cut Line= 4
      2394241.05     13169965.21      2394748.84     13169865.38
      2394887.73     13169583.27       2394615.2      13169120.4
#Sta/Elev= 30
  4371.3    80.4  4459.6    78.3  4560.8   72.99  4596.6   71.38  4602.3   70.39
    4694   64.62  4714.4   62.58  4877.5   52.89  4888.8   52.51  4895.2   53.12
  4900.7   51.94  4923.2   51.27    4985   51.31  4990.6   49.88  4998.4   47.19
  5001.6   47.69  5007.5   50.43  5142.3   51.48  5147.9   50.58  5154.7   50.58
  5245.5   53.88  5251.9   55.55  5257.7   54.39  5273.4   54.34  5326.2   55.98
  5464.8   62.04  5535.6   65.98  5603.4   68.49  5630.7   70.25  5740.4   74.44
#Mann= 5 ,-1 , 0
  4371.3      .1       0  4560.8     .15       0  4990.6     .07       0
  5007.5     .15       0  5740.4      .1       0
Bank Sta=4990.6,5007.5
XS Rating Curve= 0 ,0
Exp/Cntr=0.3,0.1

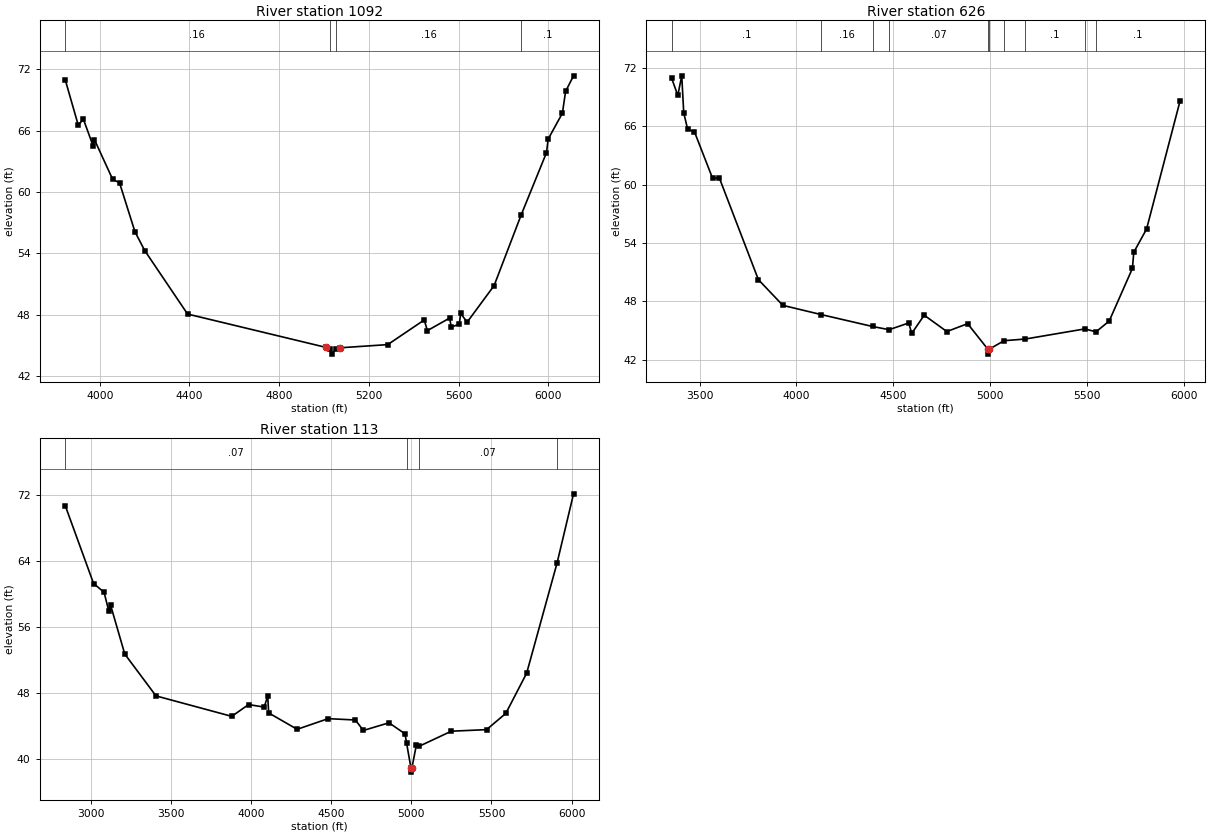
Type RM Length L Ch R = 1 ,1092    ,466,466,466
BEGIN DESCRIPTION:
Mapping XS 2bd8f829
END DESCRIPTION:
XS GIS Cut Line= 4
      2394371.22     13170138.82      2395421.59     13169908.79
      2395438.95      13169769.9      2394666.39      13169058.1
#Sta/Elev= 30
  3846.1   70.99  3903.9   66.57  3927.5   67.11  3971.3   64.46  3976.4   65.13
  4057.5   61.25  4088.2   60.91  4156.9   56.12  4200.8   54.27  4391.5   48.07
    5010    44.8  5024.1   44.68  5033.9   44.15  5054.3   44.68  5071.5   44.77
  5283.6   45.08  5446.3   47.49  5460.5   46.45  5559.8   47.68  5566.6   46.79
  5602.3   47.08  5609.1   48.13  5637.4   47.27  5757.7   50.85  5878.5   57.77
  5991.3   63.86  5998.7   65.18  6062.2   67.72  6076.4   69.85  6111.8   71.37
#Mann= 4 ,-1 , 0
  3846.1     .16       0  5024.1     .07       0  5054.3     .16       0
  5878.5      .1       0
Bank Sta=5010,5071.5
XS Rating Curve= 0 ,0
Exp/Cntr=0.3,0.1

Type RM Length L Ch R = 1 ,626     ,513,513,513
BEGIN DESCRIPTION:
Mapping XS 144707de
END DESCRIPTION:
XS GIS Cut Line= 5
      2394366.92     13170156.18      2395417.25     13169930.49
       2395595.2     13169631.01      2395603.88     13169440.04
      2394710.35     13168971.59
#Sta/Elev= 30
  3356.1   70.92  3387.6   69.16  3408.1   71.17  3418.3   67.37  3438.7   65.66
  3473.2   65.44  3566.8   60.66  3602.4   60.66  3803.5   50.23  3929.7   47.59
    4128   46.64  4392.3   45.42    4478   45.09  4579.1   45.78  4594.7   44.71
    4659   46.58  4775.8    44.9    4883   45.71  4987.7   43.08  4990.4   42.58
  4993.7   43.08  5071.3   43.96  5180.4   44.13  5487.7   45.17  5545.6   44.87
  5613.5   45.98  5733.4   51.39  5740.2   53.04  5806.3   55.43  5978.8   68.57
#Mann= 10 ,-1 , 0
  3356.1      .1       0    4128     .16       0  4392.3     .12       0
    4478     .07       0  4987.7     .07       0  4993.7     .07       0
  5071.3     .12       0  5180.4      .1       0  5487.7     .05       0
  5545.6      .1       0
#XS Ineff= 1 ,-1
    4056  4663.2   46.51
Permanent Ineff=
       F
Bank Sta=4987.7,4993.7
XS Rating Curve= 0 ,0
Exp/Cntr=0.3,0.1

Type RM Length L Ch R = 1 ,113     ,0,0,0
BEGIN DESCRIPTION:
UNT030 IN BACR 1.0
END DESCRIPTION:
XS GIS Cut Line= 5
      2394370.37     13170168.34      2395466.53     13169939.01
      2395629.92     13169617.99      2395634.26     13168884.48
      2394675.04     13168867.12
#Sta/Elev= 30
  2839.1    70.7  3016.2   61.25  3081.6   60.19    3111   57.93  3122.5   58.62
  3210.9    52.7  3405.7   47.63  3878.5   45.15  3983.9   46.58  4081.1   46.27
  4103.3   47.61  4108.9   45.57  4286.9   43.58  4480.3   44.87  4650.3   44.71
  4700.3   43.44  4860.3   44.37  4960.3   43.03  4970.3   41.88  4997.3   38.89
  5000.1   38.39  5003.3   38.89  5030.3   41.62    5049   41.53  5249.3   43.35
  5469.3   43.54  5589.4   45.51  5719.4   50.38  5909.4   63.74  6012.1   72.12
#Mann= 4 ,-1 , 0
  2839.1     .07       0  4970.3     .05       0    5049     .07       0
  5909.4      .1       0
Bank Sta=4997.3,5003.3
XS Rating Curve= 0 ,0
Exp/Cntr=0.3,0.1

Chan Stop Cuts=-1
Use User Specified Reach Order=0
Composite Channel Slope=5