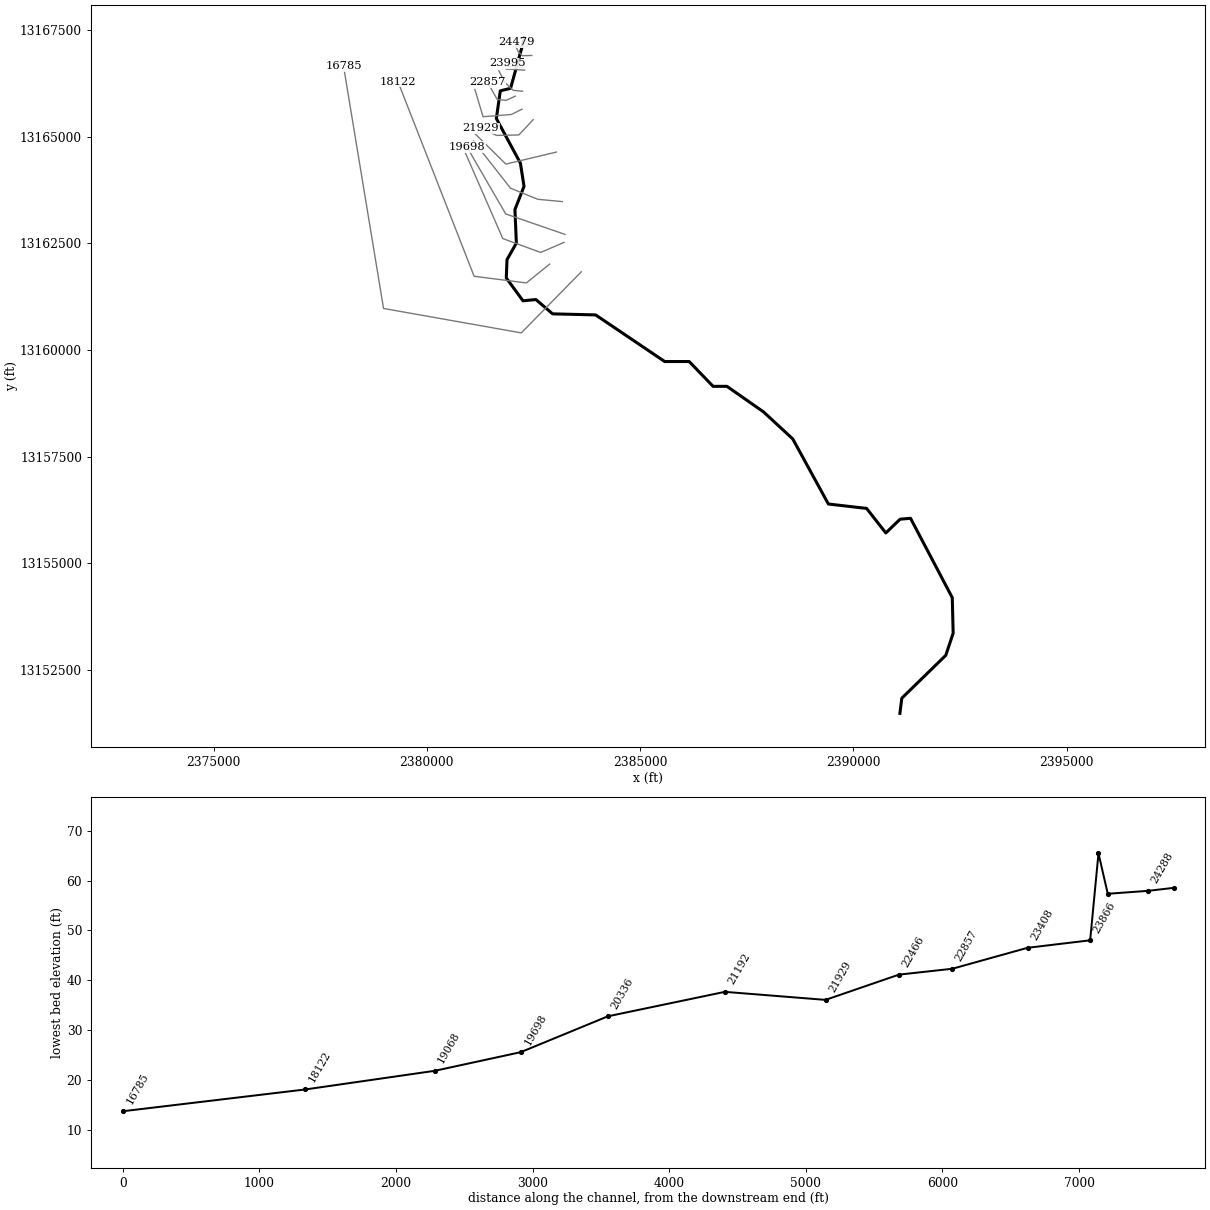
--- UNT031 IN BACR.prj (project) ---

Proj Title=UNT031 IN BACR Base Level Engineering
Current Plan=p01
Default Exp/Contr=0.3,0.1
English Units
Geom File=g01
Flow File=f01
Plan File=p01
Y Axis Title=Elevation
X Axis Title(PF)=Main Channel Distance
X Axis Title(XS)=Station
BEGIN DESCRIPTION:
UNT031 IN BACR
END DESCRIPTION:
DSS File=dss
DSS Export Rating Curves= 0
DSS Export Rating Curve Sorted= 0
DSS Export Volume Flow Curves= 0
DXF OffsetX= 0
DXF OffsetY= 0
DXF ScaleX= 1
DXF ScaleY= 10

--- UNT031 IN BACR.p01 (plan) ---

Plan Title=Multiple Run
Program Version=4.10
Short Identifier=Multiple Run
Geom File=g01
Flow File=f01
Subcritical Flow
K Sum by GR= 0
Std Step Tol= 0.01
Critical Tol= 0.01
Num of Std Step Trials= 20
Max Error Tol= 0.3
Flow Tol Ratio= 0.001
Split Flow NTrial= 30
Split Flow Tol= 0.02
Split Flow Ratio= 0.02
Log Output Level= 0
Friction Slope Method= 1
Unsteady Friction Slope Method= 2
Unsteady Bridges Friction Slope Method= 1
Parabolic Critical Depth
Global Vel Dist= 1 , 1 , 1
Global Log Level= 0
CheckData=True
Encroach Param=-1 ,0,0, 0
BEGIN DESCRIPTION:
Multiple Run
END DESCRIPTION:
Computation Interval=1HOUR
Output Interval=1HOUR
Run HTab= 0
Run UNet= 0
Run PostProcess= 0
Run WQNet= 0
UNET Theta= 1
UNET Theta Warmup= 1
UNET ZTol= 0.02
UNET ZSATol= 0.05
UNET MxIter= 20
UNET MaxInSteps= 0
UNET DtIC= 0
UNET DtMin= 0
UNET MaxCRTS= 20
UNET WFStab= 2
UNET SFStab= 1
UNET WFX= 1
UNET SFX= 1
UNET DSS MLevel= 4
UNET DZMax Abort= 100
UNET Convert EG Bridges= 0
UNET Use Existing IB Tables=-1
UNET Froude Reduction=False
UNET Froude Limit= 1
UNET Froude Power= 10
UNET Time Slicing=0,0, 5
UNET Junction Losses=0
Instantaneous Interval=1HOUR
DSS File=dss
Write IC File= 0
Write IC File at Sim End=0
Echo Input=False
Echo Parameters=False
Echo Output=False
Write Detailed= 0
WQ AD Non Conservative
WQ ULTIMATE=-1
WQ Max Comp Step=1HOUR
WQ Output Interval=15MIN
WQ Output Selected Increments= 0
WQ Output face flow=0
WQ Output face velocity=0
WQ Output face area=0
WQ Output face dispersion=0
WQ Output cell volume=0
WQ Output cell surface area=0
WQ Output cell continuity=0
WQ Output cumulative cell continuity=0
WQ Output face conc=0
WQ Output face dconc_dx=0
WQ Output face courant=0
WQ Output face peclet=0
WQ Output face adv mass=0
WQ Output face disp mass=0
WQ Output cell mass=0
WQ Output cell source sink temp=0
WQ Output cell source sink nsm=0
WQ Output MaxMinRange=-1
WQ Daily Max Min Mean=-1
WQ Daily Range=0
WQ Daily Time=0
WQ Create Restart=0
WQ Fixed Restart=0
WQ System Summary=0
WQ Use Fixed Temperature=0
Sorting and Armoring Iterations= 10
XS Update Threshold= 0.02
Hydraulics Update Threshold= 0.02
Energy Slope Method= 1
Volume Change Method= 0
XS Weighting Method= 0
Number of US Weighted Cross Sections= 1
Number of DS Weighted Cross Sections= 1
Upstream XS Weight=0.25
Main XS Weight=0.5
Downstream XS Weight=0.25
Number of DS XS's Weighted with US Boundary= 1
Upstream Boundary Weight= 1
Weight of XSs Associated with US Boundary= 0
Number of US XS's Weighted with DS Boundary= 1
Downstream Boundary Weight= 0.5
Weight of XSs Associated with DS Boundary= 0.5
Sediment Output Level= 4
Mass or Volume Output= 0
Output Increment Type= 1
Profile and TS Output Increment= 10
XS Output Flag= 0
XS Output Increment= 10
Disregard all LS=0
Disregard all Conn=0
Disregard all Breaches=0
Disregard all Pumps=0

--- UNT031 IN BACR.f01 (steady flow) ---

Flow Title=Multiple
Number of Profiles=7
Profile Names=10-year,25-year,50-year,1pct_min,100-year,1pct_plu,500-year
River Rch & RM= UNT031 IN BACR,Reach-1,24479
     276     370     446     394     533     720     766
River Rch & RM= UNT031 IN BACR,Reach-1,23995
     364     498     607     542     733     991    1079
River Rch & RM= UNT031 IN BACR,Reach-1,16785
     658     922    1143    1036    1401    1895    2127
Boundary for River Rch & Prof#=UNT031 IN BACR,Reach-1,1
Up Type=0
Dn Type=3
Dn Slope=0.005
Boundary for River Rch & Prof#=UNT031 IN BACR,Reach-1,2
Up Type=0
Dn Type=3
Dn Slope=0.005
Boundary for River Rch & Prof#=UNT031 IN BACR,Reach-1,3
Up Type=0
Dn Type=3
Dn Slope=0.005
Boundary for River Rch & Prof#=UNT031 IN BACR,Reach-1,4
Up Type=0
Dn Type=3
Dn Slope=0.005
Boundary for River Rch & Prof#=UNT031 IN BACR,Reach-1,5
Up Type=0
Dn Type=3
Dn Slope=0.005
Boundary for River Rch & Prof#=UNT031 IN BACR,Reach-1,6
Up Type=0
Dn Type=3
Dn Slope=0.005
Boundary for River Rch & Prof#=UNT031 IN BACR,Reach-1,7
Up Type=0
Dn Type=3
Dn Slope=0.005

--- UNT031 IN BACR.g01 (geometry) ---

Geom Title=Existing Conditions
Program Version=4.10

River Reach=UNT031 IN BACR  ,Reach-1
Reach XY= 30
      2382285.86     13167305.78      2381962.37     13166133.98
      2381721.34     13166075.37        2381629.     13165426.53
      2382192.45     13164380.15      2382277.72     13163836.85
      2382064.87     13163293.52      2382097.85     13162505.33
       2381879.1     13162119.91      2381861.74     13161689.35
      2382253.24     13161154.34       2382555.6     13161183.19
      2382948.12     13160847.96      2383956.12     13160822.99
      2385575.84     13159729.74      2386147.97     13159730.74
      2386708.88     13159148.77      2387033.69     13159149.25
      2387892.53     13158548.71      2388575.86     13157916.98
      2389411.47     13156390.67      2390307.39     13156287.39
      2390757.82     13155712.28      2391092.46      13156035.2
      2391337.25     13156056.03       2392315.3     13154195.85
      2392336.01     13153361.92      2392162.84     13152844.09
      2391132.55     13151839.57      2391087.72     13151483.57

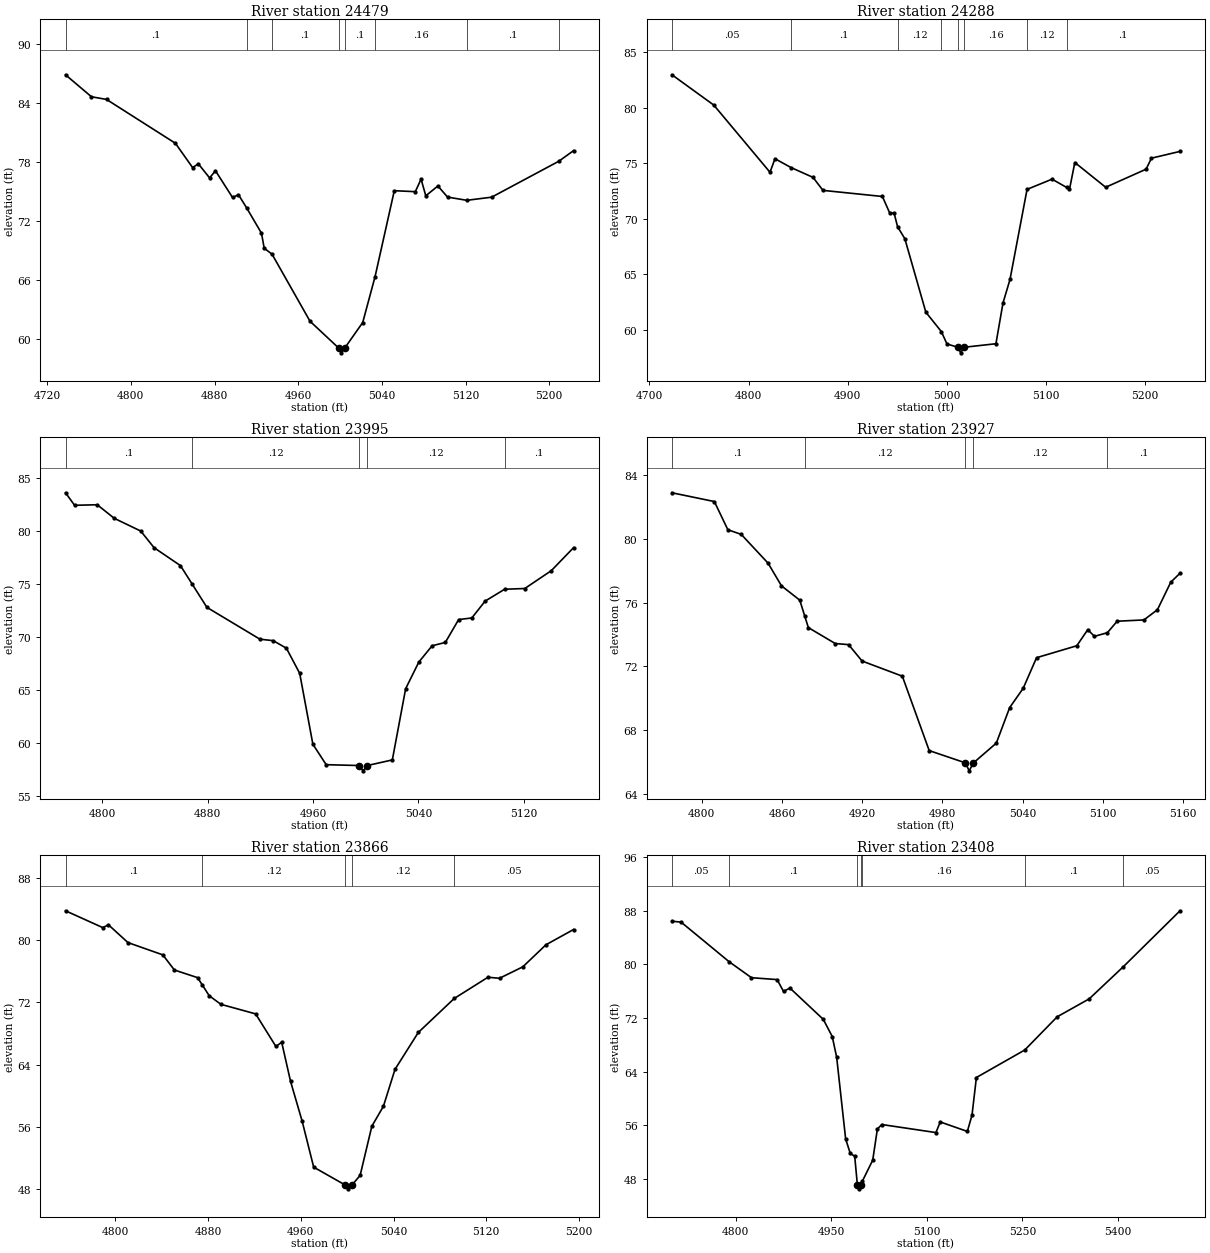
Type RM Length L Ch R = 1 ,24479   ,191,191,191
BEGIN DESCRIPTION:
UNT031 IN BACR 33.0
END DESCRIPTION:
XS GIS Cut Line= 4
      2382429.91     13167288.77      2382340.31     13167120.25
      2382183.84     13167100.86      2382108.93      13167215.9
#Sta/Elev= 30
  4737.5   86.87  4762.3   84.63  4776.7   84.36  4842.6   79.89    4859   77.42
  4864.6   77.79  4875.3   76.36  4880.9   77.09  4897.2   74.37  4902.9   74.65
  4910.8   73.29  4924.9   70.73  4927.5    69.2    4935   68.59  4971.3   61.76
  4998.6   59.04  5001.3   58.54  5004.6   59.04  5021.7   61.63  5033.5    66.3
  5051.9   75.06    5072   74.96  5077.5   76.24    5082   74.54  5093.6   75.54
  5102.8   74.41  5121.2   74.08    5145    74.4  5209.2   78.06  5223.3   79.14
#Mann= 8 ,-1 , 0
  4737.5      .1       0  4910.8     .05       0    4935      .1       0
  4998.6     .07       0  5004.6      .1       0  5033.5     .16       0
  5121.2      .1       0  5209.2     .16       0
Bank Sta=4998.6,5004.6
XS Rating Curve= 0 ,0
Exp/Cntr=0.3,0.1

Type RM Length L Ch R = 1 ,24288   ,293,293,293
BEGIN DESCRIPTION:
Mapping XS ff82226e
END DESCRIPTION:
XS GIS Cut Line= 4
      2382459.96     13166904.28        2382238.     13166898.93
       2382137.7     13166997.89      2382080.89     13167136.26
#Sta/Elev= 30
  4722.8   82.97    4765   80.24  4821.7   74.19  4826.7   75.41  4842.8   74.62
  4865.1   73.73  4875.1   72.56  4935.1   72.01  4942.5   70.51  4946.9   70.51
  4950.4   69.28  4957.7   68.21  4978.9   61.59  4994.5   59.85  5000.2   58.73
  5011.3   58.43  5014.1   57.93  5017.3   58.43  5049.6   58.75  5056.7   62.41
  5063.8   64.54    5081   72.65  5106.2   73.57  5120.8   72.83  5123.8   72.65
  5129.2   75.07  5160.3   72.84  5201.1   74.47  5206.5   75.46  5235.3   76.07
#Mann= 8 ,-1 , 0
  4722.8     .05       0  4842.8      .1       0  4950.4     .12       0
  4994.5     .16       0  5011.3     .07       0  5017.3     .16       0
    5081     .12       0  5120.8      .1       0
Bank Sta=5011.3,5017.3
XS Rating Curve= 0 ,0
Exp/Cntr=0.3,0.1

Type RM Length L Ch R = 1 ,23995   ,68,68,68
BEGIN DESCRIPTION:
Mapping XS 176b08f7
END DESCRIPTION:
XS GIS Cut Line= 2
      2382284.54     13166679.26      2381900.92     13166717.28
#Sta/Elev= 30
  4772.2   83.58  4779.1    82.4  4796.3   82.45  4809.2   81.17  4829.3   79.97
  4839.4    78.4  4859.4   76.71  4868.3   74.97  4879.5   72.77  4919.7   69.77
  4929.8   69.63  4939.8   68.92  4949.9   66.55  4959.9   59.86    4970   57.93
  4995.2   57.85    4998   57.35  5001.2   57.85  5020.2   58.38  5030.3    65.1
  5040.3   67.61  5050.4   69.15  5060.4   69.46  5070.5   71.62  5080.5   71.77
  5090.6   73.36  5105.4   74.48  5120.7   74.55  5140.8   76.23  5157.7    78.4
#Mann= 5 ,-1 , 0
  4772.2      .1       0  4868.3     .12       0  4995.2     .07       0
  5001.2     .12       0  5105.4      .1       0
Bank Sta=4995.2,5001.2
XS Rating Curve= 0 ,0
Exp/Cntr=0.3,0.1

Type RM Length L Ch R = 1 ,23927   ,61,61,61
BEGIN DESCRIPTION:
Mapping XS 0fc91b3f
END DESCRIPTION:
XS GIS Cut Line= 2
      2382279.31     13166613.29      2381900.88     13166647.85
#Sta/Elev= 30
  4777.7   82.89  4809.4   82.34  4819.5   80.57  4829.5   80.28  4849.6   78.47
  4859.6   77.05  4873.3   76.15  4876.9   75.18  4879.7   74.43  4899.8   73.43
  4909.8   73.36  4919.9   72.33    4950   71.38  4970.1   66.71  4997.2   65.94
    5000   65.44  5003.2   65.94  5020.3   67.18  5030.3   69.41  5040.4   70.62
  5050.4   72.54  5080.5   73.29  5088.7    74.3  5093.7   73.88  5103.4   74.11
  5110.7   74.83  5130.7   74.91  5140.8   75.55  5150.8   77.28  5157.7   77.84
#Mann= 5 ,-1 , 0
  4777.7      .1       0  4876.9     .12       0  4997.2     .07       0
  5003.2     .12       0  5103.4      .1       0
Bank Sta=4997.2,5003.2
XS Rating Curve= 0 ,0
Exp/Cntr=0.3,0.1

Type RM Length L Ch R = 1 ,23866   ,458,458,458
BEGIN DESCRIPTION:
UNT031 IN BACR 32.0
END DESCRIPTION:
XS GIS Cut Line= 2
      2382291.48     13166559.47      2381853.98     13166588.99
#Sta/Elev= 30
  4756.9   83.78    4789   81.62    4794   81.97  4810.8   79.69  4840.9   78.11
  4850.9   76.16  4870.9   75.18  4875.1   74.21  4880.9   72.86    4891   71.75
    4921   70.52  4938.5   66.33  4943.5   66.87  4951.1   61.86  4961.1   56.75
  4971.1   50.81  4998.2   48.52    5001   48.02  5004.2   48.52  5011.2   49.75
  5021.3   56.07  5031.3   58.64  5041.3   63.39  5061.4   68.13  5092.4    72.5
  5121.5   75.23  5131.5    75.1  5151.6   76.57  5171.6   79.41  5195.4   81.37
#Mann= 5 ,-1 , 0
  4756.9      .1       0  4875.1     .12       0  4998.2     .07       0
  5004.2     .12       0  5092.4     .05       0
Bank Sta=4998.2,5004.2
XS Rating Curve= 0 ,0
Exp/Cntr=0.3,0.1

Type RM Length L Ch R = 1 ,23408   ,551,551,551
BEGIN DESCRIPTION:
UNT031 IN BACR 31.0
END DESCRIPTION:
XS GIS Cut Line= 4
      2382241.99     13166065.55      2382025.81     13166086.39
      2381822.34     13166277.62      2381687.73     13166546.83
#Sta/Elev= 30
  4700.1   86.42  4714.4   86.29    4790   80.37  4824.9      78  4865.1   77.72
  4875.2   75.95  4885.2   76.46  4937.6   71.79  4951.7   69.22  4958.6   66.13
  4972.7   53.95    4980   51.79  4986.9   51.39  4991.2   47.02    4994   46.52
  4997.2   47.02  4998.7   47.62  5015.2    50.8  5022.5   55.44  5029.4   56.11
  5114.4   54.91  5121.2   56.49  5163.7   55.08    5171    57.5  5177.9   63.12
  5253.8   67.22  5304.7   72.17    5355   74.85  5408.3   79.62  5497.5   87.98
#Mann= 7 ,-1 , 0
  4700.1     .05       0    4790      .1       0  4991.2     .07       0
  4997.2      .1       0  4998.7     .16       0  5253.8      .1       0
  5408.3     .05       0
Bank Sta=4991.2,4997.2
XS Rating Curve= 0 ,0
Exp/Cntr=0.3,0.1

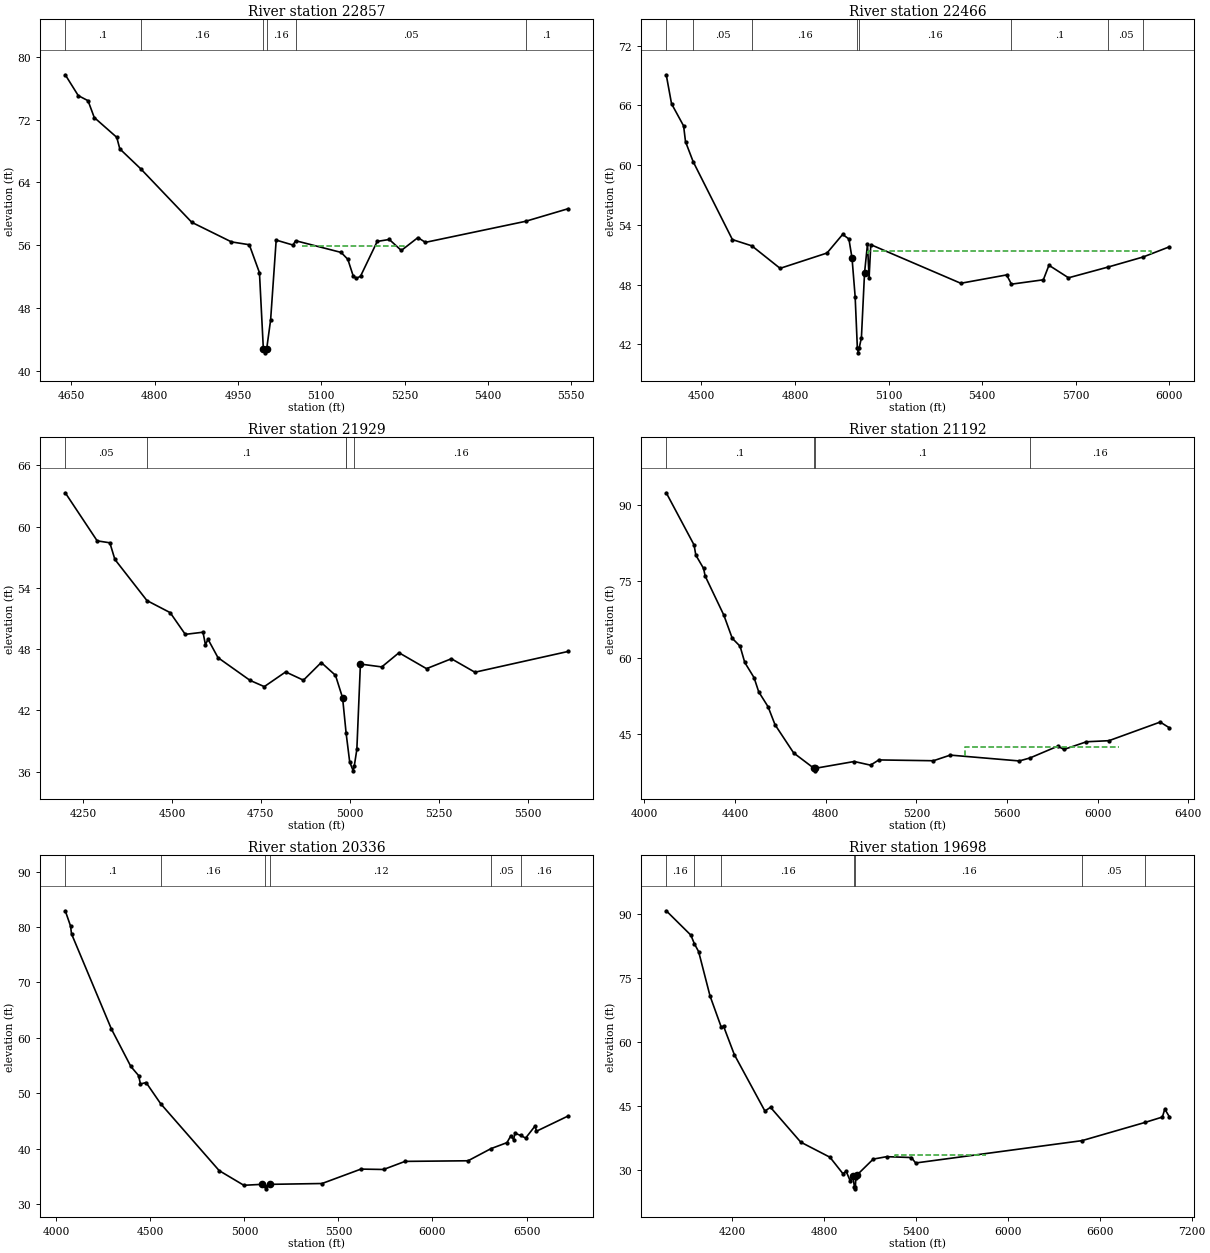
Type RM Length L Ch R = 1 ,22857   ,391,391,391
BEGIN DESCRIPTION:
UNT031 IN BACR 30.0
END DESCRIPTION:
XS GIS Cut Line= 4
      2382075.25     13165950.95      2381856.54     13165852.01
      2381648.21     13165875.45      2381424.82     13166272.87
#Sta/Elev= 30
    4639   77.71  4662.4   75.06    4680   74.41  4691.2   72.27  4731.7   69.75
  4737.2   68.28  4774.9   65.74  4866.8   58.93  4938.2   56.44  4970.3   56.08
  4988.6   52.52  4995.6   42.82  4998.4   42.32  5001.6   42.82  5008.7   46.52
  5018.7   56.67  5048.9   56.04  5053.7   56.59  5135.6    55.1  5147.7   54.22
  5157.3   52.12    5163   51.79  5170.6   52.08  5200.6    56.5  5222.3   56.75
    5244   55.35  5273.9   56.99  5287.3   56.38  5467.7   59.06  5544.6   60.67
#Mann= 6 ,-1 , 0
    4639      .1       0  4774.9     .16       0  4995.6     .07       0
  5001.6     .16       0  5053.7     .05       0  5467.7      .1       0
#XS Ineff= 1 ,-1
  5064.8  5249.6   55.91
Permanent Ineff=
       F
Bank Sta=4995.6,5001.6
XS Rating Curve= 0 ,0
Exp/Cntr=0.3,0.1

Type RM Length L Ch R = 1 ,22466   ,537,537,537
BEGIN DESCRIPTION:
UNT031 IN BACR 29.0
END DESCRIPTION:
XS GIS Cut Line= 4
      2382232.96     13165646.53      2381981.24     13165520.68
      2381317.18     13165468.59      2381126.21      13166106.6
#Sta/Elev= 30
  4387.1   69.08  4404.1   66.17  4442.8   63.94  4448.9   62.36  4473.3   60.36
  4599.3   52.52  4661.7   51.89  4752.3   49.63  4902.8   51.17  4952.9   53.04
    4973   52.58    4983   50.66    4993   46.79  5000.1   41.64  5002.8   41.14
  5006.1   41.64  5013.1   42.66  5023.1   49.16  5032.6   52.07  5037.7   48.65
  5043.2   52.01  5331.8   48.13  5478.9   48.97  5494.3   48.04  5596.6   48.48
  5614.6   49.94  5677.3   48.68  5804.2   49.76  5916.5   50.77  6000.6   51.79
#Mann= 8 ,-1 , 0
  4387.1      .1       0  4473.3     .05       0  4661.7     .16       0
  5000.1     .07       0  5006.1     .16       0  5494.3      .1       0
  5804.2     .05       0  5916.5      .1       0
#XS Ineff= 2 ,-1
  4481.6  4953.6   52.06 5034.11 5942.8551.41662
Permanent Ineff=
       F       F
Bank Sta=4983,5023.1
XS Rating Curve= 0 ,0
Exp/Cntr=0.3,0.1

Type RM Length L Ch R = 1 ,21929   ,737,737,737
BEGIN DESCRIPTION:
Mapping XS a840e169
END DESCRIPTION:
XS GIS Cut Line= 4
       2382492.2     13165399.28      2382155.85     13165041.23
      2381635.01     13165030.38      2381267.58     13165192.48
#Sta/Elev= 30
  4200.3   63.32    4290   58.61  4325.6   58.42  4339.8   56.79  4429.9   52.76
  4495.1   51.58  4537.6   49.45  4587.4   49.66  4594.3   48.43  4601.5   48.97
  4629.5   47.17  4719.7   44.94  4759.7   44.33  4819.7   45.77  4869.7   44.96
  4919.7   46.69  4959.7   45.44  4979.7   43.24  4989.7   39.75  4999.7   36.95
  5009.5   36.08  5012.7   36.58  5019.8   38.18  5029.8   46.54  5089.8   46.26
  5138.2   47.65  5215.6   46.09  5285.5   47.06  5351.6   45.74  5614.1   47.78
#Mann= 5 ,-1 , 0
  4200.3     .05       0  4429.9      .1       0  4989.7     .05       0
  4989.7     .05       0  5012.7     .16       0
#XS Ineff= 1 ,-1
 4621.12  4916.8   46.29
Permanent Ineff=
       F
Bank Sta=4979.7,5029.8
XS Rating Curve= 0 ,0
Exp/Cntr=0.3,0.1

Type RM Length L Ch R = 1 ,21192   ,856,856,856
BEGIN DESCRIPTION:
UNT031 IN BACR 28.0
END DESCRIPTION:
XS GIS Cut Line= 3
      2383034.72     13164639.75      2381852.03     13164357.64
      2381136.46     13165062.36
#Sta/Elev= 30
    4096   92.48  4218.8    82.2  4226.6   80.19  4260.9   77.56  4267.7   76.08
  4350.3   68.36  4387.3   63.81  4421.9   62.24  4442.5   59.05  4483.6   56.05
  4504.1   53.26  4545.3   50.33  4576.1   46.78  4658.3   41.22  4747.9   38.19
  4750.6   37.69  4753.9   38.19  4925.6   39.53  4997.6   38.81  5034.3   39.84
  5275.2   39.68  5349.7   40.79  5653.8   39.64  5700.9   40.22  5823.4   42.54
  5851.7   41.91  5950.7   43.42  6049.7   43.63    6276    47.3  6316.2   46.18
#Mann= 4 ,-1 , 0
    4096      .1       0  4747.9     .03       0  4753.9      .1       0
  5700.9     .16       0
#XS Ineff= 1 ,-1
    5414    6094   42.43
Permanent Ineff=
       F
Bank Sta=4747.9,4753.9
XS Rating Curve= 0 ,0
Exp/Cntr=0.3,0.1

Type RM Length L Ch R = 1 ,20336   ,638,638,638
BEGIN DESCRIPTION:
UNT031 IN BACR 27.0
END DESCRIPTION:
XS GIS Cut Line= 4
      2383175.79     13163478.73      2382600.72     13163532.98
      2381960.53      13163793.4      2381092.62     13164899.99
#Sta/Elev= 30
  4047.2   82.92  4075.4   80.16  4080.4   78.77  4292.4   61.62  4395.8   54.86
    4437   53.22    4447    51.7  4477.2   51.95  4554.3   48.15  4865.8   36.07
  4996.9   33.43  5092.3    33.6  5110.9   33.29  5113.6   32.79  5135.5    33.6
  5412.6   33.75  5619.6   36.35  5739.9   36.28  5854.1   37.74  6189.2   37.85
  6311.2   40.04  6396.1   41.12    6417   42.38  6431.4   41.64  6438.7   42.83
  6468.1   42.41  6495.6   41.95  6545.3   44.11  6553.1   43.18  6722.3   45.94
#Mann= 6 ,-1 , 0
  4047.2      .1       0  4554.3     .16       0  5110.9     .07       0
  5135.5     .12       0  6311.2     .05       0  6468.1     .16       0
Bank Sta=5092.3,5135.5
XS Rating Curve= 0 ,0
Exp/Cntr=0.3,0.1

Type RM Length L Ch R = 1 ,19698   ,630,630,630
BEGIN DESCRIPTION:
UNT031 IN BACR 26.0
END DESCRIPTION:
XS GIS Cut Line= 3
      2383237.67      13162710.5      2381848.73     13163189.68
      2380939.02     13164759.12
#Sta/Elev= 30
  3770.3   90.87    3931   85.15  3953.7   83.15  3981.8   81.28  4055.9    70.9
  4129.9    63.5  4144.1    63.8  4214.5   57.12  4414.3   43.86  4450.8   44.74
  4648.2   36.56  4838.7   33.02  4923.3   29.17  4944.7   29.71  4970.6    27.5
  4986.8   28.58  4998.8    26.1  5001.5    25.6  5004.8    26.1  5007.9   28.23
  5018.5   28.96  5121.3   32.58  5208.9   33.15  5370.2   32.95  5398.1   31.67
  6483.4   36.91  6894.3   41.18  7008.4   42.45  7024.2   44.33  7053.6   42.53
#Mann= 7 ,-1 , 0
  3770.3     .16       0  3953.7      .1       0  4129.9     .16       0
  4998.8     .07       0  5004.8     .16       0  6483.4     .05       0
  6894.3      .1       0
#XS Ineff= 1 ,-1
  5266.4  5858.4   33.64
Permanent Ineff=
       F
Bank Sta=4986.8,5018.5
XS Rating Curve= 0 ,0
Exp/Cntr=0.3,0.1

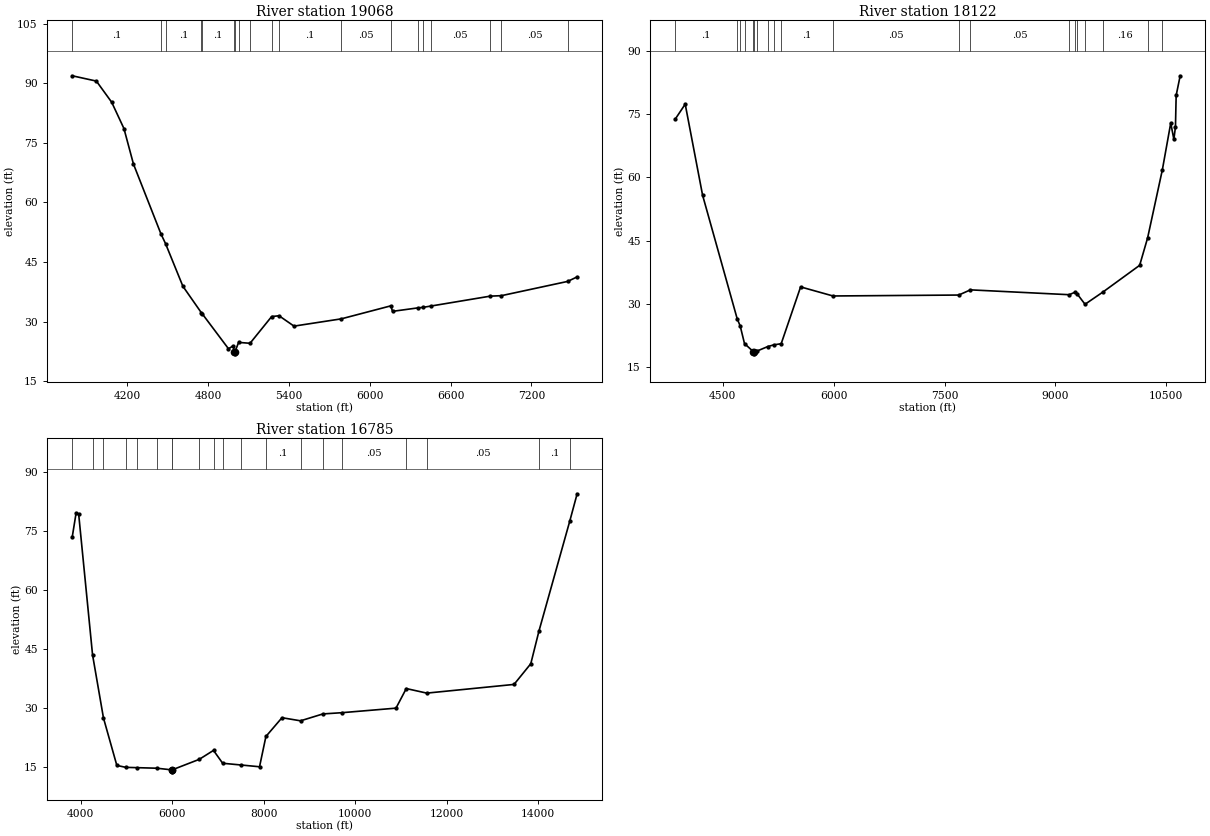
Type RM Length L Ch R = 1 ,19068   ,946,946,946
BEGIN DESCRIPTION:
UNT031 IN BACR 25.0
END DESCRIPTION:
XS GIS Cut Line= 4
      2383216.77     13162523.01      2382668.18     13162286.91
      2381779.29      13162613.3      2380897.85     13164632.97
#Sta/Elev= 30
  3791.7   91.89    3971   90.55  4084.6   85.23  4175.6    78.6  4246.2   69.66
    4450   52.09  4484.6    49.6  4613.1   38.88  4750.2   32.21  4755.8   31.99
  4951.6   23.14  4987.4    23.9  4993.6   22.36  4996.4   21.86  4999.6   22.36
  5026.6   24.74  5111.6   24.52  5271.9   31.25  5326.8   31.45  5437.9   28.84
  5788.5   30.67  6156.8   33.95    6169   32.56  6356.5   33.43  6392.3   33.55
  6451.1   33.88  6894.4   36.39  6977.2   36.51  7469.1    40.1  7539.5   41.24
#Mann= 19 ,-1 , 0
  3791.7      .1       0    4450     .16       0  4484.6      .1       0
  4750.2     .16       0  4755.8      .1       0  4993.6     .07       0
  4999.6      .1       0  5026.6     .12       0  5111.6      .1       0
  5271.9     .16       0  5326.8      .1       0  5788.5     .05       0
  6156.8      .1       0  6356.5     .05       0  6392.3      .1       0
  6451.1     .05       0  6894.4      .1       0  6977.2     .05       0
  7469.1      .1       0
Bank Sta=4993.6,4999.6
XS Rating Curve= 0 ,0
Exp/Cntr=0.3,0.1

Type RM Length L Ch R = 1 ,18122   ,1337,1337,1337
BEGIN DESCRIPTION:
UNT031 IN BACR 24.0
END DESCRIPTION:
XS GIS Cut Line= 4
       2382879.1     13162015.19      2382332.24      13161572.5
      2381108.28     13161728.75      2379324.41     13166286.07
#Sta/Elev= 30
  3856.9   73.79  3991.6   77.33  4226.6   55.75  4694.6   26.46  4735.7   24.73
  4793.8   20.56  4914.9   18.63  4917.6   18.13  4920.9   18.63  4968.6   18.83
  5110.5   19.87    5191   20.26  5290.2   20.53    5553      34  5991.4   31.85
  7693.1   32.07  7850.1    33.3  9187.9   32.15  9259.6    32.7  9292.8   32.38
  9401.2   29.88  9643.7   32.79 10140.3   39.12 10248.2   45.64 10447.3   61.76
 10560.8   72.85 10603.3   68.98 10624.8      72 10634.2   79.41 10688.4   84.06
#Mann= 20 ,-1 , 0
  3856.9      .1       0  4694.6     .12       0  4735.7     .16       0
  4793.8     .12       0  4914.9     .07       0  4920.9      .1       0
  4968.6     .12       0  5110.5      .1       0    5191     .12       0
  5290.2      .1       0  5991.4     .05       0  7693.1      .1       0
  7850.1     .05       0  9187.9     .16       0  9259.6      .1       0
  9292.8     .16       0  9401.2      .1       0  9643.7     .16       0
 10248.2      .1       0 10447.3      .1       0
Bank Sta=4914.9,4920.9
XS Rating Curve= 0 ,0
Exp/Cntr=0.3,0.1

Type RM Length L Ch R = 1 ,16785   ,0,0,0
BEGIN DESCRIPTION:
UNT031 IN BACR 1.0
END DESCRIPTION:
XS GIS Cut Line= 4
      2383620.43     13161833.78      2382214.18     13160401.49
      2378985.02     13160974.41      2378047.51     13166651.49
#Sta/Elev= 30
  3811.8   73.43  3896.4   79.54  3952.9   79.27  4256.2   43.51  4494.8   27.46
  4787.4   15.39    4984    14.9  5231.8   14.82    5664   14.68    5990   14.26
  5992.8   13.76    5996   14.26  6588.3   16.93    6901   19.21  7101.3   15.94
  7512.6   15.49  7907.6   15.05  8047.1   22.75  8398.6   27.52    8804   26.73
  9293.4   28.48  9704.7   28.79 10891.3   29.95 11116.4   34.93 11564.2   33.77
 13472.5   35.98   13839   41.24 14017.9   49.56 14690.1   77.44 14852.6   84.44
#Mann= 20 ,-1 , 0
  3811.8      .1       0  4256.2     .16       0  4494.8     .16       0
    4984     .12       0  5231.8     .05       0    5664     .12       0
    5990     .07       0    5996     .12       0  6588.3      .1       0
    6901      .1       0  7101.3     .07       0  7512.6     .05       0
  8047.1      .1       0    8804     .05       0  9293.4      .1       0
  9704.7     .05       0 11116.4      .1       0 11564.2     .05       0
 14017.9      .1       0 14690.1     .05       0
Bank Sta=5990,5996
XS Rating Curve= 0 ,0
Exp/Cntr=0.3,0.1

Chan Stop Cuts=-1
Use User Specified Reach Order=0
Composite Channel Slope=5