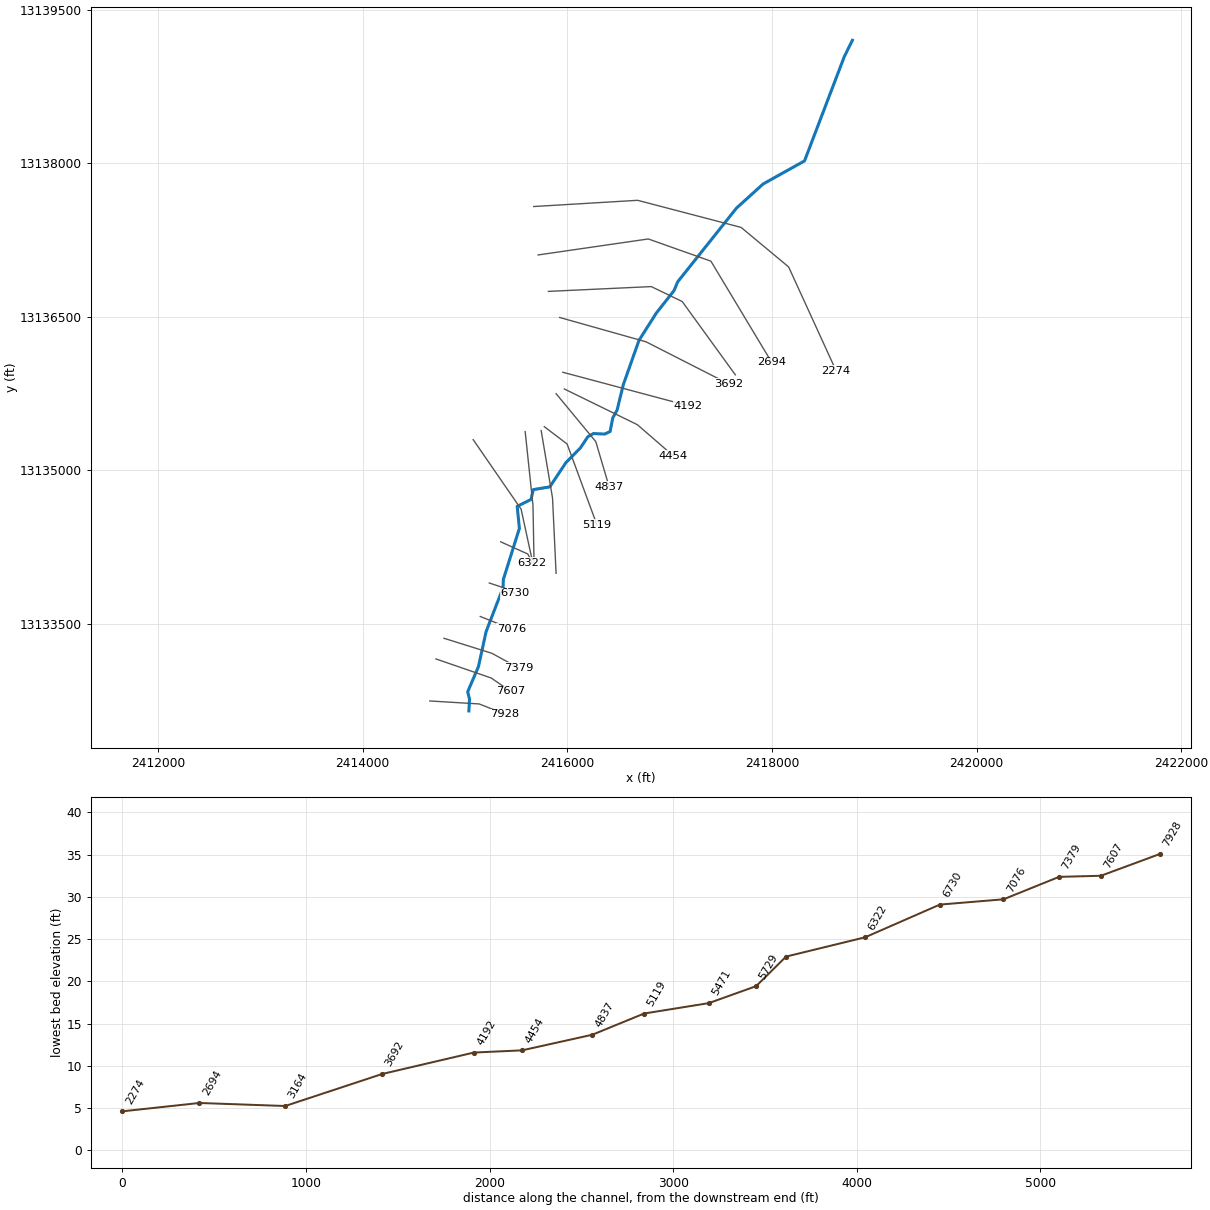
--- UNT032 IN BACR.prj (project) ---

Proj Title=UNT032 IN BACR Base Level Engineering
Current Plan=p01
Default Exp/Contr=0.3,0.1
English Units
Geom File=g01
Flow File=f01
Plan File=p01
Y Axis Title=Elevation
X Axis Title(PF)=Main Channel Distance
X Axis Title(XS)=Station
BEGIN DESCRIPTION:
UNT032 IN BACR
END DESCRIPTION:
DSS Export Rating Curves= 0
DSS Export Rating Curve Sorted= 0
DSS Export Volume Flow Curves= 0
DXF OffsetX= 0
DXF OffsetY= 0
DXF ScaleX= 1
DXF ScaleY= 10

--- UNT032 IN BACR.p01 (plan) ---

Plan Title=Multiple Run
Short Identifier=Multiple
Geom File=g01
Flow File=f01
Subcritical Flow
K Sum by GR= 0
Std Step Tol= 0.01
Critical Tol= 0.01
Num of Std Step Trials= 20
Max Error Tol= 0.3
Flow Tol Ratio= 0.001
Split Flow NTrial= 30
Split Flow Tol= 0.02
Split Flow Ratio= 0.02
Log Output Level= 0
Friction Slope Method= 1
Unsteady Friction Slope Method= 2
Unsteady Bridges Friction Slope Method= 1
Parabolic Critical Depth
Global Vel Dist=  1 , 1 , 1
Global Log Level= 0
CheckData=True
Encroach Param= -1, 0, 0, 0
BEGIN DESCRIPTION:
Multiple Run
END DESCRIPTION:

--- UNT032 IN BACR.f01 (steady flow) ---

Flow Title=Multiple
Number of Profiles=7
Profile Names=10-year,25-year,50-year,1pct_min,100-year,1pct_plu,500-year
River Rch & RM= UNT032 IN BACR,Reach-1,7928
     283     379     456     403     545     737     783
River Rch & RM= UNT032 IN BACR,Reach-1,7076
     355     484     588     524     709     958    1038
River Rch & RM= UNT032 IN BACR,Reach-1,3692
     427     586     716     641     867    1172    1282
Boundary for River Rch & Prof#=UNT032 IN BACR,Reach-1,1
Up Type=0
Dn Type=3
Dn Slope=0.005
Boundary for River Rch & Prof#=UNT032 IN BACR,Reach-1,2
Up Type=0
Dn Type=3
Dn Slope=0.005
Boundary for River Rch & Prof#=UNT032 IN BACR,Reach-1,3
Up Type=0
Dn Type=3
Dn Slope=0.005
Boundary for River Rch & Prof#=UNT032 IN BACR,Reach-1,4
Up Type=0
Dn Type=3
Dn Slope=0.005
Boundary for River Rch & Prof#=UNT032 IN BACR,Reach-1,5
Up Type=0
Dn Type=3
Dn Slope=0.005
Boundary for River Rch & Prof#=UNT032 IN BACR,Reach-1,6
Up Type=0
Dn Type=3
Dn Slope=0.005
Boundary for River Rch & Prof#=UNT032 IN BACR,Reach-1,7
Up Type=0
Dn Type=3
Dn Slope=0.005

--- UNT032 IN BACR.g01 (geometry) ---

Geom Title=Existing Conditions
Program Version=4.10

River Reach=UNT032 IN BACR  ,Reach-1
Reach XY= 30
      2415037.72     13132646.85      2415043.96     13132763.23
      2415025.86     13132833.32      2415131.33     13133079.41
      2415205.98     13133421.43      2415371.78     13133851.11
      2415374.39     13133930.98      2415531.51     13134430.98
       2415509.8     13134646.25      2415645.22     13134713.09
      2415666.92     13134809.45      2415828.74     13134836.27
      2415986.15     13135073.35      2416125.95     13135215.11
      2416200.49     13135326.19      2416255.18     13135357.44
      2416363.69     13135352.23      2416417.51     13135376.53
      2416443.55     13135509.35      2416486.08      13135586.6
      2416546.85     13135834.87      2416699.83     13136267.47
       2416869.1     13136534.39      2417043.58     13136755.75
      2417077.44     13136839.08      2417652.96     13137560.43
      2417913.38     13137796.11      2418317.72      13138021.6
      2418706.07     13139039.86      2418785.07     13139200.16

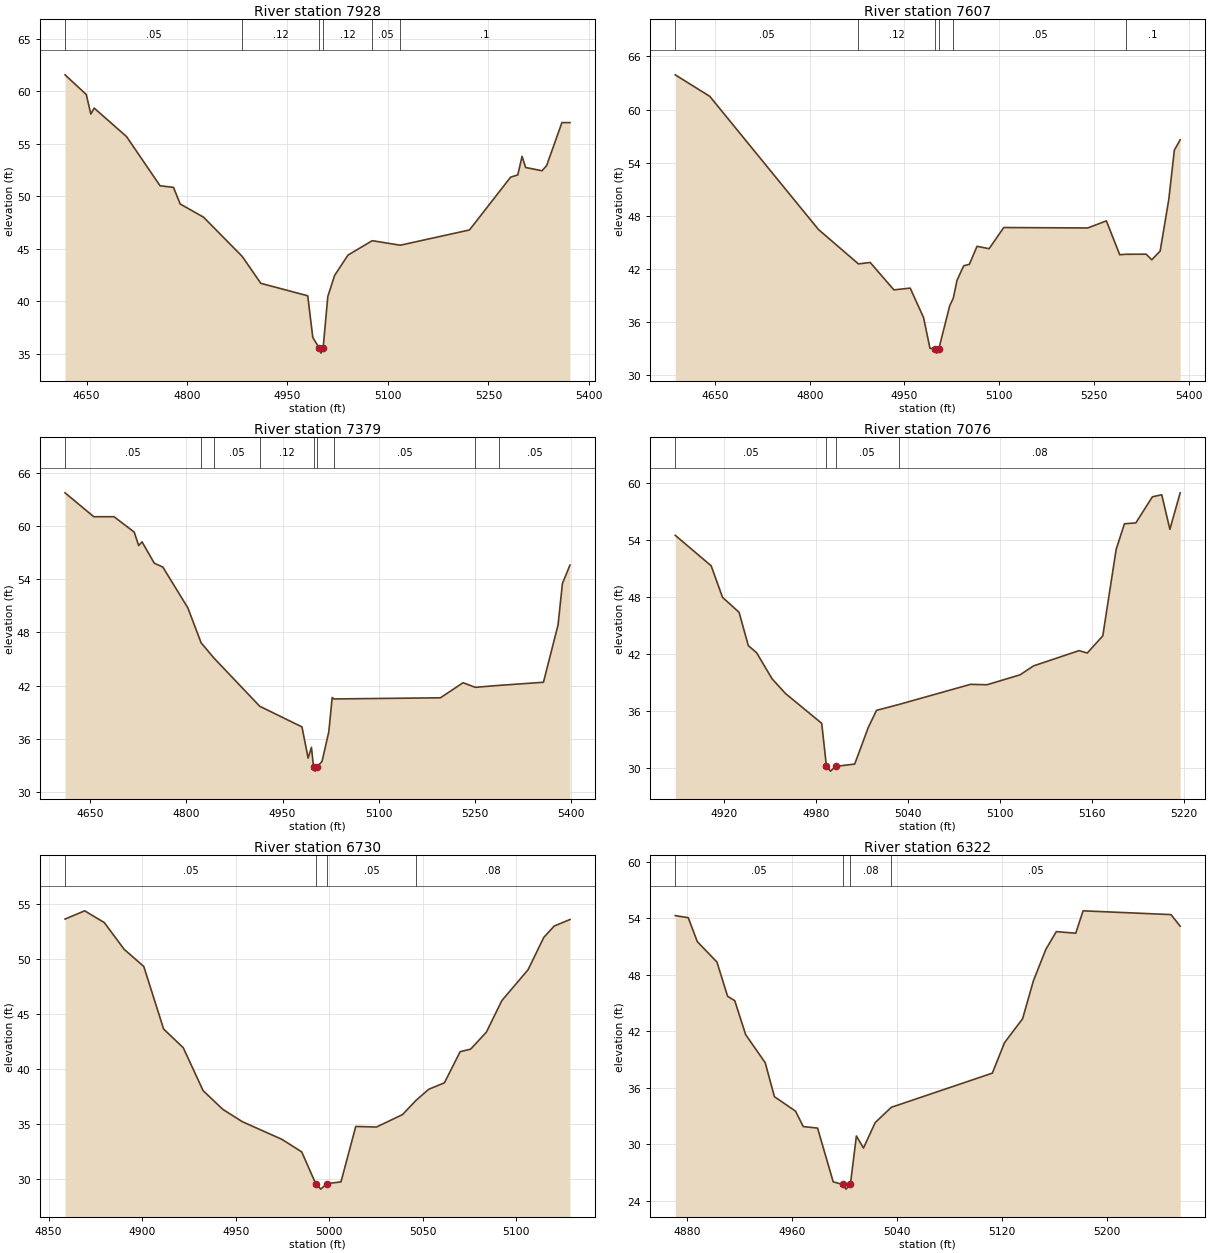
Type RM Length L Ch R = 1 ,7928    ,321,321,321
BEGIN DESCRIPTION:
UNT032 IN BACR 25.0
END DESCRIPTION:
XS GIS Cut Line= 3
       2414656.1     13132744.27      2415138.61     13132715.19
      2415390.15     13132615.94
#Sta/Elev= 30
  4617.9   61.55  4649.6   59.68  4656.4   57.82  4661.4   58.39  4709.7   55.68
  4759.8      51  4779.8   50.85  4789.8   49.27  4824.6   48.02  4882.5   44.28
  4910.1   41.73  4980.2   40.54  4987.8   36.58  4997.2   35.59    5000   35.09
  5003.2   35.59  5010.2   40.47  5020.3   42.47  5040.3   44.41  5076.5   45.78
  5118.4   45.35  5221.7    46.8  5283.1   51.82  5293.8   52.03  5300.2    53.8
  5305.5   52.74  5329.9   52.43  5336.8   52.91  5359.7   57.01  5371.7   57.01
#Mann= 6 ,-1 , 0
  4617.9     .05       0  4882.5     .12       0  4997.2     .07       0
  5003.2     .12       0  5076.5     .05       0  5118.4      .1       0
Bank Sta=4997.2,5003.2
XS Rating Curve= 0 ,0
Exp/Cntr=0.3,0.1

Type RM Length L Ch R = 1 ,7607    ,228,228,228
BEGIN DESCRIPTION:
UNT032 IN BACR 16.0
END DESCRIPTION:
XS GIS Cut Line= 3
      2414716.02     13133154.92      2415256.68     13132968.43
      2415443.83     13132839.12
#Sta/Elev= 30
  4587.1   63.93  4641.8    61.5  4813.8   46.47  4877.2   42.58  4895.7   42.75
  4933.3   39.65  4959.1   39.85  4980.3   36.51  4990.4   33.05  4998.5   33.01
  5001.2   32.51  5004.5   33.01  5021.6   37.85  5027.4   38.73  5033.2   40.73
  5043.8   42.37  5052.8   42.54  5064.9   44.57    5084    44.3  5107.2   46.69
  5240.1   46.64  5269.7   47.44  5290.8   43.62  5300.1   43.67  5332.7   43.68
  5341.5   43.05  5354.8   44.03  5368.5   49.87  5377.3   55.43  5386.5   56.59
#Mann= 6 ,-1 , 0
  4587.1     .05       0  4877.2     .12       0  4998.5     .07       0
  5004.5     .12       0  5027.4     .05       0  5300.1      .1       0
Bank Sta=4998.5,5004.5
XS Rating Curve= 0 ,0
Exp/Cntr=0.3,0.1

Type RM Length L Ch R = 1 ,7379    ,303,303,303
BEGIN DESCRIPTION:
Mapping XS 53cf26aa
END DESCRIPTION:
XS GIS Cut Line= 3
       2414794.7     13133356.83      2415263.52     13133209.69
      2415523.98     13133066.69
#Sta/Elev= 30
  4610.4   63.73  4655.3   61.04  4686.9   61.04  4718.4   59.31  4725.4   57.79
  4730.6   58.21  4749.8    55.8  4763.1   55.37  4802.2   50.77  4822.9   46.84
  4842.8   45.13  4914.4   39.69  4980.4   37.36    4990   33.85  4995.2   35.06
  4998.4   32.88  5001.1   32.38  5004.4   32.88  5011.8   33.49  5022.3   36.81
  5027.6   40.67  5030.4   40.51  5196.6   40.64    5232   42.34    5251   41.82
  5288.3   42.04  5357.5   42.39  5380.3   48.85  5387.1   53.51  5398.9   55.59
#Mann= 9 ,-1 , 0
  4610.4     .05       0  4822.9     .08       0  4842.8     .05       0
  4914.4     .12       0  4998.4     .07       0  5004.4     .12       0
  5030.4     .05       0    5251     .08       0  5288.3     .05       0
Bank Sta=4998.4,5004.4
XS Rating Curve= 0 ,0
Exp/Cntr=0.3,0.1

Type RM Length L Ch R = 1 ,7076    ,346,346,346
BEGIN DESCRIPTION:
UNT032 IN BACR 15.0
END DESCRIPTION:
XS GIS Cut Line= 2
      2415149.14     13133569.78      2415454.52     13133447.63
#Sta/Elev= 30
  4888.5   54.48  4911.9   51.28  4919.3   47.97  4930.1   46.39  4936.1    42.9
  4941.5   42.15  4951.6   39.41  4960.3   37.87  4983.9   34.74    4987   30.22
  4989.7   29.72    4993   30.22  5005.4   30.46  5014.2   34.29  5019.6    36.1
    5034   36.71  5080.8   38.83  5091.6   38.79  5113.1   39.83  5121.9   40.77
  5151.5   42.37  5156.9   42.12    5167   43.92  5175.7      53  5181.1   55.69
  5188.5   55.78  5199.3   58.52  5205.4   58.74  5210.7   55.11  5217.4   58.94
#Mann= 4 ,-1 , 0
  4888.5     .05       0    4987     .04       0    4993     .05       0
    5034     .08       0
Bank Sta=4987,4993
XS Rating Curve= 0 ,0
Exp/Cntr=0.3,0.1

Type RM Length L Ch R = 1 ,6730    ,408,408,408
BEGIN DESCRIPTION:
UNT032 IN BACR 14.0
END DESCRIPTION:
XS GIS Cut Line= 3
      2415237.75     13133896.84      2415387.72     13133846.85
      2415487.73     13133796.85
#Sta/Elev= 30
  4858.8   53.66  4869.3   54.41  4879.8   53.34  4890.4   50.91  4900.9   49.35
  4911.5   43.66    4922   41.96  4932.6   38.06  4943.1   36.36  4953.6   35.23
  4974.7   33.63  4985.3   32.49  4992.8    29.6  4995.5    29.1  4998.8    29.6
  5006.3   29.76  5014.2    34.8  5025.3   34.75  5039.2   35.88  5046.4   37.17
  5053.2   38.18  5061.6   38.77    5070    41.6  5075.6   41.83    5084   43.37
  5092.3   46.25  5106.3   49.05  5114.7   51.99  5120.3   53.03  5128.7   53.62
#Mann= 4 ,-1 , 0
  4858.8     .05       0  4992.8     .04       0  4998.8     .05       0
  5046.4     .08       0
Bank Sta=4992.8,4998.8
XS Rating Curve= 0 ,0
Exp/Cntr=0.3,0.1

Type RM Length L Ch R = 1 ,6322    ,430,430,430
BEGIN DESCRIPTION:
UNT032 IN BACR 13.0
END DESCRIPTION:
XS GIS Cut Line= 3
      2415348.73     13134299.31      2415613.68     13134180.27
      2415655.91     13134095.81
#Sta/Elev= 30
  4871.2    54.3  4881.1   54.08    4888   51.54    4903   49.36  4911.1   45.73
  4916.6   45.25  4924.9   41.64  4939.8   38.66  4946.8   35.05  4962.9   33.51
  4968.8   31.87  4979.7   31.71  4991.6      26  4998.7   25.72  5001.4   25.22
  5004.7   25.72  5009.3   30.87  5014.7   29.59  5023.6   32.29  5035.9   33.92
  5112.9   37.55  5122.2   40.79    5136   43.34  5144.2   47.36  5153.7   50.71
  5161.7    52.6  5176.5   52.43  5182.1   54.81  5249.1   54.41  5256.1   53.18
#Mann= 4 ,-1 , 0
  4871.2     .05       0  4998.7     .04       0  5004.7     .08       0
  5035.9     .05       0
Bank Sta=4998.7,5004.7
XS Rating Curve= 0 ,0
Exp/Cntr=0.3,0.1

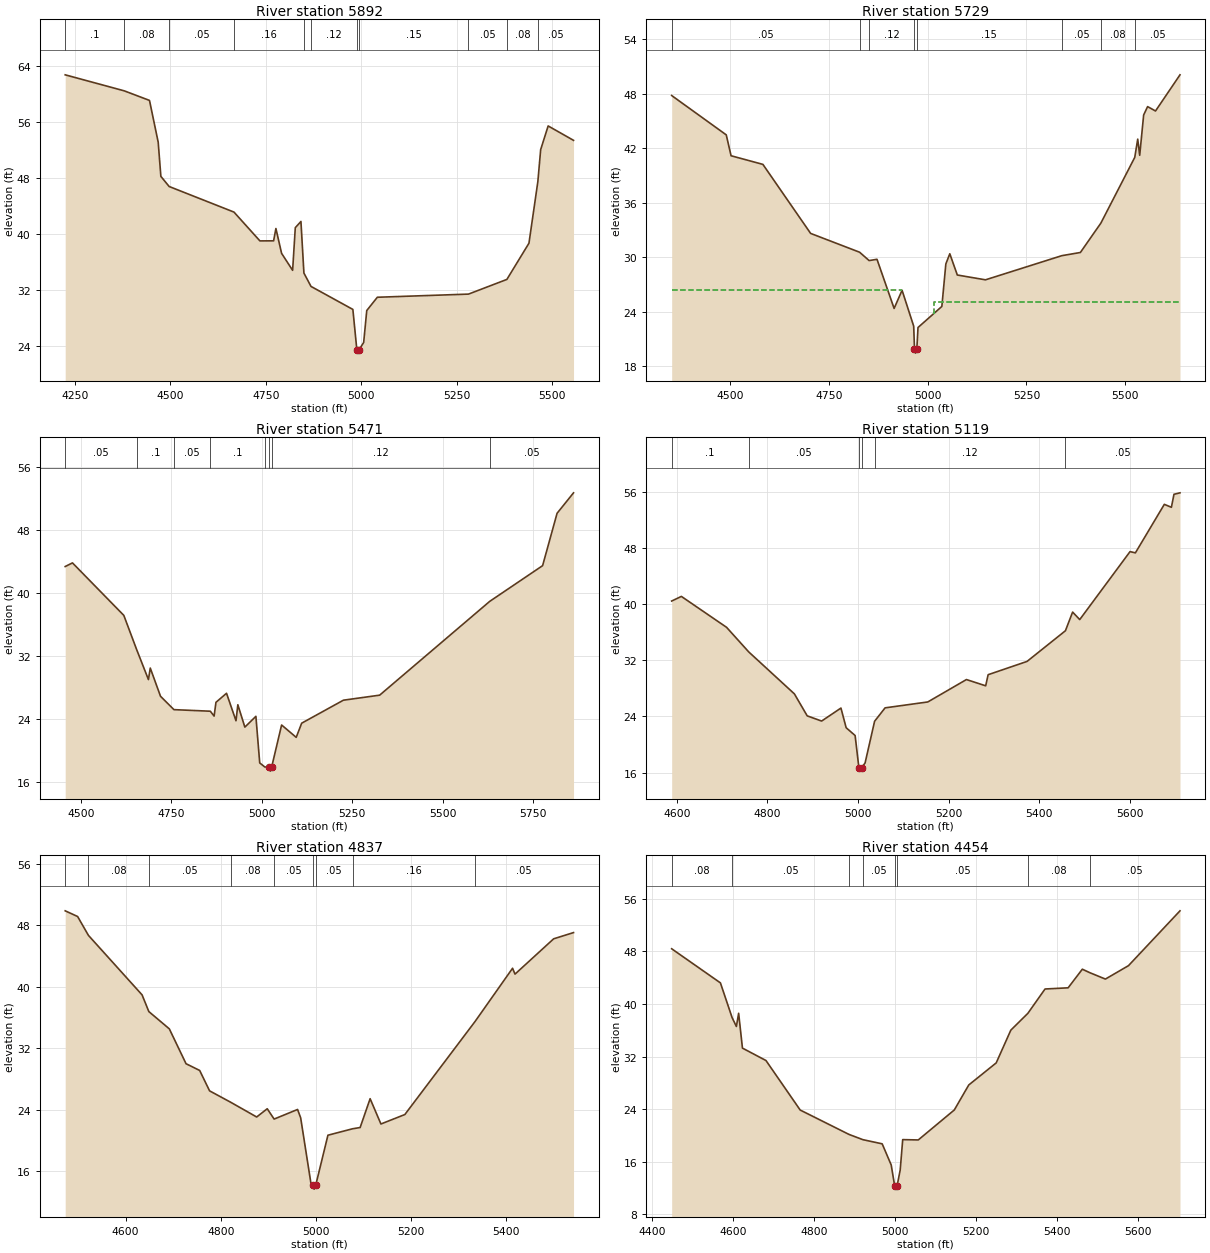
Type RM Length L Ch R = 1 ,5892    ,163,163,163
BEGIN DESCRIPTION:
Mapping XS 57076d1a
END DESCRIPTION:
XS GIS Cut Line= 3
        2415080.     13135297.55      2415548.41     13134617.97
      2415655.91     13134122.67
#Sta/Elev= 30
  4224.1   62.74  4378.8   60.45    4445   59.08  4467.8   53.11  4474.8   48.22
  4496.5   46.77  4666.4   43.11  4734.4   38.99  4770.3      39  4776.3   40.76
  4791.2   37.21  4820.1   34.78  4827.1   40.88  4841.9   41.77  4849.7   34.39
  4868.3   32.48    4978   29.19  4988.4   23.44  4991.1   22.94  4994.4   23.44
  5006.3   24.46  5014.4   29.03  5042.1   30.93    5281   31.38  5381.6   33.48
  5439.5   38.66  5462.8   47.47  5470.2   52.05  5489.8   55.43  5556.3   53.37
#Mann= 11 ,-1 , 0
  4224.1      .1       0  4378.8     .08       0  4496.5     .05       0
  4666.4     .16       0  4849.7     .05       0  4868.3     .12       0
  4988.4     .07       0  4994.4     .15       0    5281     .05       0
  5381.6     .08       0  5462.8     .05       0
Bank Sta=4988.4,4994.4
XS Rating Curve= 0 ,0
Exp/Cntr=0.3,0.1

Type RM Length L Ch R = 1 ,5729    ,258,258,258
BEGIN DESCRIPTION:
UNT032 IN BACR 12.0
END DESCRIPTION:
XS GIS Cut Line= 3
      2415587.91     13135376.27      2415664.29     13134654.07
      2415674.71     13134094.99
#Sta/Elev= 30
  4352.8    47.8  4490.8   43.47    4503   41.17  4583.5   40.22  4704.2   32.62
    4828   30.55  4852.1   29.63    4872   29.77  4915.3   24.36  4935.4   26.36
  4964.8   22.41  4966.8   19.94  4969.6   19.44  4972.8   19.94  4975.7   22.26
    5036   24.58  5046.1   29.26  5056.1   30.38  5075.1   28.04  5146.3   27.51
  5339.4   30.17  5386.3   30.52  5438.2   33.76  5523.8   40.99  5531.3      43
  5536.3   41.22  5546.3   45.66  5556.3   46.58  5576.3    46.1  5638.2   50.08
#Mann= 8 ,-1 , 0
  4352.8     .05       0    4828      .1       0  4852.1     .12       0
  4966.8     .07       0  4972.8     .15       0  5339.4     .05       0
  5438.2     .08       0  5523.8     .05       0
#XS Ineff= 2 , 0
       0 4935.42   26.37 5015.78       0   25.04
Permanent Ineff=
       T       T
Bank Sta=4966.8,4972.8
XS Rating Curve= 0 ,0
Exp/Cntr=0.3,0.1

Type RM Length L Ch R = 1 ,5471    ,352,352,352
BEGIN DESCRIPTION:
UNT032 IN BACR 11.0
END DESCRIPTION:
XS GIS Cut Line= 3
      2415744.16      13135386.7      2415855.27     13134726.99
      2415889.96     13133991.41
#Sta/Elev= 30
  4456.2   43.42  4476.3   43.88  4618.3   37.21  4653.5    32.9  4686.3   29.06
  4691.4   30.52  4719.7   26.94  4756.8   25.24  4857.4   25.04  4867.9   24.42
    4873   26.17  4902.2   27.32  4928.4   23.83  4933.5   25.86  4952.9   23.02
  4983.4   24.39    4994   18.47  5008.3   17.95  5020.9   17.93  5023.7   17.43
  5026.9   17.93  5054.5   23.29  5094.9   21.72    5110   23.52  5225.4   26.44
  5325.6   27.08  5630.1      39  5776.1   43.53  5816.1   50.18  5861.6   52.78
#Mann= 8 ,-1 , 0
  4456.2     .05       0  4653.5      .1       0  4756.8     .05       0
  4857.4      .1       0  5008.3     .12       0  5020.9     .07       0
  5026.9     .12       0  5630.1     .05       0
Bank Sta=5020.9,5026.9
XS Rating Curve= 0 ,0
Exp/Cntr=0.3,0.1

Type RM Length L Ch R = 1 ,5119    ,282,282,282
BEGIN DESCRIPTION:
Mapping XS 1616614e
END DESCRIPTION:
XS GIS Cut Line= 3
      2415774.98     13135424.23      2415997.63     13135255.33
      2416289.42      13134464.4
#Sta/Elev= 30
  4588.4   40.42  4609.8   41.08  4709.6   36.68  4758.5   33.18  4859.4    27.2
  4887.7   24.07  4919.5   23.33  4962.2   25.18  4973.7   22.38  4993.5   21.27
  5001.8    16.7  5004.6    16.2  5007.8    16.7  5015.5   17.36  5036.5    23.3
  5059.7   25.21    5154   26.05  5239.3   29.24  5281.8   28.35  5287.2   29.93
  5373.1   31.82  5457.9   36.19  5473.8   38.85  5489.5   37.78  5600.6   47.46
  5612.4   47.28  5676.3   54.19  5691.9   53.77  5697.6   55.62  5710.9   55.83
#Mann= 6 ,-1 , 0
  4588.4      .1       0  4758.5     .05       0  5001.8    .035       0
  5007.8     .05       0  5036.5     .12       0  5457.9     .05       0
Bank Sta=5001.8,5007.8
XS Rating Curve= 0 ,0
Exp/Cntr=0.3,0.1

Type RM Length L Ch R = 1 ,4837    ,383,383,383
BEGIN DESCRIPTION:
UNT032 IN BACR 10.0
END DESCRIPTION:
XS GIS Cut Line= 3
       2415890.1      13135746.8      2416277.91     13135278.36
      2416408.46     13134836.79
#Sta/Elev= 30
    4473   49.88  4499.1   49.14  4521.8   46.69  4634.6   38.95  4648.8   36.78
  4691.9   34.53    4727      30  4755.7   29.12  4776.5   26.47  4820.8   24.99
  4875.5   23.07  4897.7   24.14  4912.2    22.8  4961.5   24.05    4968   22.96
  4990.2    14.2  4993.6   14.19  4996.4   13.69  4999.6   14.19  5025.3    20.7
  5077.2   21.54    5093    21.7    5114   25.45  5136.7   22.16    5187   23.39
  5334.6   35.49  5413.4   42.41  5418.6   41.65  5499.8   46.24  5541.6   47.05
#Mann= 9 ,-1 , 0
    4473     .05       0  4521.8     .08       0  4648.8     .05       0
  4820.8     .08       0  4912.2     .05       0  4993.6     .04       0
  4999.6     .05       0  5077.2     .16       0  5334.6     .05       0
Bank Sta=4993.6,4999.6
XS Rating Curve= 0 ,0
Exp/Cntr=0.3,0.1

Type RM Length L Ch R = 1 ,4454    ,262,262,262
BEGIN DESCRIPTION:
UNT032 IN BACR 9.0
END DESCRIPTION:
XS GIS Cut Line= 3
      2415970.71     13135792.87      2416684.89     13135443.46
       2417032.5     13135141.69
#Sta/Elev= 30
  4448.4    48.4  4568.8   43.21  4597.6   37.94  4608.2   36.58  4613.8   38.59
  4623.2   33.29  4681.3    31.4  4765.8   23.87  4886.4   20.16  4920.8   19.36
  4968.3   18.73  4990.6   15.51  4999.1   12.34  5001.8   11.84  5005.1   12.34
  5012.8   14.75    5019   19.37  5057.4   19.32  5146.4   23.88  5182.1   27.68
  5249.9   31.04    5286   36.02  5328.1   38.58  5370.5   42.28  5427.5   42.46
  5462.6   45.29  5481.5   44.75  5519.6   43.79  5576.6   45.83  5703.8   54.17
#Mann= 8 ,-1 , 0
  4448.4     .08       0  4597.6     .05       0  4886.4     .08       0
  4920.8     .05       0  4999.1     .04       0  5005.1     .05       0
  5328.1     .08       0  5481.5     .05       0
Bank Sta=4999.1,5005.1
XS Rating Curve= 0 ,0
Exp/Cntr=0.3,0.1

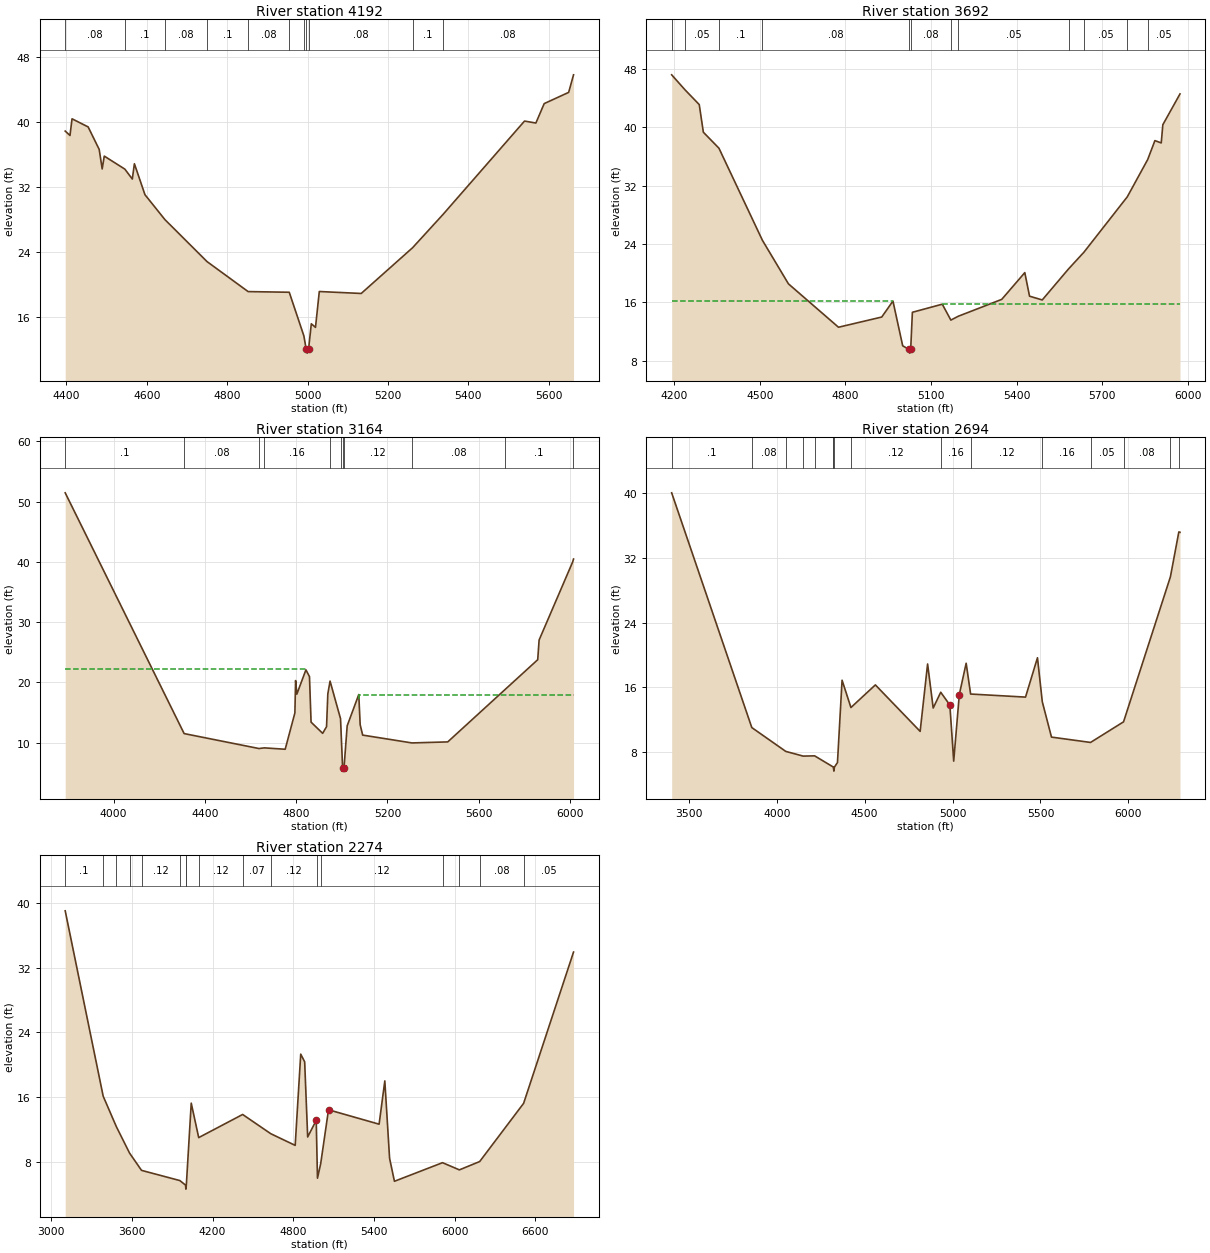
Type RM Length L Ch R = 1 ,4192    ,500,500,500
BEGIN DESCRIPTION:
UNT032 IN BACR 8.0
END DESCRIPTION:
XS GIS Cut Line= 2
      2415955.94     13135956.16      2417178.21     13135629.76
#Sta/Elev= 30
  4396.8    38.9  4408.7   38.36  4413.8   40.41  4453.9   39.41  4481.4   36.64
  4488.8   34.24    4494   35.82  4545.2   34.22  4563.8      33    4569   34.88
  4595.3   31.07  4645.1      28  4749.8   22.84  4852.1   19.15  4954.4   19.07
  4990.8    13.7  4996.5   12.08  4999.3   11.58  5002.5   12.08  5009.3   15.19
  5019.7   14.75  5029.2   19.16  5133.5   18.92  5261.4   24.55  5336.5   28.61
  5539.9   40.13  5568.2   39.89  5588.9   42.28  5649.8   43.66  5661.9   45.82
#Mann= 11 ,-1 , 0
  4396.8     .08       0  4545.2      .1       0  4645.1     .08       0
  4749.8      .1       0  4852.1     .08       0  4954.4      .1       0
  4990.8     .08       0  4996.5     .07       0  5002.5     .08       0
  5261.4      .1       0  5336.5     .08       0
Bank Sta=4996.5,5002.5
XS Rating Curve= 0 ,0
Exp/Cntr=0.3,0.1

Type RM Length L Ch R = 1 ,3692    ,528,528,528
BEGIN DESCRIPTION:
UNT032 IN BACR 7.0
END DESCRIPTION:
XS GIS Cut Line= 3
      2415924.72     13136491.62      2416769.36     13136253.59
      2417574.17     13135843.52
#Sta/Elev= 30
  4191.5    47.2  4238.8   45.12  4288.1   43.12  4302.5   39.33  4357.1   37.14
  4509.4   24.51  4600.6   18.54  4775.9   12.59  4927.5   13.99  4966.7   16.18
  5000.8   10.05  5022.8    9.54  5025.5    9.04  5028.8    9.54  5034.8   14.64
  5139.5   15.75  5169.6   13.57  5195.8    14.1  5347.8   16.41  5428.6   20.08
  5445.2   16.85  5489.7   16.33  5581.7   20.58  5635.6   22.87  5787.8   30.48
  5859.1   35.58  5884.4   38.18  5906.6   37.86  5912.2   40.36  5972.3   44.58
#Mann= 12 ,-1 , 0
  4191.5      .1       0  4238.8     .05       0  4357.1      .1       0
  4509.4     .08       0  5022.8     .07       0  5028.8     .08       0
  5169.6      .1       0  5195.8     .05       0  5581.7      .1       0
  5635.6     .05       0  5787.8     .08       0  5859.1     .05       0
#XS Ineff= 2 , 0
       0 4965.91   16.21 5140.91       0   15.83
Permanent Ineff=
       T       T
Bank Sta=5022.8,5028.8
XS Rating Curve= 0 ,0
Exp/Cntr=0.3,0.1

Type RM Length L Ch R = 1 ,3164    ,467,467,467
BEGIN DESCRIPTION:
UNT032 IN BACR 6.0
END DESCRIPTION:
XS GIS Cut Line= 4
      2415814.97     13136746.43       2416820.2     13136793.31
      2417122.28     13136647.47      2417641.77     13135930.57
#Sta/Elev= 30
    3788   51.44  4309.1   11.48  4636.9       9    4660    9.11  4751.8    8.88
  4794.3   14.91  4797.4   20.28  4802.9   18.03  4842.6   22.06  4858.2   20.94
  4865.2   13.38    4916   11.52    4933   12.63  4938.6   18.07  4948.4   20.19
  4994.3   13.95  5003.4    5.75  5006.1    5.25  5009.4    5.75  5023.4   12.77
  5074.2   17.96  5080.3   12.95  5091.3   11.23  5307.2    9.93    5464    10.1
  5714.4   18.77  5858.2   23.74  5864.3   27.01    6011   39.94  6015.1   40.45
#Mann= 11 ,-1 , 0
    3788      .1       0  4309.1     .08       0  4636.9     .05       0
    4660     .16       0  4948.4     .05       0  4994.3     .12       0
  5003.4     .07       0  5009.4     .12       0  5307.2     .08       0
  5714.4      .1       0    6011     .05       0
#XS Ineff= 2 , 0
       0 4843.18   22.15    5075       0   17.87
Permanent Ineff=
       T       T
Bank Sta=5003.4,5009.4
XS Rating Curve= 0 ,0
Exp/Cntr=0.3,0.1

Type RM Length L Ch R = 1 ,2694    ,420,420,420
BEGIN DESCRIPTION:
Mapping XS e05eb23e
END DESCRIPTION:
XS GIS Cut Line= 4
      2415714.37     13137102.49      2416790.78     13137258.74
      2417402.76     13137041.73      2417997.38     13136052.15
#Sta/Elev= 30
  3402.1   40.05  3857.9      11  4051.3    8.05  4150.1    7.47  4215.4     7.5
    4322    6.11  4324.8    5.61    4328    6.11  4345.2    6.67  4371.4   16.86
  4421.8   13.48  4560.8   16.28  4815.5   10.53  4857.9   18.87  4889.7   13.42
  4932.6   15.37  4984.5   13.79  5006.4    6.85  5038.3   15.09  5077.2   18.96
  5102.6   15.15  5414.9   14.77  5482.9   19.64  5510.3    14.2  5562.6    9.82
  5784.9    9.16  5972.5   11.71  6239.1   29.66    6287   35.21  6293.6   35.17
#Mann= 16 ,-1 , 0
  3402.1      .1       0  3857.9     .08       0  4051.3     .05       0
  4150.1     .16       0  4215.4     .05       0  4318.6     .16       0
    4322     .07       0    4328     .16       0  4421.8     .12       0
  4932.6     .16       0  5102.6     .12       0  5510.3     .16       0
  5784.9     .05       0  5972.5     .08       0  6239.1     .05       0
    6287      .1       0
Bank Sta=4984.5,5038.3
XS Rating Curve= 0 ,0
Exp/Cntr=0.3,0.1

Type RM Length L Ch R = 1 ,2274    ,0,0,0
BEGIN DESCRIPTION:
UNT032 IN BACR 1.0
END DESCRIPTION:
XS GIS Cut Line= 5
      2415671.03     13137575.59      2416686.62     13137636.35
       2417697.9     13137371.59      2418162.31      13136985.3
      2418626.22     13135970.77
#Sta/Elev= 30
  3103.1   39.03  3385.7   16.11  3483.8   12.34  3581.9    9.08    3671    6.94
  3955.9    5.68  3998.4    5.12  4001.1    4.62  4004.4    5.12  4040.9   15.25
  4096.5   10.99  4423.4   13.85  4632.9   11.47  4814.4   10.03  4855.6   21.31
  4884.9   20.36  4907.3   11.07  4970.9   13.12  4980.2    5.97  5004.2    7.77
  5062.3   14.43  5438.8   12.65  5481.3      18  5516.8    8.43  5552.9    5.59
  5910.7    7.89  6036.1       7  6187.2    8.03  6514.2   15.23  6885.5   33.93
#Mann= 17 ,-1 , 0
  3103.1      .1       0  3385.7     .08       0  3483.8     .05       0
  3581.9     .16       0    3671     .12       0  3955.9     .07       0
  3998.4     .07       0  4004.4     .07       0  4096.5     .12       0
  4423.4     .07       0  4632.9     .12       0  4980.2     .16       0
  5004.2     .12       0  5910.7     .16       0  6036.1     .05       0
  6187.2     .08       0  6514.2     .05       0
Bank Sta=4970.9,5062.3
XS Rating Curve= 0 ,0
Exp/Cntr=0.3,0.1

Chan Stop Cuts=-1
Use User Specified Reach Order=0
Composite Channel Slope=5