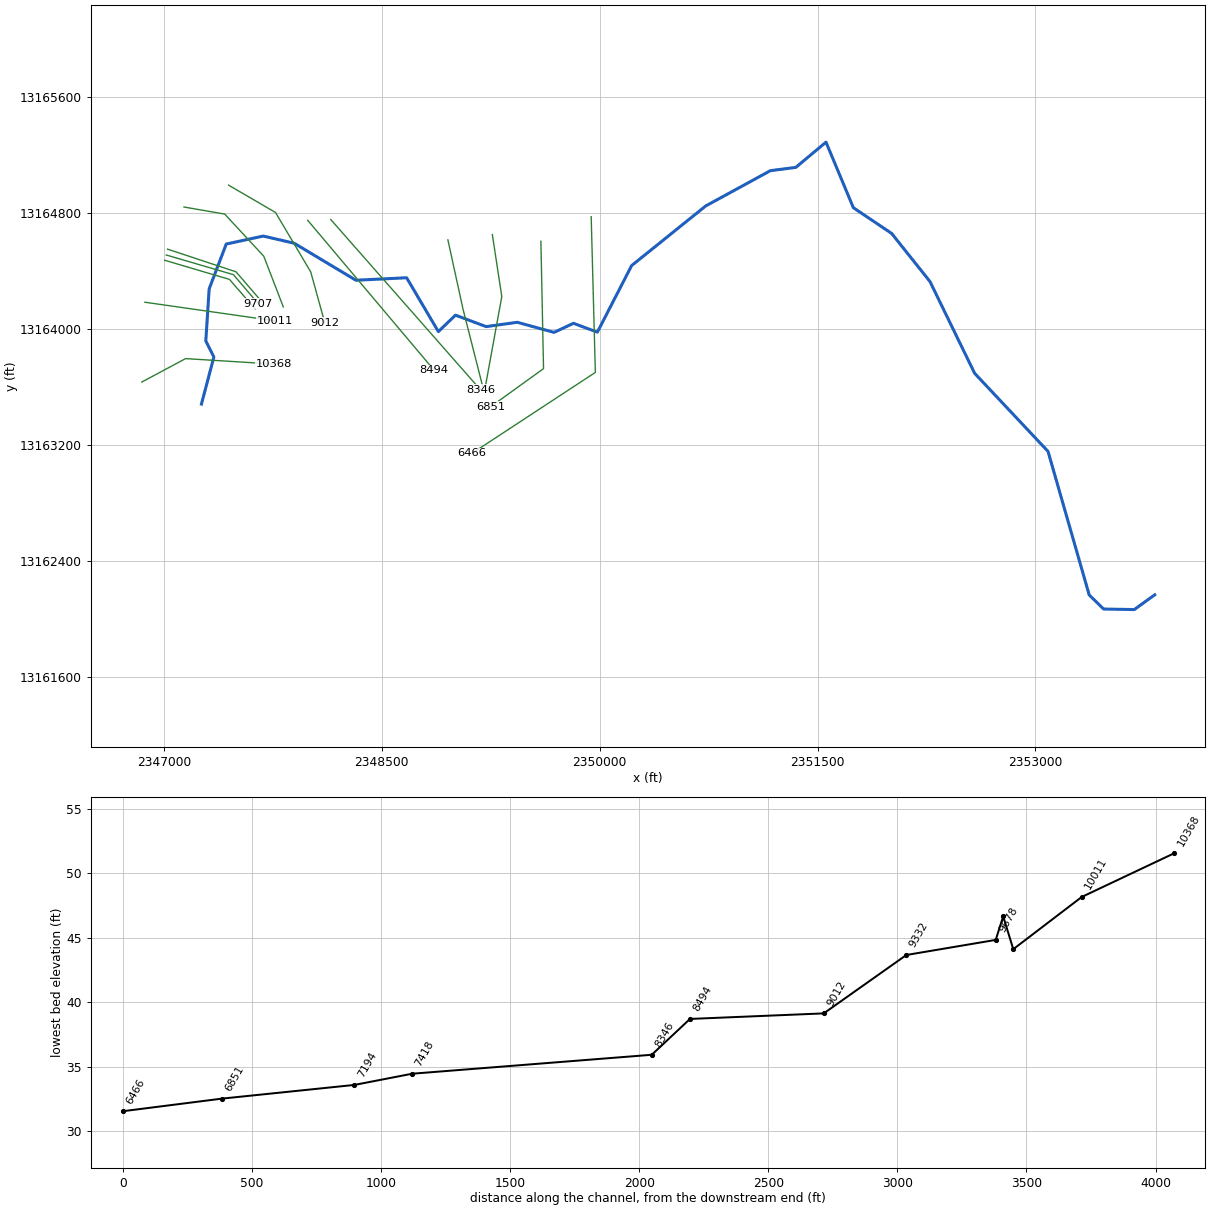
--- UNT033 IN BACR.prj (project) ---

Proj Title=UNT033 IN BACR Base Level Engineering
Current Plan=p01
Default Exp/Contr=0.3,0.1
English Units
Geom File=g01
Flow File=f01
Plan File=p01
Y Axis Title=Elevation
X Axis Title(PF)=Main Channel Distance
X Axis Title(XS)=Station
BEGIN DESCRIPTION:
UNT033 IN BACR
END DESCRIPTION:
DSS Export Rating Curves= 0
DSS Export Rating Curve Sorted= 0
DSS Export Volume Flow Curves= 0
DXF OffsetX= 0
DXF OffsetY= 0
DXF ScaleX= 1
DXF ScaleY= 10

--- UNT033 IN BACR.p01 (plan) ---

Plan Title=Multiple Run
Short Identifier=Multiple
Geom File=g01
Flow File=f01
Subcritical Flow
K Sum by GR= 0
Std Step Tol= 0.01
Critical Tol= 0.01
Num of Std Step Trials= 20
Max Error Tol= 0.3
Flow Tol Ratio= 0.001
Split Flow NTrial= 30
Split Flow Tol= 0.02
Split Flow Ratio= 0.02
Log Output Level= 0
Friction Slope Method= 1
Unsteady Friction Slope Method= 2
Unsteady Bridges Friction Slope Method= 1
Parabolic Critical Depth
Global Vel Dist=  1 , 1 , 1
Global Log Level= 0
CheckData=True
Encroach Param= -1, 0, 0, 0
BEGIN DESCRIPTION:
Multiple Run
END DESCRIPTION:

--- UNT033 IN BACR.f01 (steady flow) ---

Flow Title=Multiple
Number of Profiles=7
Profile Names=10-year,25-year,50-year,1pct_min,100-year,1pct_plu,500-year
River Rch & RM= UNT033 IN BACR,Reach-1,10368
     537     699     823     562     953    1343    1264
River Rch & RM= UNT033 IN BACR,Reach-1,8346
     784    1019    1201     820    1389    1959    1843
Boundary for River Rch & Prof#=UNT033 IN BACR,Reach-1,1
Up Type=0
Dn Type=3
Dn Slope=0.005
Boundary for River Rch & Prof#=UNT033 IN BACR,Reach-1,2
Up Type=0
Dn Type=3
Dn Slope=0.005
Boundary for River Rch & Prof#=UNT033 IN BACR,Reach-1,3
Up Type=0
Dn Type=3
Dn Slope=0.005
Boundary for River Rch & Prof#=UNT033 IN BACR,Reach-1,4
Up Type=0
Dn Type=3
Dn Slope=0.005
Boundary for River Rch & Prof#=UNT033 IN BACR,Reach-1,5
Up Type=0
Dn Type=3
Dn Slope=0.005
Boundary for River Rch & Prof#=UNT033 IN BACR,Reach-1,6
Up Type=0
Dn Type=3
Dn Slope=0.005
Boundary for River Rch & Prof#=UNT033 IN BACR,Reach-1,7
Up Type=0
Dn Type=3
Dn Slope=0.005

--- UNT033 IN BACR.g01 (geometry) ---

Geom Title=Existing Conditions
Program Version=4.10

River Reach=UNT033 IN BACR  ,Reach-1
Reach XY= 30
      2347257.72     13163481.85      2347343.25     13163806.23
      2347287.76     13163916.88      2347310.91     13164275.85
      2347428.43     13164584.69       2347683.3     13164639.56
      2347895.73     13164590.34      2348321.46     13164335.19
      2348670.57     13164352.33      2348888.94     13163981.29
      2349006.76     13164094.73      2349217.85     13164015.69
      2349432.06     13164045.43      2349685.53     13163975.99
      2349819.21     13164038.49      2349983.72     13163977.42
      2350219.62     13164436.08      2350729.17     13164846.67
      2351174.89     13165090.16      2351350.21     13165112.74
      2351557.93     13165286.79      2351746.18     13164835.09
      2352010.07     13164657.58      2352273.96     13164325.98
      2352581.25     13163694.04      2353086.64      13163155.7
      2353370.07     13162166.89      2353469.21     13162069.71
      2353680.25     13162066.02      2353821.53     13162167.61

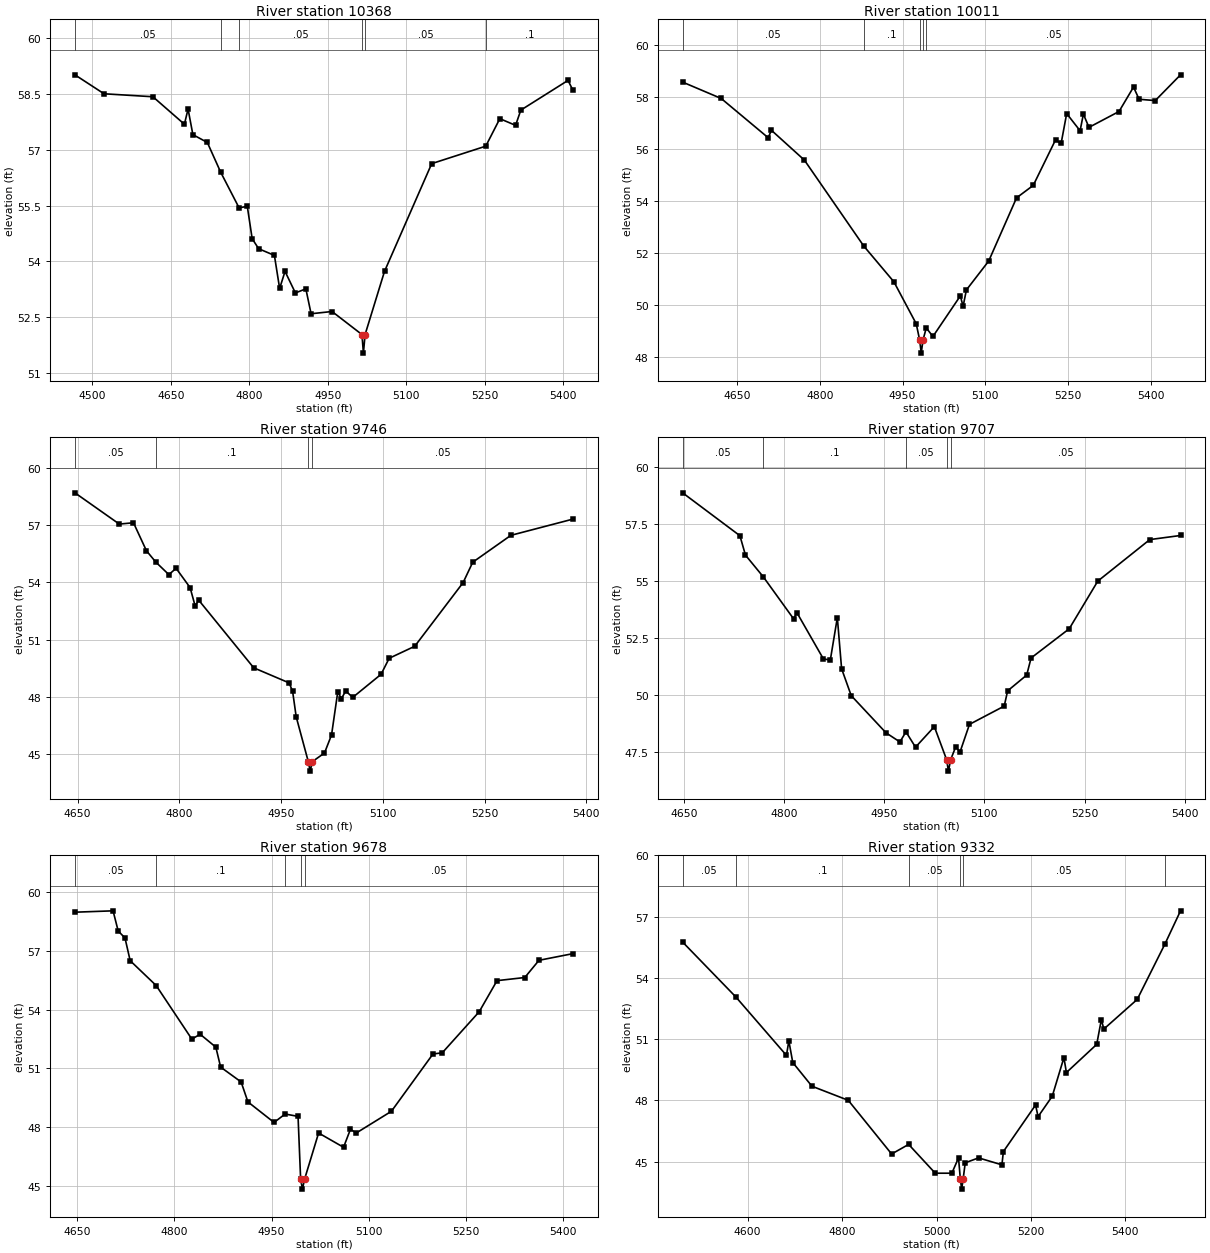
Type RM Length L Ch R = 1 ,10368   ,357,357,357
BEGIN DESCRIPTION:
UNT033 IN BACR 12.0
END DESCRIPTION:
XS GIS Cut Line= 3
      2346847.16     13163633.73      2347148.64     13163795.24
      2347756.95     13163757.56
#Sta/Elev= 30
  4466.6   59.02  4522.2   58.51  4615.6   58.43  4675.8   57.69  4682.8    58.1
    4692   57.41  4719.6    57.2  4745.1    56.4  4780.3   55.44    4796   55.48
  4805.3   54.61  4817.7   54.34  4847.8   54.16  4857.8   53.27  4868.1   53.73
  4887.9   53.15  4907.9   53.26  4917.9   52.59    4958   52.65  5015.1   52.03
  5017.9   51.53  5021.1   52.03  5058.2   53.73  5148.4   56.63  5251.7    57.1
  5278.6   57.84  5308.7   57.66  5318.7   58.07  5408.9   58.87  5418.1   58.61
#Mann= 6 ,-1 , 0
  4466.6     .05       0  4745.1      .1       0  4780.3     .05       0
  5015.1     .03       0  5021.1     .05       0  5251.7      .1       0
Bank Sta=5015.1,5021.1
XS Rating Curve= 0 ,0
Exp/Cntr=0.3,0.1

Type RM Length L Ch R = 1 ,10011   ,265,265,265
BEGIN DESCRIPTION:
UNT033 IN BACR 11.0
END DESCRIPTION:
XS GIS Cut Line= 2
      2346868.45     13164183.73      2347762.06     13164055.94
#Sta/Elev= 30
  4551.3   58.57  4621.3   57.94  4706.5   56.43  4712.2   56.72  4772.1   55.57
  4879.6   52.27  4934.4   50.89  4974.8   49.28  4981.1   48.65  4983.9   48.15
  4987.1   48.65    4993   49.12  5005.1   48.79  5054.8   50.35  5059.8   49.95
  5065.8   50.58  5106.2   51.69  5156.7   54.12    5187    54.6  5227.4   56.35
  5237.5   56.21  5247.6   57.36  5271.9    56.7  5277.9   57.34    5288   56.83
  5342.5   57.44  5368.8   58.38  5378.9   57.91  5408.2   57.86    5454   58.85
#Mann= 5 ,-1 , 0
  4551.3     .05       0  4879.6      .1       0  4981.1     .03       0
  4987.1      .1       0    4993     .05       0
Bank Sta=4981.1,4987.1
XS Rating Curve= 0 ,0
Exp/Cntr=0.3,0.1

Type RM Length L Ch R = 1 ,9746    ,39,39,39
BEGIN DESCRIPTION:
Mapping XS ea7529e7
END DESCRIPTION:
XS GIS Cut Line= 3
      2347004.98      13164472.7      2347450.26      13164341.2
      2347627.36     13164138.05
#Sta/Elev= 30
  4646.2    58.7  4711.6   57.06  4732.5   57.13  4751.6   55.66  4765.3   55.07
  4784.6   54.41  4795.3   54.74  4815.9   53.73  4823.4   52.76  4828.6   53.07
  4909.7   49.52  4961.8   48.73    4967   48.29  4972.3   46.95  4990.1    44.6
  4992.9    44.1  4996.1    44.6    5014   45.05  5024.4      46  5033.6   48.27
  5038.8    47.9  5045.3    48.3  5055.7   47.97  5097.4   49.18  5109.3   50.02
    5147   50.65  5218.3   53.99  5232.5   55.06  5288.7   56.47    5380   57.32
#Mann= 4 ,-1 , 0
  4646.2     .05       0  4765.3      .1       0  4990.1     .03       0
  4996.1     .05       0
Bank Sta=4990.1,4996.1
XS Rating Curve= 0 ,0
Exp/Cntr=0.3,0.1

Type RM Length L Ch R = 1 ,9707    ,29,29,29
BEGIN DESCRIPTION:
UNT033 IN BACR 10.0
END DESCRIPTION:
XS GIS Cut Line= 3
       2347015.4     13164509.16       2347477.6     13164373.75
      2347649.46     13164173.25
#Sta/Elev= 30
    4648   58.85  4733.8   56.97  4742.1   56.12    4769   55.16  4814.1   53.33
  4819.3   53.59  4858.8   51.57  4869.2   51.52  4879.7   53.38  4886.1   51.14
  4900.5   49.96  4952.6   48.33  4973.4   47.93  4982.5   48.37  4996.8    47.7
    5025    48.6  5043.4   47.15  5046.1   46.65  5049.4   47.15  5056.8    47.7
  5063.6    47.5  5077.6    48.7  5129.6    49.5  5134.8   50.17  5163.3   50.86
  5169.9   51.61    5227   52.89  5269.8   54.98  5347.7    56.8  5393.7   56.98
#Mann= 5 ,-1 , 0
    4648     .05       0    4769      .1       0  4982.5     .05       0
  5043.4     .03       0  5049.4     .05       0
Bank Sta=5043.4,5049.4
XS Rating Curve= 0 ,0
Exp/Cntr=0.3,0.1

Type RM Length L Ch R = 1 ,9678    ,346,346,346
BEGIN DESCRIPTION:
Mapping XS 2897e653
END DESCRIPTION:
XS GIS Cut Line= 3
      2347024.43     13164549.55      2347495.83     13164393.28
       2347672.8     13164187.68
#Sta/Elev= 30
  4646.7   58.98  4705.5   59.05  4713.4   58.02  4723.9   57.66  4731.9    56.5
    4772   55.23    4827   52.49  4839.8   52.74    4864   52.08  4871.4   51.06
    4903    50.3  4913.5   49.28  4953.8   48.23  4970.9   48.66  4990.8   48.54
  4994.8   45.32  4997.6   44.82  5000.8   45.32  5022.5   47.69    5061   46.96
  5071.6   47.88  5080.6   47.69  5134.8    48.8  5198.9   51.73  5213.2   51.79
  5270.2   53.89  5297.7   55.48  5340.5   55.64  5362.4   56.52  5414.6   56.86
#Mann= 5 ,-1 , 0
  4646.7     .05       0    4772      .1       0  4970.9     .05       0
  4994.8     .03       0  5000.8     .05       0
Bank Sta=4994.8,5000.8
XS Rating Curve= 0 ,0
Exp/Cntr=0.3,0.1

Type RM Length L Ch R = 1 ,9332    ,320,320,320
BEGIN DESCRIPTION:
UNT033 IN BACR 9.0
END DESCRIPTION:
XS GIS Cut Line= 4
      2347137.83     13164839.67      2347417.82     13164791.21
        2347687.     13164500.49      2347821.35      13164151.2
#Sta/Elev= 30
  4462.2   55.75    4575   53.06  4682.1    50.2  4687.2   50.91  4695.5   49.85
  4736.1   48.69    4813      48  4904.9   45.37  4940.9   45.84  4997.3   44.43
  5032.4   44.43  5046.6   45.18  5050.4   44.15  5053.2   43.65  5056.4   44.15
  5060.8   44.94  5089.1   45.18  5138.5   44.84  5141.6   45.49  5209.8   47.77
  5215.1    47.2  5245.1    48.2  5269.8   50.09  5275.1   49.36  5339.3   50.74
  5349.1   51.95  5354.4   51.49    5425   52.94  5483.9   55.66  5516.8   57.28
#Mann= 6 ,-1 , 0
  4462.2     .05       0    4575      .1       0  4940.9     .05       0
  5050.4     .03       0  5056.4     .05       0  5483.9      .1       0
Bank Sta=5050.4,5056.4
XS Rating Curve= 0 ,0
Exp/Cntr=0.3,0.1

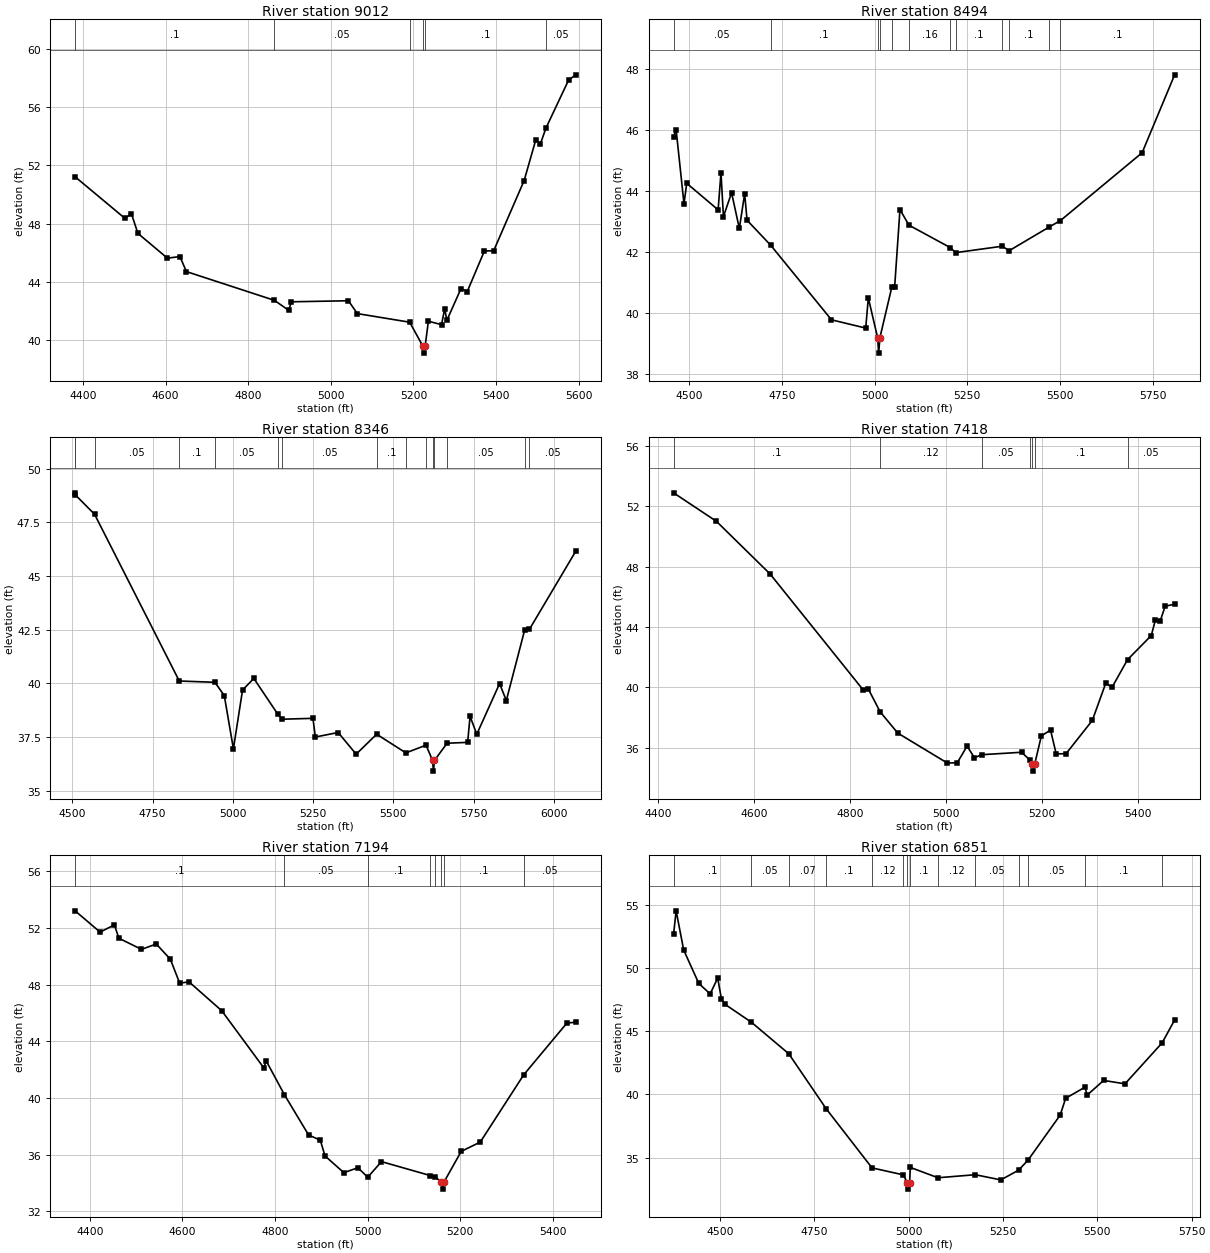
Type RM Length L Ch R = 1 ,9012    ,518,518,518
BEGIN DESCRIPTION:
Mapping XS 226ed356
END DESCRIPTION:
XS GIS Cut Line= 4
      2347444.75      13164990.4      2347767.76     13164801.98
      2348010.02     13164392.82      2348106.94     13164042.84
#Sta/Elev= 30
  4381.2   51.21  4501.8   48.36  4517.5   48.68  4533.2   47.33  4604.6   45.63
  4634.9   45.74  4650.6   44.71  4863.4   42.74  4898.5   42.05  4904.3   42.64
  5042.7   42.71  5064.2   41.83    5191   41.24  5222.4   39.62  5225.1   39.12
  5228.4   39.62  5236.2   41.31    5268   41.07  5275.7   42.17  5280.9   41.37
  5315.2   43.55  5330.2   43.34  5371.7   46.12  5394.2   46.14  5467.9   50.95
  5496.2   53.75  5507.4   53.47  5520.4   54.53    5576   57.87  5593.8    58.2
#Mann= 6 ,-1 , 0
  4381.2      .1       0  4863.4     .05       0    5191      .1       0
  5222.4     .03       0  5228.4      .1       0  5520.4     .05       0
Bank Sta=5222.4,5228.4
XS Rating Curve= 0 ,0
Exp/Cntr=0.3,0.1

Type RM Length L Ch R = 1 ,8494    ,148,148,148
BEGIN DESCRIPTION:
UNT033 IN BACR 8.0
END DESCRIPTION:
XS GIS Cut Line= 2
      2347989.29     13164748.36      2348859.52     13163715.36
#Sta/Elev= 30
    4458   45.78  4464.9      46  4486.1   43.58  4493.5   44.25  4578.1   43.38
  4585.8    44.6  4592.4   43.16  4614.4   43.94  4635.3   42.77  4649.6   43.91
  4656.1   43.04    4720   42.22  4883.7   39.78    4976   39.51    4983    40.5
  5008.1   39.19  5010.9   38.69  5014.1   39.19  5046.7   40.87    5054   40.86
  5068.3   43.39  5092.4   42.88  5204.5   42.14  5218.5   41.98  5344.6   42.19
  5362.2   42.04  5470.8   42.82    5501   43.03  5721.1   45.25  5808.7    47.8
#Mann= 12 ,-1 , 0
    4458     .05       0    4720      .1       0  5008.1     .07       0
  5014.1      .1       0  5046.7     .05       0  5092.4     .16       0
  5204.5     .05       0  5218.5      .1       0  5344.6     .16       0
  5362.2      .1       0  5470.8     .16       0    5501      .1       0
Bank Sta=5008.1,5014.1
XS Rating Curve= 0 ,0
Exp/Cntr=0.3,0.1

Type RM Length L Ch R = 1 ,8346    ,928,928,928
BEGIN DESCRIPTION:
UNT033 IN BACR 7.0
END DESCRIPTION:
XS GIS Cut Line= 2
      2348148.18     13164753.52      2349178.56      13163580.9
#Sta/Elev= 30
  4508.4   48.88  4509.4   48.78  4569.1   47.88    4833   40.11    4944   40.05
  4973.2   39.43  5001.6   36.95  5030.1   39.69  5065.2   40.23  5140.5   38.55
  5154.2   38.33  5249.4   38.37  5256.9    37.5    5328   37.71    5384    36.7
  5447.9   37.63    5539   36.76  5601.7   37.12    5622   36.41  5624.8   35.91
    5628   36.41  5667.3   37.21  5731.3   37.25  5738.9   38.46  5759.8   37.63
  5830.9   39.99  5851.8    39.2  5909.2    42.5  5923.9   42.52  6069.4   46.19
#Mann= 15 ,-1 , 0
  4508.4     .05       0  4509.4      .1       0  4569.1     .05       0
    4833      .1       0    4944     .05       0  5140.5      .1       0
  5154.2     .05       0  5447.9      .1       0    5539     .05       0
  5601.7      .1       0    5622     .04       0    5628      .1       0
  5667.3     .05       0  5909.2      .1       0  5923.9     .05       0
Bank Sta=5622,5628
XS Rating Curve= 0 ,0
Exp/Cntr=0.3,0.1

Type RM Length L Ch R = 1 ,7418    ,224,224,224
BEGIN DESCRIPTION:
UNT033 IN BACR 6.0
END DESCRIPTION:
XS GIS Cut Line= 3
       2348954.6     13164613.33      2349058.76     13164135.91
      2349195.47     13163597.75
#Sta/Elev= 30
  4432.2   52.89  4521.5      51  4633.3   47.51  4827.8    39.8    4838   39.88
  4862.6   38.37  4899.4   36.96  5002.4   34.98  5023.2   34.99  5043.7    36.1
    5059   35.33  5074.3   35.53  5157.2   35.69  5175.5   35.15  5178.8   34.94
  5181.5   34.44  5184.8   34.94  5198.5   36.78  5217.6   37.16  5229.4   35.58
    5250    35.6  5304.6    37.8  5332.6   40.27  5345.6   39.99    5378   41.83
  5427.5   43.43  5435.8   44.44  5446.1    44.4  5456.4   45.37  5476.1   45.51
#Mann= 7 ,-1 , 0
  4432.2      .1       0  4862.6     .12       0  5074.3     .05       0
  5175.5      .1       0  5178.8     .07       0  5184.8      .1       0
    5378     .05       0
Bank Sta=5178.8,5184.8
XS Rating Curve= 0 ,0
Exp/Cntr=0.3,0.1

Type RM Length L Ch R = 1 ,7194    ,512,512,512
BEGIN DESCRIPTION:
UNT033 IN BACR 5.0
END DESCRIPTION:
XS GIS Cut Line= 3
      2349260.58     13164650.28      2349325.69     13164222.71
      2349208.94     13163582.97
#Sta/Elev= 30
  4368.1    53.2  4422.1    51.7  4453.1   52.21  4462.6   51.27  4511.6   50.48
  4543.5   50.86  4573.9   49.79  4594.1    48.1  4614.3   48.19  4685.1   46.15
    4776   42.12    4781   42.62  4820.6   40.22  4872.7   37.39    4898   37.02
  4908.2   35.91  4948.9   34.73  4979.3   35.08  5000.5   34.41  5030.2   35.51
  5135.4   34.53  5145.7   34.45  5159.3   34.07  5162.1   33.57  5165.3   34.07
  5202.5   36.23  5243.7   36.89  5337.5   41.63  5430.8   45.28  5450.9   45.35
#Mann= 8 ,-1 , 0
  4368.1      .1       0  4820.6     .05       0  5000.5      .1       0
  5135.4     .12       0  5145.7      .1       0  5159.3     .04       0
  5165.3      .1       0  5337.5     .05       0
Bank Sta=5159.3,5165.3
XS Rating Curve= 0 ,0
Exp/Cntr=0.3,0.1

Type RM Length L Ch R = 1 ,6851    ,385,385,385
BEGIN DESCRIPTION:
UNT033 IN BACR 5.0
END DESCRIPTION:
XS GIS Cut Line= 3
      2349594.85     13164603.69      2349613.08     13163726.14
       2349248.5     13163463.12
#Sta/Elev= 30
  4377.6   52.67  4384.4   54.53  4404.4   51.43  4444.5   48.78  4474.5   47.96
  4494.5   49.21  4504.5   47.53  4514.5   47.12    4584   45.71  4682.8   43.22
  4781.6   38.88  4903.3   34.19    4986   33.64    4997   33.01  4999.8   32.51
    5003   33.01  5004.6   34.23    5078   33.41  5176.8   33.65  5244.6   33.24
  5291.5   34.01  5316.2   34.79  5401.6   38.36  5416.3    39.7  5467.7   40.58
  5472.8   39.94  5516.9   41.11  5573.4   40.84  5671.7   44.08  5704.9   45.89
#Mann= 14 ,-1 , 0
  4377.6      .1       0    4584     .05       0  4682.8     .07       0
  4781.6      .1       0  4903.3     .12       0    4986      .1       0
    4997     .07       0    5003      .1       0    5078     .12       0
  5176.8     .05       0  5291.5     .12       0  5316.2     .05       0
  5467.7      .1       0  5671.7     .05       0
Bank Sta=4997,5003
XS Rating Curve= 0 ,0
Exp/Cntr=0.3,0.1

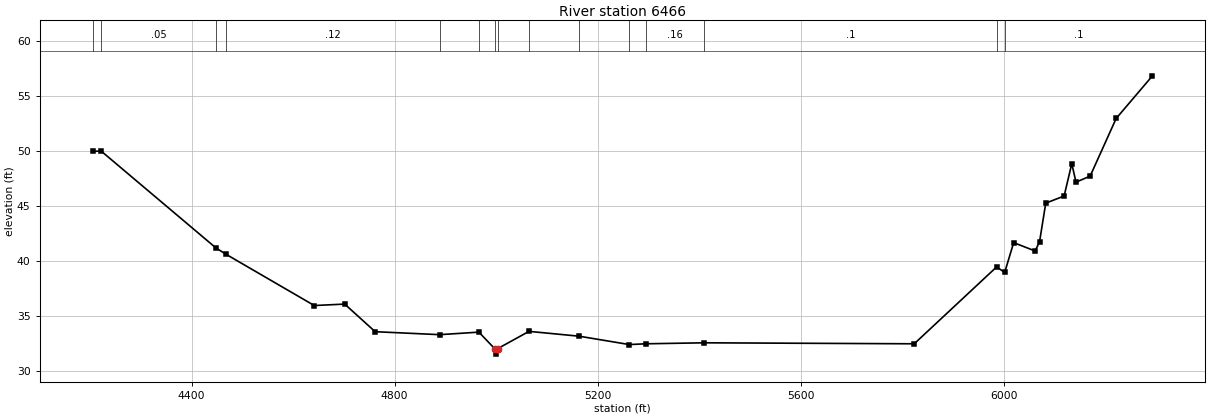
Type RM Length L Ch R = 1 ,6466    ,0,0,0
BEGIN DESCRIPTION:
UNT033 IN BACR 1.0
END DESCRIPTION:
XS GIS Cut Line= 3
       2349941.2     13164773.05      2349969.85     13163700.09
      2349121.79     13163143.39
#Sta/Elev= 30
  4205.2   49.98  4221.9   49.99  4447.8   41.19  4467.4   40.62  4641.6   35.95
  4701.6   36.08  4761.6   33.57  4888.6    33.3  4965.9   33.53    4997   32.03
  4999.8   31.53    5003   32.03  5064.7    33.6  5163.5   33.16  5262.3    32.4
  5294.9   32.47  5410.1   32.56  5823.7   32.47    5986   39.46  6001.9   38.96
  6019.6   41.67  6061.8   40.91  6070.6   41.75  6082.8   45.26    6119   45.91
  6134.1   48.85  6142.4   47.17  6170.3   47.72  6221.5   52.96    6293   56.84
#Mann= 15 ,-1 , 0
  4205.2      .1       0  4221.9     .05       0  4447.8      .1       0
  4467.4     .12       0  4888.6     .05       0  4965.9     .16       0
    4997     .07       0    5003     .16       0  5064.7      .1       0
  5163.5     .16       0  5262.3     .12       0  5294.9     .16       0
  5410.1      .1       0    5986     .05       0  6001.9      .1       0
Bank Sta=4997,5003
XS Rating Curve= 0 ,0
Exp/Cntr=0.3,0.1

Chan Stop Cuts=-1
Use User Specified Reach Order=0
Composite Channel Slope=5