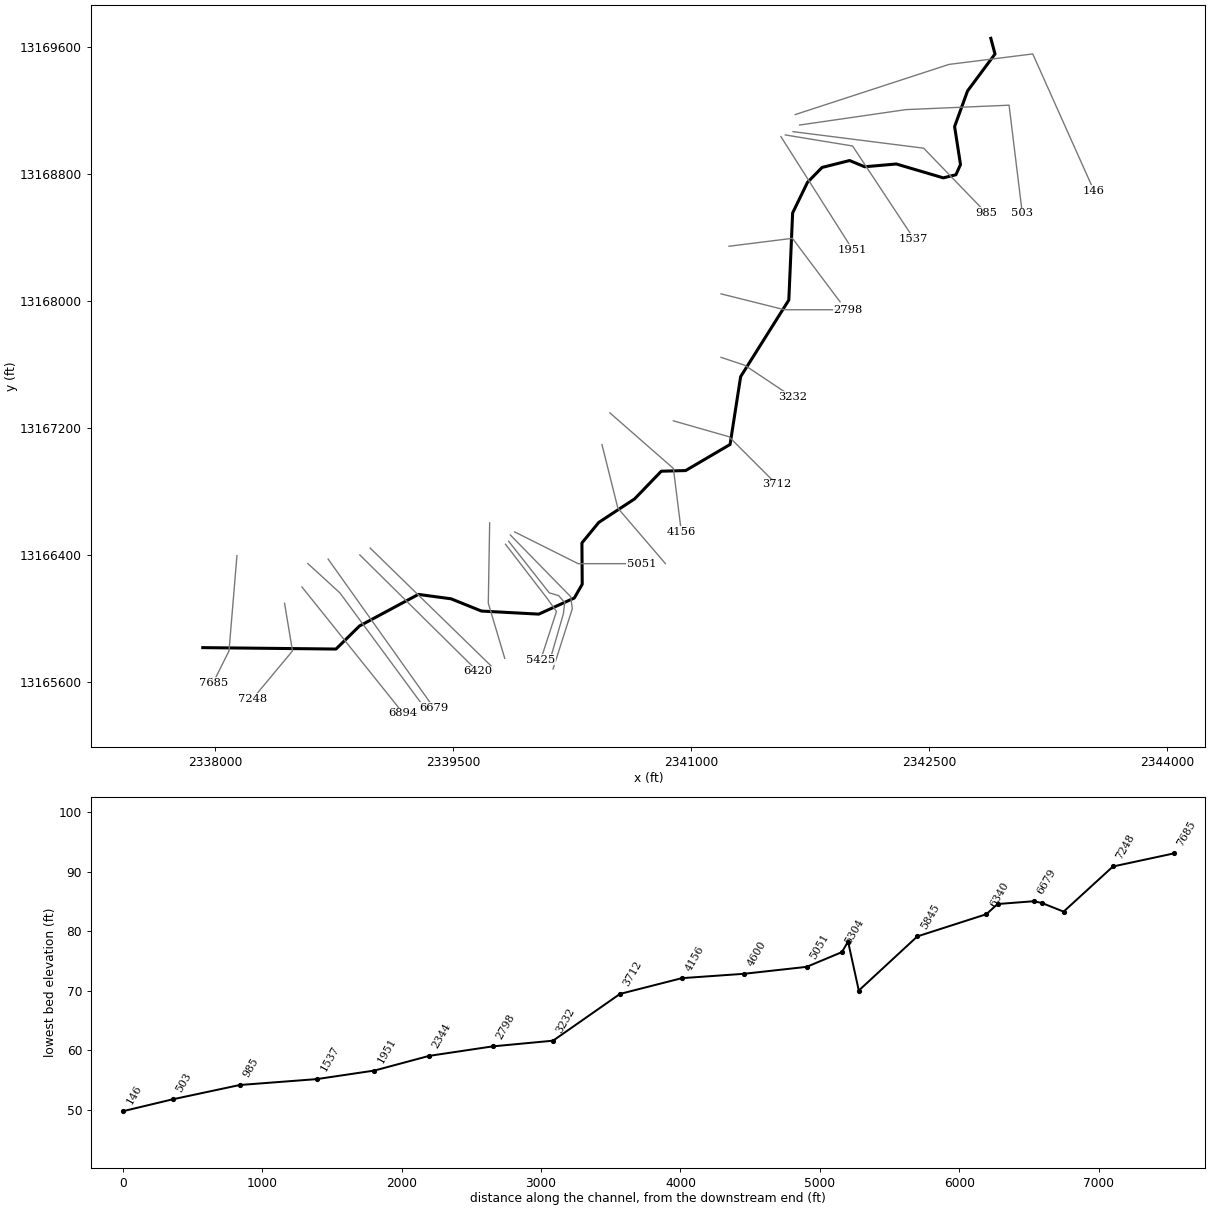
--- UNT035 IN BACR.prj (project) ---

Proj Title=UNT035 IN BACR Base Level Engineering
Current Plan=p01
Default Exp/Contr=0.3,0.1
English Units
Geom File=g01
Flow File=f01
Plan File=p01
BEGIN DESCRIPTION:
UNT035 IN BACR
END DESCRIPTION:

--- UNT035 IN BACR.p01 (plan) ---

Plan Title=Multiple Run
Short Identifier=Multiple
Geom File=g01
Flow File=f01
Subcritical Flow
K Sum by GR= 0
Std Step Tol= 0.01
Critical Tol= 0.01
Num of Std Step Trials= 20
Max Error Tol= 0.3
Flow Tol Ratio= 0.001
Split Flow NTrial= 30
Split Flow Tol= 0.02
Split Flow Ratio= 0.02
Log Output Level= 0
Friction Slope Method= 1
Unsteady Friction Slope Method= 2
Unsteady Bridges Friction Slope Method= 1
Parabolic Critical Depth
Global Vel Dist=  1 , 1 , 1
Global Log Level= 0
CheckData=True
Encroach Param= -1, 0, 0, 0
BEGIN DESCRIPTION:
Multiple Run
END DESCRIPTION:

--- UNT035 IN BACR.f01 (steady flow) ---

Flow Title=Multiple
Number of Profiles=7
Profile Names=10-year,25-year,50-year,1pct_min,100-year,1pct_plu,500-year
River Rch & RM= UNT035 IN BACR,Reach-1,7685
     248     334     403     356     482     652     696
River Rch & RM= UNT035 IN BACR,Reach-1,6420
     448     625     772     698     944    1277    1427
River Rch & RM= UNT035 IN BACR,Reach-1,4600
     498     697     863     783    1058    1431    1607
Boundary for River Rch & Prof#=UNT035 IN BACR,Reach-1,1
Up Type=0
Dn Type=3
Dn Slope=0.005
Boundary for River Rch & Prof#=UNT035 IN BACR,Reach-1,2
Up Type=0
Dn Type=3
Dn Slope=0.005
Boundary for River Rch & Prof#=UNT035 IN BACR,Reach-1,3
Up Type=0
Dn Type=3
Dn Slope=0.005
Boundary for River Rch & Prof#=UNT035 IN BACR,Reach-1,4
Up Type=0
Dn Type=3
Dn Slope=0.005
Boundary for River Rch & Prof#=UNT035 IN BACR,Reach-1,5
Up Type=0
Dn Type=3
Dn Slope=0.005
Boundary for River Rch & Prof#=UNT035 IN BACR,Reach-1,6
Up Type=0
Dn Type=3
Dn Slope=0.005
Boundary for River Rch & Prof#=UNT035 IN BACR,Reach-1,7
Up Type=0
Dn Type=3
Dn Slope=0.005

--- UNT035 IN BACR.g01 (geometry) ---

Geom Title=Existing Conditions

River Reach=UNT035 IN BACR,Reach-1
Reach XY= 30
      2337922.50     13165817.85      2338761.99     13165808.95
      2338909.51     13165953.93      2339280.62     13166153.23
      2339486.91     13166125.48      2339678.34     13166048.27
      2340039.46     13166028.92      2340263.42     13166130.48
      2340313.17     13166217.04      2340311.40     13166477.51
      2340417.68     13166606.88      2340643.45     13166755.09
      2340811.38     13166929.42      2340964.79     13166933.45
      2341244.83     13167097.96      2341311.42     13167525.32
      2341614.96     13168008.00      2341638.99     13168556.85
      2341732.64     13168749.55      2341824.41     13168843.33
      2341997.94     13168886.85      2342092.90     13168847.71
      2342291.91     13168865.13      2342588.28     13168777.78
      2342667.77     13168797.32      2342696.72     13168861.62
      2342659.51     13169101.03      2342741.09     13169325.46
      2342914.12     13169558.23      2342887.72     13169656.86

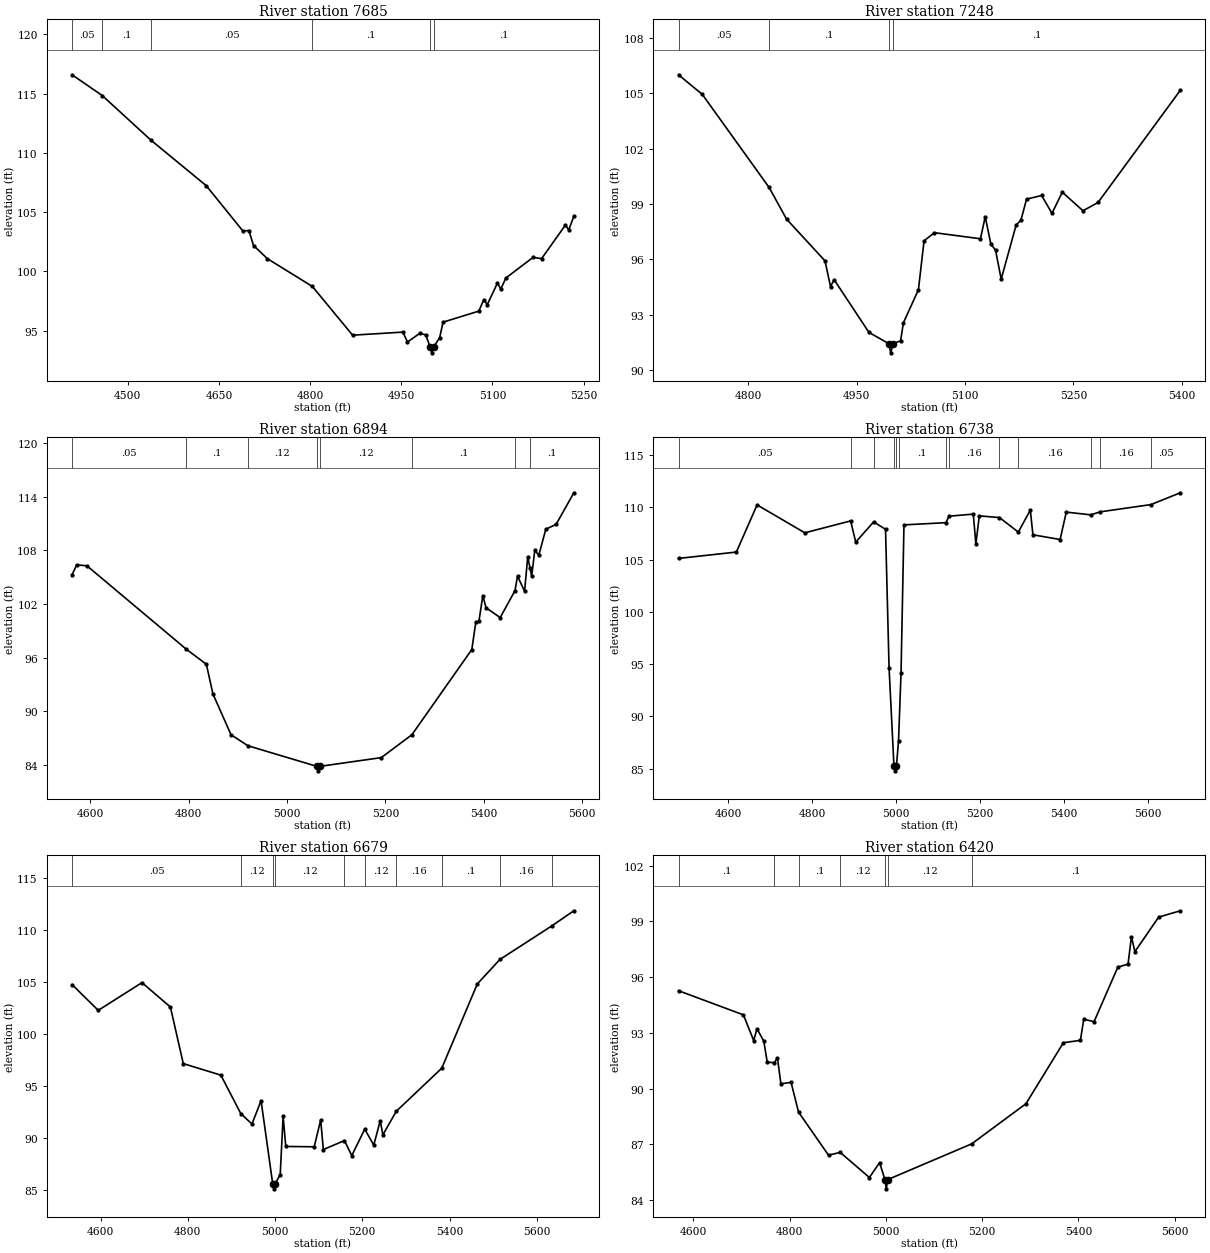
Type RM Length L Ch R = 1,7685,437,437,437
BEGIN DESCRIPTION:
UNT035 IN BACR 14.0
END DESCRIPTION:
XS GIS Cut Line= 3
      2338137.72     13166396.88      2338087.72     13165796.85
      2337987.72     13165596.86
#Sta/Elev= 30
  4408.2  116.59  4457.8  114.84  4538.0  111.07  4629.0  107.23  4689.2  103.41
  4699.2  103.44  4706.8  102.18  4729.3  101.08  4803.7   98.72  4869.8   94.61
  4952.6   94.87  4960.1   94.03  4980.2   94.76  4990.2   94.64  4997.3   93.62
  5000.0   93.12  5003.3   93.62  5013.1   94.41  5018.7   95.71  5077.4   96.64
  5085.8   97.61  5091.4   97.19  5108.1   99.00  5113.7   98.51  5122.1   99.44
  5166.8  101.18  5180.8  101.07  5219.9  103.90  5225.5  103.50  5233.9  104.65
#Mann=6,-1,0
  4408.2    0.05       0  4457.8     0.1       0  4538.0    0.05       0
  4803.7     0.1       0  4997.3    0.07       0  5003.3     0.1       0
Bank Sta=4997.3,5003.3
Exp/Cntr=0.3,0.1

Type RM Length L Ch R = 1,7248,354,354,354
BEGIN DESCRIPTION:
UNT035 IN BACR 13.0
END DESCRIPTION:
XS GIS Cut Line= 3
      2338437.72     13166096.86      2338487.72     13165796.85
      2338237.69     13165496.82
#Sta/Elev= 30
  4703.2  106.01  4736.2  104.94  4828.5   99.90  4852.7   98.18  4906.0   95.91
  4913.6   94.52  4918.6   94.89  4966.8   92.03  4994.2   91.42  4997.0   90.92
  5000.2   91.42  5010.6   91.57  5014.5   92.55  5035.3   94.34  5043.1   97.00
  5057.5   97.44  5121.2   97.11  5127.8   98.31  5135.6   96.82  5142.1   96.49
  5149.9   94.92  5170.7   97.87  5177.2   98.11  5185.0   99.26  5205.9   99.46
  5220.2   98.49  5234.5   99.64  5263.1   98.63  5284.0   99.08  5397.9  105.17
#Mann=4,-1,0
  4703.2    0.05       0  4828.5     0.1       0  4994.2    0.07       0
  5000.2     0.1       0
Bank Sta=4994.2,5000.2
Exp/Cntr=0.3,0.1

Type RM Length L Ch R = 1,6894,156,156,156
BEGIN DESCRIPTION:
UNT035 IN BACR 12.0
END DESCRIPTION:
XS GIS Cut Line= 2
      2338547.39     13166199.98      2339185.36     13165403.61
#Sta/Elev= 30
  4562.8  105.26  4572.3  106.37  4593.1  106.26  4794.5   96.96  4835.9   95.25
  4849.2   91.94  4886.0   87.37  4920.2   86.14  5060.6   83.83  5063.4   83.33
  5066.6   83.83  5191.7   84.81  5253.9   87.37  5375.7   96.90  5383.7   99.93
  5390.1  100.04  5398.1  102.93  5404.6  101.57  5433.4  100.47  5463.5  103.49
  5468.6  105.10  5483.0  103.42  5489.4  107.28  5494.1  106.00  5497.4  105.10
  5503.8  108.03  5511.8  107.43  5526.2  110.36  5547.0  110.89  5583.2  114.43
#Mann=8,-1,0
  4562.8    0.05       0  4794.5     0.1       0  4920.2    0.12       0
  5060.6    0.07       0  5066.6    0.12       0  5253.9     0.1       0
  5463.5    0.05       0  5494.1     0.1       0
Bank Sta=5060.6,5066.6
Exp/Cntr=0.3,0.1

Type RM Length L Ch R = 1,6738,59,59,59
BEGIN DESCRIPTION:
Mapping XS 545c6166
END DESCRIPTION:
XS GIS Cut Line= 3
      2338584.24     13166347.60      2338786.09     13166163.12
      2339332.51     13165421.54
#Sta/Elev= 30
  4482.5  105.11  4620.2  105.72  4669.5  110.23  4783.2  107.56  4892.3  108.70
  4904.3  106.67  4946.9  108.60  4975.3  107.90  4983.7   94.66  4995.3   85.29
  4998.1   84.79  5001.3   85.29  5006.2   87.61  5012.2   94.17  5019.2  108.32
  5119.1  108.53  5126.4  109.15  5184.2  109.35  5190.4  106.49  5198.5  109.18
  5246.5  109.02  5291.4  107.63  5320.0  109.73  5326.2  107.37  5390.9  106.92
  5405.6  109.54  5463.6  109.28  5486.9  109.57  5607.1  110.26  5677.1  111.39
#Mann=13,-1,0
  4482.5    0.05       0  4892.3     0.1       0  4946.9    0.12       0
  4995.3    0.07       0  5001.3    0.12       0  5006.2     0.1       0
  5119.1    0.12       0  5126.4    0.16       0  5246.5     0.1       0
  5291.4    0.16       0  5463.6     0.1       0  5486.9    0.16       0
  5607.1    0.05       0
Bank Sta=4995.3,5001.3
Exp/Cntr=0.3,0.1

Type RM Length L Ch R = 1,6679,259,259,259
BEGIN DESCRIPTION:
Mapping XS ed13bc8d
END DESCRIPTION:
XS GIS Cut Line= 2
      2338712.30     13166375.79      2339378.53     13165438.30
#Sta/Elev= 30
  4534.8  104.75  4594.8  102.27  4695.0  104.94  4760.2  102.59  4789.7   97.14
  4875.8   96.03  4921.5   92.33  4947.1   91.32  4968.0   93.57  4994.6   85.58
  4997.3   85.08  5000.6   85.58  5011.9   86.46  5018.5   92.06  5024.6   89.16
  5089.8   89.13  5104.6   91.72  5110.7   88.86  5159.1   89.73  5175.9   88.28
  5205.6   90.83  5226.3   89.29  5241.1   91.65  5247.2   90.28  5277.9   92.55
  5382.2   96.70  5463.7  104.82  5515.4  107.17  5634.2  110.40  5684.9  111.86
#Mann=10,-1,0
  4534.8    0.05       0  4921.5    0.12       0  4994.6    0.07       0
  5000.6    0.12       0  5159.1    0.16       0  5205.6    0.12       0
  5277.9    0.16       0  5382.2     0.1       0  5515.4    0.16       0
  5634.2    0.05       0
Bank Sta=4994.6,5000.6
Exp/Cntr=0.3,0.1

Type RM Length L Ch R = 1,6420,80,80,80
BEGIN DESCRIPTION:
UNT035 IN BACR 11.0
END DESCRIPTION:
XS GIS Cut Line= 2
      2338911.98     13166401.81      2339653.46     13165669.00
#Sta/Elev= 30
  4569.3   95.27  4704.1   93.97  4725.4   92.59  4732.4   93.22  4746.5   92.55
  4753.6   91.42  4768.6   91.40  4774.8   91.66  4781.9   90.26  4803.1   90.34
  4818.6   88.74  4880.9   86.42  4905.2   86.57  4965.8   85.22  4987.0   86.02
  4998.1   85.11  5000.9   84.61  5004.1   85.11  5178.3   87.03  5291.1   89.19
  5368.8   92.47  5404.2   92.60  5411.2   93.74  5432.5   93.60  5482.0   96.54
  5503.2   96.70  5510.2   98.18  5517.4   97.37  5566.8   99.23  5611.8   99.57
#Mann=7,-1,0
  4569.3     0.1       0  4768.6    0.05       0  4818.6     0.1       0
  4905.2    0.12       0  4998.1    0.07       0  5004.1    0.12       0
  5178.3     0.1       0
Bank Sta=4998.1,5004.1
Exp/Cntr=0.3,0.1

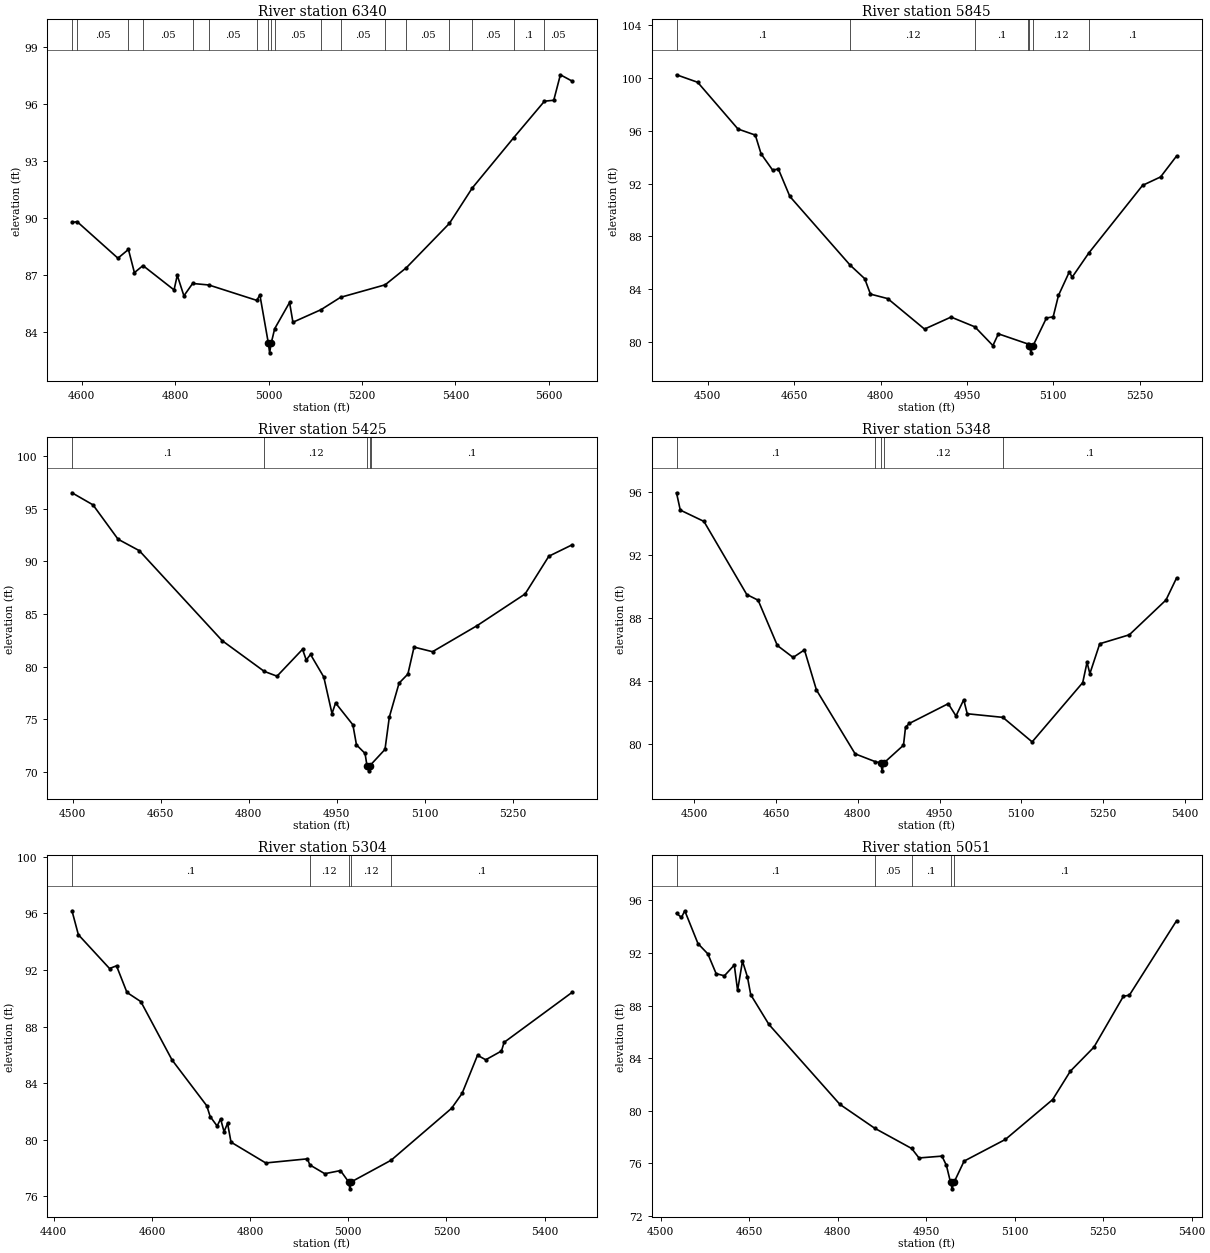
Type RM Length L Ch R = 1,6340,495,495,495
BEGIN DESCRIPTION:
Mapping XS b880d486
END DESCRIPTION:
XS GIS Cut Line= 2
      2338977.07     13166445.23      2339743.99     13165697.80
#Sta/Elev= 30
  4578.9   89.76  4590.0   89.80  4677.3   87.88  4699.8   88.34  4712.6   87.12
  4731.0   87.49  4797.5   86.21  4804.4   86.98  4818.6   85.90  4837.3   86.55
  4872.0   86.47  4974.7   85.66  4981.3   85.95  4999.5   83.40  5002.2   82.90
  5005.5   83.40  5013.0   84.17  5044.9   85.55  5052.1   84.51  5112.2   85.17
  5154.0   85.82  5249.7   86.48  5295.1   87.38  5387.2   89.71  5436.1   91.57
  5524.6   94.21  5590.8   96.14  5610.7   96.19  5624.9   97.53  5649.8   97.20
#Mann=18,-1,0
  4578.9     0.1       0  4590.0    0.05       0  4699.8     0.1       0
  4731.0    0.05       0  4837.3     0.1       0  4872.0    0.05       0
  4974.7    0.12       0  4999.5    0.07       0  5005.5    0.12       0
  5013.0    0.05       0  5112.2    0.12       0  5154.0    0.05       0
  5249.7     0.1       0  5295.1    0.05       0  5387.2     0.1       0
  5436.1    0.05       0  5524.6     0.1       0  5590.8    0.05       0
Bank Sta=4999.5,5005.5
Exp/Cntr=0.3,0.1

Type RM Length L Ch R = 1,5845,420,420,420
BEGIN DESCRIPTION:
UNT035 IN BACR 10.0
END DESCRIPTION:
XS GIS Cut Line= 3
      2339730.10     13166603.69      2339721.42     13166098.01
      2339825.09     13165750.28
#Sta/Elev= 30
  4445.6  100.24  4482.4   99.67  4552.4   96.13  4582.5   95.67  4592.5   94.25
  4612.5   93.02  4622.5   93.10  4642.5   91.02  4747.1   85.82  4772.5   84.79
  4782.5   83.62  4812.5   83.28  4876.4   80.97  4922.5   81.88  4963.9   81.14
  4995.2   79.72  5004.7   80.61  5056.2   79.84  5058.5   79.67  5061.3   79.17
  5064.5   79.67  5088.2   81.81  5099.9   81.90  5109.1   83.52  5127.8   85.29
  5133.0   84.91  5161.7   86.73  5255.2   91.86  5286.5   92.50  5314.2   94.08
#Mann=7,-1,0
  4445.6     0.1       0  4747.1    0.12       0  4963.9     0.1       0
  5056.2    0.12       0  5058.5    0.07       0  5064.5    0.12       0
  5161.7     0.1       0
Bank Sta=5058.5,5064.5
Exp/Cntr=0.3,0.1

Type RM Length L Ch R = 1,5425,77,77,77
BEGIN DESCRIPTION:
UNT035 IN BACR 9.0
END DESCRIPTION:
XS GIS Cut Line= 4
      2339829.95     13166469.08      2340090.34     13166130.57
      2340151.10     13166045.93      2340051.60     13165740.92
#Sta/Elev= 30
  4499.0   96.54  4534.8   95.39  4577.5   92.12  4613.7   91.03  4755.0   82.46
  4826.6   79.54  4848.4   79.08  4891.9   81.64  4898.2   80.62  4905.5   81.15
  4928.1   79.00  4942.1   75.52  4948.2   76.53  4977.7   74.45  4983.8   72.54
  4998.4   71.73  5001.7   70.57  5004.5   70.07  5007.7   70.57  5008.3   70.66
  5032.4   72.11  5039.8   75.19  5056.4   78.42  5071.4   79.28  5081.9   81.85
  5113.4   81.41  5189.3   83.89  5271.2   86.91  5311.6   90.50  5351.1   91.58
#Mann=5,-1,0
  4499.0     0.1       0  4826.6    0.12       0  5001.7    0.07       0
  5007.7    0.12       0  5008.3     0.1       0
Bank Sta=5001.7,5007.7
Exp/Cntr=0.3,0.1

Type RM Length L Ch R = 1,5348,44,44,44
BEGIN DESCRIPTION:
Mapping XS 082f604f
END DESCRIPTION:
XS GIS Cut Line= 6
      2339849.47     13166488.62      2340105.53     13166163.12
      2340164.12     13166145.76      2340203.19     13166102.35
      2340194.51     13166030.74      2340107.78     13165731.55
#Sta/Elev= 30
  4467.4   95.98  4474.3   94.88  4517.7   94.16  4596.3   89.51  4617.1   89.15
  4652.4   86.27  4681.3   85.51  4702.1   85.99  4724.1   83.44  4795.1   79.38
  4832.3   78.88  4841.8   78.80  4844.6   78.30  4847.8   78.80  4883.8   79.93
  4887.5   81.07  4894.3   81.31  4965.9   82.57  4980.1   81.79  4994.3   82.82
  5000.7   81.93  5066.1   81.70  5119.8   80.14  5212.6   83.91  5220.5   85.20
  5225.7   84.48  5243.8   86.38  5298.1   86.95  5365.3   89.16  5384.7   90.56
#Mann=5,-1,0
  4467.4     0.1       0  4832.3    0.12       0  4841.8    0.07       0
  4847.8    0.12       0  5066.1     0.1       0
Bank Sta=4841.8,4847.8
Exp/Cntr=0.3,0.1

Type RM Length L Ch R = 1,5304,253,253,253
BEGIN DESCRIPTION:
Mapping XS 1eb64497
END DESCRIPTION:
XS GIS Cut Line= 4
      2339860.32     13166527.69      2340240.08     13166139.25
      2340250.93     13166063.29      2340129.41     13165683.53
#Sta/Elev= 30
  4437.2   96.18  4450.2   94.49  4513.7   92.10  4527.9   92.29  4549.2   90.41
  4577.5   89.76  4641.0   85.64  4711.8   82.40  4718.7   81.64  4732.9   80.97
  4740.0   81.47  4747.0   80.57  4754.2   81.16  4761.2   79.83  4831.9   78.36
  4916.8   78.65  4921.8   78.22  4952.2   77.60  4984.2   77.82  5000.6   77.03
  5003.4   76.53  5006.6   77.03  5087.3   78.55  5210.5   82.22  5231.9   83.27
  5263.4   85.97  5280.1   85.65  5312.2   86.27  5317.5   86.88  5455.9   90.41
#Mann=5,-1,0
  4437.2     0.1       0  4921.8    0.12       0  5000.6    0.07       0
  5006.6    0.12       0  5087.3     0.1       0
Bank Sta=5000.6,5006.6
Exp/Cntr=0.3,0.1

Type RM Length L Ch R = 1,5051,451,451,451
BEGIN DESCRIPTION:
UNT035 IN BACR 8.0
END DESCRIPTION:
XS GIS Cut Line= 3
      2339887.69     13166546.87      2340287.72     13166346.85
      2340687.77     13166346.85
#Sta/Elev= 30
  4527.0   95.02  4535.4   94.70  4541.0   95.21  4563.4   92.71  4580.1   91.93
  4594.1   90.43  4608.1   90.26  4624.9   91.08  4630.5   89.15  4638.8   91.38
  4647.2   90.17  4652.8   88.82  4683.6   86.56  4803.8   80.48  4862.9   78.66
  4925.5   77.12  4937.9   76.40  4976.8   76.54  4984.3   75.84  4991.3   74.55
  4994.0   74.05  4997.3   74.55  5014.3   76.16  5084.3   77.81  5164.3   80.84
  5194.3   83.00  5234.3   84.83  5284.3   88.71  5294.3   88.78  5374.3   94.45
#Mann=5,-1,0
  4527.0     0.1       0  4862.9    0.05       0  4925.5     0.1       0
  4991.3    0.07       0  4997.3     0.1       0
Bank Sta=4991.3,4997.3
Exp/Cntr=0.3,0.1

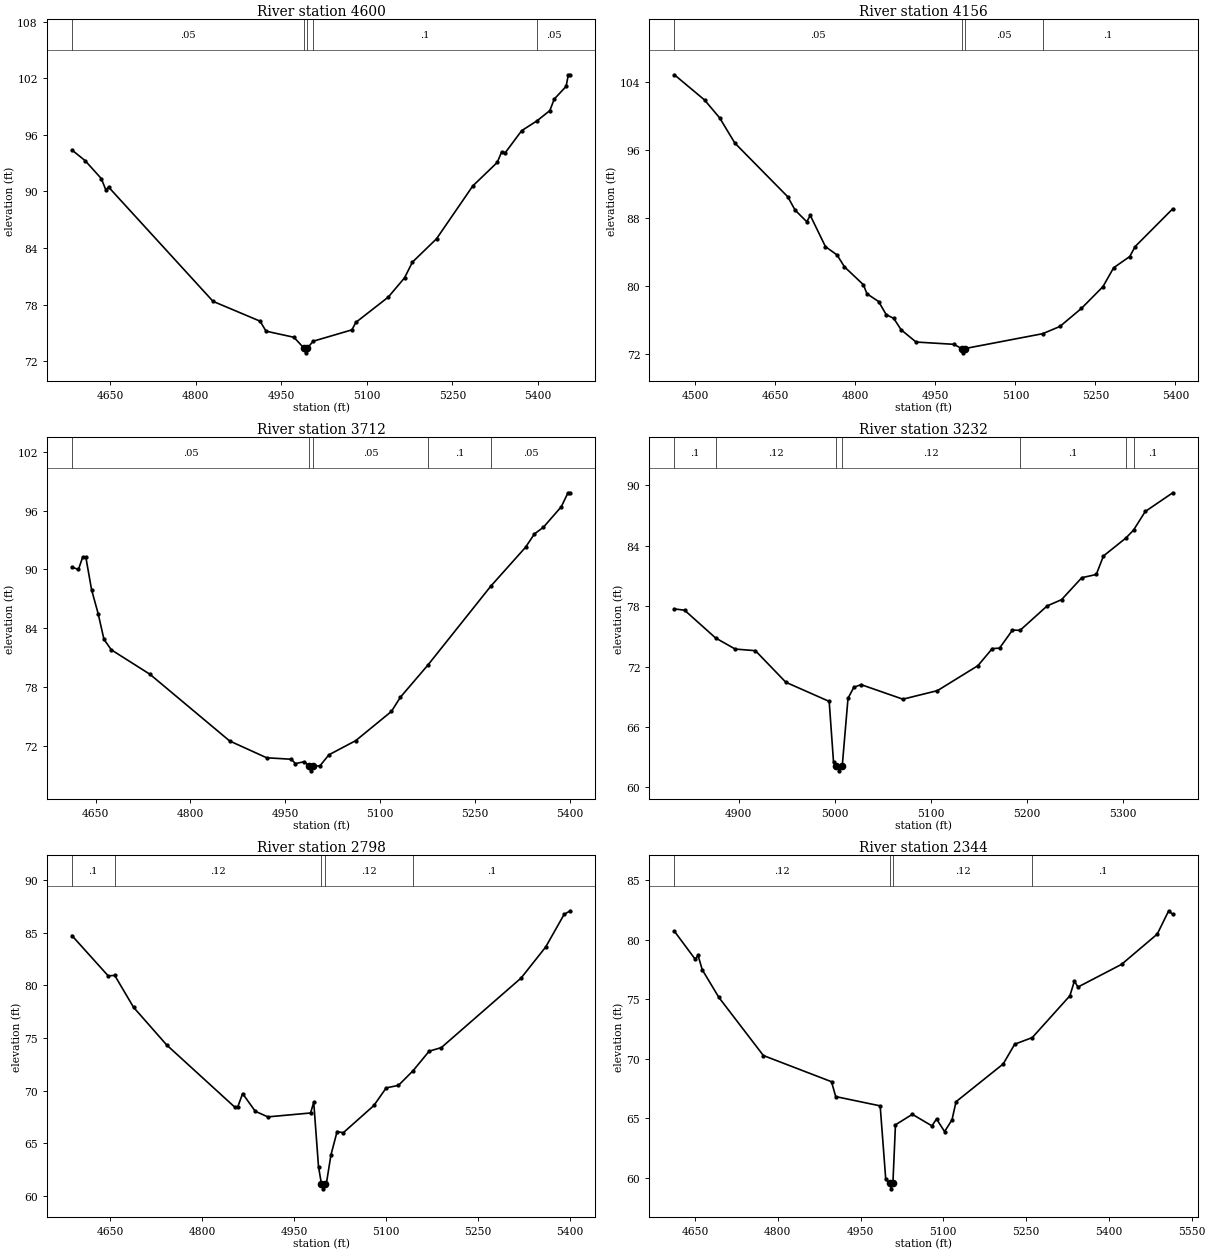
Type RM Length L Ch R = 1,4600,444,444,444
BEGIN DESCRIPTION:
UNT035 IN BACR 7.0
END DESCRIPTION:
XS GIS Cut Line= 3
      2340437.72     13167096.85      2340537.72     13166696.85
      2340837.73     13166346.84
#Sta/Elev= 30
  4583.2   94.40  4606.4   93.27  4634.7   91.37  4642.5   90.19  4647.6   90.46
  4830.6   78.34  4913.0   76.24  4923.4   75.18  4972.3   74.53  4989.9   73.38
  4992.7   72.88  4995.9   73.38  5005.9   74.11  5074.0   75.32  5080.6   76.10
  5137.6   78.79  5166.2   80.84  5179.9   82.50  5222.2   84.98  5285.8   90.59
  5328.6   93.08  5336.3   94.19  5342.9   94.13  5371.4   96.45  5398.0   97.48
  5420.8   98.58  5428.5   99.80  5449.3  101.15  5453.2  102.38  5456.5  102.38
#Mann=5,-1,0
  4583.2    0.05       0  4989.9   0.035       0  4995.9    0.05       0
  5005.9     0.1       0  5398.0    0.05       0
Bank Sta=4989.9,4995.9
Exp/Cntr=0.3,0.1

Type RM Length L Ch R = 1,4156,444,444,444
BEGIN DESCRIPTION:
UNT035 IN BACR 6.0
END DESCRIPTION:
XS GIS Cut Line= 3
      2340487.73     13167296.85      2340887.72     13166946.85
      2340937.72     13166546.87
#Sta/Elev= 30
  4460.5  104.83  4517.0  101.87  4545.4   99.76  4573.9   96.80  4673.1   90.49
  4686.9   88.92  4708.7   87.56  4715.3   88.30  4743.8   84.63  4765.6   83.65
  4779.4   82.26  4815.0   80.15  4821.6   79.09  4843.5   78.18  4857.7   76.64
  4871.9   76.20  4885.7   74.86  4913.7   73.42  4984.9   73.15  4999.1   72.65
  5001.8   72.15  5005.1   72.65  5151.2   74.40  5183.5   75.25  5223.8   77.37
  5264.1   79.92  5284.3   82.15  5314.5   83.47  5324.6   84.64  5395.1   89.08
#Mann=4,-1,0
  4460.5    0.05       0  4999.1    0.03       0  5005.1    0.05       0
  5151.2     0.1       0
Bank Sta=4999.1,5005.1
Exp/Cntr=0.3,0.1

Type RM Length L Ch R = 1,3712,480,480,480
BEGIN DESCRIPTION:
UNT035 IN BACR 5.0
END DESCRIPTION:
XS GIS Cut Line= 3
      2340887.69     13167246.86      2341237.72     13167146.85
      2341537.72     13166846.86
#Sta/Elev= 30
  4612.4   90.23  4622.8   90.01  4629.3   91.23  4634.5   91.23  4643.6   87.92
  4654.0   85.49  4663.1   82.89  4674.8   81.82  4735.9   79.33  4862.0   72.54
  4920.5   70.83  4959.5   70.68  4966.0   70.24  4980.0   70.43  4987.6   70.00
  4990.3   69.50  4993.6   70.00  5004.7   70.00  5018.9   71.13  5061.3   72.57
  5117.9   75.55  5132.0   76.99  5175.7   80.28  5274.9   88.29  5330.0   92.26
  5344.1   93.62  5358.3   94.30  5386.6   96.39  5397.2   97.81  5400.7   97.81
#Mann=5,-1,0
  4612.4    0.05       0  4987.6    0.03       0  4993.6    0.05       0
  5175.7     0.1       0  5274.9    0.05       0
Bank Sta=4987.6,4993.6
Exp/Cntr=0.3,0.1

Type RM Length L Ch R = 1,3232,434,434,434
BEGIN DESCRIPTION:
UNT035 IN BACR 4.0
END DESCRIPTION:
XS GIS Cut Line= 3
      2341187.70     13167646.86      2341337.72     13167596.85
      2341637.73     13167396.85
#Sta/Elev= 30
  4833.2   77.73  4843.8   77.60  4876.1   74.84  4896.5   73.74  4917.5   73.58
  4949.2   70.44  4994.3   68.54  4998.8   62.53  5001.9   62.14  5004.6   61.64
  5007.9   62.14  5013.9   68.85  5019.9   69.93  5027.4   70.21  5071.0   68.76
  5107.0   69.61  5149.1   72.09  5164.1   73.79  5171.6   73.83  5185.1   75.63
  5193.0   75.60  5221.2   78.03  5236.2   78.65  5257.2   80.83  5272.3   81.15
  5279.8   82.99  5303.1   84.77  5311.1   85.56  5323.3   87.41  5351.9   89.27
#Mann=7,-1,0
  4833.2     0.1       0  4876.1    0.12       0  5001.9    0.07       0
  5007.9    0.12       0  5193.0     0.1       0  5303.1    0.16       0
  5311.1     0.1       0
Bank Sta=5001.9,5007.9
Exp/Cntr=0.3,0.1

Type RM Length L Ch R = 1,2798,454,454,454
BEGIN DESCRIPTION:
UNT035 IN BACR 3.0
END DESCRIPTION:
XS GIS Cut Line= 3
      2341187.77     13168046.84      2341587.72     13167946.85
      2341987.76     13167946.85
#Sta/Elev= 30
  4587.7   84.72  4646.9   80.89  4657.5   80.94  4688.2   77.91  4742.3   74.33
  4853.1   68.44  4858.2   68.48  4866.0   69.72  4886.6   68.04  4907.2   67.51
  4976.8   67.88  4981.9   68.90  4989.7   62.78  4994.4   61.18  4997.1   60.68
  5000.4   61.18  5002.5   61.18  5010.0   63.90  5020.0   66.12  5030.0   66.00
  5080.0   68.59  5100.0   70.26  5120.0   70.50  5143.7   71.88  5170.0   73.74
  5190.0   74.09  5320.0   80.69  5360.0   83.63  5390.0   86.72  5400.0   87.07
#Mann=5,-1,0
  4587.7     0.1       0  4657.5    0.12       0  4994.4    0.07       0
  5000.4    0.12       0  5143.7     0.1       0
Bank Sta=4994.4,5000.4
Exp/Cntr=0.3,0.1

Type RM Length L Ch R = 1,2344,393,393,393
BEGIN DESCRIPTION:
UNT035 IN BACR 2.0
END DESCRIPTION:
XS GIS Cut Line= 3
      2341237.72     13168346.86      2341637.72     13168396.85
      2341937.71     13167996.86
#Sta/Elev= 30
  4612.6   80.73  4650.4   78.37  4655.4   78.71  4663.0   77.50  4693.2   75.17
  4773.8   70.29  4897.3   68.09  4904.9   66.84  4985.5   66.06  4995.6   59.89
  5002.6   59.59  5005.4   59.09  5008.6   59.59  5013.2   64.47  5043.8   65.35
  5079.3   64.38  5087.6   64.96  5102.2   63.90  5115.7   64.89  5123.0   66.41
  5208.4   69.58  5229.3   71.24  5261.2   71.80  5329.3   75.31  5337.6   76.56
  5343.8   76.04  5423.0   77.95  5487.6   80.49  5508.4   82.45  5515.7   82.15
#Mann=4,-1,0
  4612.6    0.12       0  5002.6    0.07       0  5008.6    0.12       0
  5261.2     0.1       0
Bank Sta=5002.6,5008.6
Exp/Cntr=0.3,0.1

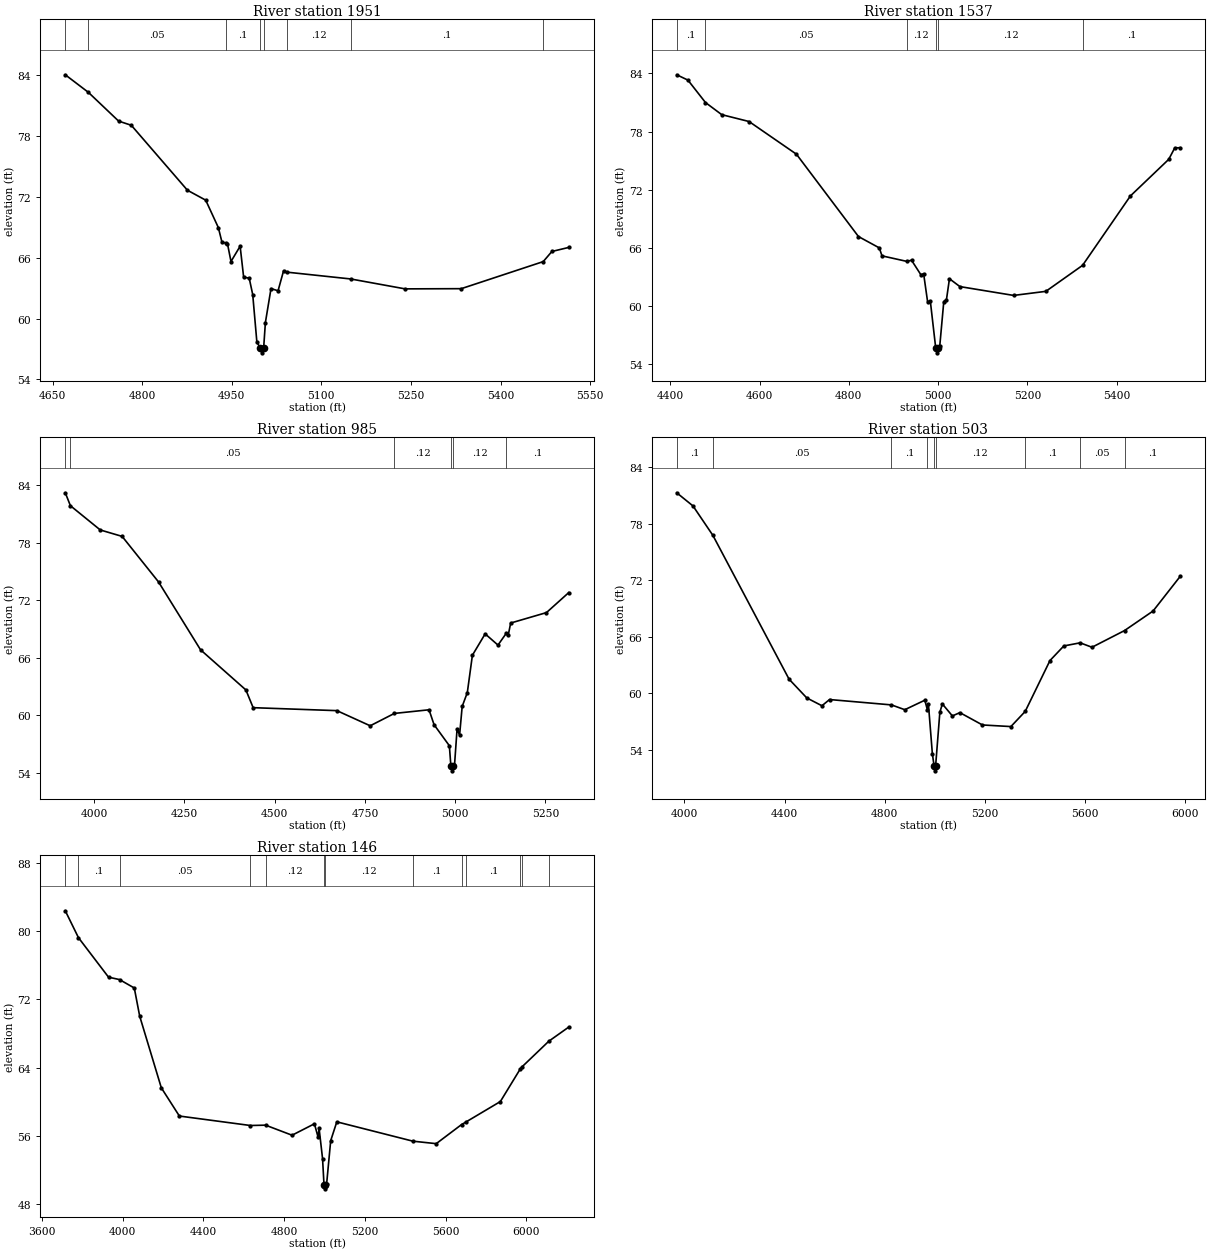
Type RM Length L Ch R = 1,1951,414,414,414
BEGIN DESCRIPTION:
Mapping XS d9f37cfc
END DESCRIPTION:
XS GIS Cut Line= 2
      2341565.15     13169037.71      2342016.56     13168325.87
#Sta/Elev= 30
  4671.3   84.05  4709.9   82.32  4760.6   79.48  4781.8   79.07  4875.8   72.66
  4906.4   71.68  4927.5   68.98  4933.5   67.56  4939.7   67.45  4942.8   67.39
  4948.7   65.63  4964.0   67.14  4969.9   64.08  4979.2   63.99  4985.1   62.36
  4992.0   57.70  4997.4   57.12  5000.2   56.62  5003.4   57.12  5006.3   59.61
  5015.7   62.96  5027.5   62.74  5036.8   64.73  5042.2   64.58  5148.9   63.91
  5240.2   62.93  5334.2   62.95  5471.4   65.62  5485.9   66.62  5514.2   67.02
#Mann=8,-1,0
  4671.3     0.1       0  4709.9    0.05       0  4939.7     0.1       0
  4997.4    0.07       0  5003.4     0.1       0  5042.2    0.12       0
  5148.9     0.1       0  5471.4    0.12       0
Bank Sta=4997.4,5003.4
Exp/Cntr=0.3,0.1

Type RM Length L Ch R = 1,1537,552,552,552
BEGIN DESCRIPTION:
Mapping XS 168ceba7
END DESCRIPTION:
XS GIS Cut Line= 3
      2341592.95     13169048.10      2342016.55     13168978.66
      2342401.96     13168395.34
#Sta/Elev= 30
  4414.3   83.85  4439.4   83.30  4478.7   80.99  4515.1   79.74  4576.4   79.03
  4682.6   75.66  4821.6   67.17  4868.3   66.00  4874.3   65.18  4929.9   64.61
  4940.5   64.73  4961.6   63.22  4967.6   63.34  4976.6   60.42  4982.6   60.53
  4994.7   55.68  4997.5   55.18  5000.7   55.68  5003.7   55.85  5012.8   60.47
  5018.8   60.67  5025.5   62.82  5048.9   62.01  5169.3   61.10  5241.5   61.52
  5323.8   64.20  5431.1   71.36  5516.9   75.13  5530.4   76.31  5542.7   76.33
#Mann=6,-1,0
  4414.3     0.1       0  4478.7    0.05       0  4929.9    0.12       0
  4994.7    0.07       0  5000.7    0.12       0  5323.8     0.1       0
Bank Sta=4994.7,5000.7
Exp/Cntr=0.3,0.1

Type RM Length L Ch R = 1,985,482,482,482
BEGIN DESCRIPTION:
Mapping XS 2c4745a9
END DESCRIPTION:
XS GIS Cut Line= 3
      2341641.60     13169068.93      2342464.47     13168964.77
      2342856.82     13168558.54
#Sta/Elev= 30
  3920.4   83.20  3934.6   81.85  4017.3   79.32  4077.8   78.65  4178.6   73.90
  4294.9   66.82  4420.5   62.63  4440.6   60.78  4672.5   60.47  4764.7   58.89
  4831.6   60.18  4927.6   60.56  4941.6   59.00  4983.9   56.81  4988.1   54.69
  4990.9   54.19  4994.1   54.69  4998.1   54.74  5005.3   58.58  5012.2   57.91
  5019.4   60.91  5033.6   62.35  5047.7   66.25  5083.0   68.48  5118.5   67.31
  5141.3   68.53  5146.8   68.32  5153.7   69.61  5252.8   70.70  5314.6   72.79
#Mann=6,-1,0
  3920.4     0.1       0  3934.6    0.05       0  4831.6    0.12       0
  4988.1    0.07       0  4994.1    0.12       0  5141.3     0.1       0
Bank Sta=4988.1,4994.1
Exp/Cntr=0.3,0.1

Type RM Length L Ch R = 1,503,357,357,357
BEGIN DESCRIPTION:
Mapping XS 0f6671a1
END DESCRIPTION:
XS GIS Cut Line= 4
      2341683.25     13169110.60      2342353.36     13169207.82
      2343002.67     13169235.60      2343086.00     13168555.01
#Sta/Elev= 30
  3969.0   81.30  4034.1   79.90  4113.5   76.78  4418.1   61.51  4488.9   59.52
  4549.5   58.69  4579.8   59.35  4827.4   58.78  4880.7   58.27  4960.8   59.28
  4971.1   58.24  4975.1   58.86  4990.8   53.62  4997.8   52.28  5000.6   51.78
  5003.8   52.28  5020.8   58.00  5030.8   58.88  5070.9   57.61  5100.9   57.96
  5191.0   56.65  5304.8   56.48  5362.0   58.09  5461.0   63.49  5516.4   65.04
  5581.6   65.37  5628.9   64.90  5758.9   66.67  5873.2   68.75  5981.7   72.43
#Mann=9,-1,0
  3969.0     0.1       0  4113.5    0.05       0  4827.4     0.1       0
  4971.1    0.12       0  4997.8    0.07       0  5003.8    0.12       0
  5362.0     0.1       0  5581.6    0.05       0  5758.9     0.1       0
Bank Sta=4997.8,5003.8
Exp/Cntr=0.3,0.1

Type RM Length L Ch R = 1,146,0,0,0
BEGIN DESCRIPTION:
UNT035 IN BACR 1.0
END DESCRIPTION:
XS GIS Cut Line= 4
      2341655.40     13169176.56      2342624.19     13169492.55
      2343151.97     13169558.52      2343537.37     13168697.44
#Sta/Elev= 30
  3716.0   82.40  3781.4   79.24  3930.3   74.61  3984.6   74.33  4057.9   73.34
  4084.6   70.04  4191.8   61.63  4281.2   58.32  4633.1   57.21  4708.4   57.25
  4839.4   56.07  4950.2   57.41  4968.3   55.85  4973.4   56.86  4990.5   53.33
  4997.6   50.28  5000.4   49.78  5003.6   50.28  5010.7   50.36  5030.8   55.43
  5061.1   57.64  5438.3   55.37  5553.6   55.08  5679.1   57.32  5703.5   57.66
  5871.3   60.02  5969.5   63.83  5980.3   64.13  6111.4   67.10  6210.3   68.76
#Mann=13,-1,0
  3716.0    0.05       0  3781.4     0.1       0  3984.6    0.05       0
  4633.1     0.1       0  4708.4    0.12       0  4997.6    0.07       0
  5003.6    0.12       0  5438.3     0.1       0  5679.1    0.05       0
  5703.5     0.1       0  5969.5    0.16       0  5980.3     0.1       0
  6111.4    0.16       0
Bank Sta=4997.6,5003.6
Exp/Cntr=0.3,0.1

Chan Stop Cuts=-1