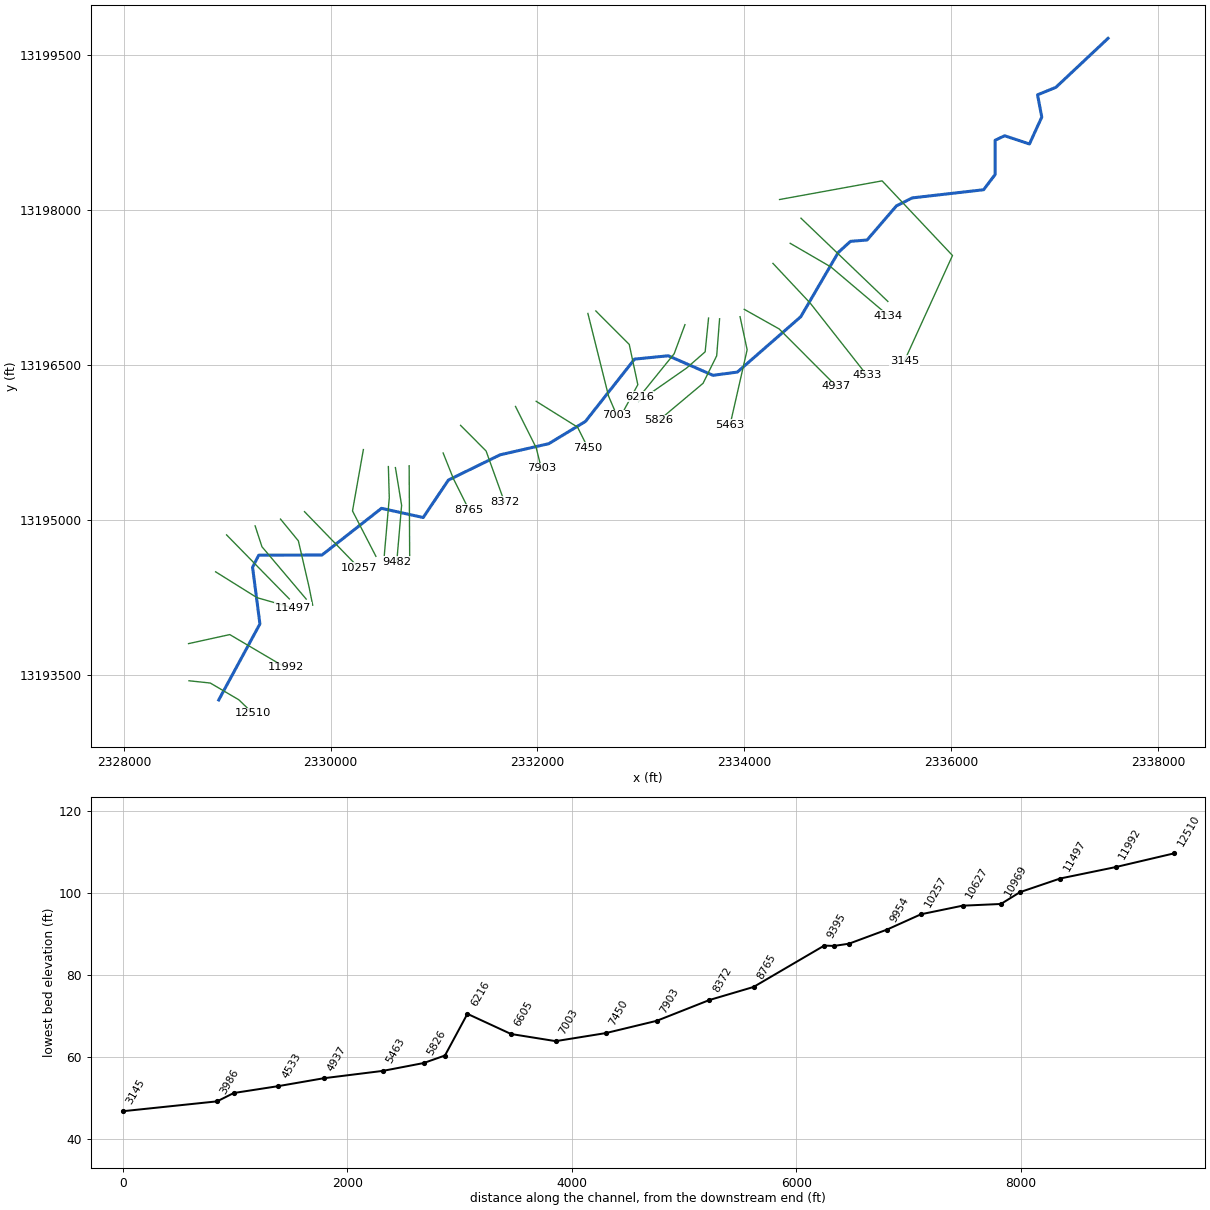
--- UNT036 IN BACR.prj (project) ---

Proj Title=UNT036 IN BACR Base Level Engineering
Current Plan=p01
Default Exp/Contr=0.3,0.1
English Units
Geom File=g01
Flow File=f01
Plan File=p01
Y Axis Title=Elevation
X Axis Title(PF)=Main Channel Distance
X Axis Title(XS)=Station
BEGIN DESCRIPTION:
UNT036 IN BACR
END DESCRIPTION:
DSS Export Rating Curves= 0
DSS Export Rating Curve Sorted= 0
DSS Export Volume Flow Curves= 0
DXF OffsetX= 0
DXF OffsetY= 0
DXF ScaleX= 1
DXF ScaleY= 10

--- UNT036 IN BACR.p01 (plan) ---

Plan Title=Multiple Run
Short Identifier=Multiple
Geom File=g01
Flow File=f01
Subcritical Flow
K Sum by GR= 0
Std Step Tol= 0.01
Critical Tol= 0.01
Num of Std Step Trials= 20
Max Error Tol= 0.3
Flow Tol Ratio= 0.001
Split Flow NTrial= 30
Split Flow Tol= 0.02
Split Flow Ratio= 0.02
Log Output Level= 0
Friction Slope Method= 1
Unsteady Friction Slope Method= 2
Unsteady Bridges Friction Slope Method= 1
Parabolic Critical Depth
Global Vel Dist=  1 , 1 , 1
Global Log Level= 0
CheckData=True
Encroach Param= -1, 0, 0, 0
BEGIN DESCRIPTION:
Multiple Run
END DESCRIPTION:

--- UNT036 IN BACR.f01 (steady flow) ---

Flow Title=Multiple
Program Version=4.10
Number of Profiles= 7
Profile Names=10-year,25-year,50-year,1pct_min,100-year,1pct_plu,500-year
River Rch & RM=UNT036 IN BACR,Reach-1         ,12510
     499     692     850     763    1032    1396    1526
River Rch & RM=UNT036 IN BACR,Reach-1         ,11992
     568     793     979     883    1194    1614    1779
River Rch & RM=UNT036 IN BACR,Reach-1         ,10969
     626     880    1092     988    1337    1808    2011
River Rch & RM=UNT036 IN BACR,Reach-1         ,9954
    1069    1536    1933    1771    2395    3239    3694
River Rch & RM=UNT036 IN BACR,Reach-1         ,9615
    1069    1536    1933    1771    2395    3239    3694
River Rch & RM=UNT036 IN BACR,Reach-1         ,5826
    1278    1857    2354    2172    2937    3972    4594
Boundary for River Rch & Prof#=UNT036 IN BACR,Reach-1         , 1
Up Type= 0
Dn Type= 3
Dn Slope=0.005
Boundary for River Rch & Prof#=UNT036 IN BACR,Reach-1         , 2
Up Type= 0
Dn Type= 3
Dn Slope=0.005
Boundary for River Rch & Prof#=UNT036 IN BACR,Reach-1         , 3
Up Type= 0
Dn Type= 3
Dn Slope=0.005
Boundary for River Rch & Prof#=UNT036 IN BACR,Reach-1         , 4
Up Type= 0
Dn Type= 3
Dn Slope=0.005
Boundary for River Rch & Prof#=UNT036 IN BACR,Reach-1         , 5
Up Type= 0
Dn Type= 3
Dn Slope=0.005
Boundary for River Rch & Prof#=UNT036 IN BACR,Reach-1         , 6
Up Type= 0
Dn Type= 3
Dn Slope=0.005
Boundary for River Rch & Prof#=UNT036 IN BACR,Reach-1         , 7
Up Type= 0
Dn Type= 3
Dn Slope=0.005
DSS Import GetInterval= 0
DSS Import GetPeak= 0
DSS Import FillOption= 0

--- UNT036 IN BACR.g01 (geometry) ---

Geom Title=Existing Conditions
Program Version=4.10

River Reach=UNT036 IN BACR  ,Reach-1
Reach XY= 30
      2328917.72     13193256.86      2329315.98     13193992.64
      2329244.88     13194541.46      2329304.92     13194657.93
      2329916.58      13194659.6      2330491.58      13195111.2
      2330894.96     13195022.34      2331138.55     13195384.63
      2331638.86     13195629.14      2332109.78     13195736.92
      2332463.52     13195951.76      2332938.78     13196555.06
      2333265.02     13196587.61      2333696.85     13196398.49
      2333932.96     13196429.74      2334546.39     13196965.62
      2334908.65     13197587.15      2335026.71     13197694.79
      2335187.41     13197707.74      2335471.95     13198038.59
      2335623.29     13198115.09      2336314.45     13198194.23
      2336426.22     13198342.29      2336425.59     13198672.83
      2336517.72     13198716.86      2336757.53     13198637.03
      2336876.78     13198897.41      2336835.89     13199112.93
      2337013.34     13199185.18      2337517.65     13199659.37

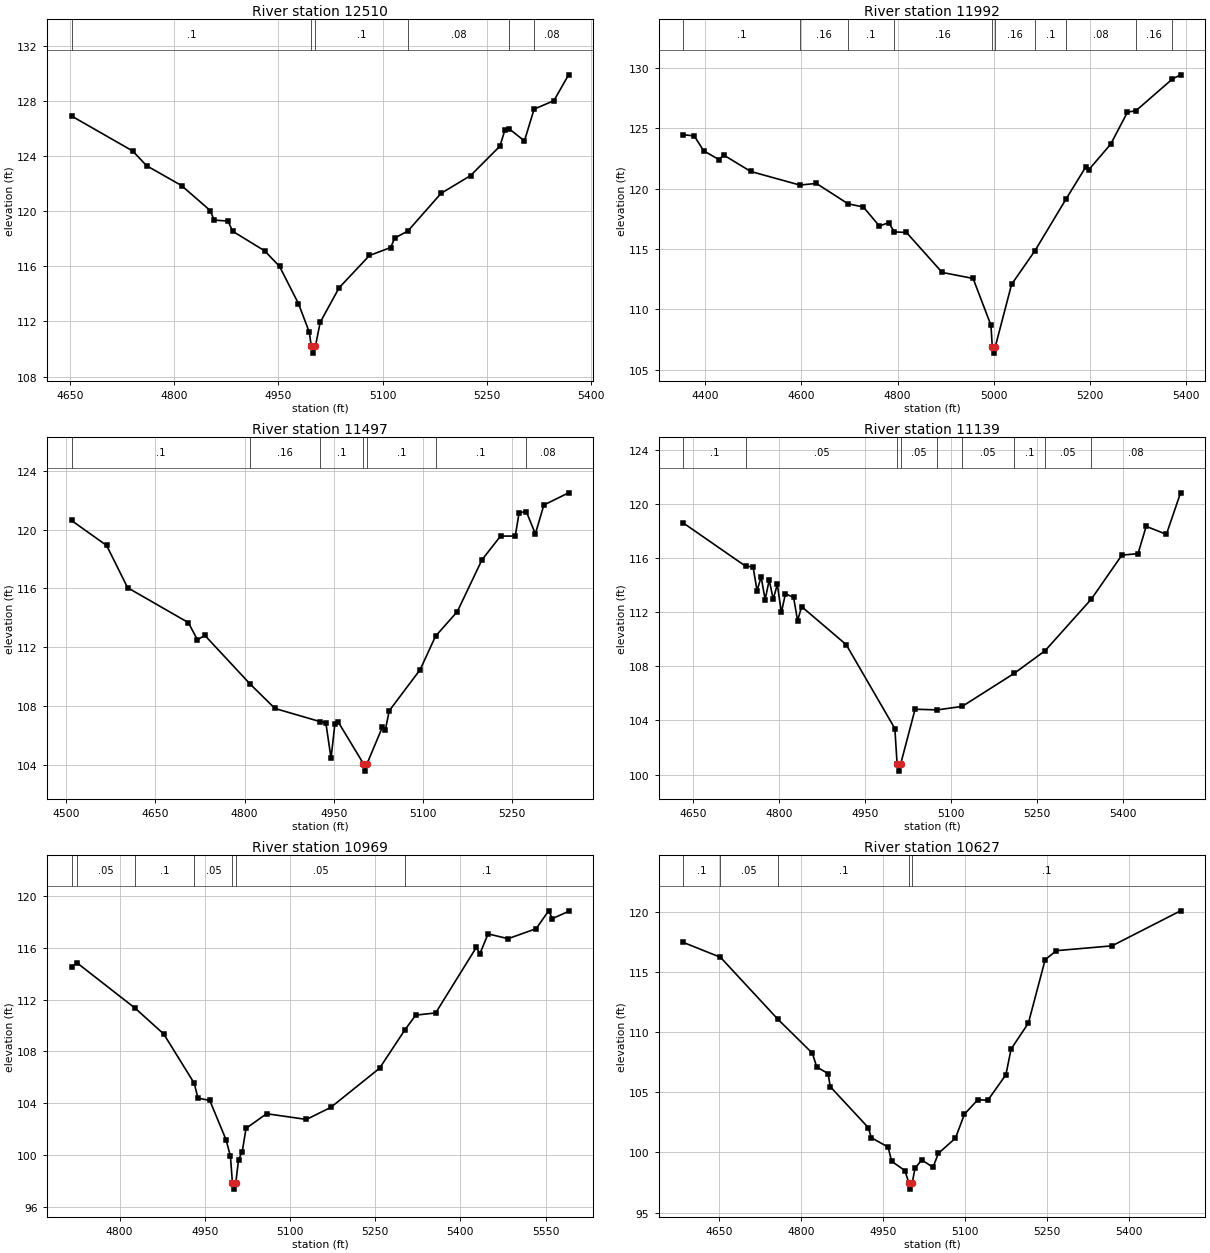
Type RM Length L Ch R = 1 ,12510   ,518,518,518
BEGIN DESCRIPTION:
UNT036 IN BACR 27.0
END DESCRIPTION:
XS GIS Cut Line= 4
       2328630.1     13193442.61      2328836.09     13193420.69
      2329112.16     13193258.56      2329248.04     13193127.06
#Sta/Elev= 30
  4651.8  126.92  4739.9  124.38    4760  123.31  4810.3  121.87  4851.8  120.05
  4857.3  119.36  4877.3  119.29    4884  118.55  4930.1  117.13  4951.6     116
  4978.9  113.29  4994.5  111.22  4997.3   110.2  5000.1   109.7  5003.3   110.2
  5010.2  111.94  5037.5  114.45  5081.2  116.79  5111.8  117.37  5117.6  118.06
  5136.4  118.56  5184.3   121.3  5226.8  122.59  5269.2  124.73  5276.2  125.87
  5282.2     126  5304.5  125.11  5318.5  127.42  5346.9  128.03  5368.2  129.91
#Mann= 6 ,-1 , 0
  4651.8      .1       0  4997.3     .07       0  5003.3      .1       0
  5136.4     .08       0  5282.2      .1       0  5318.5     .08       0
Bank Sta=4997.3,5003.3
XS Rating Curve= 0 ,0
Exp/Cntr=0.3,0.1

Type RM Length L Ch R = 1 ,11992   ,495,495,495
BEGIN DESCRIPTION:
UNT036 IN BACR 26.0
END DESCRIPTION:
XS GIS Cut Line= 3
       2328625.8     13193801.94      2329024.52     13193889.57
      2329562.71     13193571.86
#Sta/Elev= 30
  4354.8  124.47  4377.2  124.38  4396.8  123.14  4428.4  122.42  4438.7  122.78
  4494.6  121.43  4596.9   120.3    4631  120.44  4696.8  118.75  4728.8  118.48
  4762.1   116.9  4781.2  117.19  4793.2  116.42  4818.3  116.37  4892.5  113.06
  4956.8  112.56  4993.9  108.68  4996.7  106.87  4999.4  106.37  5002.7  106.87
  5036.8  112.07  5085.4  114.86  5149.9  119.14    5191   121.8  5196.8  121.55
  5242.9   123.7  5277.7  126.35  5295.2  126.46  5370.9  129.09    5388  129.44
#Mann= 10 ,-1 , 0
  4354.8      .1       0  4596.9     .16       0  4696.8      .1       0
  4793.2     .16       0  4996.7     .07       0  5002.7     .16       0
  5085.4      .1       0  5149.9     .08       0  5295.2     .16       0
  5370.9     .08       0
Bank Sta=4996.7,5002.7
XS Rating Curve= 0 ,0
Exp/Cntr=0.3,0.1

Type RM Length L Ch R = 1 ,11497   ,358,358,358
BEGIN DESCRIPTION:
UNT036 IN BACR 25.0
END DESCRIPTION:
XS GIS Cut Line= 3
      2328887.72     13194496.86      2329287.72     13194246.85
      2329637.71     13194146.86
#Sta/Elev= 30
    4509  120.62    4568  118.92  4603.3  116.05  4705.3  113.68  4720.7  112.51
  4733.1  112.81  4809.5  109.49    4851  107.84  4927.4  106.94  4936.5  106.88
  4945.3  104.46  4951.8   106.8  4957.7   106.9  4999.8  104.08  5002.6  103.58
  5005.8  104.08  5031.4  106.55  5036.6  106.38  5043.1  107.68  5095.1  110.48
  5121.1  112.76  5157.5  114.42  5199.1  117.95  5230.3  119.56    5255  119.56
  5261.5  121.16  5273.7  121.21  5288.8  119.71  5303.1  121.67  5344.7   122.5
#Mann= 7 ,-1 , 0
    4509      .1       0  4809.5     .16       0  4927.4      .1       0
  4999.8     .07       0  5005.8      .1       0  5121.1      .1       0
  5273.7     .08       0
Bank Sta=4999.8,5005.8
XS Rating Curve= 0 ,0
Exp/Cntr=0.3,0.1

Type RM Length L Ch R = 1 ,11139   ,170,170,170
BEGIN DESCRIPTION:
UNT036 IN BACR 24.0
END DESCRIPTION:
XS GIS Cut Line= 2
       2328993.6     13194854.26      2329600.33     13194234.51
#Sta/Elev= 30
  4632.8   118.6  4741.6   115.4  4754.2  115.37  4761.2   113.6  4768.3  114.62
  4775.3  112.94  4782.4  114.39  4789.4  112.98  4796.6  114.06  4803.6  111.99
  4810.7  113.37  4824.9  113.11  4831.9  111.38    4839  112.42  4916.7  109.61
  5001.6   103.4  5005.6  100.75  5008.4  100.25  5011.6  100.75  5036.9  104.83
  5075.6  104.78  5119.2  105.04  5210.1  107.49  5263.8  109.16  5344.5  112.98
  5397.7  116.23  5425.9  116.34  5440.1  118.36  5475.4  117.77  5500.1  120.84
#Mann= 9 ,-1 , 0
  4632.8      .1       0  4741.6     .05       0  5005.6     .04       0
  5011.6     .05       0  5075.6      .1       0  5119.2     .05       0
  5210.1      .1       0  5263.8     .05       0  5344.5     .08       0
Bank Sta=5005.6,5011.6
XS Rating Curve= 0 ,0
Exp/Cntr=0.3,0.1

Type RM Length L Ch R = 1 ,10969   ,342,342,342
BEGIN DESCRIPTION:
Mapping XS d085d7db
END DESCRIPTION:
XS GIS Cut Line= 3
      2329269.92     13194941.21      2329335.64     13194739.68
      2329763.72     13194232.98
#Sta/Elev= 30
  4715.2  114.53  4724.7  114.84  4827.6  111.32  4877.6  109.34  4931.3  105.54
  4937.8  104.39  4958.6  104.22  4987.2  101.19    4995   99.92  4998.5   97.87
  5001.3   97.37  5004.5   97.87  5009.3   99.64  5015.8  100.26  5022.5  102.06
  5058.7  103.19  5128.9  102.75  5171.8  103.68  5257.6   106.7  5302.5  109.68
  5321.3   110.8  5356.4  110.97  5427.9  116.02  5434.4  115.55  5448.7  117.07
  5483.9   116.7  5533.3  117.47  5555.3  118.85  5561.9  118.25  5590.5  118.81
#Mann= 7 ,-1 , 0
  4715.2      .1       0  4724.7     .05       0  4827.6      .1       0
  4931.3     .05       0  4998.5    .035       0  5004.5     .05       0
  5302.5      .1       0
Bank Sta=4998.5,5004.5
XS Rating Curve= 0 ,0
Exp/Cntr=0.3,0.1

Type RM Length L Ch R = 1 ,10627   ,370,370,370
BEGIN DESCRIPTION:
UNT036 IN BACR 23.0
END DESCRIPTION:
XS GIS Cut Line= 4
      2329515.32     13195006.97      2329687.72     13194796.85
      2329791.37     13194349.68      2329826.43     13194174.37
#Sta/Elev= 30
  4584.3  117.44    4652  116.21  4756.9  111.07  4820.2  108.24  4828.1   107.1
  4848.9  106.55  4852.9  105.46  4922.7  102.05  4927.9  101.22  4958.7  100.45
  4965.3   99.26  4989.5   98.49  4996.8   97.45  4999.6   96.95  5002.8   97.45
    5008   98.68  5020.3   99.38  5040.9   98.76  5050.7   99.92  5081.9  101.18
  5098.5  103.18    5123  104.38  5141.2  104.33  5174.3  106.45  5183.8  108.59
  5215.4  110.74  5246.2  116.02  5266.7  116.76  5368.4  117.16  5493.9  120.07
#Mann= 5 ,-1 , 0
  4584.3      .1       0    4652     .05       0  4756.9      .1       0
  4996.8     .07       0  5002.8      .1       0
Bank Sta=4996.8,5002.8
XS Rating Curve= 0 ,0
Exp/Cntr=0.3,0.1

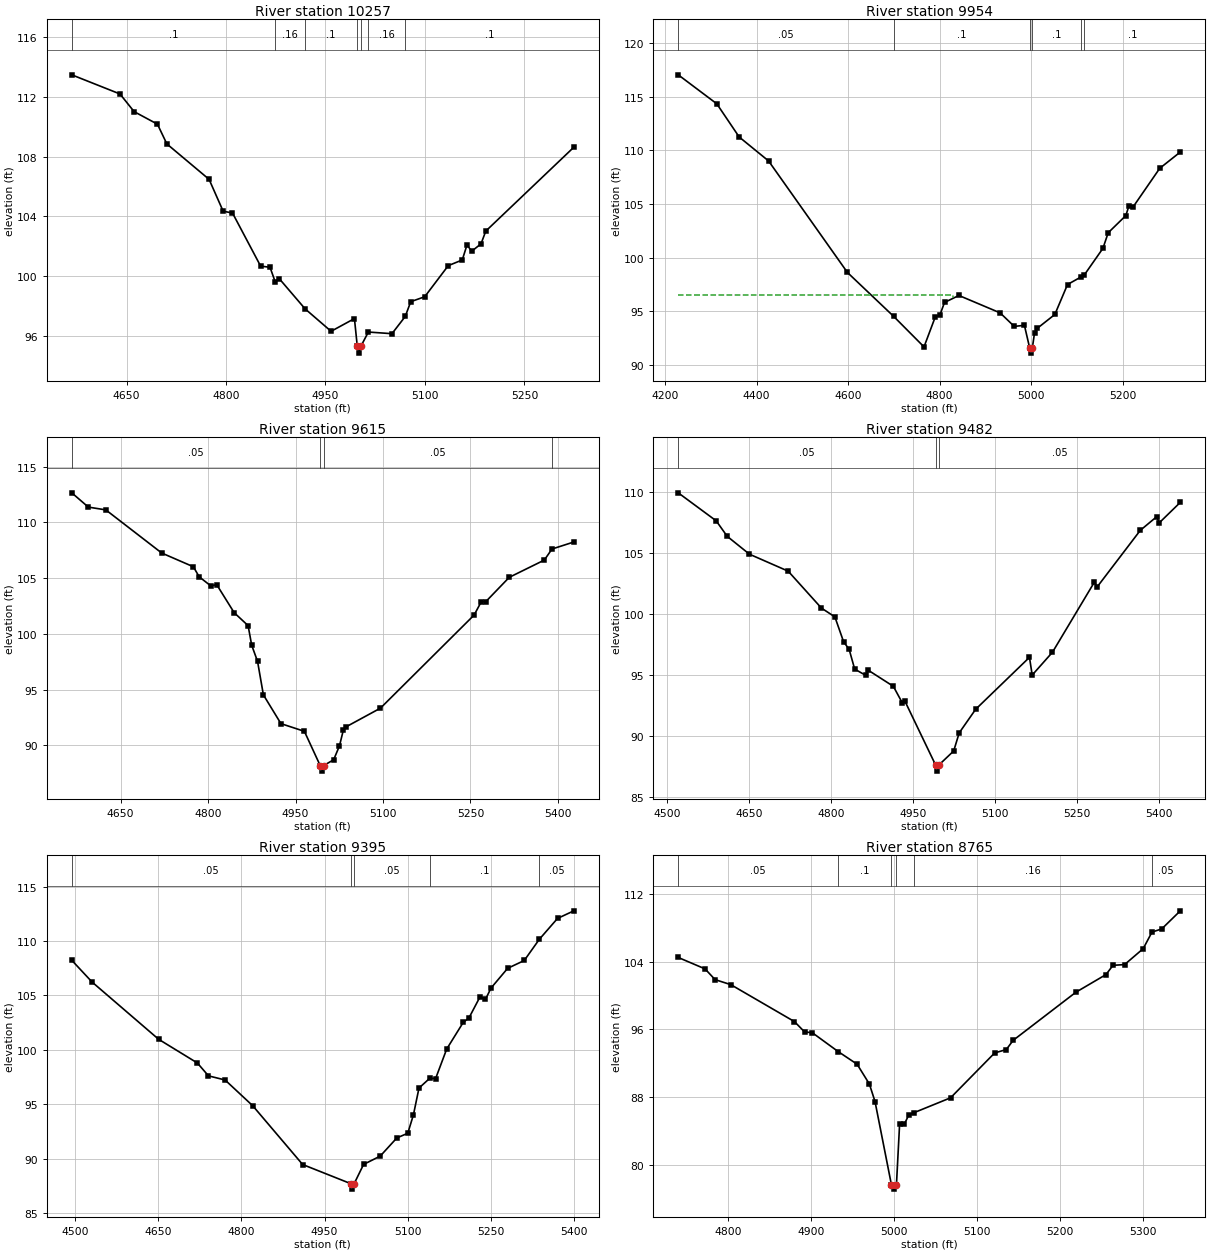
Type RM Length L Ch R = 1 ,10257   ,303,303,303
BEGIN DESCRIPTION:
Mapping XS c264890a
END DESCRIPTION:
XS GIS Cut Line= 2
      2329747.08     13195079.08      2330273.77     13194535.06
#Sta/Elev= 30
  4567.4  113.47  4640.1  112.19  4661.4  111.01  4696.6  110.17  4710.8  108.85
  4774.5  106.48  4795.7  104.35  4809.8  104.23  4852.2  100.68  4866.4   100.6
  4874.1   99.64  4880.5   99.83  4919.3   97.82  4958.5   96.32  4993.7   97.17
  4997.9   95.36  5000.7   94.86  5003.9   95.36  5014.7   96.27  5050.3   96.16
  5070.3   97.31  5078.6    98.3  5099.7   98.63  5135.2  100.71  5156.3  101.09
  5163.5   102.1  5170.5  101.67  5184.6  102.17  5191.8  103.02  5324.6  108.63
#Mann= 7 ,-1 , 0
  4567.4      .1       0  4874.1     .16       0  4919.3      .1       0
  4997.9     .07       0  5003.9      .1       0  5014.7     .16       0
  5070.3      .1       0
Bank Sta=4997.9,5003.9
XS Rating Curve= 0 ,0
Exp/Cntr=0.3,0.1

Type RM Length L Ch R = 1 ,9954    ,339,339,339
BEGIN DESCRIPTION:
UNT036 IN BACR 22.0
END DESCRIPTION:
XS GIS Cut Line= 3
      2330316.51     13195679.85      2330211.34     13195085.87
      2330437.74     13194646.82
#Sta/Elev= 30
  4228.7  117.04    4313  114.34  4361.9  111.25  4426.1  109.02  4598.5   98.63
  4699.5   94.54  4765.8    91.7  4790.3   94.48  4800.4   94.66  4810.6   95.84
  4842.1   96.49  4932.1   94.87    4963   93.61  4985.2   93.71  4996.6   91.62
  4999.3   91.12  5002.6   91.62  5007.3      93    5013   93.42  5051.7   94.72
  5079.4   97.51  5108.7   98.21  5116.4   98.42  5156.8  100.88  5168.3  102.33
  5206.8  103.93  5213.3  104.79  5223.3  104.77  5280.9  108.33  5325.9  109.85
#Mann= 6 ,-1 , 0
  4228.7     .05       0  4699.5      .1       0  4996.6     .07       0
  5002.6      .1       0  5108.7     .16       0  5116.4      .1       0
#XS Ineff= 2 , 0
         4829.32   96.57
Permanent Ineff=
       F       F
Bank Sta=4996.6,5002.6
XS Rating Curve= 0 ,0
Exp/Cntr=0.3,0.1

Type RM Length L Ch R = 1 ,9615    ,133,133,133
BEGIN DESCRIPTION:
UNT036 IN BACR 21.0
END DESCRIPTION:
XS GIS Cut Line= 3
      2330558.22     13195515.25      2330566.99     13195212.93
      2330518.79     13194656.46
#Sta/Elev= 30
  4566.3  112.64  4594.7  111.36  4624.7  111.11  4720.6  107.24  4774.8  106.01
  4784.8  105.11  4804.8  104.29  4814.8  104.41  4844.8  101.89  4868.7  100.73
  4874.8   98.98  4884.9   97.52  4894.9   94.52    4925   91.94  4965.2   91.25
  4992.3   88.18    4995   87.68  4998.3   88.18  5015.4    88.7  5025.4   89.95
  5032.2    91.4  5037.3   91.67  5095.7   93.33  5256.3  101.68  5268.6  102.88
  5276.3  102.88  5316.5  105.06  5376.7  106.61  5389.8   107.6  5427.3  108.23
#Mann= 4 ,-1 , 0
  4566.3     .05       0  4992.3     .03       0  4998.3     .05       0
  5389.8      .1       0
Bank Sta=4992.3,4998.3
XS Rating Curve= 0 ,0
Exp/Cntr=0.3,0.1

Type RM Length L Ch R = 1 ,9482    ,87,87,87
BEGIN DESCRIPTION:
Mapping XS be2081d9
END DESCRIPTION:
XS GIS Cut Line= 3
       2330626.4      13195505.3      2330686.29     13195140.74
      2330639.42     13194593.89
#Sta/Elev= 30
  4520.7  109.91  4590.1  107.62  4610.3  106.35  4650.9  104.89  4721.8   103.5
  4782.6  100.48  4807.2   99.76  4823.1   97.73  4833.3    97.1  4843.4   95.49
  4863.4   94.98  4868.4   95.39  4914.1   94.08  4930.6   92.72  4935.6   92.84
  4991.4   87.64  4994.2   87.14  4997.4   87.64  5024.5   88.79  5034.6   90.27
  5064.7    92.2  5163.1   96.45  5168.1      95  5205.2   96.87  5281.8   102.6
  5286.9  102.21  5365.8  106.84  5395.6  107.95  5400.6  107.46    5439  109.13
#Mann= 3 ,-1 , 0
  4520.7     .05       0  4991.4     .03       0  4997.4     .05       0
Bank Sta=4991.4,4997.4
XS Rating Curve= 0 ,0
Exp/Cntr=0.3,0.1

Type RM Length L Ch R = 1 ,9395    ,630,630,630
BEGIN DESCRIPTION:
UNT036 IN BACR 20.0
END DESCRIPTION:
XS GIS Cut Line= 2
      2330759.21     13195523.53      2330764.42     13194617.35
#Sta/Elev= 30
  4493.8  108.23  4530.5  106.23  4650.5  100.98  4720.5    98.8  4740.5   97.62
  4770.5   97.24  4820.5   94.87  4910.5   89.48  4997.5   87.72  5000.2   87.22
  5003.5   87.72  5020.5   89.49  5050.5   90.25  5080.5   91.92  5100.3   92.35
  5110.5   94.05  5120.5    96.5    5140    97.4  5150.5   97.37  5170.5  100.08
  5200.5  102.54  5210.5  102.92  5230.5  104.86  5240.5  104.64  5250.5  105.68
  5280.5  107.49  5310.5  108.21  5337.6  110.15  5370.5  112.07    5400  112.77
#Mann= 5 ,-1 , 0
  4493.8     .05       0  4997.5     .04       0  5003.5     .05       0
    5140      .1       0  5337.6     .05       0
Bank Sta=4997.5,5003.5
XS Rating Curve= 0 ,0
Exp/Cntr=0.3,0.1

Type RM Length L Ch R = 1 ,8765    ,393,393,393
BEGIN DESCRIPTION:
UNT036 IN BACR 19.0
END DESCRIPTION:
XS GIS Cut Line= 3
      2331087.72     13195646.87      2331187.72     13195396.85
      2331337.73     13195096.84
#Sta/Elev= 30
    4740   104.5  4772.3  103.15  4784.4  101.88  4803.3  101.29    4880   96.92
  4892.1   95.71  4901.6    95.6  4932.5   93.39  4955.4   91.89  4970.2   89.55
    4977   87.48  4996.8   77.63  4999.6   77.13  5002.8   77.63  5006.6   84.77
  5012.1   84.77  5017.7   85.89  5023.4   86.14    5068   87.92  5121.1   93.22
  5135.1   93.62  5143.4   94.71  5218.9  100.39  5255.2  102.48  5263.6  103.57
  5277.6  103.66    5300  105.54  5310.6   107.5  5322.3  107.87  5344.7  110.01
#Mann= 6 ,-1 , 0
    4740     .05       0  4932.5      .1       0  4996.8     .07       0
  5002.8      .1       0  5023.4     .16       0  5310.6     .05       0
Bank Sta=4996.8,5002.8
XS Rating Curve= 0 ,0
Exp/Cntr=0.3,0.1

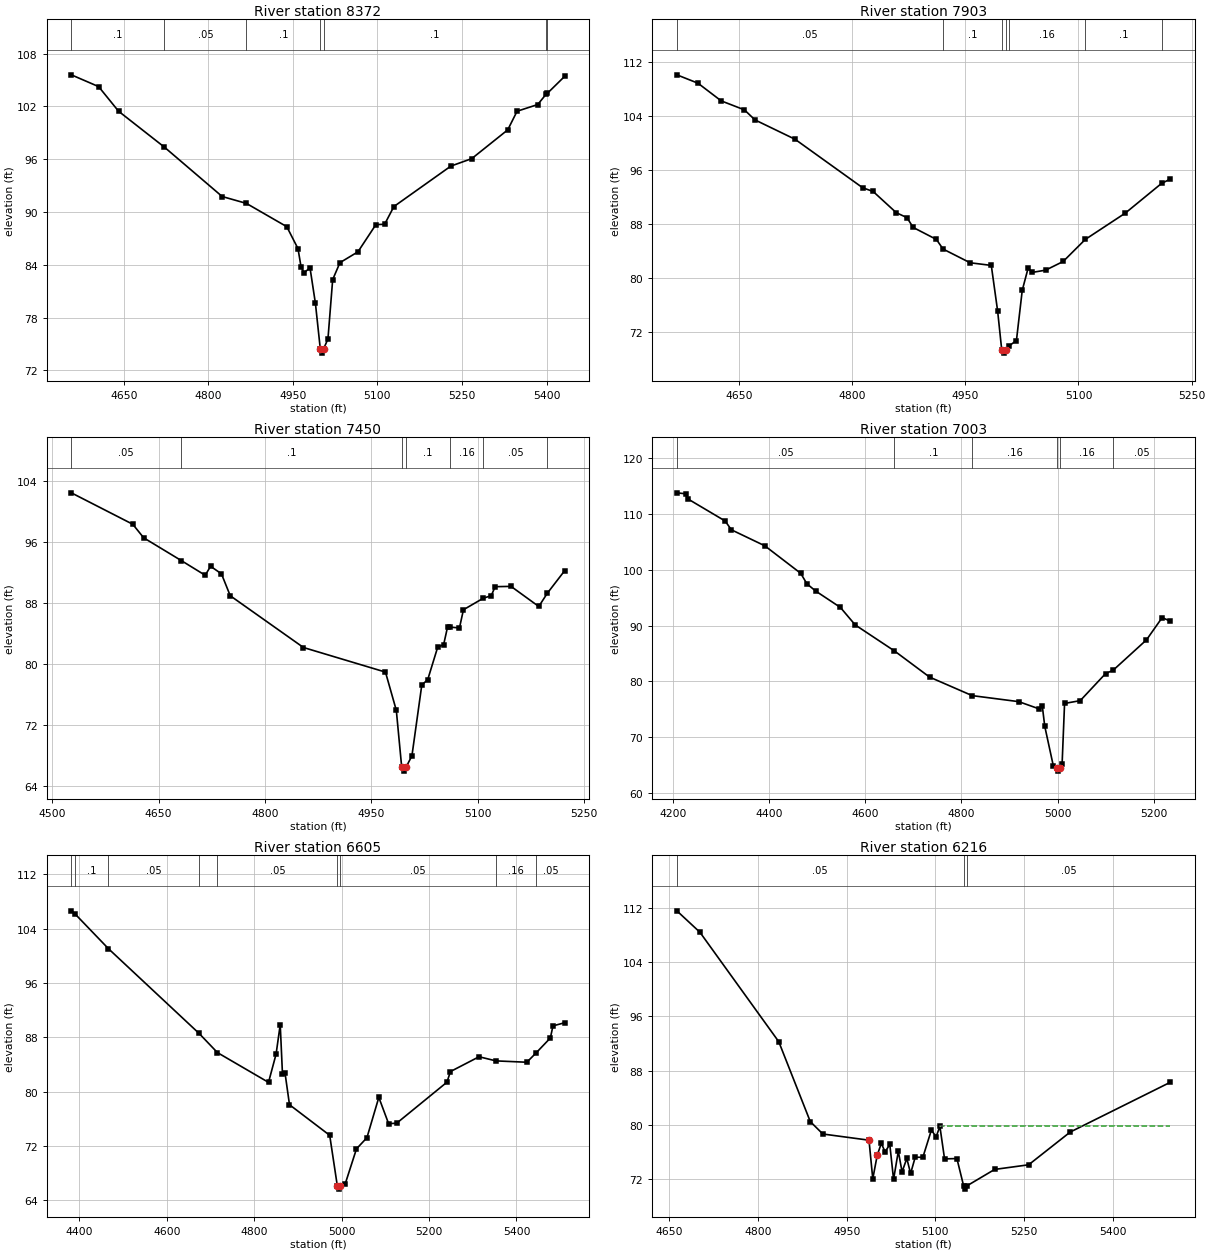
Type RM Length L Ch R = 1 ,8372    ,469,469,469
BEGIN DESCRIPTION:
UNT036 IN BACR 18.0
END DESCRIPTION:
XS GIS Cut Line= 3
      2331256.58      13195914.2      2331503.01     13195666.28
       2331681.1     13195171.95
#Sta/Elev= 30
  4557.1   105.6  4605.5  104.26  4640.9  101.46  4722.3   97.37  4824.7   91.76
  4867.6   90.98  4939.3   88.33  4959.2   85.83  4964.7   83.72    4970    83.1
  4980.5   83.65  4990.1    79.6  4998.7   74.45  5001.5   73.95  5004.7   74.45
  5012.3   75.56  5020.7   82.31  5033.6   84.24  5065.5   85.47  5097.4   88.57
  5112.8    88.6  5129.3   90.62  5230.3   95.22  5267.4   96.07  5331.2   99.34
  5347.8  101.46  5384.4  102.22  5399.2  103.39  5401.6   103.5  5432.1  105.42
#Mann= 7 ,-1 , 0
  4557.1      .1       0  4722.3     .05       0  4867.6      .1       0
  4998.7     .07       0  5004.7      .1       0  5399.2     .05       0
  5401.6     .08       0
Bank Sta=4998.7,5004.7
XS Rating Curve= 0 ,0
Exp/Cntr=0.3,0.1

Type RM Length L Ch R = 1 ,7903    ,453,453,453
BEGIN DESCRIPTION:
UNT036 IN BACR 17.0
END DESCRIPTION:
XS GIS Cut Line= 3
      2331787.71     13196096.88      2331987.72     13195696.85
      2332037.72     13195496.85
#Sta/Elev= 30
    4568  110.03    4596  108.79  4626.7  106.18  4657.5  104.85  4671.4  103.37
  4724.6   100.5    4814   93.34    4828   92.78  4858.7   89.64  4872.7   88.92
  4881.1   87.46  4911.8   85.69  4920.6   84.27  4956.5   82.24  4984.5   81.85
  4992.9   75.11  4998.3   69.38    5001   68.88  5004.3   69.38  5007.3   69.89
  5017.8   70.74  5025.5   78.16  5033.3   81.46  5038.4   80.81  5056.5   81.15
  5079.7   82.43    5109   85.69  5162.1   89.59  5210.1   93.98  5221.4    94.6
#Mann= 7 ,-1 , 0
    4568     .05       0  4920.6      .1       0  4998.3     .07       0
  5004.3      .1       0  5007.3     .16       0    5109      .1       0
  5210.1     .05       0
Bank Sta=4998.3,5004.3
XS Rating Curve= 0 ,0
Exp/Cntr=0.3,0.1

Type RM Length L Ch R = 1 ,7450    ,447,447,447
BEGIN DESCRIPTION:
UNT036 IN BACR 16.0
END DESCRIPTION:
XS GIS Cut Line= 3
      2331987.74     13196146.84      2332387.72     13195896.85
      2332487.73     13195696.83
#Sta/Elev= 30
  4526.9  102.45  4613.5   98.32  4628.9   96.54  4681.9   93.55  4715.6   91.62
  4723.2    92.8  4738.5   91.81  4750.9   88.93  4854.1   82.13  4969.7    78.9
    4985   73.87  4992.6   66.39  4995.4   65.89  4998.6   66.39    5007    67.9
  5020.9    77.2  5029.3   77.92  5043.3   82.17  5051.7   82.51  5057.3   84.86
  5060.8   84.81    5074    84.7  5079.6   87.09  5107.5    88.6  5118.8   88.94
  5124.3   90.12  5146.7   90.16  5185.8   87.52    5198   89.28  5222.2   92.21
#Mann= 7 ,-1 , 0
  4526.9     .05       0  4681.9      .1       0  4992.6     .07       0
  4998.6      .1       0  5060.8     .16       0  5107.5     .05       0
    5198     .08       0
Bank Sta=4992.6,4998.6
XS Rating Curve= 0 ,0
Exp/Cntr=0.3,0.1

Type RM Length L Ch R = 1 ,7003    ,398,398,398
BEGIN DESCRIPTION:
UNT036 IN BACR 15.0
END DESCRIPTION:
XS GIS Cut Line= 3
      2332487.73     13196996.81      2332687.72     13196196.85
       2332767.1     13196011.63
#Sta/Elev= 30
  4207.9  113.79  4225.9  113.62    4231  112.69  4308.4  108.74  4321.2  107.17
  4390.8   104.3  4465.5   99.37  4478.4   97.49  4496.5    96.2    4548   93.26
  4578.9   90.12  4660.5   85.46  4733.6   80.77  4822.2   77.45  4919.1   76.37
  4960.3   75.11  4968.1   75.57  4973.2   71.95  4991.2   64.79  4998.6   64.42
  5001.3   63.92  5004.6   64.42  5009.3   65.22  5014.4   76.05    5047   76.55
  5099.6   81.39  5115.6   82.01  5184.8   87.44  5217.4   91.43    5234   90.81
#Mann= 6 ,-1 , 0
  4207.9     .05       0  4660.5      .1       0  4822.2     .16       0
  4998.6     .07       0  5004.6     .16       0  5115.6     .05       0
Bank Sta=4998.6,5004.6
XS Rating Curve= 0 ,0
Exp/Cntr=0.3,0.1

Type RM Length L Ch R = 1 ,6605    ,389,389,389
BEGIN DESCRIPTION:
UNT036 IN BACR 14.0
END DESCRIPTION:
XS GIS Cut Line= 4
      2332564.18     13197021.39      2332887.72     13196696.85
      2332970.43     13196307.84       2332840.2     13196068.21
#Sta/Elev= 30
  4381.4  106.61  4390.7   106.1  4466.3  101.04  4673.9   88.56  4715.7   85.75
  4832.6   81.37  4849.9   85.52  4859.4   89.87  4864.5   82.64  4870.3   82.78
  4880.6   78.08  4972.6   73.58    4990   66.16  4992.8   65.66    4996   66.16
  5008.2   66.45  5033.9   71.59  5057.8   73.23    5085   79.16  5107.4   75.29
  5125.9   75.36  5240.8   81.39  5248.9   82.96  5314.4   85.14    5353   84.53
  5423.7   84.33    5445   85.71  5477.5    87.9  5483.5   89.68  5510.1   90.14
#Mann= 9 ,-1 , 0
  4381.4     .05       0  4390.7      .1       0  4466.3     .05       0
  4673.9      .1       0  4715.7     .05       0    4990    .035       0
    4996     .05       0    5353     .16       0    5445     .05       0
Bank Sta=4990,4996
XS Rating Curve= 0 ,0
Exp/Cntr=0.3,0.1

Type RM Length L Ch R = 1 ,6216    ,200,200,200
BEGIN DESCRIPTION:
UNT036 IN BACR 13.0
END DESCRIPTION:
XS GIS Cut Line= 3
      2333426.17     13196888.59        2333322.     13196607.32
       2332985.7     13196191.28
#Sta/Elev= 30
  4662.6  111.53  4701.6  108.38  4835.1   92.27  4888.4   80.52  4909.7   78.69
  4987.8   77.78  4994.2   72.09  5001.7   75.55  5008.6   77.31  5015.1   76.07
    5023   77.15  5029.4   72.01  5037.4   76.15  5043.8   73.12  5051.8    75.1
  5058.2   72.88    5066   75.27    5079   75.27  5093.4   79.27  5101.4   78.28
  5107.8   79.81  5115.7   75.03  5136.6   75.08  5147.9   71.08  5150.7   70.58
  5153.9   71.08  5200.5   73.48    5258   74.16  5328.4   78.98  5497.5   86.29
#Mann= 3 ,-1 , 0
  4662.6     .05       0  5147.9    .035       0  5153.9     .05       0
#XS Ineff= 2 , 0
                         5107.95           79.82
Permanent Ineff=
       F       F
Bank Sta=4987.8,5001.7
XS Rating Curve= 0 ,0
Exp/Cntr=0.3,0.1

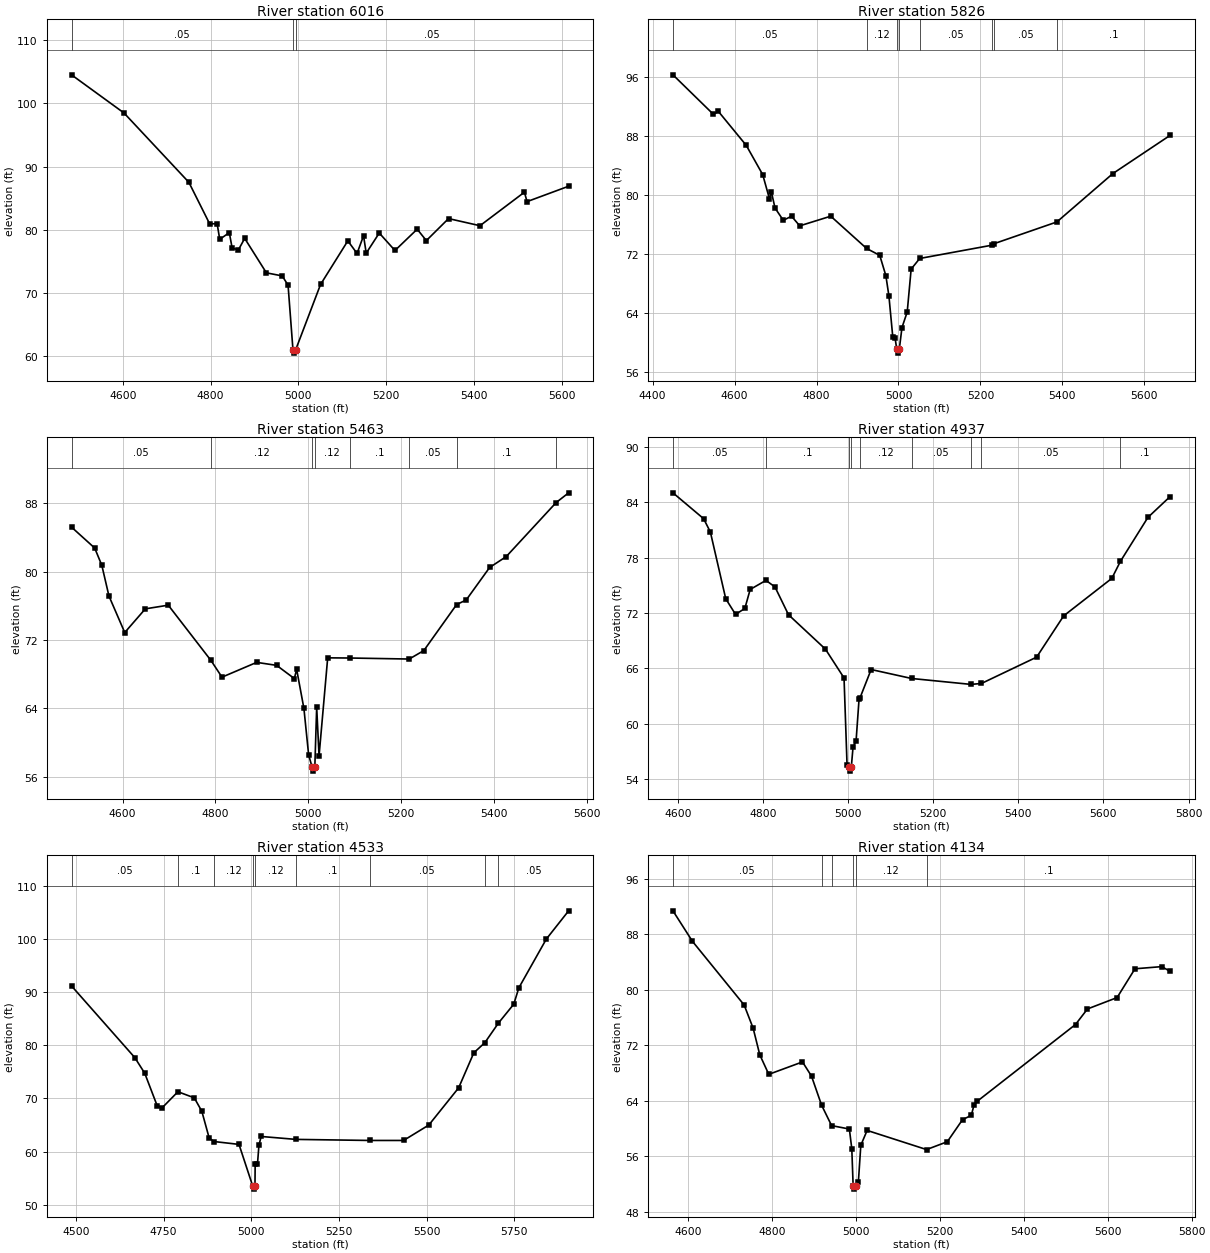
Type RM Length L Ch R = 1 ,6016    ,190,190,190
BEGIN DESCRIPTION:
UNT036 IN BACR 12.0
END DESCRIPTION:
XS GIS Cut Line= 4
      2333654.51      13196952.9      2333621.51     13196625.48
       2333441.3     13196468.11      2332978.23      13196145.5
#Sta/Elev= 30
  4483.3  104.54  4602.9   98.49  4750.7    87.5  4798.1   80.91  4815.1   80.94
    4821   78.46  4842.8   79.52  4849.4   77.05  4863.7   76.81  4877.9   78.61
  4927.3   73.15  4963.4   72.66  4976.7   71.19  4987.9   60.92  4990.6   60.42
  4993.9   60.92  5050.7    71.3  5112.9   78.22  5133.9   76.22  5148.7   79.03
  5154.8   76.27  5184.5   79.46  5220.3   76.69  5270.9   80.07  5291.8   78.26
  5342.4   81.75    5414   80.62  5515.2   85.93  5521.3   84.44    5616   86.88
#Mann= 3 ,-1 , 0
  4483.3     .05       0  4987.9     .04       0  4993.9     .05       0
Bank Sta=4987.9,4993.9
XS Rating Curve= 0 ,0
Exp/Cntr=0.3,0.1

Type RM Length L Ch R = 1 ,5826    ,363,363,363
BEGIN DESCRIPTION:
UNT036 IN BACR 11.0
END DESCRIPTION:
XS GIS Cut Line= 4
      2333761.12     13196945.34      2333733.19      13196587.4
      2333601.21     13196320.89      2333174.81     13195963.02
#Sta/Elev= 30
  4449.6    96.3  4548.4   90.94  4560.5   91.34  4628.6   86.73  4668.7   82.77
    4685   79.52    4690   80.37  4698.8   78.24  4718.9   76.58    4739   77.14
    4759   75.83  4834.7   77.14  4922.1   72.77  4954.3   71.83  4969.2   69.08
  4976.6   66.35  4986.1   60.76  4991.7   60.61  4995.9   59.08  4998.7   58.58
  5001.9   59.08  5008.5   62.04  5021.3   64.16  5030.9   69.97  5051.8   71.41
  5227.1    73.2  5234.1   73.43  5386.5   76.36  5523.2   82.92  5662.7   88.09
#Mann= 8 ,-1 , 0
  4449.6     .05       0  4922.1     .12       0  4995.9     .07       0
  5001.9     .12       0  5051.8     .05       0  5227.1      .1       0
  5234.1     .05       0  5386.5      .1       0
Bank Sta=4995.9,5001.9
XS Rating Curve= 0 ,0
Exp/Cntr=0.3,0.1

Type RM Length L Ch R = 1 ,5463    ,526,526,526
BEGIN DESCRIPTION:
Mapping XS 28c3e50a
END DESCRIPTION:
XS GIS Cut Line= 3
      2333959.08     13196965.64      2334027.62     13196645.78
       2333862.9     13195920.99
#Sta/Elev= 30
    4490   85.21  4539.9   82.76  4555.2   80.75  4570.6   77.15  4604.6   72.88
  4648.9   75.65  4698.3   76.08  4790.3   69.61    4814   67.66  4888.7   69.39
  4931.7   69.04  4969.7    67.5  4974.8   68.56  4990.4      64  5000.6   58.55
  5007.9   57.17  5010.6   56.67  5013.9   57.17  5017.9   64.15    5023   58.45
  5041.6   69.92  5089.2    69.9  5217.1   69.78  5248.6   70.77  5319.2   76.15
  5339.9   76.69  5390.3   80.49    5426   81.76  5533.5   88.08  5560.4   89.22
#Mann= 8 ,-1 , 0
    4490     .05       0  4790.3     .12       0  5007.9     .07       0
  5013.9     .12       0  5089.2      .1       0  5217.1     .05       0
  5319.2      .1       0  5533.5     .05       0
Bank Sta=5007.9,5013.9
XS Rating Curve= 0 ,0
Exp/Cntr=0.3,0.1

Type RM Length L Ch R = 1 ,4937    ,404,404,404
BEGIN DESCRIPTION:
UNT036 IN BACR 10.0
END DESCRIPTION:
XS GIS Cut Line= 3
      2333999.52       13197037.      2334337.72     13196846.85
      2334888.37     13196293.98
#Sta/Elev= 30
  4588.3   85.01  4660.4   82.21  4676.3   80.76  4712.4   73.54  4735.4   71.85
  4757.3   72.49  4769.8   74.55  4806.9   75.53  4828.1   74.82  4859.9   71.81
  4946.6   68.09  4990.4   64.97  4997.5   55.55  5001.6   55.38  5004.3   54.88
  5007.6   55.38  5011.6    57.5  5018.7   58.14  5025.8   62.74  5028.1   62.83
  5054.1   65.88  5149.2   64.91  5288.7   64.27  5313.3   64.37    5443   67.22
  5506.6   71.69  5619.8   75.75  5639.8   77.58  5704.6   82.35  5756.6    84.6
#Mann= 9 ,-1 , 0
  4588.3     .05       0  4806.9      .1       0  5001.6     .07       0
  5007.6      .1       0  5028.1     .12       0  5149.2     .05       0
  5288.7      .1       0  5313.3     .05       0  5639.8      .1       0
Bank Sta=5001.6,5007.6
XS Rating Curve= 0 ,0
Exp/Cntr=0.3,0.1

Type RM Length L Ch R = 1 ,4533    ,399,399,399
BEGIN DESCRIPTION:
UNT036 IN BACR 9.0
END DESCRIPTION:
XS GIS Cut Line= 3
      2334277.32     13197481.42      2334637.72     13197096.85
      2335187.73     13196396.84
#Sta/Elev= 30
  4487.3   91.16  4667.8   77.68  4696.1   74.74  4731.3   68.67  4745.5   68.24
  4790.7   71.27  4837.3   70.12  4858.8    67.6  4879.8   62.56  4893.3   61.91
  4964.8   61.37  5004.3   53.46    5007   52.96  5010.3   53.46  5010.9   57.71
  5017.5   57.71  5021.6   61.17  5027.9   62.86    5127   62.31  5337.3   62.11
    5434   62.11    5506   65.01    5591      72  5634.3   78.59  5665.7   80.49
  5704.5   84.18  5748.2   87.73  5762.7   90.81    5841   99.97  5904.6  105.28
#Mann= 9 ,-1 , 0
  4487.3     .05       0  4790.7      .1       0  4893.3     .12       0
  5004.3     .07       0  5010.3     .12       0    5127      .1       0
  5337.3     .05       0  5665.7      .1       0  5704.5     .05       0
Bank Sta=5004.3,5010.3
XS Rating Curve= 0 ,0
Exp/Cntr=0.3,0.1

Type RM Length L Ch R = 1 ,4134    ,148,148,148
BEGIN DESCRIPTION:
UNT036 IN BACR 8.0
END DESCRIPTION:
XS GIS Cut Line= 3
      2334443.93     13197675.91      2334837.72     13197446.85
      2335394.01     13196975.64
#Sta/Elev= 30
  4563.9   91.37  4610.3   86.98  4733.6    77.8  4755.1   74.44  4770.8   70.63
  4792.3   67.81  4872.6    69.6  4894.1   67.55  4918.1   63.37    4942   60.42
  4984.3   59.93  4990.1    57.1  4993.3   51.77  4996.1   51.27  4999.3   51.77
  5005.8   52.32  5011.6   57.58  5026.6   59.73  5168.3   56.97  5217.7    58.1
    5254   61.28  5274.9    61.9  5281.6   63.45  5289.2   63.94  5523.2   74.99
  5551.7   77.23  5622.3   78.87  5664.9   83.02  5728.6   83.33  5748.5   82.66
#Mann= 6 ,-1 , 0
  4563.9     .05       0  4918.1      .1       0    4942     .12       0
  4993.3     .07       0  4999.3     .12       0  5168.3      .1       0
Bank Sta=4993.3,4999.3
XS Rating Curve= 0 ,0
Exp/Cntr=0.3,0.1

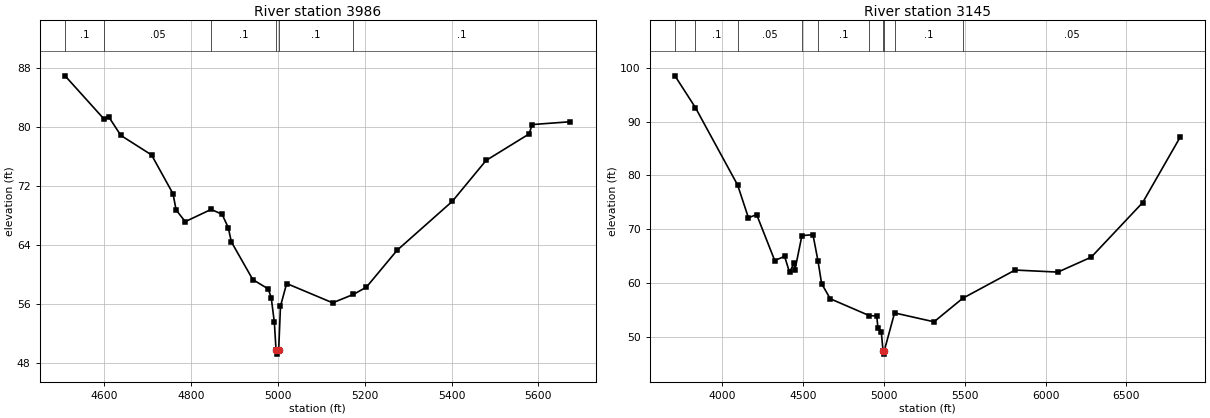
Type RM Length L Ch R = 1 ,3986    ,841,841,841
BEGIN DESCRIPTION:
UNT036 IN BACR 7.0
END DESCRIPTION:
XS GIS Cut Line= 2
      2334548.09     13197918.98      2335388.41     13197113.38
#Sta/Elev= 30
  4509.3   86.99  4599.2   81.12  4609.5   81.47  4637.8   78.91  4708.6   76.26
  4758.1   70.99  4765.2    68.8  4786.2   67.21  4845.9   68.87  4871.1   68.21
  4885.3   66.41  4892.5   64.47  4941.9   59.35  4977.4   58.09  4984.4   56.89
  4991.6   53.54  4995.5   49.74  4998.3   49.24  5001.5   49.74  5005.7   55.74
  5019.9   58.82  5125.9    56.2  5173.7   57.34  5203.6   58.32  5274.3   63.32
  5401.7   69.97  5479.4   75.51  5578.4    79.1  5585.7   80.38  5673.4   80.76
#Mann= 6 ,-1 , 0
  4509.3      .1       0  4599.2     .05       0  4845.9      .1       0
  4995.5     .07       0  5001.5      .1       0  5173.7      .1       0
Bank Sta=4995.5,5001.5
XS Rating Curve= 0 ,0
Exp/Cntr=0.3,0.1

Type RM Length L Ch R = 1 ,3145    ,0,0,0
BEGIN DESCRIPTION:
UNT036 IN BACR 1.0
END DESCRIPTION:
XS GIS Cut Line= 4
      2334341.09     13198099.48      2335332.85     13198280.06
       2336013.4     13197557.84      2335548.12     13196536.99
#Sta/Elev= 30
  3709.8    98.5    3836   92.61  4097.5    78.2  4163.8   72.14  4214.6   72.74
  4326.4   64.21  4387.4   64.98  4417.9   62.02    4446   63.74  4451.1   62.43
  4494.4   68.84  4562.8      69  4593.6   64.17  4616.2   59.92  4669.5   57.11
  4911.5   53.97  4956.9   53.93  4964.1   51.73  4985.2   50.88  4996.3   47.33
  4999.1   46.83  5002.3   47.33  5067.1   54.48  5310.9   52.83    5488   57.19
    5812   62.44  6076.5   62.06  6282.8   64.84    6600   74.95  6832.1   87.11
#Mann= 10 ,-1 , 0
  3709.8     .05       0    3836      .1       0  4097.5     .05       0
  4494.4     .08       0  4593.6      .1       0  4911.5     .12       0
  4996.3     .07       0  5002.3     .12       0  5067.1      .1       0
    5488     .05       0
Bank Sta=4996.3,5002.3
XS Rating Curve= 0 ,0
Exp/Cntr=0.3,0.1

Chan Stop Cuts=-1
Use User Specified Reach Order=0
Composite Channel Slope=5