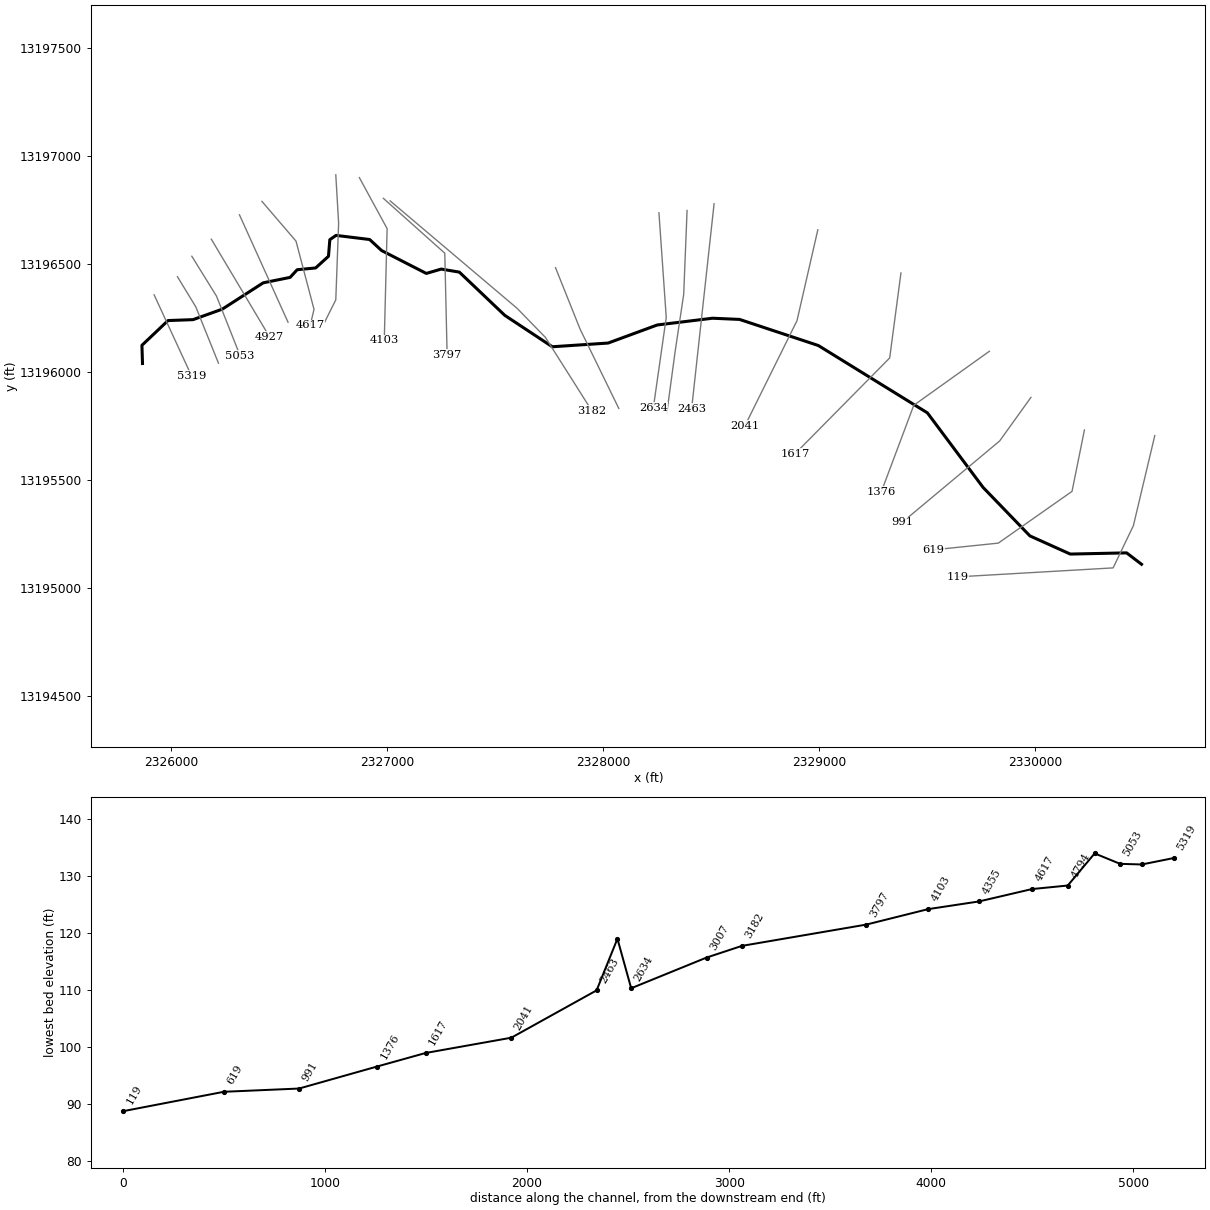
--- UNT037 IN BACR.prj (project) ---

Proj Title=UNT037 IN BACR Base Level Engineering
Current Plan=p01
Default Exp/Contr=0.3,0.1
English Units
Geom File=g01
Flow File=f01
Plan File=p01
Y Axis Title=Elevation
X Axis Title(PF)=Main Channel Distance
X Axis Title(XS)=Station
BEGIN DESCRIPTION:
UNT037 IN BACR
END DESCRIPTION:
DSS Export Rating Curves= 0
DSS Export Rating Curve Sorted= 0
DSS Export Volume Flow Curves= 0
DXF OffsetX= 0
DXF OffsetY= 0
DXF ScaleX= 1
DXF ScaleY= 10

--- UNT037 IN BACR.p01 (plan) ---

Plan Title=Multiple Run
Short Identifier=Multiple
Geom File=g01
Flow File=f01
Subcritical Flow
K Sum by GR= 0
Std Step Tol= 0.01
Critical Tol= 0.01
Num of Std Step Trials= 20
Max Error Tol= 0.3
Flow Tol Ratio= 0.001
Split Flow NTrial= 30
Split Flow Tol= 0.02
Split Flow Ratio= 0.02
Log Output Level= 0
Friction Slope Method= 1
Unsteady Friction Slope Method= 2
Unsteady Bridges Friction Slope Method= 1
Parabolic Critical Depth
Global Vel Dist=  1 , 1 , 1
Global Log Level= 0
CheckData=True
Encroach Param= -1, 0, 0, 0
BEGIN DESCRIPTION:
Multiple Run
END DESCRIPTION:

--- UNT037 IN BACR.f01 (steady flow) ---

Flow Title=Multiple
Program Version=4.10
Number of Profiles= 7
Profile Names=10-year,25-year,50-year,1pct_min,100-year,1pct_plu,500-year
River Rch & RM=UNT037 IN BACR,Reach-1         ,5319
     411     558     676     598     809    1094    1160
River Rch & RM=UNT037 IN BACR,Reach-1         ,4103
     450     614     745     661     894    1209    1291
River Rch & RM=UNT037 IN BACR,Reach-1         ,3007
     542     750     921     826    1116    1510    1646
Boundary for River Rch & Prof#=UNT037 IN BACR,Reach-1         , 1
Up Type= 0
Dn Type= 3
Dn Slope=0.005
Boundary for River Rch & Prof#=UNT037 IN BACR,Reach-1         , 2
Up Type= 0
Dn Type= 3
Dn Slope=0.005
Boundary for River Rch & Prof#=UNT037 IN BACR,Reach-1         , 3
Up Type= 0
Dn Type= 3
Dn Slope=0.005
Boundary for River Rch & Prof#=UNT037 IN BACR,Reach-1         , 4
Up Type= 0
Dn Type= 3
Dn Slope=0.005
Boundary for River Rch & Prof#=UNT037 IN BACR,Reach-1         , 5
Up Type= 0
Dn Type= 3
Dn Slope=0.005
Boundary for River Rch & Prof#=UNT037 IN BACR,Reach-1         , 6
Up Type= 0
Dn Type= 3
Dn Slope=0.005
Boundary for River Rch & Prof#=UNT037 IN BACR,Reach-1         , 7
Up Type= 0
Dn Type= 3
Dn Slope=0.005
DSS Import GetInterval= 0
DSS Import GetPeak= 0
DSS Import FillOption= 0

--- UNT037 IN BACR.g01 (geometry) ---

Geom Title=Existing Conditions
Program Version=4.10

River Reach=UNT037 IN BACR  ,Reach-1
Reach XY= 30
      2325869.04     13196040.13      2325866.43     13196124.33
      2325987.09     13196238.91      2326103.16     13196243.14
      2326238.34     13196291.75      2326427.69     13196413.51
      2326552.01     13196438.59      2326584.67     13196474.11
      2326670.15     13196482.34       2326729.6     13196536.31
      2326735.83     13196613.12      2326764.47     13196632.95
      2326920.06     13196613.88      2326975.46     13196562.82
      2327182.34     13196456.92      2327251.16     13196477.05
       2327335.1     13196463.05      2327545.29     13196263.05
      2327765.19     13196117.68      2328023.53     13196134.81
      2328250.65     13196218.43      2328506.44     13196249.68
      2328631.76     13196244.15      2328996.26     13196123.33
      2329500.73     13195811.87       2329758.3     13195467.01
      2329975.04     13195242.53      2330161.95     13195158.42
       2330422.6     13195163.97      2330491.58      13195111.2

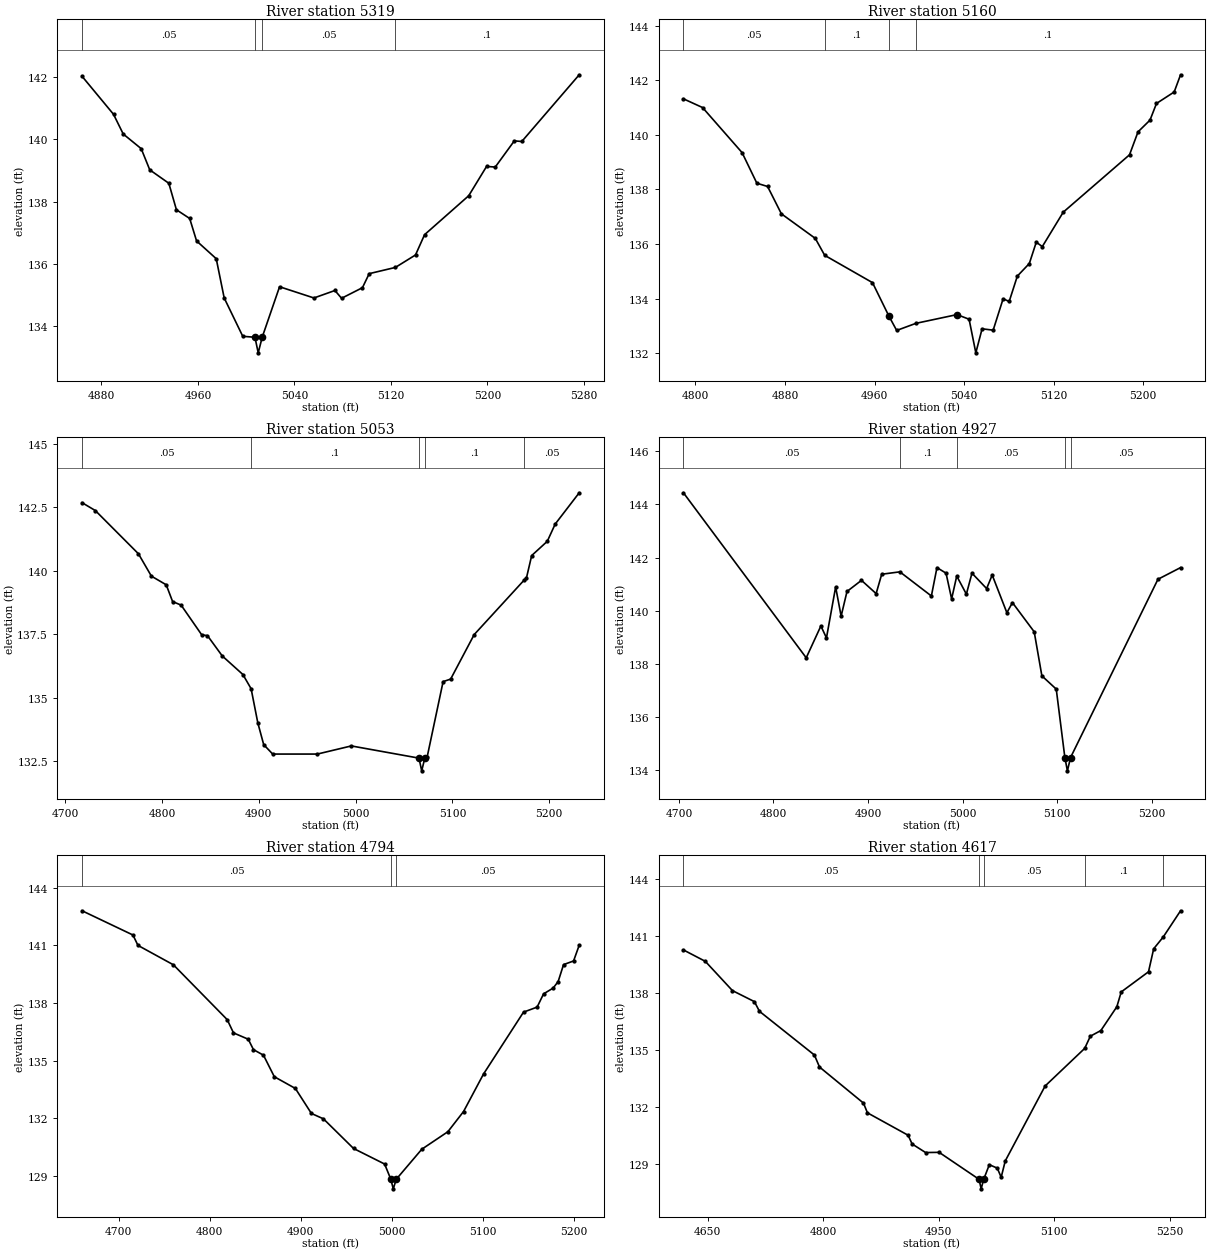
Type RM Length L Ch R = 1 ,5319    ,159,159,159
BEGIN DESCRIPTION:
UNT037 IN BACR 11.0
END DESCRIPTION:
XS GIS Cut Line= 2
      2325922.86     13196357.82      2326095.61     13195983.68
#Sta/Elev= 30
    4864  142.02  4890.1   140.8  4898.1  140.17    4913   139.7  4920.1  139.02
  4935.9  138.59  4942.2  137.74  4953.2  137.46  4958.9  136.74  4975.2  136.17
  4981.8  134.91  4997.2  133.68  5007.3  133.65    5010  133.15  5013.3  133.65
  5027.7  135.27  5056.2  134.91  5073.6  135.15  5079.1   134.9  5096.4  135.24
    5102  135.69  5123.7  135.89  5140.4  136.29  5147.9  136.94  5184.5  138.19
  5199.3  139.13  5206.5  139.11  5222.3  139.95  5228.5  139.93  5276.1  142.07
#Mann= 4 ,-1 , 0
    4864     .05       0  5007.3     .03       0  5013.3     .05       0
  5123.7      .1       0
Bank Sta=5007.3,5013.3
XS Rating Curve= 0 ,0
Exp/Cntr=0.3,0.1

Type RM Length L Ch R = 1 ,5160    ,107,107,107
BEGIN DESCRIPTION:
Mapping XS 07bf4e29
END DESCRIPTION:
XS GIS Cut Line= 3
      2326030.87     13196441.56      2326115.49      13196302.7
      2326220.59     13196041.57
#Sta/Elev= 30
  4789.3  141.32  4806.4     141  4841.7  139.35  4854.9  138.23  4864.5  138.11
  4876.8  137.11  4907.1  136.21  4915.5  135.59  4958.2  134.59  4972.8  133.37
  4979.8  132.84    4997   133.1  5033.7  133.42  5044.5  133.25  5050.5  132.02
  5056.1   132.9    5066  132.85  5074.9     134  5080.3   133.9  5087.6  134.83
  5098.3  135.29  5104.5  136.07  5109.9  135.91  5128.6  137.17  5187.8  139.27
  5195.4  140.11  5206.1  140.54  5211.9  141.15  5227.7  141.57  5233.4   142.2
#Mann= 4 ,-1 , 0
  4789.3     .05       0  4915.5      .1       0  4972.8     .07       0
    4997      .1       0
Bank Sta=4972.8,5033.7
XS Rating Curve= 0 ,0
Exp/Cntr=0.3,0.1

Type RM Length L Ch R = 1 ,5053    ,126,126,126
BEGIN DESCRIPTION:
Mapping XS b4d24785
END DESCRIPTION:
XS GIS Cut Line= 3
      2326097.31     13196536.34      2326211.27     13196352.26
      2326320.82     13196076.19
#Sta/Elev= 30
  4717.5  142.68  4731.2  142.37  4775.7  140.67  4789.1  139.79  4804.4  139.45
    4811  138.79  4819.8  138.65  4841.1  137.48    4847  137.45  4862.3  136.65
  4883.6  135.92  4892.1  135.36    4899  134.02  4905.1  133.16  4914.4  132.79
  4960.5  132.79  4995.6  133.11  5065.5  132.63  5068.3  132.13  5071.5  132.63
  5073.9  132.67  5090.4  135.64  5098.2  135.74  5122.5  137.49    5174  139.63
  5176.5  139.72  5181.9   140.6    5198  141.16  5206.2  141.84    5231  143.07
#Mann= 5 ,-1 , 0
  4717.5     .05       0  4892.1      .1       0  5065.5     .07       0
  5071.5      .1       0    5174     .05       0
Bank Sta=5065.5,5071.5
XS Rating Curve= 0 ,0
Exp/Cntr=0.3,0.1

Type RM Length L Ch R = 1 ,4927    ,133,133,133
BEGIN DESCRIPTION:
Mapping XS a500d1e8
END DESCRIPTION:
XS GIS Cut Line= 2
      2326187.48     13196615.33      2326456.57     13196163.95
#Sta/Elev= 30
  4704.8  144.44  4834.6  138.22  4850.1  139.42    4856  138.97  4865.7  140.89
  4871.5  139.79  4877.7  140.72    4893  141.14  4908.5  140.64  4914.4  141.37
  4933.6  141.46  4966.9  140.55  4972.8  141.62  4982.4  141.41  4988.3  140.44
  4993.7   141.3  5003.9  140.62  5009.8  141.41  5025.3  140.83  5031.2  141.34
  5046.7  139.92  5052.6   140.3  5075.6   139.2  5083.7  137.54  5098.9  137.04
    5108  134.46  5110.7  133.96    5114  134.46  5206.4  141.18  5230.3  141.62
#Mann= 5 ,-1 , 0
  4704.8     .05       0  4933.6      .1       0  4993.7     .05       0
    5108     .04       0    5114     .05       0
Bank Sta=5108,5114
XS Rating Curve= 0 ,0
Exp/Cntr=0.3,0.1

Type RM Length L Ch R = 1 ,4794    ,177,177,177
BEGIN DESCRIPTION:
Mapping XS 2c8f0b17
END DESCRIPTION:
XS GIS Cut Line= 2
       2326317.7     13196728.16      2326542.41      13196231.2
#Sta/Elev= 30
    4660  142.79  4715.8  141.53  4721.3  140.99  4760.2  139.98  4819.2  137.13
  4826.1  136.44  4842.3  136.11    4848  135.57    4859  135.28  4870.9  134.16
    4894  133.55  4911.6  132.25  4924.8  131.97  4957.8  130.43  4991.9  129.62
  4998.7  128.83  5001.4  128.33  5004.7  128.83  5032.7  130.39  5061.3   131.3
  5078.5  132.35  5100.4   134.3  5144.3  137.52  5159.2  137.78  5166.3  138.47
  5176.8  138.77  5182.3  139.11  5188.2  139.99  5199.2  140.18  5205.4     141
#Mann= 3 ,-1 , 0
    4660     .05       0  4998.7    .035       0  5004.7     .05       0
Bank Sta=4998.7,5004.7
XS Rating Curve= 0 ,0
Exp/Cntr=0.3,0.1

Type RM Length L Ch R = 1 ,4617    ,262,262,262
BEGIN DESCRIPTION:
Mapping XS c6eea562
END DESCRIPTION:
XS GIS Cut Line= 4
      2326421.63     13196790.42      2326579.36     13196606.41
      2326662.61     13196290.91      2326645.08     13196216.41
#Sta/Elev= 30
  4618.6  140.28    4647  139.68  4682.2  138.14  4710.7  137.56  4717.3  137.05
  4788.6  134.75  4795.2  134.12  4852.3  132.22  4857.4  131.71  4910.2  130.53
  4915.4  130.07  4932.9  129.62  4950.5  129.63  5002.3  128.21    5005  127.71
  5008.3  128.21  5015.6  128.98  5025.9   128.8    5031  128.32  5036.3  129.18
    5088  133.12  5139.4   135.1  5146.7  135.74  5160.4  136.04  5181.1  137.29
  5186.8  138.07  5222.2  139.13  5228.9  140.34  5241.3  140.96  5263.8  142.34
#Mann= 5 ,-1 , 0
  4618.6     .05       0  5002.3    .035       0  5008.3     .05       0
  5139.4      .1       0  5241.3     .05       0
Bank Sta=5002.3,5008.3
XS Rating Curve= 0 ,0
Exp/Cntr=0.3,0.1

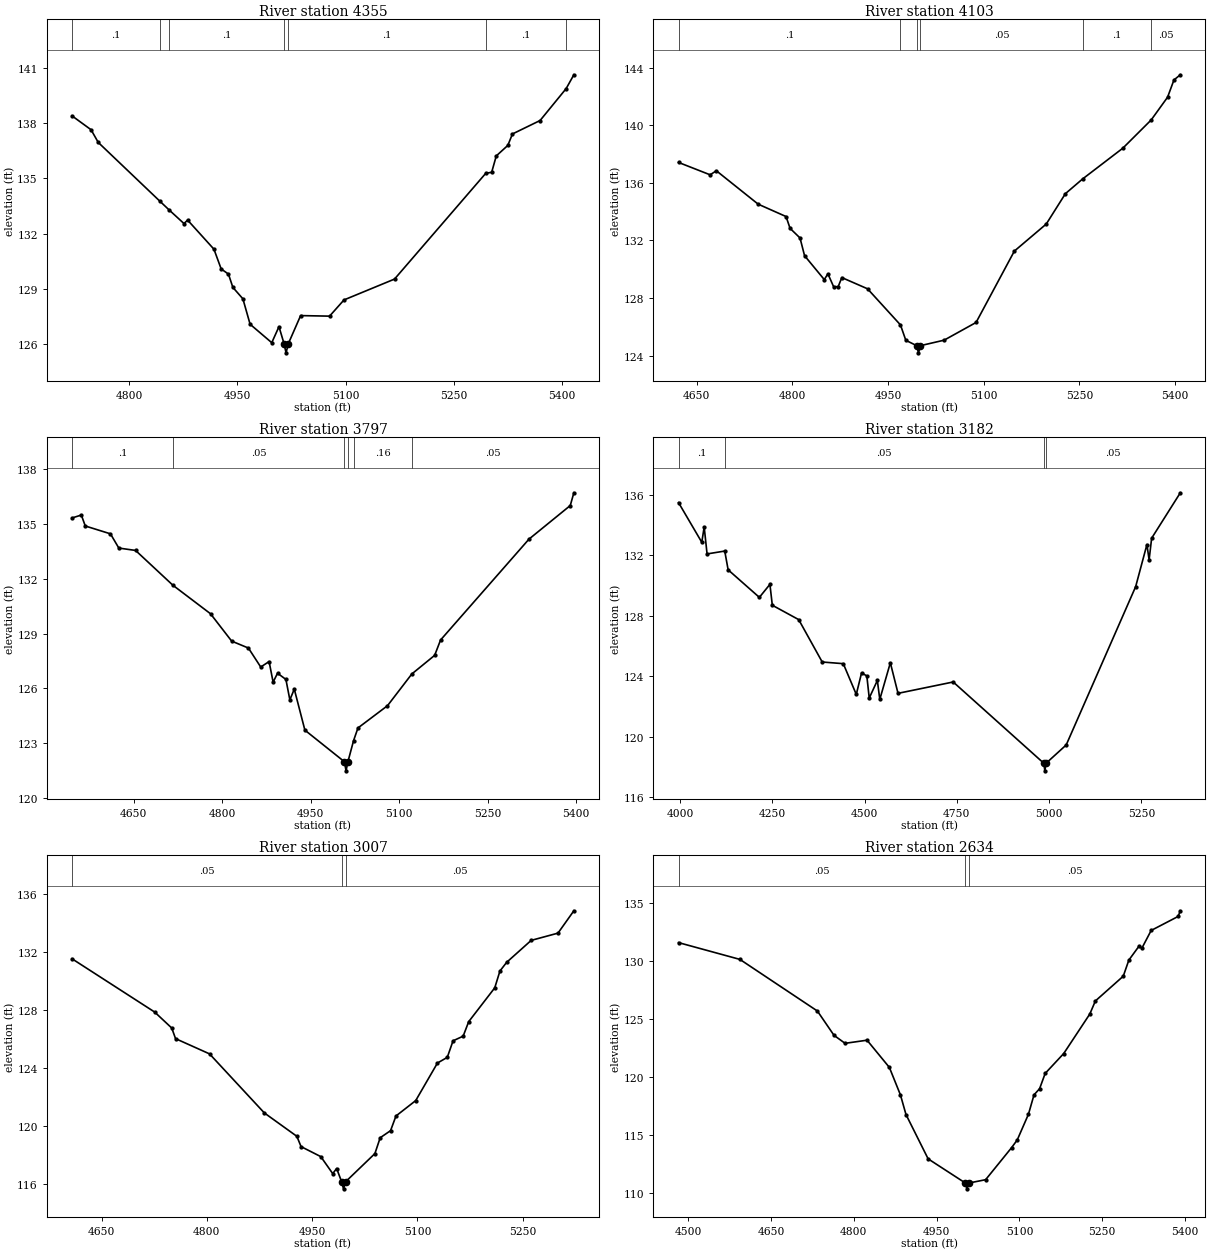
Type RM Length L Ch R = 1 ,4355    ,252,252,252
BEGIN DESCRIPTION:
UNT037 IN BACR 10.0
END DESCRIPTION:
XS GIS Cut Line= 4
       2326763.4     13196913.13      2326776.55     13196689.67
       2326763.4     13196334.73      2326711.41     13196230.74
#Sta/Elev= 30
    4721  138.39  4747.3  137.64  4757.3  136.95  4842.5  133.77  4855.2   133.3
  4876.1  132.55  4881.1  132.74  4917.6  131.16  4927.6  130.09  4937.7  129.81
  4943.8  129.09  4957.7  128.47  4967.7  127.09  4997.7  126.09  5007.7  126.96
  5014.7  126.04  5017.5  125.54  5020.7  126.04  5037.7  127.56  5077.8  127.53
  5097.8  128.41  5167.8  129.54  5294.3  135.28  5302.4  135.33  5308.8  136.22
  5324.8  136.79  5331.2  137.41  5369.5  138.14  5405.6  139.87  5416.3  140.62
#Mann= 7 ,-1 , 0
    4721      .1       0  4842.5     .05       0  4855.2      .1       0
  5014.7     .07       0  5020.7      .1       0  5294.3      .1       0
  5405.6     .05       0
Bank Sta=5014.7,5020.7
XS Rating Curve= 0 ,0
Exp/Cntr=0.3,0.1

Type RM Length L Ch R = 1 ,4103    ,306,306,306
BEGIN DESCRIPTION:
UNT037 IN BACR 9.0
END DESCRIPTION:
XS GIS Cut Line= 3
      2326872.44     13196900.36      2327000.93      13196664.2
      2326987.72     13196146.82
#Sta/Elev= 30
  4621.7  137.42  4671.2  136.56    4681  136.84  4746.5  134.52  4790.2  133.66
  4796.5  132.84  4812.1  132.17  4819.2  130.94  4850.1  129.28  4855.8  129.68
  4864.8  128.78  4871.9  128.79  4877.6  129.42  4917.9  128.64  4969.5  126.13
  4977.9  125.06  4994.9  124.69  4997.7  124.19  5000.9  124.69  5037.9  125.07
    5088   126.3    5148  131.26    5198  133.14    5228  135.25  5254.9  136.27
    5318  138.41  5362.4  140.37  5388.1  141.95  5398.1  143.15  5408.1  143.51
#Mann= 6 ,-1 , 0
  4621.7      .1       0  4969.5     .05       0  4994.9    .035       0
  5000.9     .05       0  5254.9      .1       0  5362.4     .05       0
Bank Sta=4994.9,5000.9
XS Rating Curve= 0 ,0
Exp/Cntr=0.3,0.1

Type RM Length L Ch R = 1 ,3797    ,615,615,615
BEGIN DESCRIPTION:
Mapping XS 601fc747
END DESCRIPTION:
XS GIS Cut Line= 3
      2326983.44     13196804.52      2327267.71     13196550.63
      2327278.54      13196080.8
#Sta/Elev= 30
  4545.3  135.34    4561   135.5  4567.7   134.9  4610.4  134.47  4624.6  133.69
    4653  133.56  4716.4  131.65  4780.1  130.09    4816  128.59  4844.4  128.21
  4865.3  127.17  4879.5  127.47  4886.3  126.34  4893.8  126.83    4908  126.49
  4914.7  125.37  4922.2  125.96  4940.2  123.71  5007.2  121.98    5010  121.48
  5013.2  121.98  5022.8  123.14  5030.2  123.83  5080.3  125.05  5121.6  126.79
  5160.3  127.81  5170.3  128.65  5320.3  134.18  5390.3  136.02  5396.4  136.72
#Mann= 6 ,-1 , 0
  4545.3      .1       0  4716.4     .05       0  5007.2    .035       0
  5013.2     .05       0  5022.8     .16       0  5121.6     .05       0
Bank Sta=5007.2,5013.2
XS Rating Curve= 0 ,0
Exp/Cntr=0.3,0.1

Type RM Length L Ch R = 1 ,3182    ,175,175,175
BEGIN DESCRIPTION:
UNT037 IN BACR 8.0
END DESCRIPTION:
XS GIS Cut Line= 4
      2327014.81     13196792.69      2327601.63     13196296.15
      2327733.57     13196160.73       2327948.4     13195821.16
#Sta/Elev= 30
  3996.1  135.47  4059.1  132.85  4065.6  133.86  4073.4  132.08  4121.3  132.27
  4130.5  131.03  4215.1  129.21  4243.7  130.07  4250.2  128.69  4321.7  127.74
  4385.4  124.94  4442.5  124.83  4477.7   122.8    4492  124.22  4506.3  124.02
  4512.8  122.56  4534.8  123.72  4541.4  122.47    4570  124.89  4590.8  122.87
  4740.3  123.62  4985.9  118.25  4988.6  117.75  4991.9  118.25  5046.5  119.46
  5234.7  129.92  5265.2   132.7  5271.1  131.69    5278  133.12  5355.7  136.12
#Mann= 4 ,-1 , 0
  3996.1      .1       0  4121.3     .05       0  4985.9    .035       0
  4991.9     .05       0
Bank Sta=4985.9,4991.9
XS Rating Curve= 0 ,0
Exp/Cntr=0.3,0.1

Type RM Length L Ch R = 1 ,3007    ,373,373,373
BEGIN DESCRIPTION:
UNT037 IN BACR 7.0
END DESCRIPTION:
XS GIS Cut Line= 3
      2327780.03     13196483.72      2327893.96     13196198.89
      2328072.93     13195832.21
#Sta/Elev= 30
    4608  131.55  4725.7  127.88    4750  126.78  4755.4  126.05  4803.8     125
  4881.9  120.93  4928.2  119.32  4934.2  118.61  4962.3  117.92  4979.3  116.75
  4984.9   117.1  4991.9   116.2  4994.7   115.7  4997.9   116.2  5039.4  118.13
  5046.9  119.22  5061.7  119.71  5069.4  120.72  5097.5  121.78  5128.5  124.37
  5142.5  124.76  5150.7   125.9  5165.1  126.22    5173  127.22  5210.1  129.55
  5217.5  130.71  5227.1  131.31    5262  132.82  5300.2  133.32  5322.8  134.86
#Mann= 3 ,-1 , 0
    4608     .05       0  4991.9    .035       0  4997.9     .05       0
Bank Sta=4991.9,4997.9
XS Rating Curve= 0 ,0
Exp/Cntr=0.3,0.1

Type RM Length L Ch R = 1 ,2634    ,68,68,68
BEGIN DESCRIPTION:
UNT037 IN BACR 6.0
END DESCRIPTION:
XS GIS Cut Line= 3
       2328258.6     13196737.66      2328292.45     13196253.33
      2328232.63     13195834.59
#Sta/Elev= 30
  4482.8  131.59  4593.9  130.14  4734.2  125.68  4764.3  123.58  4784.3  122.89
  4824.1  123.16  4864.5  120.81  4884.6  118.43  4894.6  116.74  4934.7  112.91
  5002.2  110.82  5004.9  110.32  5008.2  110.82  5038.8  111.11    5086  113.89
  5096.1  114.55  5116.3  116.76  5126.4  118.44  5136.5  118.97  5146.6  120.29
  5180.2  122.01  5227.4  125.42  5237.5  126.55    5288  128.69  5298.1  130.08
  5316.6  131.29  5321.7  131.11  5338.5  132.64  5387.3  133.85  5391.3  134.34
#Mann= 3 ,-1 , 0
  4482.8     .05       0  5002.2    .035       0  5008.2     .05       0
Bank Sta=5002.2,5008.2
XS Rating Curve= 0 ,0
Exp/Cntr=0.3,0.1

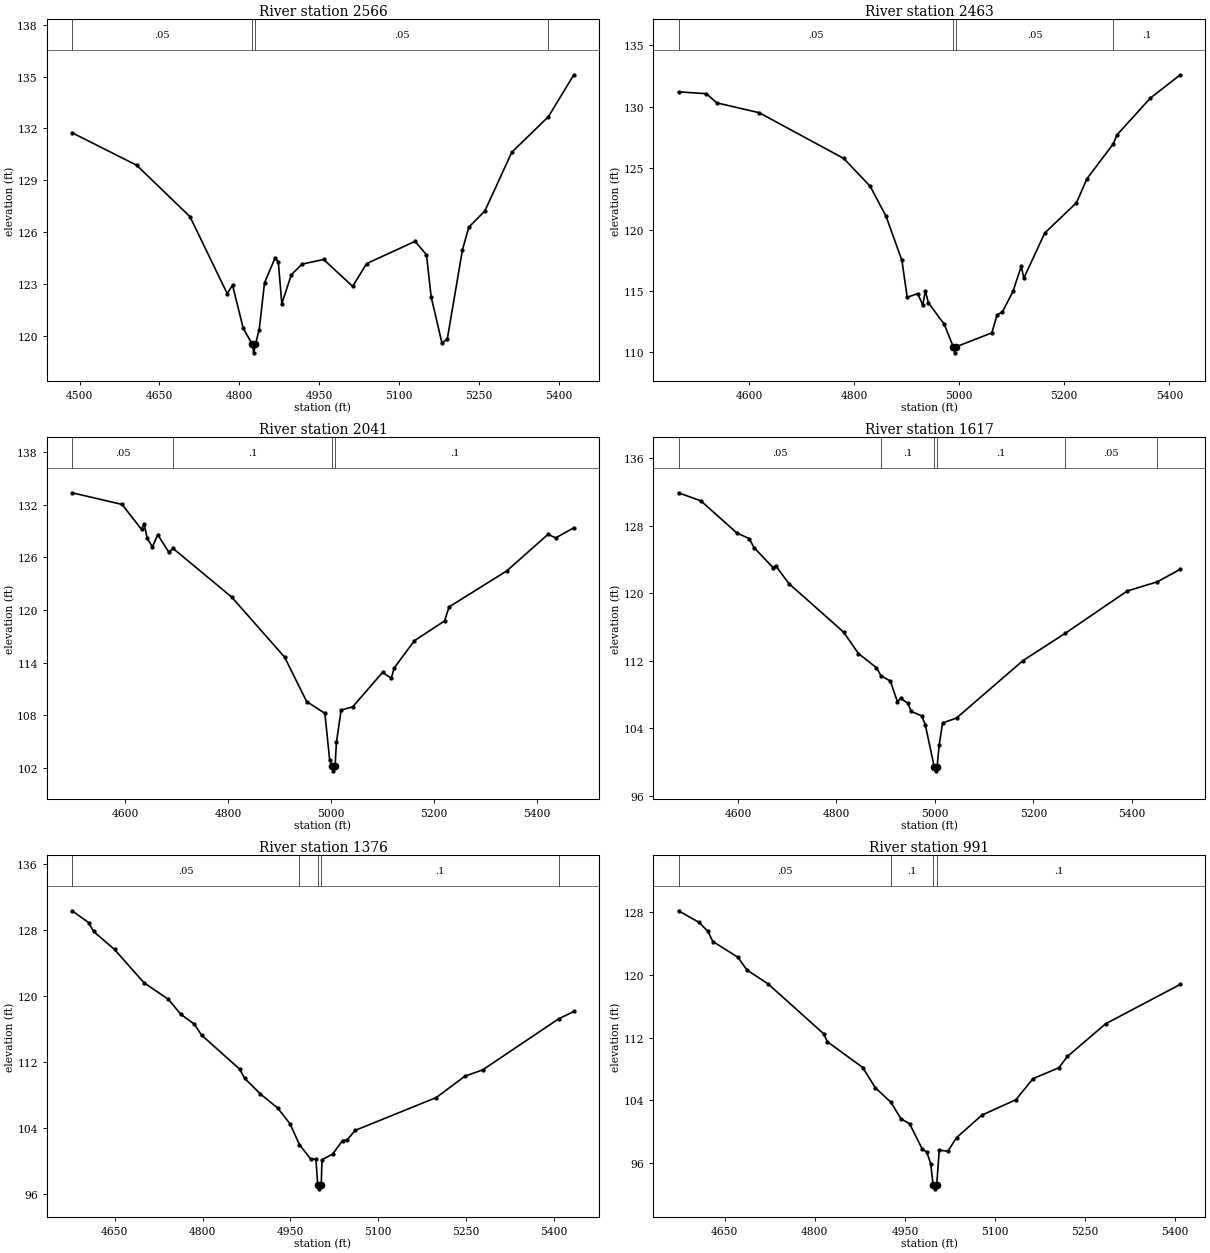
Type RM Length L Ch R = 1 ,2566    ,103,103,103
BEGIN DESCRIPTION:
Mapping XS eaf1a9eb
END DESCRIPTION:
XS GIS Cut Line= 4
      2328388.81     13196748.16      2328373.18      13196360.1
      2328334.12     13196099.68      2328295.14     13195811.21
#Sta/Elev= 30
  4485.9  131.75  4607.3  129.87  4707.4  126.89  4777.4  122.43  4787.4  122.92
  4807.5  120.42  4824.5   119.5  4827.2     119  4830.5   119.5  4837.5  120.34
  4847.5  123.06  4867.5  124.51  4873.4  124.27    4880  121.85  4897.8  123.52
    4918  124.14  4958.5  124.41  5013.1  122.85  5039.3  124.17  5130.4  125.46
  5151.8  124.68  5160.6  122.24  5180.8  119.57  5190.9   119.8  5219.4  124.97
  5231.3  126.28  5261.5  127.22    5312  130.62  5380.8  132.68  5428.7  135.11
#Mann= 4 ,-1 , 0
  4485.9     .05       0  4824.5    .035       0  4830.5     .05       0
  5380.8      .1       0
Bank Sta=4824.5,4830.5
XS Rating Curve= 0 ,0
Exp/Cntr=0.3,0.1

Type RM Length L Ch R = 1 ,2463    ,422,422,422
BEGIN DESCRIPTION:
Mapping XS ea2e051e
END DESCRIPTION:
XS GIS Cut Line= 2
      2328513.81     13196779.37      2328409.81     13195830.35
#Sta/Elev= 30
  4466.1  131.22  4518.9  131.07    4539  130.32  4619.5  129.52  4780.5  125.79
  4830.8  123.52    4861  121.07  4891.1  117.48  4901.2  114.47  4921.3  114.78
  4930.7  113.84  4935.7     115  4941.4  114.03  4971.6  112.28  4988.7  110.45
  4991.5  109.95  4994.7  110.45  5062.2  111.58  5072.2  113.04  5082.3  113.29
  5102.4  114.95  5118.1     117  5123.1  116.04  5162.8  119.71  5223.1  122.18
  5243.2  124.14  5293.4  126.99  5300.4  127.72    5364  130.72  5420.8  132.61
#Mann= 4 ,-1 , 0
  4466.1     .05       0  4988.7    .035       0  4994.7     .05       0
  5293.4      .1       0
Bank Sta=4988.7,4994.7
XS Rating Curve= 0 ,0
Exp/Cntr=0.3,0.1

Type RM Length L Ch R = 1 ,2041    ,424,424,424
BEGIN DESCRIPTION:
UNT037 IN BACR 5.0
END DESCRIPTION:
XS GIS Cut Line= 3
      2328993.84     13196658.97      2328897.44     13196238.32
      2328656.42     13195751.91
#Sta/Elev= 30
    4497  133.36  4594.1  132.03  4631.9  129.18    4637  129.84  4642.8  128.18
  4653.1  127.19  4663.3  128.59    4685  126.57  4693.2  127.01  4806.9  121.47
  4909.8  114.61  4952.5  109.55  4987.9  108.21  4997.2  102.89  5001.7  102.15
  5004.5  101.65  5007.7  102.15  5010.3  104.89  5019.5  108.58  5041.8  108.94
    5100  112.88  5116.9   112.2  5122.4  113.37  5161.7  116.49  5220.4  118.75
    5229  120.34  5341.1  124.45  5421.2  128.62  5436.3  128.22  5471.4  129.37
#Mann= 4 ,-1 , 0
    4497     .05       0  4693.2      .1       0  5001.7     .07       0
  5007.7      .1       0
Bank Sta=5001.7,5007.7
XS Rating Curve= 0 ,0
Exp/Cntr=0.3,0.1

Type RM Length L Ch R = 1 ,1617    ,241,241,241
BEGIN DESCRIPTION:
UNT037 IN BACR 4.0
END DESCRIPTION:
XS GIS Cut Line= 3
      2329378.39     13196459.07      2329326.31     13196065.83
       2328888.8     13195623.11
#Sta/Elev= 30
  4479.2  131.92  4524.6  130.96    4598  127.14  4622.7   126.5  4632.7  125.41
  4671.4  123.04  4676.4  123.28  4703.4  121.16  4814.3  115.42  4844.6  112.87
  4881.2  111.19  4890.5  110.24  4909.5   109.6  4923.6  107.18  4930.7  107.57
  4944.8  106.96  4951.9  106.01  4973.1  105.48  4980.2  104.46  4998.4   99.47
  5001.1   98.97  5004.4   99.47  5008.5  102.02  5015.5  104.64  5043.8  105.23
  5178.2  112.01  5264.1  115.25  5390.4  120.28  5451.6  121.37  5498.3  122.86
#Mann= 6 ,-1 , 0
  4479.2     .05       0  4890.5      .1       0  4998.4     .07       0
  5004.4      .1       0  5264.1     .05       0  5451.6      .1       0
Bank Sta=4998.4,5004.4
XS Rating Curve= 0 ,0
Exp/Cntr=0.3,0.1

Type RM Length L Ch R = 1 ,1376    ,385,385,385
BEGIN DESCRIPTION:
UNT037 IN BACR 3.0
END DESCRIPTION:
XS GIS Cut Line= 3
      2329787.69     13196096.83      2329437.72     13195846.85
      2329287.71     13195446.83
#Sta/Elev= 30
  4577.1   130.3  4605.3  128.87  4613.9  127.79  4649.6  125.61  4699.9  121.58
  4741.7  119.56  4762.6  117.77    4786  116.55  4798.3  115.23  4863.4   111.1
    4872  109.99    4899  108.08  4928.5  106.38  4949.4  104.48  4965.5  101.96
  4985.1  100.17  4993.7  100.21  4996.8   97.09  4999.6   96.59  5002.8   97.09
  5004.1  100.12  5022.3  100.81  5039.2  102.44  5047.2  102.53  5060.6  103.67
  5199.4  107.66  5248.4  110.25  5278.6  111.01  5408.4   117.2  5434.4  118.09
#Mann= 5 ,-1 , 0
  4577.1     .05       0  4965.5      .1       0  4996.8     .07       0
  5002.8      .1       0  5408.4     .05       0
Bank Sta=4996.8,5002.8
XS Rating Curve= 0 ,0
Exp/Cntr=0.3,0.1

Type RM Length L Ch R = 1 ,991     ,372,372,372
BEGIN DESCRIPTION:
UNT037 IN BACR 2.0
END DESCRIPTION:
XS GIS Cut Line= 3
      2329979.78     13195883.36      2329835.19     13195681.81
      2329383.87     13195304.98
#Sta/Elev= 30
  4572.9  128.18  4606.9  126.71  4621.6  125.58  4630.1  124.26    4672  122.25
  4686.7  120.64  4722.3  118.85  4814.7   112.5  4820.9  111.49  4879.8   108.2
  4900.6  105.64  4926.7  103.77  4943.6  101.66  4957.9  101.03  4978.7   97.85
  4986.5   97.41    4993   95.96    4997   93.24  4999.8   92.74    5003   93.24
  5007.3   97.67  5021.6   97.54    5036   99.26  5078.2  102.13  5134.9   104.1
  5163.5  106.79  5206.5  108.17  5220.8  109.61  5284.5  113.78  5408.9   118.8
#Mann= 4 ,-1 , 0
  4572.9     .05       0  4926.7      .1       0    4997     .07       0
    5003      .1       0
Bank Sta=4997,5003
XS Rating Curve= 0 ,0
Exp/Cntr=0.3,0.1

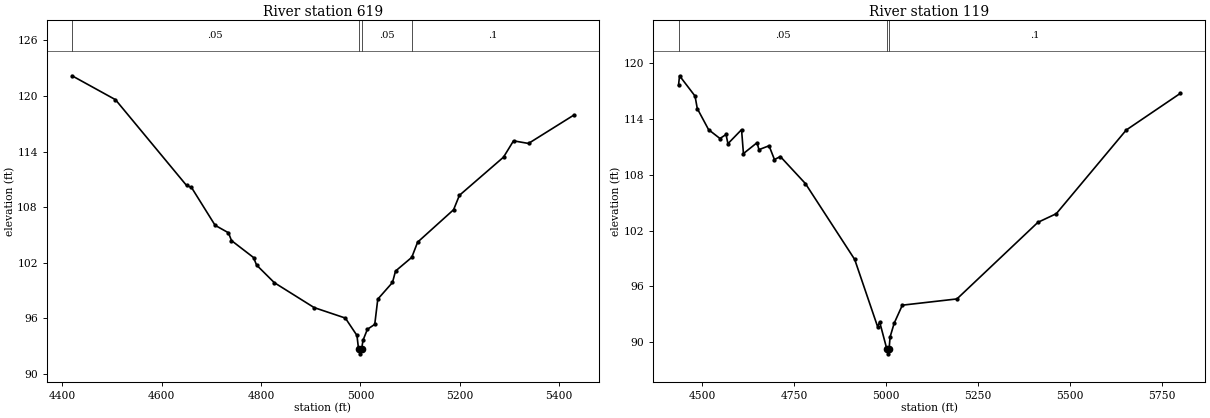
Type RM Length L Ch R = 1 ,619     ,500,500,500
BEGIN DESCRIPTION:
Mapping XS 630ca18d
END DESCRIPTION:
XS GIS Cut Line= 4
      2330227.35     13195732.49      2330170.06     13195448.64
      2329828.91     13195209.05      2329526.87     13195177.81
#Sta/Elev= 30
  4419.5  122.17  4506.9  119.59  4649.9  110.34  4659.9  110.12  4707.4  106.04
  4734.3  105.23  4740.4  104.39  4784.8  102.56  4790.9  101.75  4826.6   99.85
  4906.8   97.16  4969.6   96.03    4993   94.15  4996.2   92.67  4998.9   92.17
  5002.2   92.67  5005.3   93.65    5014   94.82  5028.8   95.35  5034.9   98.07
  5064.5   99.87  5070.6   101.1  5103.3  102.58  5115.1  104.22  5187.5  107.72
  5199.2  109.27    5288  113.39  5308.1  115.15  5338.3  114.87  5429.6  117.93
#Mann= 4 ,-1 , 0
  4419.5     .05       0  4996.2     .03       0  5002.2     .05       0
  5103.3      .1       0
Bank Sta=4996.2,5002.2
XS Rating Curve= 0 ,0
Exp/Cntr=0.3,0.1

Type RM Length L Ch R = 1 ,119     ,0,0,0
BEGIN DESCRIPTION:
UNT037 IN BACR 1.0
END DESCRIPTION:
XS GIS Cut Line= 4
      2330552.88     13195706.48      2330453.91     13195289.78
      2330360.16     13195094.47       2329640.8     13195052.92
#Sta/Elev= 30
  4434.9  117.62  4437.6  118.64  4479.8  116.46  4485.9  115.12  4516.7  112.85
  4547.6   111.9  4564.2  112.33  4569.3  111.34  4606.4  112.85  4611.5  110.28
  4648.6  111.45  4653.7   110.7  4681.2  111.12  4695.9  109.64    4712  109.96
  4780.3  107.05  4914.3    98.9  4976.7   91.67  4982.2   92.19  5001.8   89.26
  5004.6   88.76  5007.8   89.26  5010.6   90.57  5021.7   92.05  5043.9   93.99
  5192.5   94.66  5412.8  102.89  5462.9  103.82  5653.2  112.81  5800.4  116.75
#Mann= 3 ,-1 , 0
  4434.9     .05       0  5001.8     .03       0  5007.8      .1       0
Bank Sta=5001.8,5007.8
XS Rating Curve= 0 ,0
Exp/Cntr=0.3,0.1

Chan Stop Cuts=-1
Use User Specified Reach Order=0
Composite Channel Slope=5