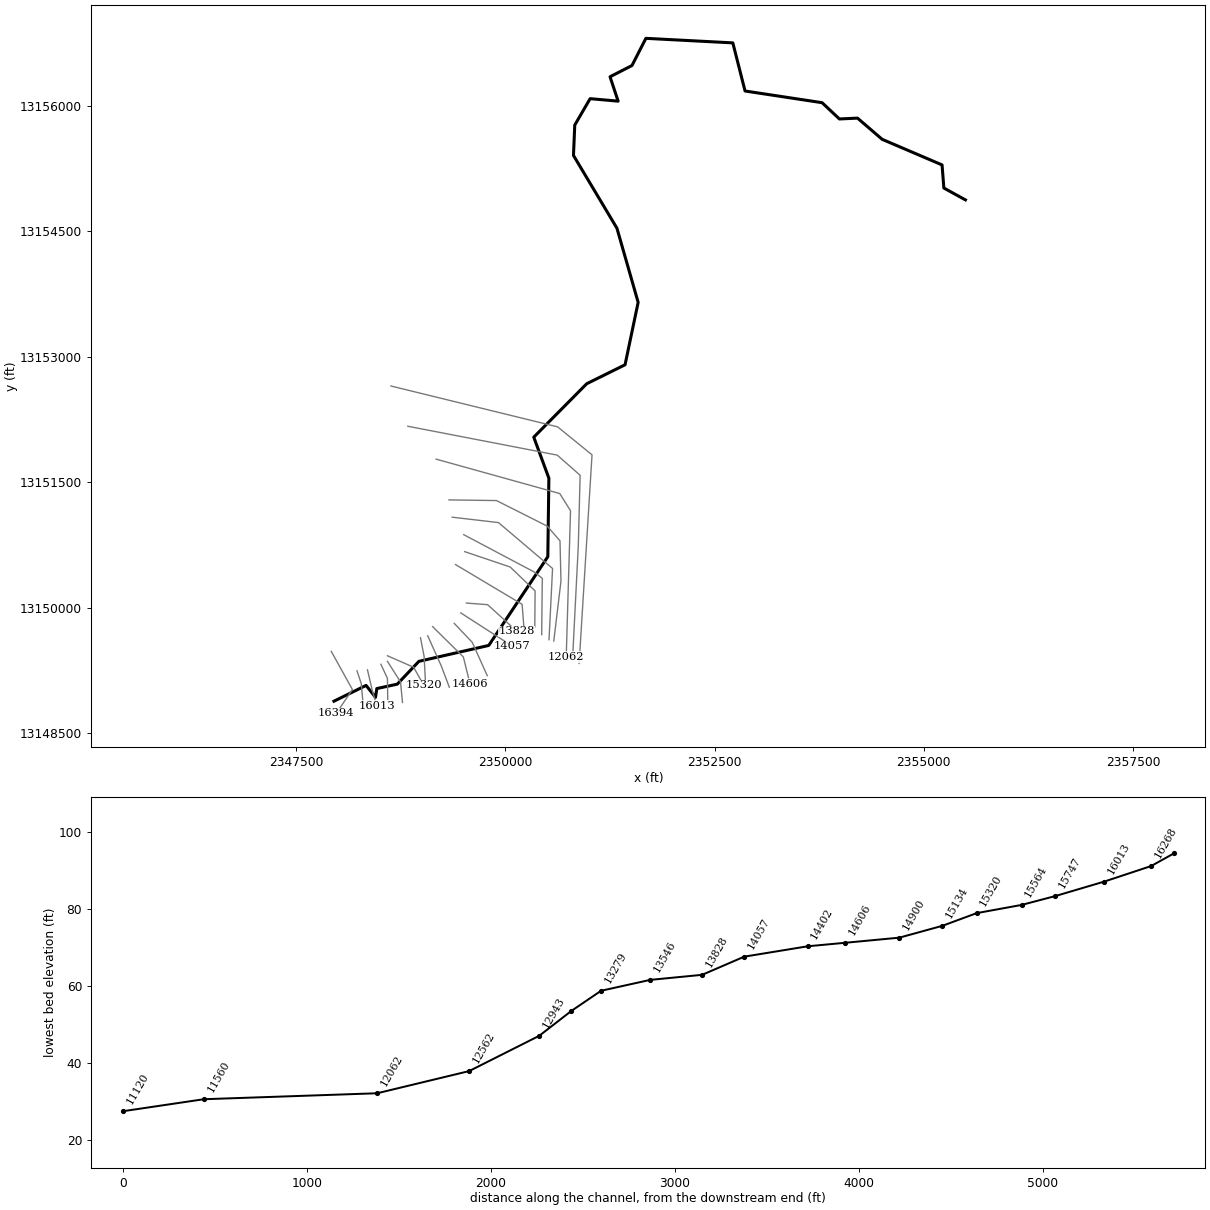
--- UNT038 IN BACR.prj (project) ---

Proj Title=UNT038 IN BACR Base Level Engineering
Current Plan=p01
Default Exp/Contr=0.3,0.1
English Units
Geom File=g01
Flow File=f01
Plan File=p01
Y Axis Title=Elevation
X Axis Title(PF)=Main Channel Distance
X Axis Title(XS)=Station
BEGIN DESCRIPTION:
UNT038 IN BACR
END DESCRIPTION:
DSS Export Rating Curves= 0
DSS Export Rating Curve Sorted= 0
DSS Export Volume Flow Curves= 0
DXF OffsetX= 0
DXF OffsetY= 0
DXF ScaleX= 1
DXF ScaleY= 10

--- UNT038 IN BACR.p01 (plan) ---

Plan Title=Multiple Run
Short Identifier=Multiple
Geom File=g01
Flow File=f01
Subcritical Flow
K Sum by GR= 0
Std Step Tol= 0.01
Critical Tol= 0.01
Num of Std Step Trials= 20
Max Error Tol= 0.3
Flow Tol Ratio= 0.001
Split Flow NTrial= 30
Split Flow Tol= 0.02
Split Flow Ratio= 0.02
Log Output Level= 0
Friction Slope Method= 1
Unsteady Friction Slope Method= 2
Unsteady Bridges Friction Slope Method= 1
Parabolic Critical Depth
Global Vel Dist=  1 , 1 , 1
Global Log Level= 0
CheckData=True
Encroach Param= -1, 0, 0, 0
BEGIN DESCRIPTION:
Multiple Run
END DESCRIPTION:

--- UNT038 IN BACR.f01 (steady flow) ---

Flow Title=Multiple
Program Version=4.10
Number of Profiles= 7
Profile Names=10-year,25-year,50-year,1pct_min,100-year,1pct_plu,500-year
River Rch & RM=UNT038 IN BACR,Reach-1         ,16394
     476     676     845     775    1048    1417    1628
Boundary for River Rch & Prof#=UNT038 IN BACR,Reach-1         , 1
Up Type= 0
Dn Type= 3
Dn Slope=0.005
Boundary for River Rch & Prof#=UNT038 IN BACR,Reach-1         , 2
Up Type= 0
Dn Type= 3
Dn Slope=0.005
Boundary for River Rch & Prof#=UNT038 IN BACR,Reach-1         , 3
Up Type= 0
Dn Type= 3
Dn Slope=0.005
Boundary for River Rch & Prof#=UNT038 IN BACR,Reach-1         , 4
Up Type= 0
Dn Type= 3
Dn Slope=0.005
Boundary for River Rch & Prof#=UNT038 IN BACR,Reach-1         , 5
Up Type= 0
Dn Type= 3
Dn Slope=0.005
Boundary for River Rch & Prof#=UNT038 IN BACR,Reach-1         , 6
Up Type= 0
Dn Type= 3
Dn Slope=0.005
Boundary for River Rch & Prof#=UNT038 IN BACR,Reach-1         , 7
Up Type= 0
Dn Type= 3
Dn Slope=0.005
DSS Import GetInterval= 0
DSS Import GetPeak= 0
DSS Import FillOption= 0

--- UNT038 IN BACR.g01 (geometry) ---

Geom Title=Existing Conditions
Program Version=4.10

River Reach=UNT038 IN BACR  ,Reach-1
Reach XY= 30
      2347949.79     13148885.62      2348333.89     13149074.26
      2348446.57     13148931.69      2348462.06     13149036.66
      2348706.67     13149089.33      2348965.42     13149362.01
      2349800.24     13149552.13      2350506.12     13150612.86
      2350518.69     13151551.39      2350338.23      13152041.5
      2350970.95     13152680.08       2351429.2     13152906.68
      2351585.82     13153652.95      2351332.11     13154539.24
      2350812.73     13155408.88       2350828.1      13155771.7
      2351011.83     13156087.44      2351346.58     13156057.64
       2351249.7     13156349.31       2351512.2     13156483.68
      2351678.35     13156808.51      2352717.37     13156754.25
      2352863.58     13156179.02      2353784.58     13156039.27
      2353991.18     13155844.82      2354207.78     13155854.92
      2354502.48     13155601.44       2355218.2     13155295.57
       2355239.9     13155019.33      2355497.66     13154877.44

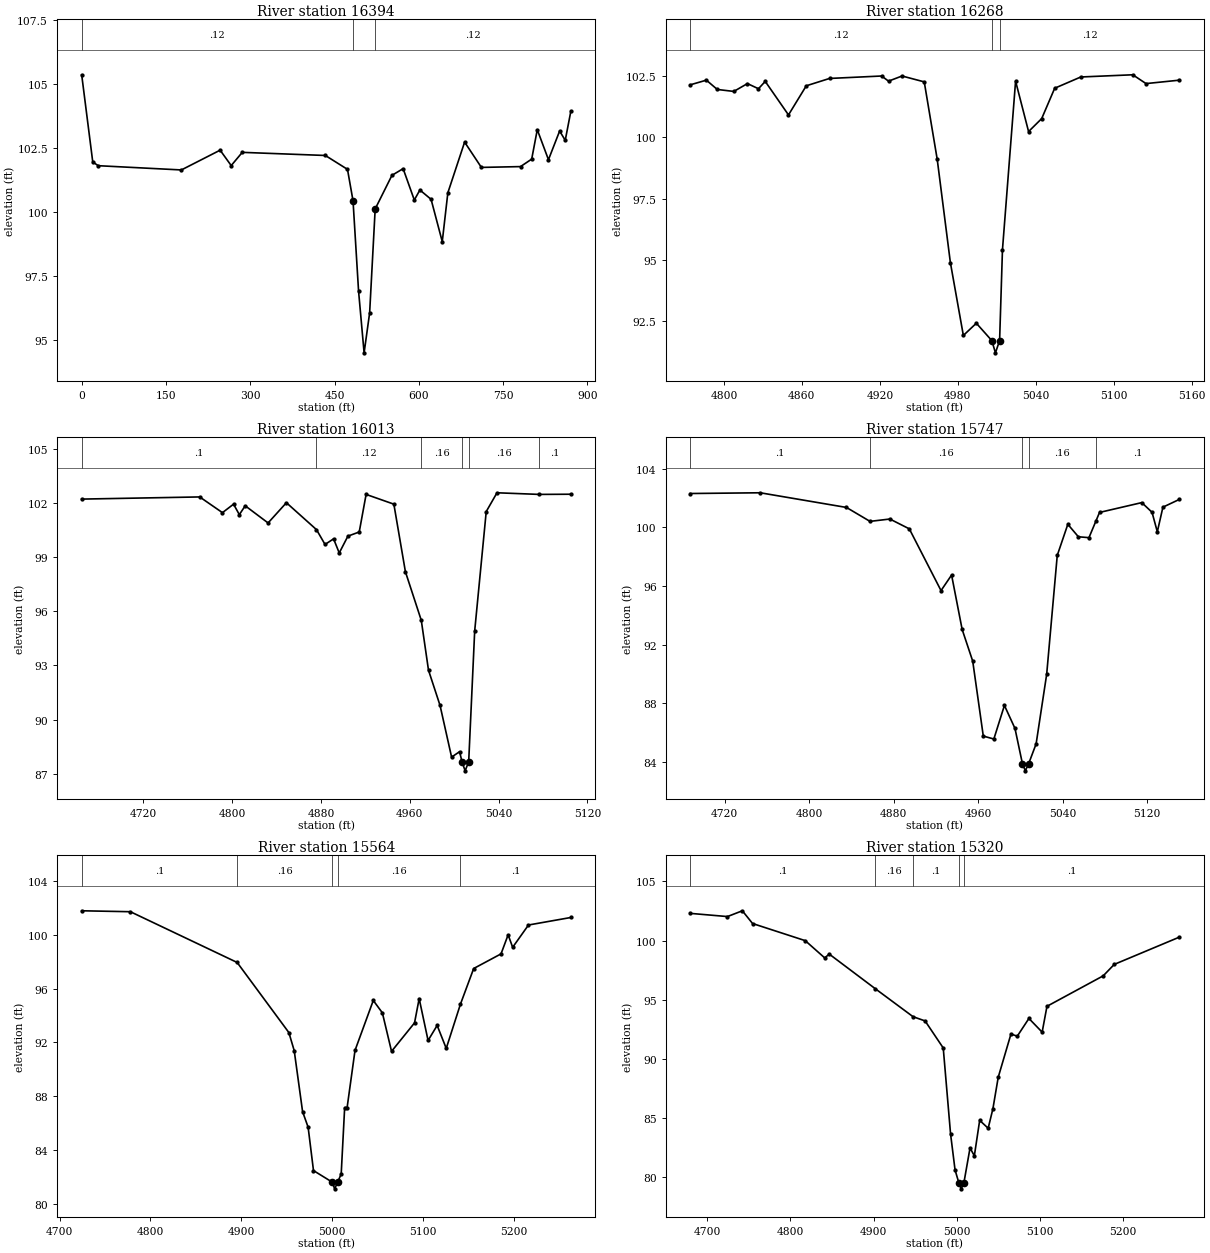
Type RM Length L Ch R = 1 ,16394   ,124,124,124
BEGIN DESCRIPTION:
UNT038 IN BACR 25.0
END DESCRIPTION:
XS GIS Cut Line= 3
     2347917.847     13149480.96     2348170.452     13149025.23
     2347977.743     13148740.07
#Sta/Elev= 30
       0105.370819.71027101.9569 29.5654 101.813177.3924101.6469246.3783102.4208
266.0886 101.818285.7989102.3352433.6259102.2132473.0464  101.67482.9016100.4403
492.7567 96.9061502.6118 94.4903 512.467  96.056522.3221100.1215552.1661101.4362
572.0621101.6975591.9581100.4705601.9061100.8618621.8021100.4975641.6981 98.8424
651.6461100.7529681.4901102.7369711.3342 101.746780.9702 101.778800.8661102.0708
810.8141103.2232830.7102102.0478850.6062 103.171860.5542102.8054870.5022103.9391
#Mann= 3 , 0 , 0
       0     .12       0482.9016     .07       0522.3221     .12       0
Bank Sta=482.9016,522.3221
XS Rating Curve= 0 ,0
Exp/Cntr=0.3,0.1

Type RM Length L Ch R = 1 ,16268   ,255,255,255
BEGIN DESCRIPTION:
Mapping XS fdfaca62
END DESCRIPTION:
XS GIS Cut Line= 3
      2348225.13      13149248.6      2348276.02     13149095.94
      2348295.54     13148881.24
#Sta/Elev= 30
  4774.1  102.15  4786.5  102.34  4794.9  101.96  4807.6  101.88  4818.1   102.2
  4826.6  101.99  4831.8  102.29  4849.7  100.92  4863.4  102.11  4881.3  102.41
  4921.4  102.51  4926.7   102.3  4937.1  102.51  4954.2  102.27  4964.2    99.1
  4974.3   94.89  4984.3   91.91  4994.3   92.41  5006.2    91.7    5009    91.2
  5012.2    91.7  5014.4   95.41  5024.5   102.3  5034.5  100.24  5044.6  100.77
  5054.6  102.01  5074.7  102.47  5114.7  102.56  5124.9   102.2  5150.6  102.34
#Mann= 3 ,-1 , 0
  4774.1     .12       0  5006.2     .07       0  5012.2     .12       0
Bank Sta=5006.2,5012.2
XS Rating Curve= 0 ,0
Exp/Cntr=0.3,0.1

Type RM Length L Ch R = 1 ,16013   ,266,266,266
BEGIN DESCRIPTION:
Mapping XS e0f80e65
END DESCRIPTION:
XS GIS Cut Line= 3
      2348350.38     13149260.31      2348409.08     13149009.83
      2348459.97      13148833.7
#Sta/Elev= 30
  4664.4   102.2  4770.7  102.32  4791.2  101.45  4801.2  101.92  4806.4  101.34
  4811.7  101.83  4832.3  100.88  4848.8     102  4875.9  100.51  4883.6   99.69
  4891.3     100  4896.4   99.22  4904.2  100.15  4914.4  100.38  4920.6  102.46
  4945.6  101.92    4956   98.18  4970.3   95.49  4976.8   92.73  4987.2   90.78
  4997.6   87.92  5004.8   88.22    5007   87.66  5009.8   87.16    5013   87.66
  5018.4    94.9  5028.8  101.51  5038.5  102.55  5076.5  102.46    5105  102.47
#Mann= 6 ,-1 , 0
  4664.4      .1       0  4875.9     .12       0  4970.3     .16       0
    5007     .07       0    5013     .16       0  5076.5      .1       0
Bank Sta=5007,5013
XS Rating Curve= 0 ,0
Exp/Cntr=0.3,0.1

Type RM Length L Ch R = 1 ,15747   ,183,183,183
BEGIN DESCRIPTION:
Mapping XS caf6d2b7
END DESCRIPTION:
XS GIS Cut Line= 3
      2348510.84     13149326.84      2348589.11     13149158.55
      2348593.02     13148881.28
#Sta/Elev= 30
  4687.6  102.31  4753.8  102.36  4835.4  101.36  4857.7  100.41  4876.5  100.57
  4894.9    99.9  4924.9   95.69  4934.9   96.75  4944.9   93.04  4954.9   90.88
  4964.9   85.77  4974.9   85.57  4984.9   87.86  4994.9   86.29  5001.9    83.9
  5004.7    83.4  5007.9    83.9  5014.9   85.24  5024.9   89.99  5034.9   98.09
  5044.9  100.21  5054.9   99.36  5064.9    99.3  5071.6  100.45  5074.9  101.02
  5114.9  101.69  5124.6  101.03  5129.6    99.7  5134.9  101.38  5150.5  101.91
#Mann= 5 ,-1 , 0
  4687.6      .1       0  4857.7     .16       0  5001.9     .07       0
  5007.9     .16       0  5071.6      .1       0
Bank Sta=5001.9,5007.9
XS Rating Curve= 0 ,0
Exp/Cntr=0.3,0.1

Type RM Length L Ch R = 1 ,15564   ,244,244,244
BEGIN DESCRIPTION:
Mapping XS 6d4c2692
END DESCRIPTION:
XS GIS Cut Line= 3
      2348589.09      13149362.1      2348745.66      13149115.5
        2348769.     13148870.42
#Sta/Elev= 30
  4724.3  101.81  4777.9  101.74  4895.4   97.96  4952.3   92.74  4958.2   91.39
  4967.4   86.85  4973.5   85.69  4979.4   82.46    5000    81.6  5002.7    81.1
    5006    81.6  5009.9   82.21  5013.7   87.15  5016.4   87.15  5025.1   91.41
  5045.2   95.13  5055.2   94.21  5065.3   91.34  5090.6   93.46  5095.7   95.27
  5105.5   92.15  5115.5   93.27  5125.5   91.56  5141.1   94.85  5155.7   97.51
  5185.8    98.6  5193.6  100.02  5198.6   99.09    5216  100.75  5262.6  101.31
#Mann= 5 ,-1 , 0
  4724.3      .1       0  4895.4     .16       0    5000     .07       0
    5006     .16       0  5141.1      .1       0
Bank Sta=5000,5006
XS Rating Curve= 0 ,0
Exp/Cntr=0.3,0.1

Type RM Length L Ch R = 1 ,15320   ,186,186,186
BEGIN DESCRIPTION:
Mapping XS 8305f76a
END DESCRIPTION:
XS GIS Cut Line= 3
      2348589.11      13149428.6      2348902.21     13149291.62
      2349023.12      13149077.1
#Sta/Elev= 30
  4679.6   102.3  4724.3  102.03  4742.2  102.52  4754.5  101.44  4817.8   99.99
  4841.2   98.53  4846.7   98.85    4902   95.92  4947.4   93.55  4961.9   93.19
  4983.7    90.9  4992.5   83.62  4997.9   80.57  5002.5   79.47  5005.3   78.97
  5008.5   79.47  5015.9   82.43  5021.1   81.77  5027.5   84.77  5037.7    84.1
  5043.4   85.75  5049.8   88.42  5065.1   92.08  5072.7    91.9  5086.7    93.4
  5102.6   92.24  5108.4   94.43    5176   97.01  5189.3   97.98  5267.6  100.29
#Mann= 5 ,-1 , 0
  4679.6      .1       0    4902     .16       0  4947.4      .1       0
  5002.5     .07       0  5008.5      .1       0
Bank Sta=5002.5,5008.5
XS Rating Curve= 0 ,0
Exp/Cntr=0.3,0.1

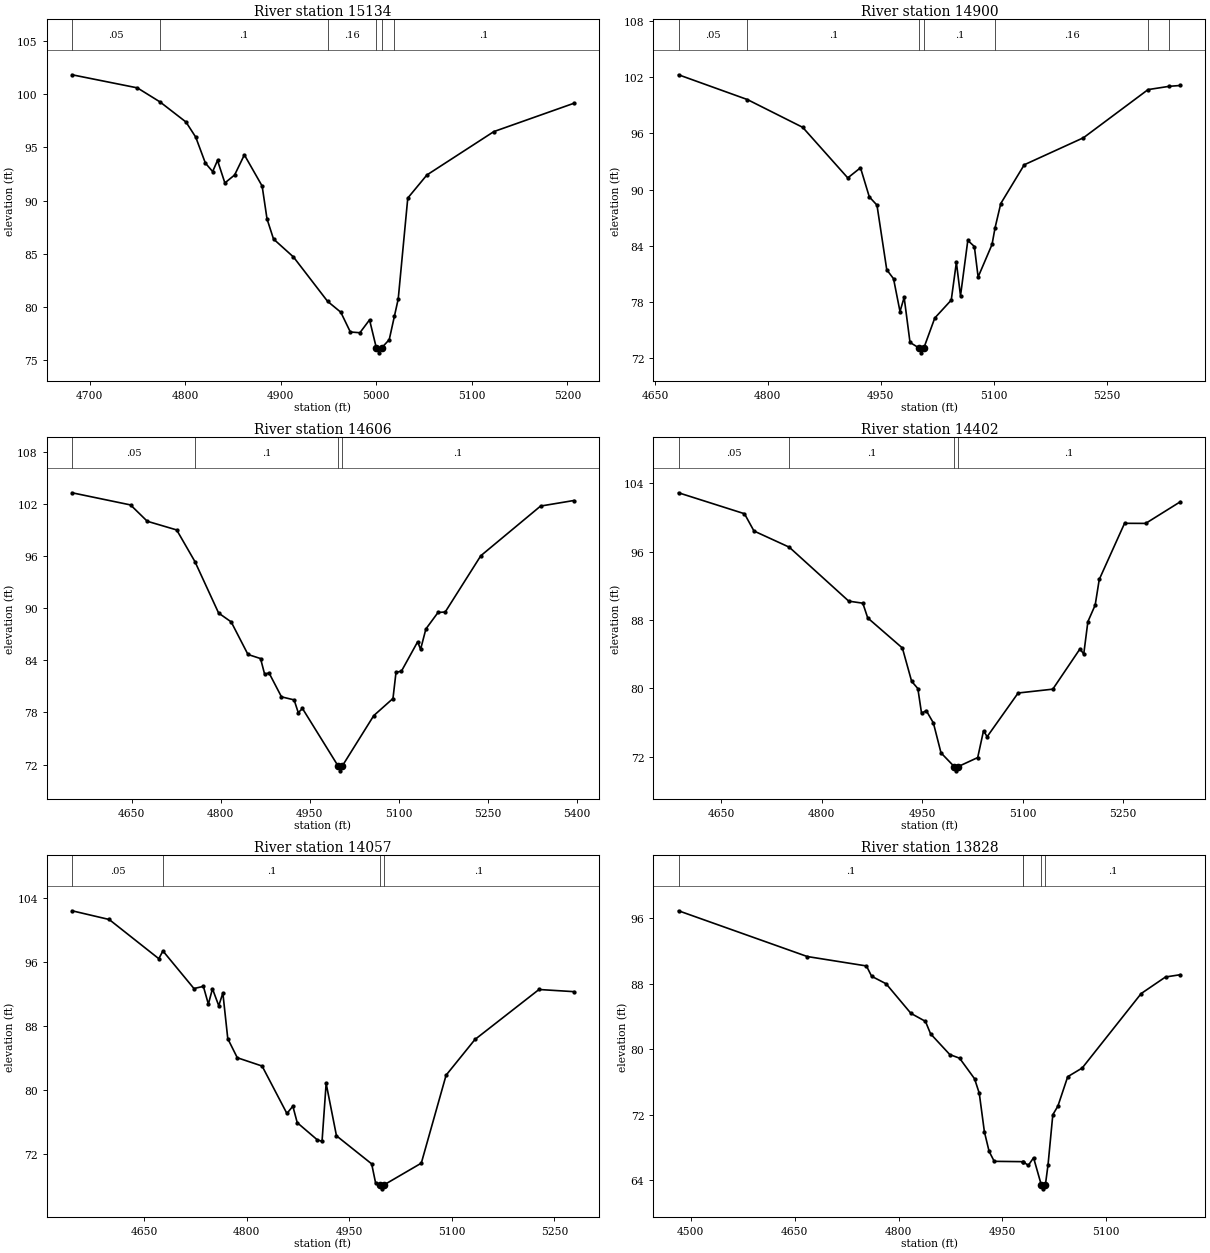
Type RM Length L Ch R = 1 ,15134   ,234,234,234
BEGIN DESCRIPTION:
Mapping XS 68bbd387
END DESCRIPTION:
XS GIS Cut Line= 3
      2348984.39     13149643.88      2349027.45     13149420.77
       2349043.1      13149123.3
#Sta/Elev= 30
  4681.6  101.82  4749.9  100.59  4773.6   99.27  4800.8   97.38    4811   95.96
  4821.1   93.52  4828.7   92.72  4833.8   93.77  4841.5   91.65  4851.7    92.4
  4861.9   94.29  4880.5   91.36  4885.6   88.27  4892.4   86.38  4913.3   84.69
    4949   80.52  4962.8    79.5  4972.8   77.64  4982.8   77.57  4992.9   78.78
  4999.9   76.18  5002.6   75.68  5005.9   76.18  5013.5   76.92    5019   79.16
  5022.9   80.74  5032.9   90.23  5052.9    92.4    5123   96.48  5206.7   99.14
#Mann= 6 ,-1 , 0
  4681.6     .05       0  4773.6      .1       0    4949     .16       0
  4999.9     .07       0  5005.9     .16       0    5019      .1       0
Bank Sta=4999.9,5005.9
XS Rating Curve= 0 ,0
Exp/Cntr=0.3,0.1

Type RM Length L Ch R = 1 ,14900   ,294,294,294
BEGIN DESCRIPTION:
Mapping XS 39c57db6
END DESCRIPTION:
XS GIS Cut Line= 3
      2349070.52     13149667.29      2349230.96     13149311.19
       2349328.8     13149052.88
#Sta/Elev= 30
  4681.3  102.23  4772.8   99.59  4846.3   96.63  4906.2   91.24  4923.1   92.32
  4934.8   89.22    4945   88.34    4958   81.45    4967    80.5  4975.6      77
  4981.1   78.51  4988.9   73.71  5001.2    73.1    5004    72.6  5007.2    73.1
  5021.8   76.31  5043.7   78.22  5050.5   82.24    5056   78.68  5065.7   84.58
  5074.4   83.93  5079.4   80.68  5097.9   84.15  5101.9   85.92  5109.5   88.51
  5140.7   92.64  5219.4   95.52  5305.2  100.65  5333.3     101  5348.1  101.09
#Mann= 7 ,-1 , 0
  4681.3     .05       0  4772.8      .1       0  5001.2     .07       0
  5007.2      .1       0  5101.9     .16       0  5305.2      .1       0
  5333.3     .05       0
Bank Sta=5001.2,5007.2
XS Rating Curve= 0 ,0
Exp/Cntr=0.3,0.1

Type RM Length L Ch R = 1 ,14606   ,204,204,204
BEGIN DESCRIPTION:
Mapping XS 97f541a8
END DESCRIPTION:
XS GIS Cut Line= 3
      2349128.93     13149777.48      2349496.67     13149414.11
      2349575.46     13149094.56
#Sta/Elev= 30
  4549.4  103.29    4648  101.89  4676.2  100.01  4725.8   99.01  4756.6   95.36
  4796.5   89.44  4817.7   88.42    4846   84.67  4867.2    84.2  4874.2   82.37
  4881.4   82.56  4902.5   79.79  4923.8   79.44  4930.8   77.97  4937.9   78.45
  4998.5   71.77  5001.3   71.27  5004.5   71.77  5058.1   77.63  5090.5    79.6
  5095.6   82.61  5104.8   82.75    5132   86.12  5137.1   85.27    5146   87.61
  5166.5   89.51  5178.6   89.56  5238.6   96.04  5339.4  101.76  5395.5   102.4
#Mann= 4 ,-1 , 0
  4549.4     .05       0  4756.6      .1       0  4998.5     .07       0
  5004.5      .1       0
Bank Sta=4998.5,5004.5
XS Rating Curve= 0 ,0
Exp/Cntr=0.3,0.1

Type RM Length L Ch R = 1 ,14402   ,345,345,345
BEGIN DESCRIPTION:
Mapping XS dfba0d3d
END DESCRIPTION:
XS GIS Cut Line= 3
      2349387.48     13149816.08      2349602.76     13149589.06
      2349782.31     13149190.93
#Sta/Elev= 30
  4586.1  102.87  4684.6  100.42  4698.8    98.4  4751.5   96.51  4840.4    90.2
  4861.4   89.96  4868.7   88.24  4920.5   84.72  4934.3   80.83  4943.6   79.98
  4949.1    77.1  4956.2    77.4  4966.8   75.96  4978.2   72.46  4997.9   70.86
  5000.6   70.36  5003.9   70.86    5033   71.91  5041.7   75.04  5047.1   74.35
  5093.4   79.46  5145.2   79.91  5185.9   84.63  5191.4      84  5197.6    87.8
  5208.5   89.74  5214.6   92.74  5252.4    99.3  5283.9   99.29  5335.7  101.82
#Mann= 4 ,-1 , 0
  4586.1     .05       0  4751.5      .1       0  4997.9     .07       0
  5003.9      .1       0
Bank Sta=4997.9,5003.9
XS Rating Curve= 0 ,0
Exp/Cntr=0.3,0.1

Type RM Length L Ch R = 1 ,14057   ,229,229,229
BEGIN DESCRIPTION:
UNT038 IN BACR 19.0
END DESCRIPTION:
XS GIS Cut Line= 2
      2349466.38     13149940.82      2350083.05     13149542.56
#Sta/Elev= 30
  4544.4  102.42  4598.7  101.33  4671.3   96.43  4677.3    97.4  4722.7    92.7
  4736.5   92.97  4743.8   90.75  4749.8   92.67    4759   90.55    4765   92.14
  4772.2   86.43  4786.1   84.05  4822.4   83.01  4858.7   77.08  4867.4   77.99
  4873.8   75.93  4903.1   73.79  4910.1    73.6  4916.1   80.84  4931.2   74.29
  4982.7   70.78  4988.6   68.33  4994.9   68.16  4997.6   67.66  5000.9   68.16
  5055.3   70.87  5091.6   81.87  5133.8   86.33  5227.5   92.58  5278.5   92.31
#Mann= 4 ,-1 , 0
  4544.4     .05       0  4677.3      .1       0  4994.9     .07       0
  5000.9      .1       0
Bank Sta=4994.9,5000.9
XS Rating Curve= 0 ,0
Exp/Cntr=0.3,0.1

Type RM Length L Ch R = 1 ,13828   ,282,282,282
BEGIN DESCRIPTION:
Mapping XS c208b545
END DESCRIPTION:
XS GIS Cut Line= 3
      2349532.35      13150058.7       2349786.7     13150039.14
      2350133.85     13149723.19
#Sta/Elev= 30
  4482.4   96.91  4668.3   91.32  4753.7   90.17  4761.2   88.91  4782.1   87.99
  4817.9   84.38  4838.9    83.4  4846.3   81.88  4874.1   79.34  4888.2    78.9
  4909.8   76.39  4916.6   74.62    4924   69.91  4930.8   67.52  4938.2    66.3
  4979.2   66.26  4979.5   66.26  4987.5   65.81    4995   66.74  5006.1   63.44
  5008.9   62.94  5012.1   63.44  5015.9   65.88  5022.8      72  5030.1   73.04
  5044.3   76.64  5065.2    77.7  5150.4    86.8  5185.5   88.82  5206.9    89.1
#Mann= 5 ,-1 , 0
  4482.4      .1       0  4979.2     .16       0  4979.5      .1       0
  5006.1     .07       0  5012.1      .1       0
Bank Sta=5006.1,5012.1
XS Rating Curve= 0 ,0
Exp/Cntr=0.3,0.1

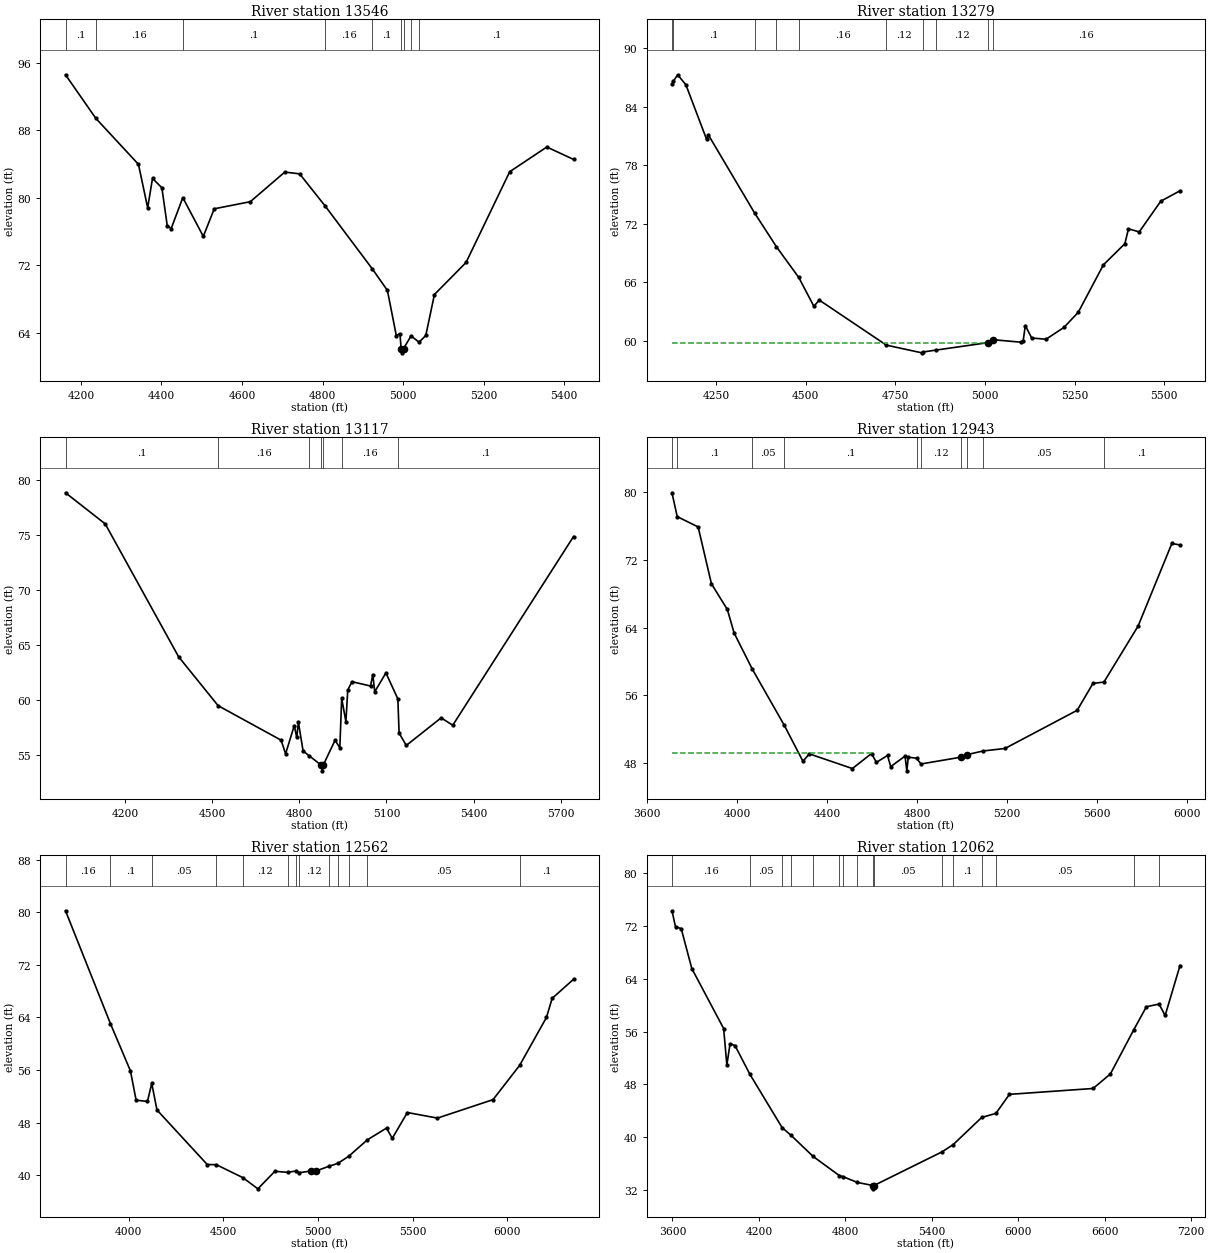
Type RM Length L Ch R = 1 ,13546   ,267,267,267
BEGIN DESCRIPTION:
UNT038 IN BACR 18.0
END DESCRIPTION:
XS GIS Cut Line= 3
      2349402.12     13150519.25      2350199.03     13150043.67
      2350224.65     13149710.69
#Sta/Elev= 30
  4161.6   94.58  4236.9   89.42  4342.8   83.97  4365.7   78.82  4377.7    82.3
    4401   81.19  4414.3    76.7  4424.1   76.36    4453   80.02  4503.9   75.43
  4531.1    78.7  4620.7   79.54  4706.3   83.05  4743.2   82.84  4807.4   78.98
  4923.7   71.58  4961.2   69.03  4983.3   63.68  4992.4   63.91  4995.2   62.13
  4997.9   61.63  5001.2   62.13    5020   63.63  5039.9   62.89  5056.6   63.69
    5078   68.54  5156.6   72.34    5265   83.09  5357.2   86.02  5423.6   84.55
#Mann= 9 ,-1 , 0
  4161.6      .1       0  4236.9     .16       0    4453      .1       0
  4807.4     .16       0  4923.7      .1       0  4995.2     .07       0
  5001.2      .1       0    5020     .12       0  5039.9      .1       0
Bank Sta=4995.2,5001.2
XS Rating Curve= 0 ,0
Exp/Cntr=0.3,0.1

Type RM Length L Ch R = 1 ,13279   ,162,162,162
BEGIN DESCRIPTION:
Mapping XS aca3c257
END DESCRIPTION:
XS GIS Cut Line= 4
      2349512.71     13150673.16      2350056.75     13150489.21
      2350354.19     13150203.51      2350350.27     13149773.04
#Sta/Elev= 30
  4126.6    86.3  4130.2   86.57  4142.4   87.25  4165.4   86.23    4223   80.66
  4228.3   81.09  4356.9   73.12  4417.7   69.67  4480.3   66.51  4522.5   63.56
  4537.4    64.2  4724.5   59.59  4823.5    58.8  4825.5   58.88    4863   59.08
  5007.3   59.84  5021.4   60.15  5099.3   59.89  5106.3   60.04  5112.3   61.59
    5130   60.32    5170   60.19    5220    61.4    5260   62.95    5330    67.8
    5390   69.97    5400   71.49    5430   71.17    5490   74.31  5543.8   75.38
#Mann= 10 ,-1 , 0
  4126.6     .05       0  4130.2      .1       0  4356.9     .16       0
  4417.7      .1       0  4480.3     .16       0  4724.5     .12       0
  4825.5      .1       0    4863     .12       0  5007.3     .07       0
  5021.4     .16       0
#XS Ineff= 2 , 0
       0 5006.88   59.85 5021.69       0   60.14
Permanent Ineff=
       T       T
Bank Sta=5007.3,5021.4
XS Rating Curve= 0 ,0
Exp/Cntr=0.3,0.1

Type RM Length L Ch R = 1 ,13117   ,174,174,174
BEGIN DESCRIPTION:
Mapping XS 0964e758
END DESCRIPTION:
XS GIS Cut Line= 5
      2349501.67     13150875.72      2350350.17     13150426.51
      2350441.32     13150352.73      2350439.15     13150281.12
      2350432.65     13149680.94
#Sta/Elev= 30
  3994.9   78.84  4131.6   76.01  4384.3   63.92  4520.3   59.47  4737.2   56.33
  4752.7   55.09  4782.5   57.66    4791   56.58  4796.7   57.96    4813   55.34
    4833   54.93    4876   54.04  4878.8   53.54    4882   54.04    4923   56.33
  4939.4   55.64  4945.8   60.13  4960.3   58.02  4966.7   60.89  4981.1   61.65
  5045.1   61.26    5053    62.3  5059.5   60.73  5098.1   62.45  5139.1   60.09
  5143.5   56.98  5168.1   55.85  5288.2   58.36  5328.2   57.69  5744.1   74.86
#Mann= 7 ,-1 , 0
  3994.9      .1       0  4520.3     .16       0    4833     .12       0
    4876     .07       0    4882     .12       0  4945.8     .16       0
  5139.1      .1       0
Bank Sta=4876,4882
XS Rating Curve= 0 ,0
Exp/Cntr=0.3,0.1

Type RM Length L Ch R = 1 ,12943   ,381,381,381
BEGIN DESCRIPTION:
UNT038 IN BACR 17.0
END DESCRIPTION:
XS GIS Cut Line= 4
      2349363.48     13151084.84      2349916.25     13151020.57
      2350562.72     13150471.85      2350520.44     13149620.64
#Sta/Elev= 30
  3710.9   79.89  3734.2   77.08  3827.1   75.86  3886.3   69.15  3956.8   66.13
    3987   63.35  4067.6    59.1    4210   52.46  4292.6   48.23  4321.2    49.1
  4512.3   47.37  4597.2   49.14  4618.9    48.1  4668.3   48.91  4682.6    47.6
  4746.3   48.84    4754    47.1  4760.5   48.71  4797.1   48.59    4817   47.91
  4994.5   48.71  5023.1   49.02  5092.4   49.44  5190.4   49.74  5510.8   54.24
  5580.9   57.41  5629.7   57.57  5781.2   64.16  5931.3   73.91  5967.6   73.74
#Mann= 10 ,-1 , 0
  3710.9     .16       0  3734.2      .1       0  4067.6     .05       0
    4210      .1       0  4797.1     .16       0    4817     .12       0
  4994.5     .07       0  5023.1     .16       0  5092.4     .05       0
  5629.7      .1       0
#XS Ineff= 2 , 0
       0 4597.06   49.15 5023.29       0   49.02
Permanent Ineff=
       T       T
Bank Sta=4994.5,5023.1
XS Rating Curve= 0 ,0
Exp/Cntr=0.3,0.1

Type RM Length L Ch R = 1 ,12562   ,500,500,500
BEGIN DESCRIPTION:
Mapping XS f2d50c08
END DESCRIPTION:
XS GIS Cut Line= 6
      2349324.92     13151291.52      2349892.37     13151283.69
      2350498.99     13150978.42      2350651.63      13150802.3
      2350663.37     13150320.92      2350577.27     13149604.76
#Sta/Elev= 30
  3667.1   80.23  3904.2   63.07  4009.9   55.88  4039.9   51.42  4099.9   51.22
  4122.4   53.99  4149.9   49.93  4415.4   41.63  4463.7    41.6  4603.2   39.64
  4682.9   37.93  4772.5    40.6  4839.4   40.44  4884.1   40.64  4898.3   40.38
  4963.6   40.64  4992.1   40.67  5059.1   41.37  5105.6   41.81  5162.6   42.89
  5261.5    45.4  5362.3   47.17  5392.3   45.61  5472.3   49.54    5631   48.69
  5924.5    51.5  6065.1   56.72  6206.5      64  6236.7   66.91  6349.6   69.81
#Mann= 13 ,-1 , 0
  3667.1     .16       0  3904.2      .1       0  4122.4     .05       0
  4463.7      .1       0  4603.2     .12       0  4839.4     .07       0
  4884.1      .1       0  4898.3     .12       0  5059.1     .16       0
  5105.6      .1       0  5162.6     .16       0  5261.5     .05       0
  6065.1      .1       0
#XS Ineff= 2 , 0
       0 4962.74   40.62               0
Permanent Ineff=
       T       F
Bank Sta=4963.6,4992.1
XS Rating Curve= 0 ,0
Exp/Cntr=0.3,0.1

Type RM Length L Ch R = 1 ,12062   ,942,942,942
BEGIN DESCRIPTION:
Mapping XS aa7517f0
END DESCRIPTION:
XS GIS Cut Line= 4
      2349170.74     13151778.94      2350648.92     13151367.62
      2350777.46     13151161.96      2350726.04     13149413.78
#Sta/Elev= 30
  3597.2   74.34  3621.8   71.91  3661.2   71.64  3734.9   65.58  3955.8   56.48
  3978.1   50.96  4000.4   54.18  4034.6    53.9  4138.5   49.52  4361.5   41.46
  4424.4   40.27  4576.5   37.09    4758   34.19  4781.9   34.03  4884.5   33.14
  4992.4   32.67  4995.1   32.17  4998.4   32.67  5469.7   37.76  5548.4   38.87
  5746.4   42.99  5845.4   43.62  5939.4    46.5  6519.7   47.39  6639.7   49.59
  6801.2   56.26  6889.8   59.79  6977.4   60.19  7019.9   58.46    7123   66.04
#Mann= 16 ,-1 , 0
  3597.2     .16       0  4138.5     .05       0  4361.5      .1       0
  4424.4     .05       0  4576.5      .1       0    4758     .16       0
  4781.9      .1       0  4884.5     .05       0  4992.4     .03       0
  4998.4     .05       0  5469.7     .12       0  5548.4      .1       0
  5746.4     .16       0  5845.4     .05       0  6801.2      .1       0
  6977.4     .16       0
Bank Sta=4992.4,4998.4
XS Rating Curve= 0 ,0
Exp/Cntr=0.3,0.1

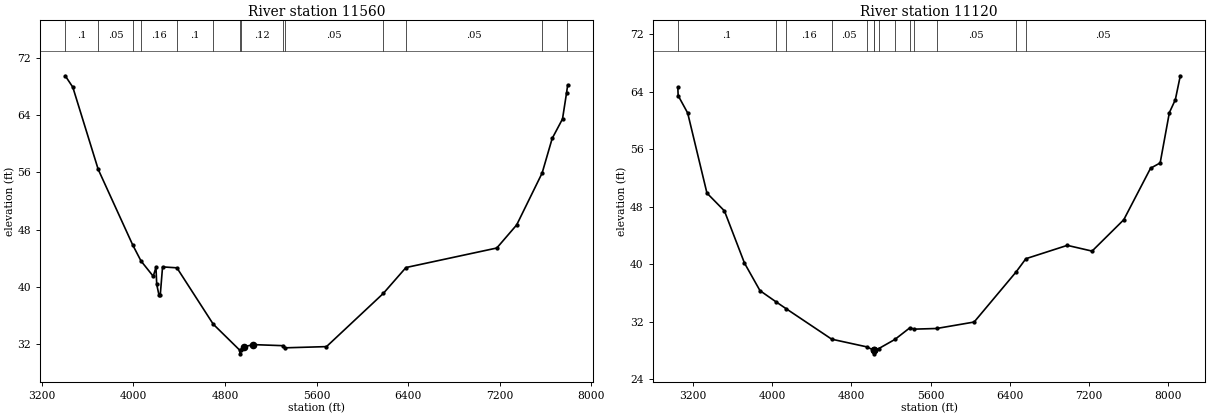
Type RM Length L Ch R = 1 ,11560   ,440,440,440
BEGIN DESCRIPTION:
Mapping XS 0aa695cd
END DESCRIPTION:
XS GIS Cut Line= 5
      2348832.81     13152171.92      2350618.79     13151826.88
      2350892.23     13151585.99      2350870.53     13150743.98
      2350801.39     13149381.54
#Sta/Elev= 30
  3403.8   69.51  3469.9   67.92  3691.9   56.42  3993.3   45.85  4066.2    43.6
  4172.7   41.47  4196.5   42.71  4203.2   40.33  4223.6   38.79  4233.8    38.8
  4254.1   42.78  4379.5   42.65  4696.8   34.77  4929.2   31.12    4932   30.62
  4935.2   31.12  4967.1   31.62  5048.6   31.91    5309   31.76  5321.5   31.46
  5686.4   31.63  6182.7   39.07  6380.6   42.69  7174.1   45.42  7347.8   48.65
  7570.1    55.9  7658.2   60.75  7748.3   63.47  7783.5    67.1  7793.7   68.24
#Mann= 14 ,-1 , 0
  3403.8      .1       0  3691.9     .05       0  3993.3      .1       0
  4066.2     .16       0  4379.5      .1       0  4696.8     .12       0
  4929.2     .07       0  4935.2     .12       0    5309      .1       0
  5321.5     .05       0  6182.7      .1       0  6380.6     .05       0
  7570.1     .16       0  7783.5      .1       0
Bank Sta=4967.1,5048.6
XS Rating Curve= 0 ,0
Exp/Cntr=0.3,0.1

Type RM Length L Ch R = 1 ,11120   ,0,0,0
BEGIN DESCRIPTION:
UNT038 IN BACR 1.0
END DESCRIPTION:
XS GIS Cut Line= 4
      2348630.84     13152653.02      2350623.21     13152164.56
      2351034.54     13151830.36      2350880.29     13149336.68
#Sta/Elev= 30
  3044.5   64.65  3047.9   63.47  3144.3   61.04    3339   49.89  3515.7   47.41
  3718.5   40.14  3875.3    36.3  4039.8   34.72  4141.5   33.77  4600.5   29.54
  4955.5   28.47  5025.4      28  5028.2    27.5  5031.4      28    5077   28.24
  5239.5   29.51  5390.8   31.13  5435.1   30.94  5660.2   31.03  6040.2   31.93
    6464    38.9  6563.2   40.75  6981.9   42.61  7232.4   41.81    7553   46.18
  7823.6   53.35  7920.8   54.09  8013.9    61.1    8074   62.89  8124.3   66.23
#Mann= 14 ,-1 , 0
  3044.5      .1       0  4039.8     .05       0  4141.5     .16       0
  4600.5     .05       0  4955.5     .12       0  5025.4     .07       0
  5031.4     .12       0    5077      .1       0  5239.5     .07       0
  5390.8     .12       0  5435.1      .1       0  5660.2     .05       0
    6464      .1       0  6563.2     .05       0
Bank Sta=5025.4,5031.4
XS Rating Curve= 0 ,0
Exp/Cntr=0.3,0.1
Stream Node=UNT038 IN BACR  ,Reach-1         , 0 , 0 ,Upstream end
Stream Node=UNT038 IN BACR  ,Reach-1         , 0 , 1 ,Downstream end

Chan Stop Cuts=-1
Use User Specified Reach Order=0
Composite Channel Slope=5