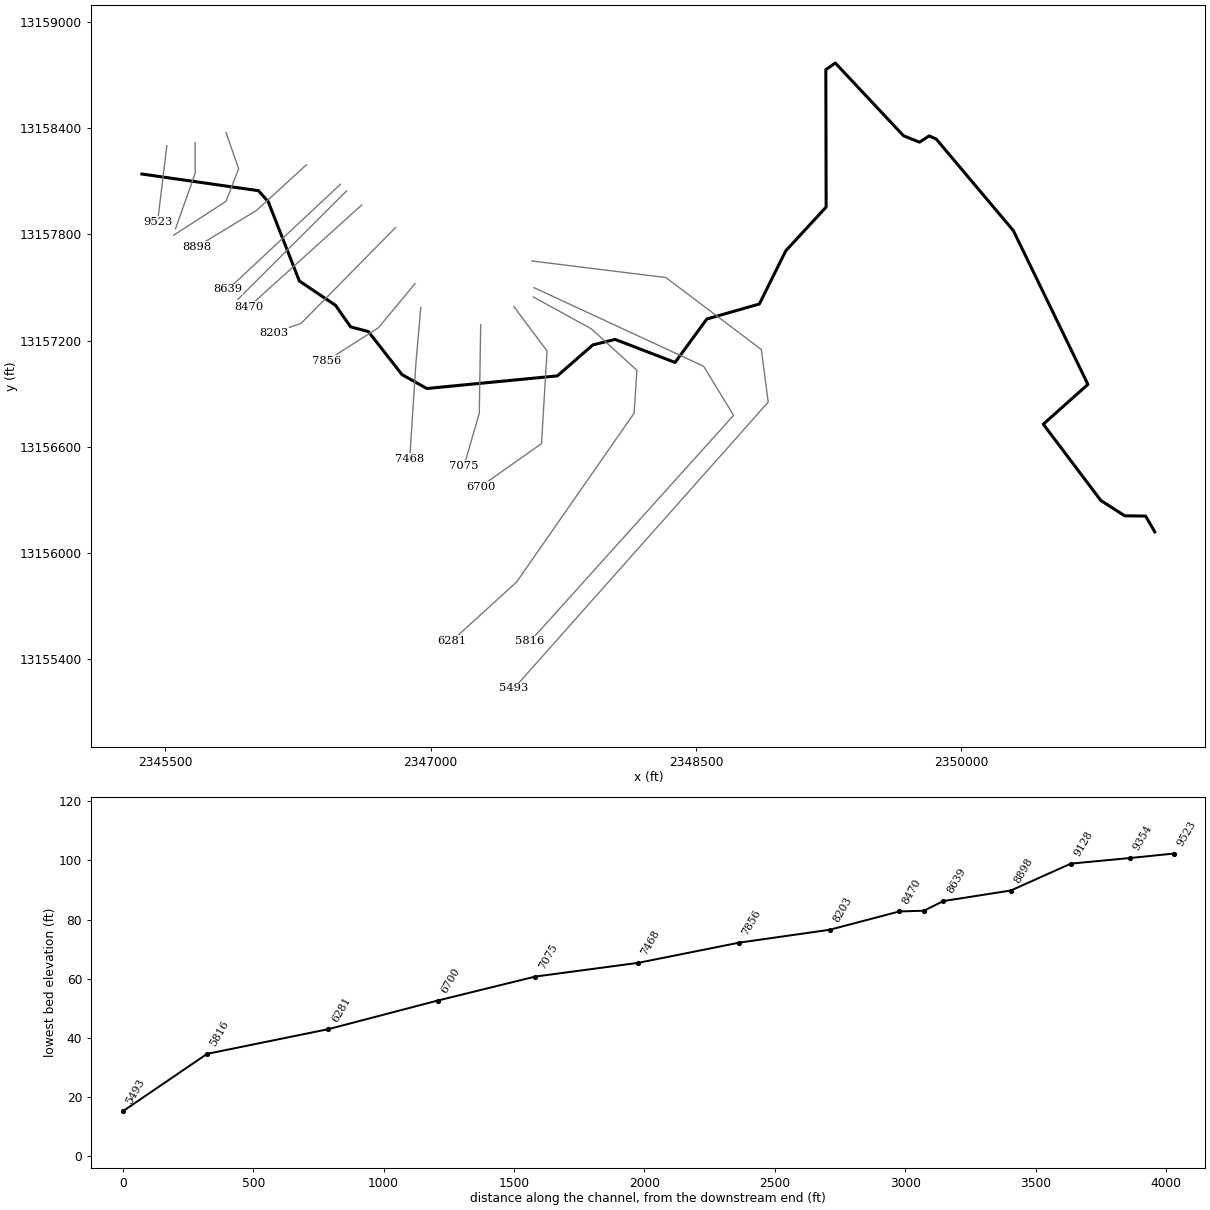
--- UNT039 IN BACR.prj (project) ---

Proj Title=UNT039 IN BACR Base Level Engineering
Current Plan=p01
Default Exp/Contr=0.3,0.1
English Units
Geom File=g01
Flow File=f01
Plan File=p01
Y Axis Title=Elevation
X Axis Title(PF)=Main Channel Distance
X Axis Title(XS)=Station
BEGIN DESCRIPTION:
UNT039 IN BACR
END DESCRIPTION:
DSS Export Rating Curves= 0
DSS Export Rating Curve Sorted= 0
DSS Export Volume Flow Curves= 0
DXF OffsetX= 0
DXF OffsetY= 0
DXF ScaleX= 1
DXF ScaleY= 10

--- UNT039 IN BACR.p01 (plan) ---

Plan Title=Multiple Run
Short Identifier=Multiple
Geom File=g01
Flow File=f01
Subcritical Flow
K Sum by GR= 0
Std Step Tol= 0.01
Critical Tol= 0.01
Num of Std Step Trials= 20
Max Error Tol= 0.3
Flow Tol Ratio= 0.001
Split Flow NTrial= 30
Split Flow Tol= 0.02
Split Flow Ratio= 0.02
Log Output Level= 0
Friction Slope Method= 1
Unsteady Friction Slope Method= 2
Unsteady Bridges Friction Slope Method= 1
Parabolic Critical Depth
Global Vel Dist=  1 , 1 , 1
Global Log Level= 0
CheckData=True
Encroach Param= -1, 0, 0, 0
BEGIN DESCRIPTION:
Multiple Run
END DESCRIPTION:

--- UNT039 IN BACR.f01 (steady flow) ---

Flow Title=Multiple
Number of Profiles=7
Profile Names=10-year,25-year,50-year,1pct_min,100-year,1pct_plu,500-year
River Rch & RM= UNT039 IN BACR,Reach-1,9523
     261     352     424     376     508     687     734
River Rch & RM= UNT039 IN BACR,Reach-1,7075
     466     650     802     725     981    1327    1482
Boundary for River Rch & Prof#=UNT039 IN BACR,Reach-1,1
Up Type=0
Dn Type=3
Dn Slope=0.005
Boundary for River Rch & Prof#=UNT039 IN BACR,Reach-1,2
Up Type=0
Dn Type=3
Dn Slope=0.005
Boundary for River Rch & Prof#=UNT039 IN BACR,Reach-1,3
Up Type=0
Dn Type=3
Dn Slope=0.005
Boundary for River Rch & Prof#=UNT039 IN BACR,Reach-1,4
Up Type=0
Dn Type=3
Dn Slope=0.005
Boundary for River Rch & Prof#=UNT039 IN BACR,Reach-1,5
Up Type=0
Dn Type=3
Dn Slope=0.005
Boundary for River Rch & Prof#=UNT039 IN BACR,Reach-1,6
Up Type=0
Dn Type=3
Dn Slope=0.005
Boundary for River Rch & Prof#=UNT039 IN BACR,Reach-1,7
Up Type=0
Dn Type=3
Dn Slope=0.005

--- UNT039 IN BACR.g01 (geometry) ---

Geom Title=Existing Conditions
Program Version=4.10

River Reach=UNT039 IN BACR  ,Reach-1
Reach XY= 30
      2345369.03     13158140.01      2346027.67     13158046.09
      2346082.78     13157984.05      2346258.63     13157536.26
      2346463.45      13157398.4      2346547.89     13157277.42
      2346648.66     13157250.67      2346838.55     13157007.96
      2346978.86      13156929.1      2347716.71     13157000.37
      2347917.48     13157175.33        2348043.     13157206.39
      2348382.23     13157076.22      2348561.46      13157321.5
      2348858.34     13157406.13      2349007.65     13157706.48
      2349235.85      13157953.7      2349234.09     13158729.55
      2349287.72     13158766.85      2349673.13     13158356.21
      2349763.32     13158320.03      2349818.26     13158355.43
      2349857.97     13158337.61      2350294.16      13157820.1
      2350715.24     13156952.43      2350463.07     13156727.61
      2350788.16     13156297.05      2350923.57     13156210.24
      2351041.19     13156208.94      2351093.13     13156119.77

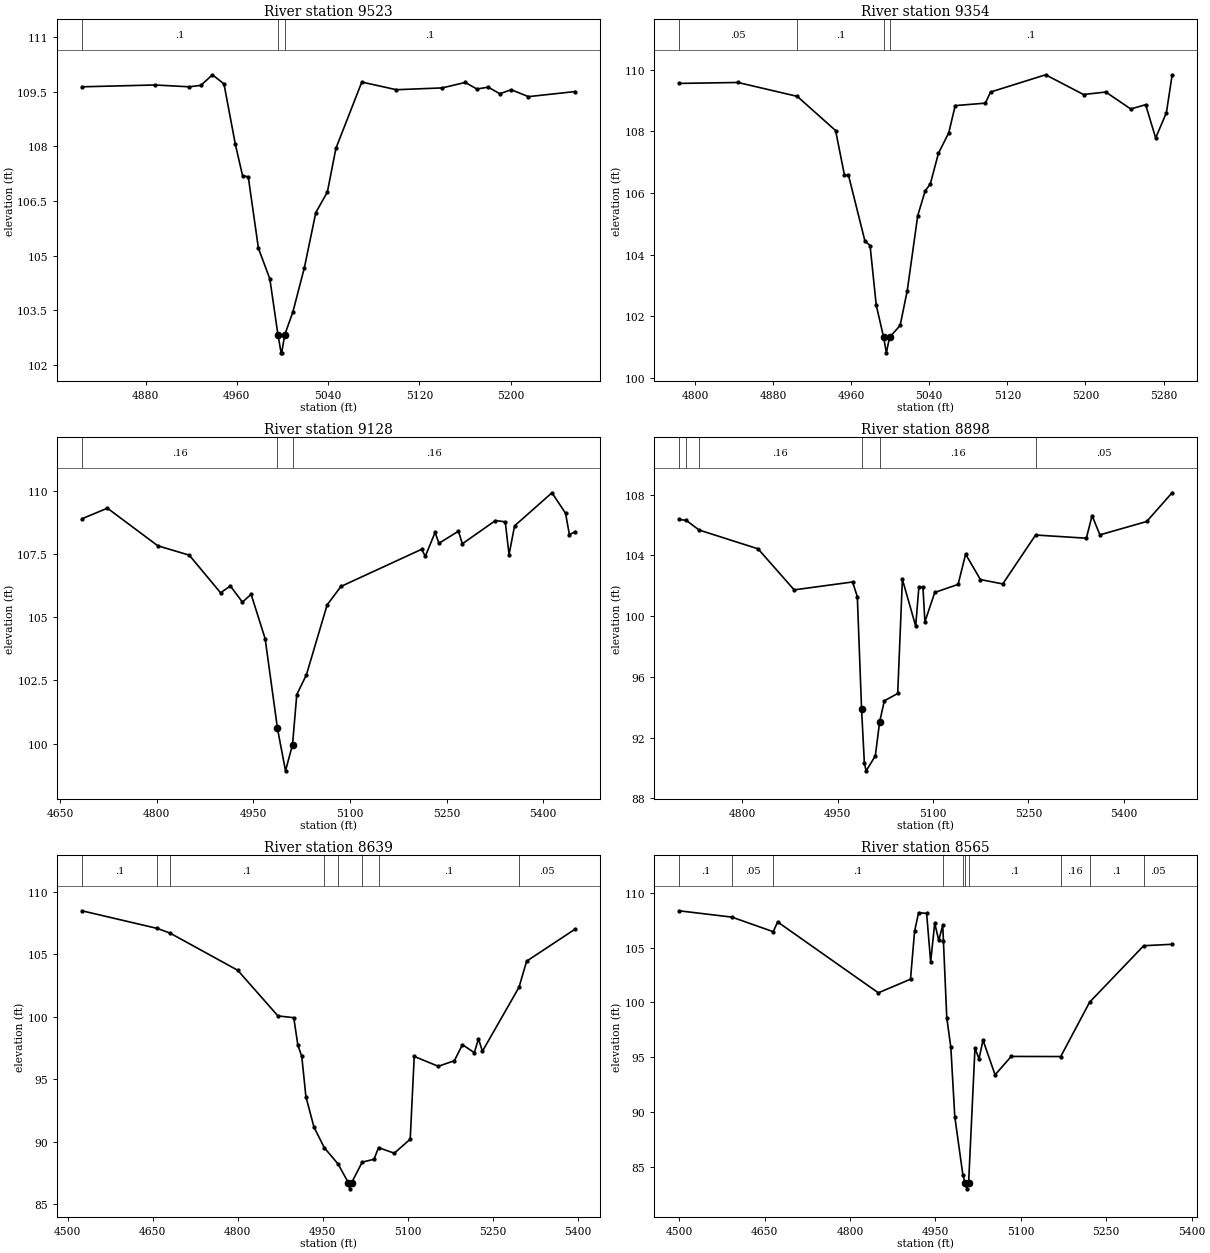
Type RM Length L Ch R = 1 ,9523    ,169,169,169
BEGIN DESCRIPTION:
UNT039 IN BACR 10.0
END DESCRIPTION:
XS GIS Cut Line= 2
       2345509.8     13158300.41      2345457.79     13157871.35
#Sta/Elev= 30
  4824.2  109.63  4888.2  109.68  4918.4  109.63  4928.5  109.67  4938.6  109.96
  4948.7  109.71  4958.7  108.05    4965  107.19    4970  107.16  4978.9   105.2
  4988.9  104.36    4996  102.83  4998.8  102.33  4999.3  102.33    5002  102.83
  5009.1  103.45  5019.2  104.67  5029.2  106.18  5039.3  106.74  5046.8  107.94
  5069.5  109.76  5099.8  109.55    5140   109.6  5160.2  109.75  5170.3  109.57
  5180.3  109.62  5190.4  109.44  5200.5  109.55  5215.5  109.36  5256.4   109.5
#Mann= 3 ,-1 , 0
  4824.2      .1       0    4996     .07       0    5002      .1       0
Bank Sta=4996,5002
XS Rating Curve= 0 ,0
Exp/Cntr=0.3,0.1

Type RM Length L Ch R = 1 ,9354    ,226,226,226
BEGIN DESCRIPTION:
UNT039 IN BACR 11.0
END DESCRIPTION:
XS GIS Cut Line= 3
      2345669.79     13158317.31      2345669.79     13158143.62
      2345558.76     13157831.36
#Sta/Elev= 30
  4783.6  109.55  4844.1  109.58  4904.8  109.13  4944.1  108.02  4953.2  106.57
  4957.3  106.57  4974.1  104.44  4979.4  104.29  4985.7  102.36  4993.3  101.31
  4996.1  100.81  4999.3  101.31  5010.2   101.7  5017.5  102.83  5028.2  105.26
  5035.8  106.06  5041.1  106.29  5049.4  107.28    5060  107.95  5066.6  108.83
  5097.5  108.91  5102.8  109.27  5159.2  109.83    5198  109.19  5220.8  109.27
  5246.4  108.72  5261.6  108.86  5271.9  107.78  5282.9   108.6  5288.7  109.81
#Mann= 4 ,-1 , 0
  4783.6     .05       0  4904.8      .1       0  4993.3     .07       0
  4999.3      .1       0
Bank Sta=4993.3,4999.3
XS Rating Curve= 0 ,0
Exp/Cntr=0.3,0.1

Type RM Length L Ch R = 1 ,9128    ,230,230,230
BEGIN DESCRIPTION:
Mapping XS 971922a0
END DESCRIPTION:
XS GIS Cut Line= 4
      2345844.02     13158374.18      2345915.62     13158170.23
      2345844.01     13157985.76      2345548.84     13157794.78
#Sta/Elev= 30
  4683.8   108.9  4723.4  109.32  4801.7  107.83  4850.5  107.46  4899.1  105.97
  4914.3  106.24    4933   105.6  4946.5  105.91  4968.3  104.15  4987.4   100.6
  4999.9   98.92  5010.8   99.96  5017.4  101.94  5032.3  102.72  5064.5  105.49
  5085.9  106.22    5211  107.69    5217  107.42  5232.1  108.36  5238.1  107.93
  5268.4  108.41  5274.4  107.91  5325.8  108.83    5341  108.78  5346.9  107.48
  5355.5  108.62  5413.5  109.93  5434.6  109.12  5440.6  108.27  5449.4  108.39
#Mann= 3 , 0 , 0
  4683.8     .16       0  4987.4     .16       0  5010.8     .16       0
Bank Sta=4987.4,5010.8
XS Rating Curve= 0 ,0
Exp/Cntr=0.3,0.1

Type RM Length L Ch R = 1 ,8898    ,259,259,259
BEGIN DESCRIPTION:
Mapping XS 2e13c781
END DESCRIPTION:
XS GIS Cut Line= 3
      2346298.61     13158192.23      2346017.22     13157935.16
       2345680.2     13157730.17
#Sta/Elev= 30
  4700.4  106.37  4712.1   106.3  4732.1  105.67  4824.9  104.43  4881.7  101.73
  4973.5  102.25    4981  101.29  4987.7   93.87  4992.1   90.32  4994.9   89.82
  5009.3    90.8  5016.1   93.04  5023.5   94.43  5044.5   94.91  5051.9  102.42
  5072.8   99.35  5077.8   101.9  5084.2   101.9  5087.3   99.63  5102.8  101.56
  5139.5  102.09  5151.3  104.08  5174.6  102.41  5209.7  102.12  5261.4  105.34
  5341.2  105.13  5350.2  106.62  5362.5  105.35  5436.1  106.23    5476  108.12
#Mann= 6 ,-1 , 0
  4700.4      .1       0  4712.1     .05       0  4732.1     .16       0
  4987.7     .05       0  5016.1     .16       0  5261.4     .05       0
Bank Sta=4987.7,5016.1
XS Rating Curve= 0 ,0
Exp/Cntr=0.3,0.1

Type RM Length L Ch R = 1 ,8639    ,74,74,74
BEGIN DESCRIPTION:
Mapping XS fd1290ea
END DESCRIPTION:
XS GIS Cut Line= 2
      2346490.71     13158082.12      2345855.33      13157488.4
#Sta/Elev= 30
  4525.2  108.48    4658  107.07  4680.4   106.7    4800  103.72  4870.9  100.07
  4898.8   99.93    4906   97.73  4912.9   96.84  4920.2   93.61  4934.4   91.18
  4952.6   89.53  4976.9   88.23  4994.9   86.74  4997.6   86.24  5000.9   86.74
  5019.4   88.37  5040.4   88.61  5048.2   89.54    5076   89.09  5104.1   90.21
  5111.2   96.83  5153.7   96.04    5182   96.49  5196.2   97.77  5217.2   97.13
  5224.5   98.25  5231.4   97.24  5295.9  102.36  5309.4  104.45  5394.8  107.01
#Mann= 8 ,-1 , 0
  4525.2      .1       0    4658     .05       0  4680.4      .1       0
  4952.6     .16       0  4976.9     .05       0  5019.4     .07       0
  5048.2      .1       0  5295.9     .05       0
Bank Sta=4994.9,5000.9
XS Rating Curve= 0 ,0
Exp/Cntr=0.3,0.1

Type RM Length L Ch R = 1 ,8565    ,95,95,95
BEGIN DESCRIPTION:
UNT039 IN BACR 9.0
END DESCRIPTION:
XS GIS Cut Line= 2
      2346525.44     13158044.37        2345912.      13157433.1
#Sta/Elev= 30
  4499.5  108.37  4592.7  107.79  4665.1  106.46  4672.9  107.35  4849.7  100.88
  4906.2  102.12  4913.3  106.48  4920.4   108.2  4934.5  108.13  4941.6   103.7
  4948.7  107.24  4955.8  105.67  4962.8  107.04    4964  105.61  4969.9   98.59
    4977   95.91    4984   89.55  4998.2   84.24  5002.2   83.48    5005   82.98
  5008.2   83.48  5019.4   95.83  5026.5   94.85  5033.5   96.56  5054.7   93.39
    5083   95.07    5170   95.06  5220.8  100.03  5315.7  105.18  5365.5  105.31
#Mann= 10 ,-1 , 0
  4499.5      .1       0  4592.7     .05       0  4665.1      .1       0
    4964     .16       0  4998.2      .1       0  5002.2     .07       0
  5008.2      .1       0    5170     .16       0  5220.8      .1       0
  5315.7     .05       0
Bank Sta=5002.2,5008.2
XS Rating Curve= 0 ,0
Exp/Cntr=0.3,0.1

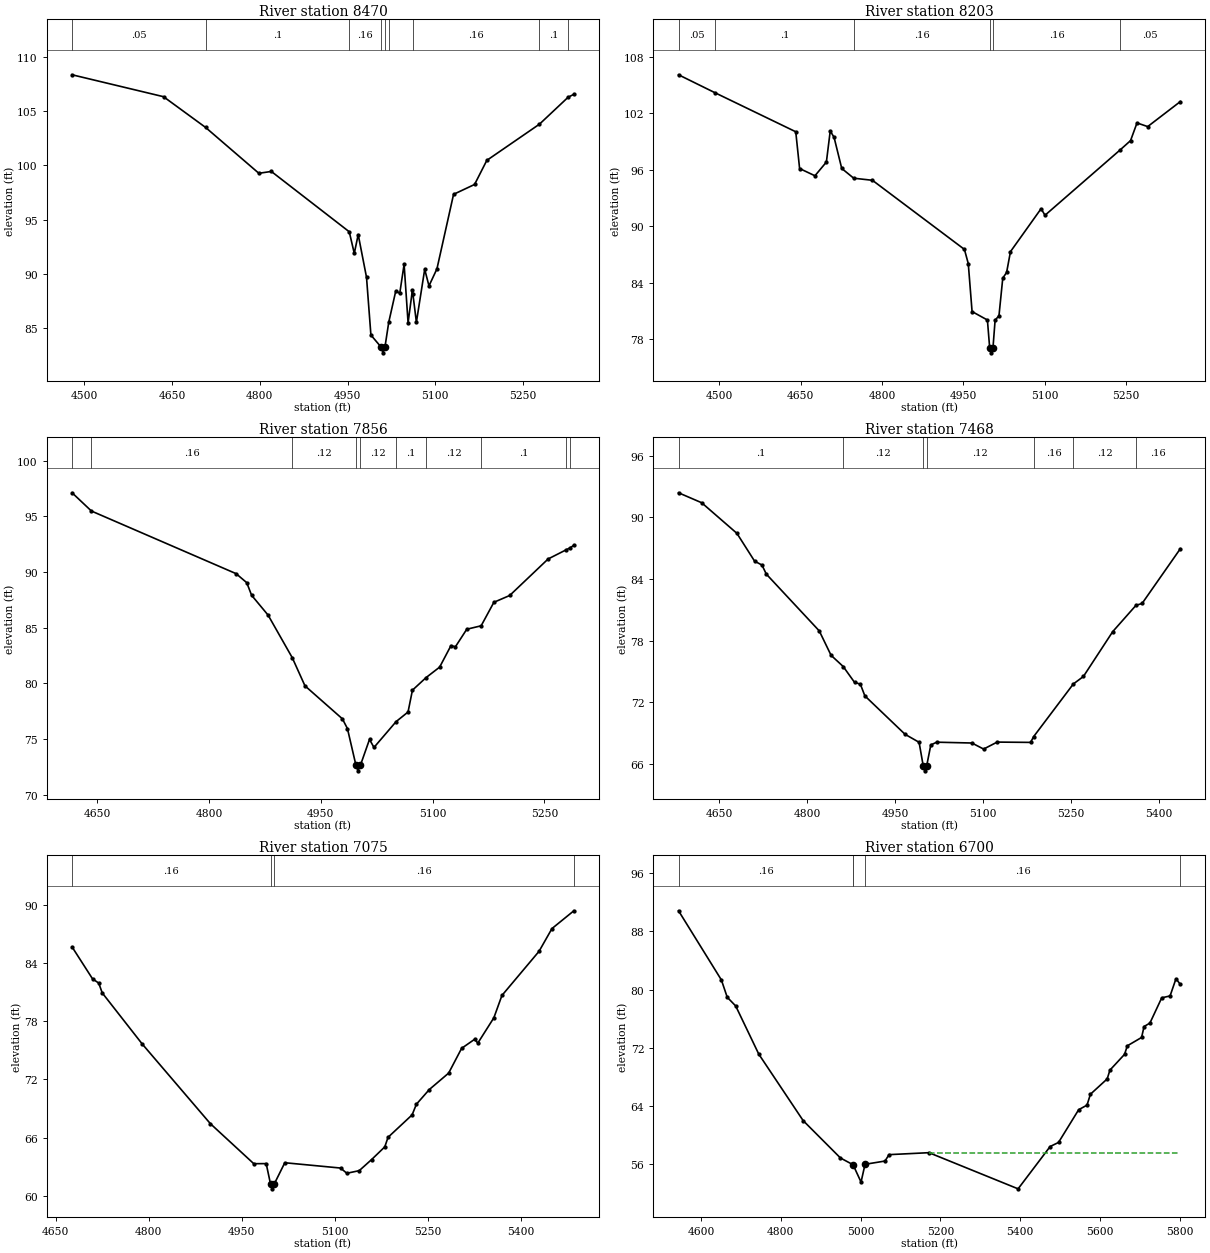
Type RM Length L Ch R = 1 ,8470    ,267,267,267
BEGIN DESCRIPTION:
Mapping XS ca386d0d
END DESCRIPTION:
XS GIS Cut Line= 2
      2346610.48     13157964.91      2345973.97     13157390.75
#Sta/Elev= 30
  4479.4  108.35  4635.6  106.33  4707.4   103.5  4798.5   99.27  4819.8   99.44
  4952.9   93.88  4961.5   91.89  4968.2   93.62  4982.4   89.68  4989.9   84.36
  5007.8   83.22  5010.5   82.72  5013.8   83.22  5020.4   85.55  5032.4   88.43
  5039.2   88.21  5046.6   90.88  5053.4   85.49  5060.8   88.51  5061.7   88.12
  5067.6   85.54  5081.8   90.42  5089.1   88.89  5102.7   90.46  5131.1   97.33
    5167   98.24  5187.9  100.46  5277.9   103.8  5326.8  106.28  5336.6  106.55
#Mann= 9 ,-1 , 0
  4479.4     .05       0  4707.4      .1       0  4952.9     .16       0
  5007.8     .07       0  5013.8     .16       0  5020.4      .1       0
  5061.7     .16       0  5277.9      .1       0  5326.8     .05       0
#XS Ineff= 2 , 0
                         5046.02           90.44
Permanent Ineff=
       F       F
Bank Sta=5007.8,5013.8
XS Rating Curve= 0 ,0
Exp/Cntr=0.3,0.1

Type RM Length L Ch R = 1 ,8203    ,347,347,347
BEGIN DESCRIPTION:
Mapping XS 6caf0039
END DESCRIPTION:
XS GIS Cut Line= 3
      2346802.41     13157837.88      2346267.37     13157295.88
      2346111.88     13157244.05
#Sta/Elev= 30
  4424.5  106.09  4492.1  104.17  4640.7  100.03  4647.8   96.12  4676.1   95.35
  4697.2   96.81  4704.3  100.12  4711.4   99.43  4725.5   96.13  4747.6   95.09
  4782.1   94.87  4951.8   87.52  4958.9   86.01  4965.9   80.91  4994.2   80.01
  4998.4   77.02  5001.1   76.52  5004.4   77.02  5008.4      80  5015.5   80.46
  5022.5   84.46  5029.6   85.07  5036.7   87.28  5093.2   91.85  5100.4   91.15
  5239.4   98.12  5258.2   99.09  5270.1  100.97  5289.8  100.58    5350  103.24
#Mann= 6 ,-1 , 0
  4424.5     .05       0  4492.1      .1       0  4747.6     .16       0
  4998.4     .07       0  5004.4     .16       0  5239.4     .05       0
Bank Sta=4998.4,5004.4
XS Rating Curve= 0 ,0
Exp/Cntr=0.3,0.1

Type RM Length L Ch R = 1 ,7856    ,388,388,388
BEGIN DESCRIPTION:
UNT039 IN BACR 8.0
END DESCRIPTION:
XS GIS Cut Line= 3
       2346912.7     13157521.83      2346705.13     13157271.56
      2346411.26     13157084.87
#Sta/Elev= 30
  4616.2   97.12  4642.2   95.48  4836.3   89.86  4850.6   89.05  4857.1   87.92
  4879.2   86.14  4911.7   82.31  4928.7   79.79  4978.9   76.83  4985.7   75.95
  4997.1   72.66  4999.8   72.16  5003.1   72.66  5015.3   74.98  5021.3   74.26
    5051   76.58    5067   77.44  5072.9    79.4  5091.2   80.53  5109.4   81.47
  5124.6    83.4  5130.5   83.29  5145.8   84.87  5165.1   85.18  5182.2   87.29
  5203.4    87.9    5255   91.18  5279.2      92  5284.5   92.18  5289.5   92.41
#Mann= 10 ,-1 , 0
  4616.2      .1       0  4642.2     .16       0  4911.7     .12       0
  4997.1     .07       0  5003.1     .12       0    5051      .1       0
  5091.2     .12       0  5165.1      .1       0  5279.2     .16       0
  5284.5      .1       0
Bank Sta=4997.1,5003.1
XS Rating Curve= 0 ,0
Exp/Cntr=0.3,0.1

Type RM Length L Ch R = 1 ,7468    ,393,393,393
BEGIN DESCRIPTION:
UNT039 IN BACR 7.0
END DESCRIPTION:
XS GIS Cut Line= 3
      2346944.86     13157386.23      2346917.06     13157066.58
      2346882.33     13156531.66
#Sta/Elev= 30
  4580.3   92.39  4619.8   91.42    4680   88.44  4710.2   85.73  4722.8   85.35
  4730.2   84.47  4820.6   78.94  4840.8   76.56  4861.5   75.47  4880.8   73.93
  4890.8   73.75  4898.5   72.61  4967.1   68.87  4991.1   68.09  4998.1   65.81
  5000.8   65.31  5004.1   65.81  5011.1   67.83  5021.1    68.1  5081.3   68.02
  5101.3   67.43  5124.4   68.11  5181.5   68.08  5186.8   68.65  5254.5   73.77
  5271.7    74.5  5321.8   78.87  5361.5   81.43  5371.9   81.61  5437.2   86.94
#Mann= 7 ,-1 , 0
  4580.3      .1       0  4861.5     .12       0  4998.1     .07       0
  5004.1     .12       0  5186.8     .16       0  5254.5     .12       0
  5361.5     .16       0
Bank Sta=4998.1,5004.1
XS Rating Curve= 0 ,0
Exp/Cntr=0.3,0.1

Type RM Length L Ch R = 1 ,7075    ,375,375,375
BEGIN DESCRIPTION:
UNT039 IN BACR 6.0
END DESCRIPTION:
XS GIS Cut Line= 3
      2347283.49     13157289.81      2347275.68     13156789.86
      2347189.74     13156492.96
#Sta/Elev= 30
  4676.3   85.71  4709.3   82.41  4719.3   81.97  4724.9   80.96  4789.3   75.68
  4899.3   67.43  4969.3   63.29  4989.3    63.3  4996.3   61.19    4999   60.69
  5002.3   61.19  5019.3   63.39  5109.3   62.84  5119.3    62.3  5139.3   62.57
  5159.3   63.72  5180.5   65.03  5185.8   66.02  5224.6   68.34  5231.5   69.44
  5252.3   70.96  5283.5   72.66  5304.4   75.22  5325.2   76.15  5330.6   75.77
  5356.4   78.38  5369.4   80.69  5429.3   85.26  5450.1   87.61  5485.4   89.45
#Mann= 4 ,-1 , 0
  4676.3     .16       0  4996.3     .07       0  5002.3     .16       0
  5485.4     .16       0
Bank Sta=4996.3,5002.3
XS Rating Curve= 0 ,0
Exp/Cntr=0.3,0.1

Type RM Length L Ch R = 1 ,6700    ,419,419,419
BEGIN DESCRIPTION:
UNT039 IN BACR 5.0
END DESCRIPTION:
XS GIS Cut Line= 4
      2347471.01     13157391.39      2347658.49     13157141.42
      2347627.24     13156617.98      2347283.52     13156375.81
#Sta/Elev= 30
    4544   90.85  4651.4   81.32    4666   78.94  4687.2   77.74  4745.1    71.1
  4856.2   61.95  4949.7    56.8  4981.3   55.87  5001.3   53.48  5011.3   55.93
  5061.4   56.38  5071.4   57.26  5171.6   57.53  5394.8   52.55  5475.1   58.38
  5496.1   58.94  5546.6   63.45  5567.5   64.08    5576   65.58    5618   67.69
  5624.9    68.9  5661.6   71.08  5668.5   72.25  5704.2    73.4  5710.5   74.91
  5725.1   75.38  5754.7   78.86  5775.6   79.12  5790.4   81.49  5801.3   80.71
#Mann= 5 ,-1 , 0
    4544     .16       0  4981.3      .1       0  4981.3     .07       0
  5011.3     .16       0  5801.3     .16       0
#XS Ineff= 2 , 0
       0                 5171.37       0   57.53
Permanent Ineff=
       F       T
Bank Sta=4981.3,5011.3
XS Rating Curve= 0 ,0
Exp/Cntr=0.3,0.1

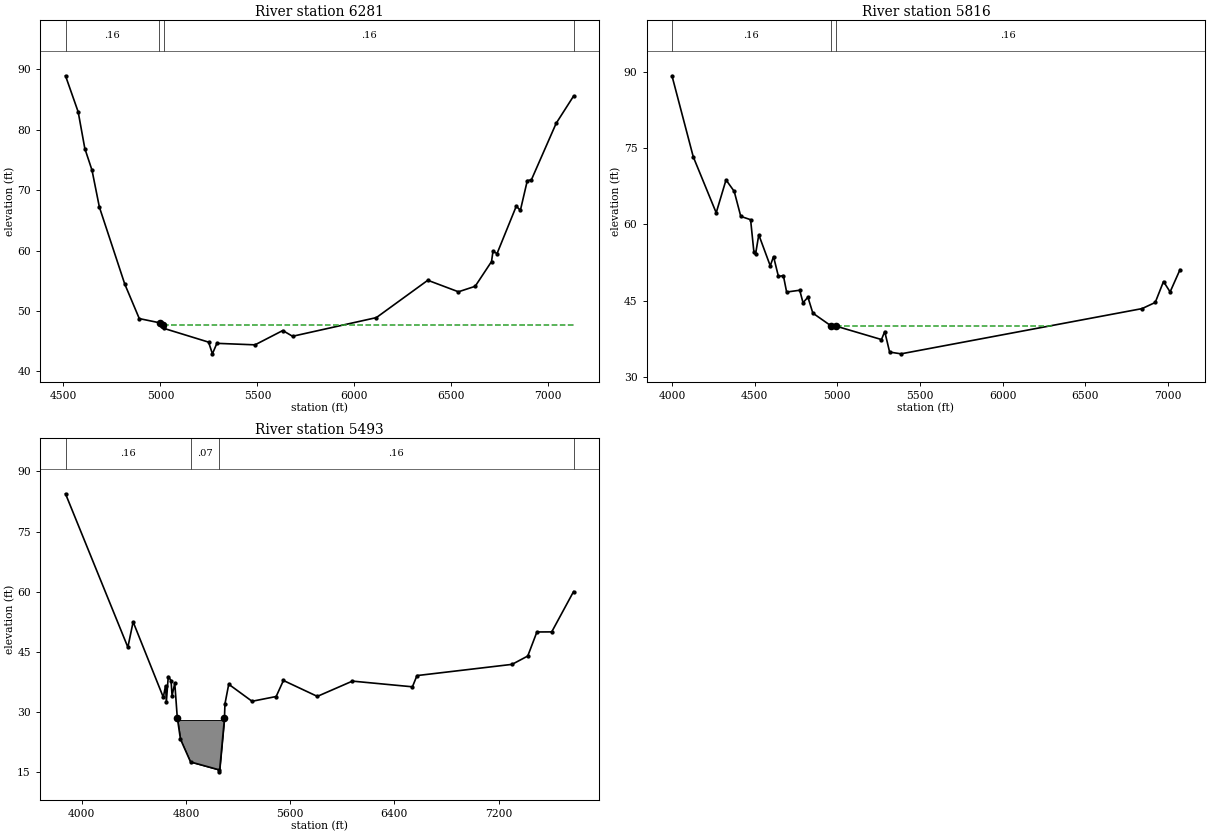
Type RM Length L Ch R = 1 ,6281    ,465,465,465
BEGIN DESCRIPTION:
UNT039 IN BACR 4.0
END DESCRIPTION:
XS GIS Cut Line= 6
      2347580.37     13157446.11      2347908.49     13157266.42
       2348166.3     13157032.04      2348150.68     13156789.86
      2347486.62     13155836.73      2347122.27     13155505.16
#Sta/Elev= 30
  4510.5   88.95  4575.9   82.96  4610.1    76.9  4647.1   73.31  4685.1    67.2
  4815.9   54.45  4890.9   48.72  4990.3   48.06  4996.9   47.97  5011.1    47.6
  5018.6   47.09  5248.2   44.82    5268   42.88    5291   44.62  5487.6   44.37
  5630.7   46.74  5681.3   45.79  6113.1   48.88  6378.5   55.07  6536.4   53.16
  6622.8   54.07  6707.1   58.17  6714.6   59.87  6735.5   59.49  6834.8   67.35
  6855.8   66.65  6891.6   71.58  6912.6   71.71  7040.3   81.07    7130   85.58
#Mann= 4 ,-1 , 0
  4510.5     .16       0  4990.3     .07       0  5018.6     .16       0
    7130     .16       0
#XS Ineff= 2 , 0
       0                 5010.83       0   47.62
Permanent Ineff=
       F       T
Bank Sta=4996.9,5011.1
XS Rating Curve= 0 ,0
Exp/Cntr=0.3,0.1

Type RM Length L Ch R = 1 ,5816    ,323,323,323
BEGIN DESCRIPTION:
Mapping XS 8011f5e9
END DESCRIPTION:
XS GIS Cut Line= 4
     2347585.057    13157498.524     2348543.404    13157054.789
     2348712.607     13156777.53     2347562.746    13155501.412
#Sta/Elev= 30
    4000 89.2166 4128.85 73.2689 4267.61 62.2608 4327.08 68.7316 4376.63 66.4761
 4416.28 61.5568 4475.75 60.9027 4495.57 54.5844 4505.48  54.071  4525.3 57.9344
 4594.68 51.8228 4614.51 53.6518 4644.24  49.728 4673.98 49.9132  4693.8 46.6699
 4773.09 47.0236 4792.91 44.5686 4822.65 45.6519 4852.38 42.5204 4961.41 40.0397
 4991.14 39.9798 5267.65 37.3224 5287.38 38.8944 5316.98 34.8596 5386.03  34.511
 6844.37 43.4081 6924.28 44.6206 6974.22 48.7412 7014.17 46.6896 7074.11 51.0768
#Mann= 3 , 0 , 0
    4000     .16       0 4961.41     .07       0 4991.14     .16       0
#XS Ineff= 1 ,-1
 5001.05 6314.04   39.97
Permanent Ineff=
       T
Bank Sta=4961.41,4991.14
XS Rating Curve= 0 ,0
Exp/Cntr=0.3,0.1

Type RM Length L Ch R = 1 ,5493    ,0,0,0
BEGIN DESCRIPTION:
UNT039 IN BACR 1.0
END DESCRIPTION:
XS GIS Cut Line= 5
      2347572.53     13157649.23      2348330.37     13157555.48
      2348869.43     13157149.23      2348908.49     13156852.36
      2347471.84     13155236.12
#Sta/Elev= 30
  3875.3   84.44  4354.1   46.16  4394.4   52.49  4626.2   33.68  4643.4   36.58
  4649.7    32.6  4664.2   38.85  4685.7   37.86  4693.4   34.06  4714.2   37.19
 4733.49   28.57  4757.9   23.21  4835.2   17.55  5054.7   15.58  5057.5   15.08
  5095.7   28.41  5099.4   32.02  5128.5   36.93  5307.5   32.68  5492.6   33.87
  5548.3   37.87  5808.7    33.9  6077.9   37.71  6538.7   36.29  6573.8   39.09
  7303.8   41.89  7424.3   43.97  7494.5   49.97  7608.2   49.99  7775.8   60.04
#Mann= 4 ,-1 , 0
  3875.3     .16       0  4835.2     .07       0  5054.7     .16       0
  7775.8     .16       0
#Block Obstruct= 1 ,-1
 4690.05  5130.1      28
Bank Sta=4733.49,5095.7
XS Rating Curve= 0 ,0
Exp/Cntr=0.3,0.1

Chan Stop Cuts=-1
Use User Specified Reach Order=0
Composite Channel Slope=5