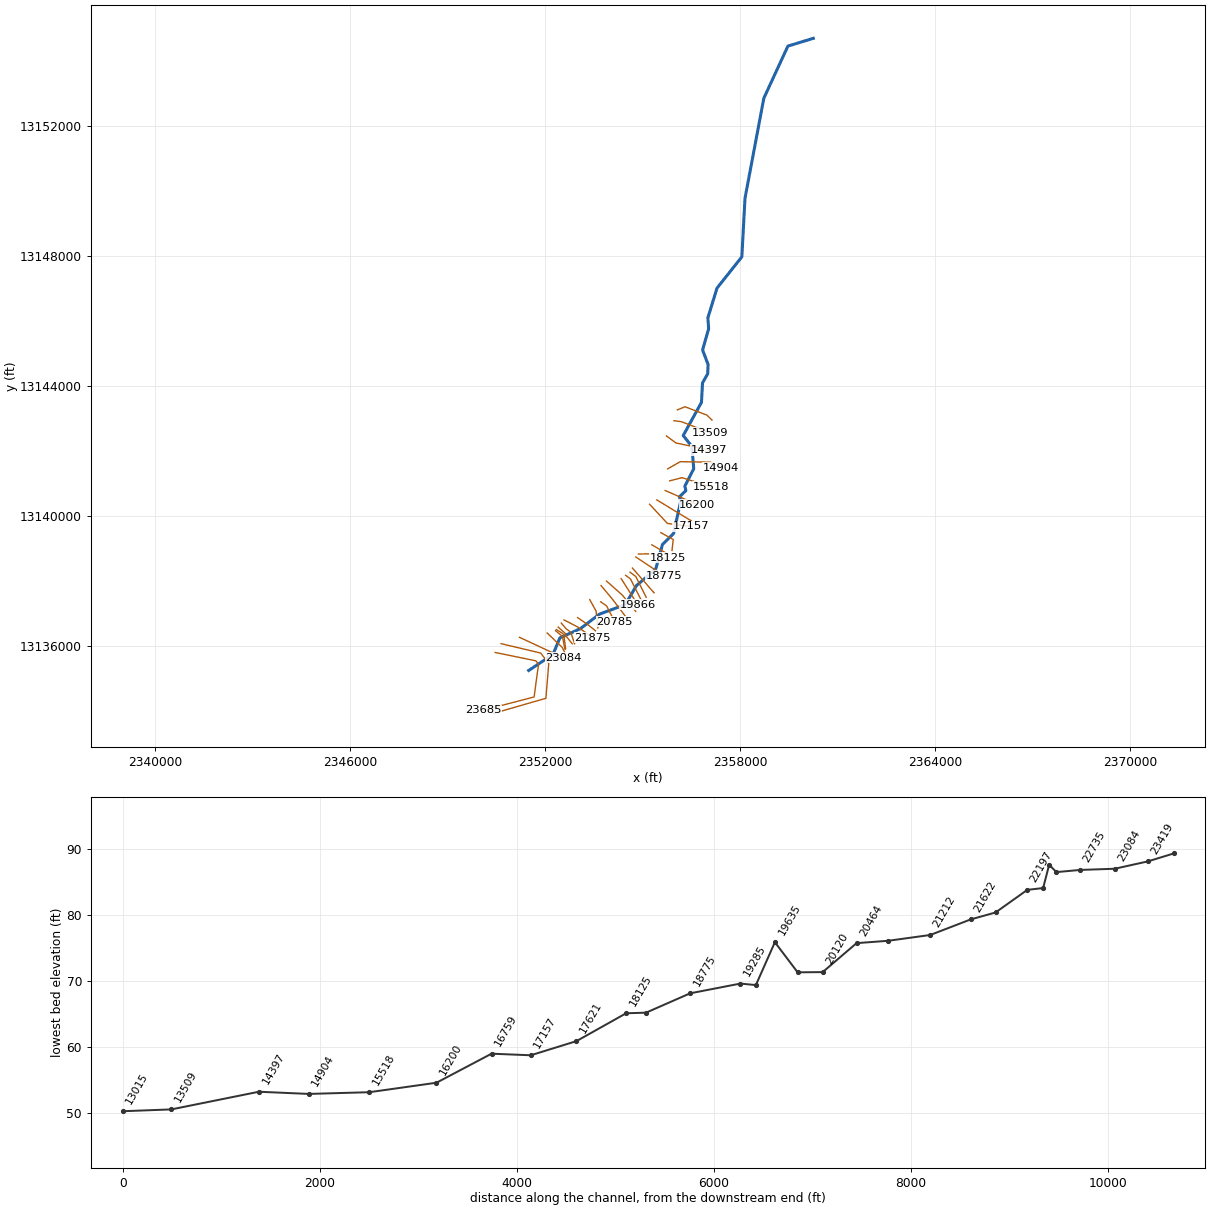
--- UNT040 IN BACR.prj (project) ---

Proj Title=UNT040 IN BACR Base Level Engineering
Current Plan=p01
Default Exp/Contr=0.3,0.1
English Units
Geom File=g01
Flow File=f01
Plan File=p01
Y Axis Title=Elevation
X Axis Title(PF)=Main Channel Distance
X Axis Title(XS)=Station
BEGIN DESCRIPTION:
UNT040 IN BACR
END DESCRIPTION:
DSS Export Rating Curves= 0
DSS Export Rating Curve Sorted= 0
DSS Export Volume Flow Curves= 0
DXF OffsetX= 0
DXF OffsetY= 0
DXF ScaleX= 1
DXF ScaleY= 10

--- UNT040 IN BACR.p01 (plan) ---

Plan Title=Multiple Run
Short Identifier=Multiple
Geom File=g01
Flow File=f01
Subcritical Flow
K Sum by GR= 0
Std Step Tol= 0.01
Critical Tol= 0.01
Num of Std Step Trials= 20
Max Error Tol= 0.3
Flow Tol Ratio= 0.001
Split Flow NTrial= 30
Split Flow Tol= 0.02
Split Flow Ratio= 0.02
Log Output Level= 0
Friction Slope Method= 1
Unsteady Friction Slope Method= 2
Unsteady Bridges Friction Slope Method= 1
Parabolic Critical Depth
Global Vel Dist=  1 , 1 , 1
Global Log Level= 0
CheckData=True
Encroach Param= -1, 0, 0, 0
BEGIN DESCRIPTION:
Multiple Run
END DESCRIPTION:

--- UNT040 IN BACR.f01 (steady flow) ---

Flow Title=Multiple
Number of Profiles=7
Profile Names=10-year,25-year,50-year,1pct_min,100-year,1pct_plu,500-year
River Rch & RM= UNT040 IN BACR,Reach-1,23685
     429     567     673     583     788    1066    1093
River Rch & RM= UNT040 IN BACR,Reach-1,21622
     655     897    1094     972    1315    1778    1921
River Rch & RM= UNT040 IN BACR,Reach-1,16759
     854    1187    1461    1311    1773    2397    2638
River Rch & RM= UNT040 IN BACR,Reach-1,12385
     925    1290    1592    1432    1936    2619    2895
River Rch & RM= UNT040 IN BACR,Reach-1,10884
    1006    1410    1744    1573    2128    2878    3199
River Rch & RM= UNT040 IN BACR,Reach-1,9568
    1062    1494    1854    1677    2268    3067    3428
River Rch & RM= UNT040 IN BACR,Reach-1,5958
    1096    1545    1919    1737    2350    3178    3560
Boundary for River Rch & Prof#=UNT040 IN BACR,Reach-1,1
Up Type=0
Dn Type=3
Dn Slope=0.005
Boundary for River Rch & Prof#=UNT040 IN BACR,Reach-1,2
Up Type=0
Dn Type=3
Dn Slope=0.005
Boundary for River Rch & Prof#=UNT040 IN BACR,Reach-1,3
Up Type=0
Dn Type=3
Dn Slope=0.005
Boundary for River Rch & Prof#=UNT040 IN BACR,Reach-1,4
Up Type=0
Dn Type=3
Dn Slope=0.005
Boundary for River Rch & Prof#=UNT040 IN BACR,Reach-1,5
Up Type=0
Dn Type=3
Dn Slope=0.005
Boundary for River Rch & Prof#=UNT040 IN BACR,Reach-1,6
Up Type=0
Dn Type=3
Dn Slope=0.005
Boundary for River Rch & Prof#=UNT040 IN BACR,Reach-1,7
Up Type=0
Dn Type=3
Dn Slope=0.005

--- UNT040 IN BACR.g01 (geometry) ---

Geom Title=Existing Conditions
Program Version=4.10

River Reach=UNT040 IN BACR  ,Reach-1
Reach XY= 30
        2351495.     13135242.44       2352244.2     13135739.91
      2352456.88     13136247.73      2353088.08     13136530.15
      2353672.95     13136976.31       2354469.4     13137270.09
      2354808.98     13137851.86      2355404.31     13138358.32
      2355613.01     13139119.39      2355953.92     13139458.12
      2356180.72     13140478.28      2356132.91     13140585.19
      2356334.22     13140778.55      2356301.47     13140915.48
      2356575.99     13141452.57      2356515.97      13142141.3
      2356251.51     13142472.85      2356813.37     13143493.86
      2356845.15     13144091.19       2357004.5     13144371.67
      2357017.52     13144658.77      2356847.53     13145106.77
       2357034.5     13145762.53      2357010.28     13146095.81
      2357291.43     13147010.13      2358055.84     13147972.18
      2358152.94     13149775.27      2358732.37     13152853.62
      2359473.82     13154458.75      2360255.26     13154696.86

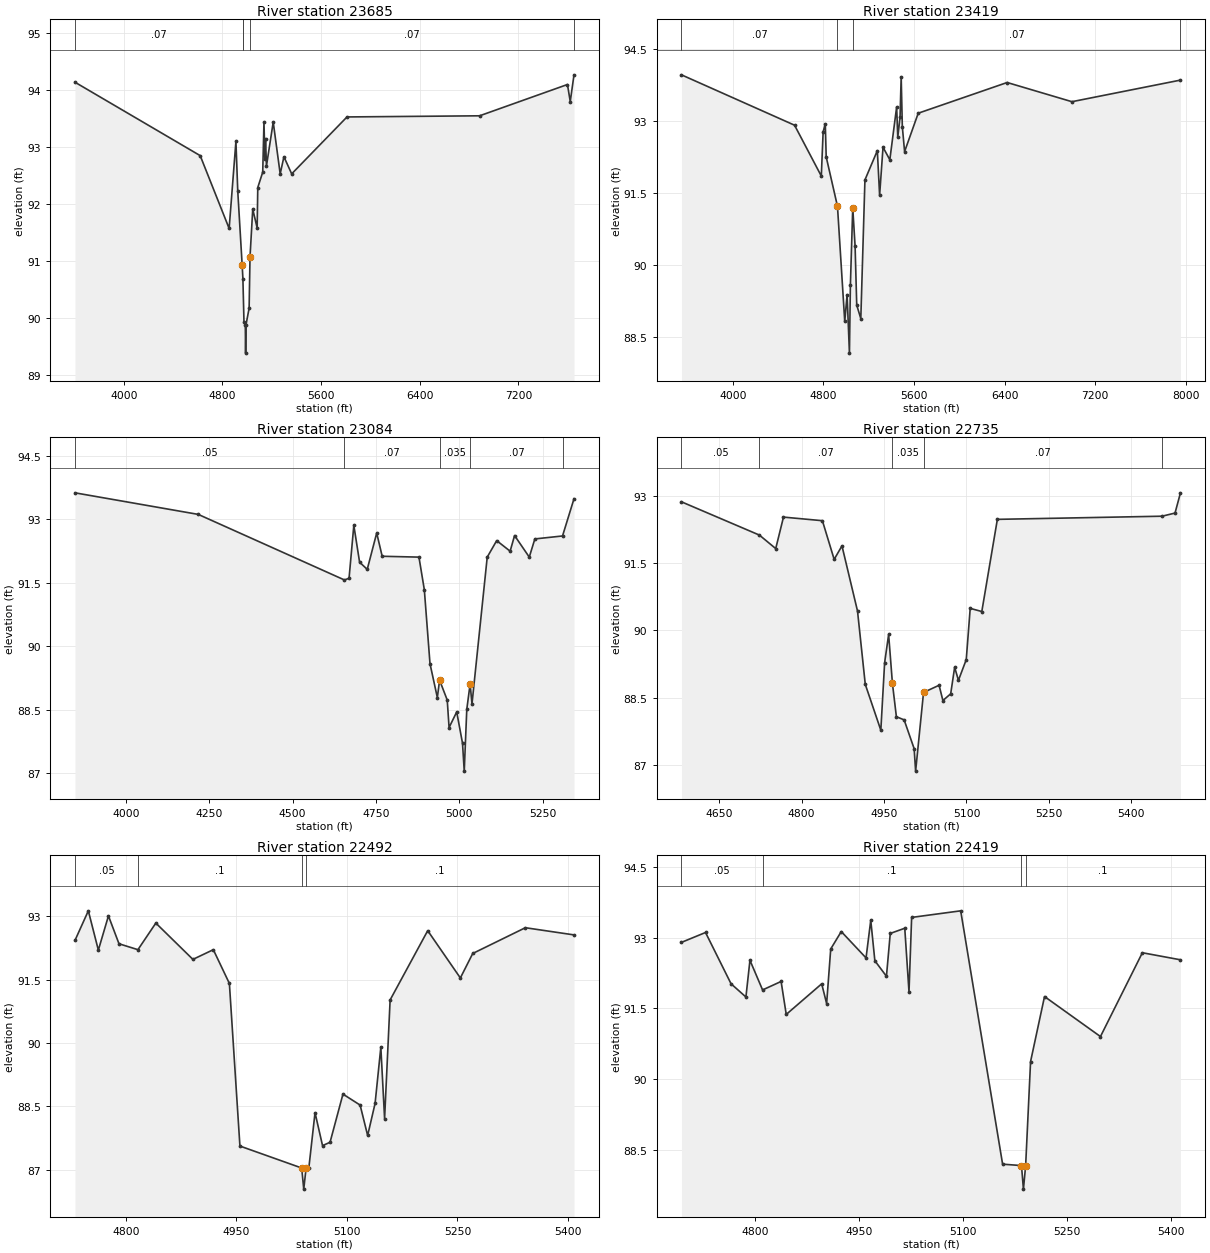
Type RM Length L Ch R = 1 ,23685   ,266,266,266
BEGIN DESCRIPTION:
UNT040 IN BACR 30.0
END DESCRIPTION:
XS GIS Cut Line= 6
      2350462.92     13135797.88      2351719.06     13135540.06
      2351801.01     13135423.97      2351770.17     13135227.58
       2351663.4      13134428.1      2350098.32     13134019.25
#Sta/Elev= 30
  3603.8   94.14  4619.3   92.85  4854.1   91.57  4909.1    93.1  4923.9   92.23
  4959.6   90.93  4965.7   90.69  4974.4   89.93    4985   89.88  4987.7   89.38
    4991   89.88  5016.2   90.17  5023.4   91.07  5045.5   91.91  5081.3   91.58
  5086.4   92.29  5126.5   92.56  5136.6   93.44  5143.9   92.79    5149   93.15
  5156.9   92.67  5211.6   93.44  5268.1   92.53  5298.4   92.83  5361.4   92.53
    5810   93.53  6885.5   93.55  7598.1    94.1  7620.8    93.8  7651.2   94.27
#Mann= 5 ,-1 , 0
  3603.8     .07       0  4965.7      .1       0  4965.7    .035       0
  5023.4     .07       0  7651.2     .05       0
Bank Sta=4959.6,5023.4
XS Rating Curve= 0 ,0
Exp/Cntr=0.3,0.1

Type RM Length L Ch R = 1 ,23419   ,335,335,335
BEGIN DESCRIPTION:
Mapping XS 071b4e90
END DESCRIPTION:
XS GIS Cut Line= 5
      2350645.21     13136068.71      2351863.92     13135779.66
      2352113.92     13135456.74      2352025.38     13134386.43
      2350415.98     13133922.88
#Sta/Elev= 30
  3544.8   93.96  4544.3   92.91  4780.7   91.85  4796.7   92.77  4815.8   92.94
  4823.9   92.25  4923.5   91.22  4987.8   88.82  5008.6   89.38  5029.2   88.16
  5037.6   89.57  5058.4   91.19  5079.2   90.39  5093.7   89.16  5129.7   88.88
  5166.2   91.77  5275.8   92.38  5295.9   91.45    5326   92.45  5386.2   92.19
  5446.4   93.29  5456.4   92.66  5476.5   93.08  5486.5   93.92  5496.6   92.88
  5516.6   92.36  5637.1   93.16  6422.9    93.8  6995.3    93.4  7954.5   93.85
#Mann= 4 ,-1 , 0
  3544.8     .07       0  4923.5    .035       0  5058.4     .07       0
  7954.5     .05       0
Bank Sta=4923.5,5058.4
XS Rating Curve= 0 ,0
Exp/Cntr=0.3,0.1

Type RM Length L Ch R = 1 ,23084   ,349,349,349
BEGIN DESCRIPTION:
Mapping XS 245fb052
END DESCRIPTION:
XS GIS Cut Line= 2
      2351212.56     13136263.51      2352569.26     13135632.42
#Sta/Elev= 30
  3847.3   93.63  4216.9   93.12  4655.2   91.57  4669.1   91.61  4683.4   92.86
  4700.7   91.99  4723.6   91.82    4752   92.68  4768.4   92.13  4878.7   92.11
  4894.8   91.34  4911.8   89.59  4933.8   88.79  4940.6    89.2  4963.5   88.73
    4969   88.08  4991.9   88.45  5009.3   87.71  5014.5   87.05  5022.1   88.51
  5032.1   89.11  5037.7   88.64  5083.4   92.11  5111.8    92.5  5152.1   92.25
  5165.4   92.62  5209.5   92.11  5226.2   92.54  5309.2   92.61  5343.6   93.49
#Mann= 5 ,-1 , 0
  3847.3     .05       0  4655.2     .07       0  4940.6    .035       0
  5032.1     .07       0  5309.2     .05       0
Bank Sta=4940.6,5032.1
XS Rating Curve= 0 ,0
Exp/Cntr=0.3,0.1

Type RM Length L Ch R = 1 ,22735   ,243,243,243
BEGIN DESCRIPTION:
UNT040 IN BACR 29.0
END DESCRIPTION:
XS GIS Cut Line= 3
      2352064.61     13136396.39      2352526.72     13135955.55
      2352648.42      13135715.5
#Sta/Elev= 30
  4581.5   92.86  4723.3   92.12    4753   91.82  4767.1   92.52  4837.9   92.44
  4859.3   91.58  4873.5   91.88  4901.8   90.43  4915.9    88.8  4944.2   87.78
  4951.1   89.28  4958.4   89.91  4965.3   88.82  4972.5   88.08  4986.6   88.01
  5004.8   87.37  5007.5   86.87  5021.9   88.62  5050.2   88.78  5057.1   88.44
  5071.3   88.59  5078.5   89.18  5085.4   88.89  5099.6   89.35  5106.8   90.49
  5127.9   90.42  5156.2   92.47  5455.8   92.54  5479.4   92.61  5489.3   93.06
#Mann= 5 ,-1 , 0
  4581.5     .05       0  4723.3     .07       0  4965.3    .035       0
  5021.9     .07       0  5455.8     .05       0
Bank Sta=4965.3,5021.9
XS Rating Curve= 0 ,0
Exp/Cntr=0.3,0.1

Type RM Length L Ch R = 1 ,22492   ,73,73,73
BEGIN DESCRIPTION:
Mapping XS e3bbb49a
END DESCRIPTION:
XS GIS Cut Line= 4
      2352323.31     13136467.12      2352505.14      13136316.1
      2352542.12     13136251.38      2352612.76     13135892.07
#Sta/Elev= 30
    4731   92.43  4749.1   93.13  4762.7    92.2  4776.4   93.01  4790.7   92.35
  4816.4   92.21  4840.7   92.84    4891   91.98  4918.7   92.21  4940.5   91.41
  4954.8   87.56  5038.6   87.04  5041.4   86.54  5044.6   87.04  5048.3   87.04
  5056.7   88.35  5066.9   87.57  5077.1   87.65  5094.6   88.79  5117.9   88.53
  5128.1   87.81  5138.2   88.57    5146    89.9  5151.1   88.21  5158.6   91.02
  5209.6   92.66  5253.9   91.54  5270.7   92.12  5342.1   92.73  5408.1   92.56
#Mann= 4 ,-1 , 0
    4731     .05       0  4816.4      .1       0  5038.6     .07       0
  5044.6      .1       0
Bank Sta=5038.6,5044.6
XS Rating Curve= 0 ,0
Exp/Cntr=0.3,0.1

Type RM Length L Ch R = 1 ,22419   ,61,61,61
BEGIN DESCRIPTION:
Mapping XS 114b4194
END DESCRIPTION:
XS GIS Cut Line= 6
      2352344.91     13136500.99      2352532.88     13136386.98
       2352579.1     13136343.83      2352594.51     13136294.53
      2352594.51     13136217.49      2352631.49      13135912.4
#Sta/Elev= 30
  4694.3    92.9    4729   93.11  4765.8   92.02  4787.2   91.74    4793   92.52
  4811.2   91.89  4837.9   92.07  4845.3   91.37  4896.4   92.02  4903.5    91.6
  4909.4   92.76  4924.6   93.13  4960.3   92.57  4967.1   93.37    4973   92.51
  4989.7   92.18  4995.2   93.09  5016.1    93.2  5022.2   91.85    5026   93.43
  5096.7   93.57  5157.1   88.19  5184.3   88.16  5187.1   87.66  5190.3   88.16
  5197.4   90.37  5217.5   91.75  5298.1    90.9  5358.5   92.68  5413.4   92.53
#Mann= 4 ,-1 , 0
  4694.3     .05       0  4811.2      .1       0  5184.3     .07       0
  5190.3      .1       0
Bank Sta=5184.3,5190.3
XS Rating Curve= 0 ,0
Exp/Cntr=0.3,0.1

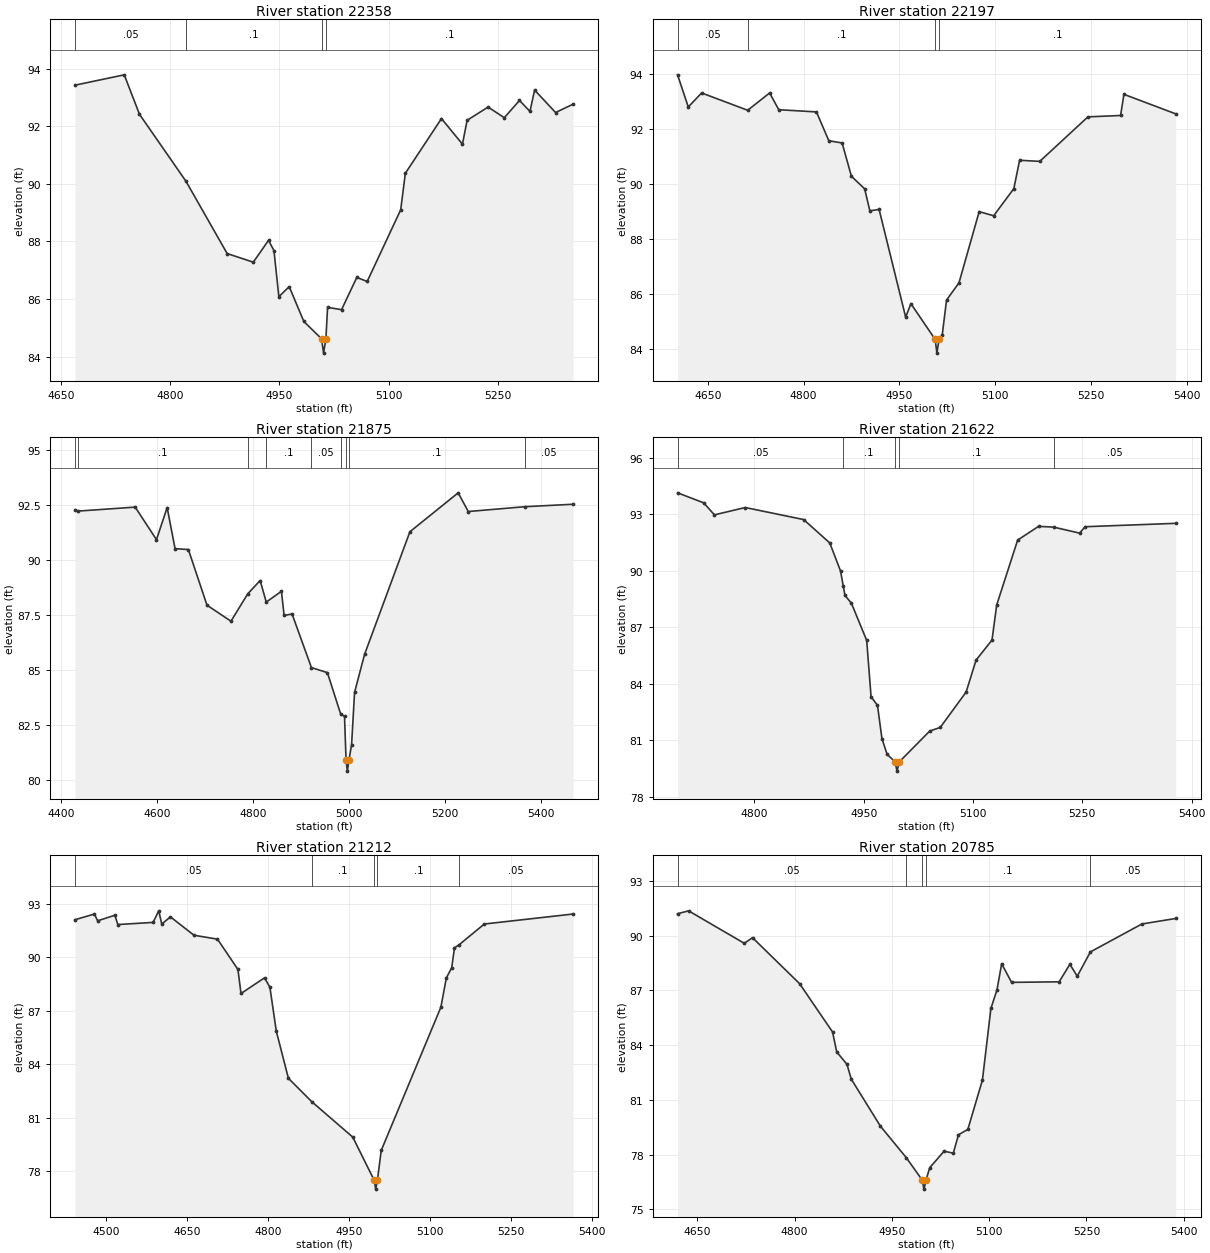
Type RM Length L Ch R = 1 ,22358   ,161,161,161
BEGIN DESCRIPTION:
Mapping XS c4f7ebe9
END DESCRIPTION:
XS GIS Cut Line= 4
      2352403.47     13136578.02      2352631.49     13136374.65
      2352659.23     13136285.28      2352837.95     13136063.42
#Sta/Elev= 30
  4669.3   93.43    4737   93.79  4757.9   92.42  4821.8   90.09  4878.3   87.58
  4914.2   87.28  4935.1   88.04  4942.6   87.68  4949.3   86.08  4963.5   86.43
  4983.6   85.22  5007.9   84.62  5010.7   84.12  5013.9   84.62  5016.2   85.71
  5035.4   85.63  5056.3   86.75  5070.6   86.61  5116.6    89.1    5123   90.37
  5172.6   92.27  5201.4   91.38  5207.8   92.21  5236.6   92.67  5258.9    92.3
  5279.7    92.9  5294.1   92.52  5300.5   93.26  5329.3   92.48  5353.3   92.77
#Mann= 4 ,-1 , 0
  4669.3     .05       0  4821.8      .1       0  5007.9     .07       0
  5013.9      .1       0
Bank Sta=5007.9,5013.9
XS Rating Curve= 0 ,0
Exp/Cntr=0.3,0.1

Type RM Length L Ch R = 1 ,22197   ,322,322,322
BEGIN DESCRIPTION:
Mapping XS 22c0bd32
END DESCRIPTION:
XS GIS Cut Line= 4
      2352498.98      13136701.3      2352637.66     13136537.98
      2352791.74     13136417.79      2352908.85     13136066.47
#Sta/Elev= 30
  4602.5   93.97  4619.3    92.8  4640.2   93.31  4712.3   92.68  4746.7   93.31
    4761    92.7    4820   92.62  4839.4   91.57  4860.2   91.49  4874.7   90.28
  4895.5   89.82  4903.6   89.02  4918.1   89.07  4959.7   85.15  4967.9   85.64
  5005.9   84.34  5008.6   83.84  5011.9   84.34  5016.9   84.49  5023.7   85.77
  5043.2    86.4  5074.8   88.99  5097.5   88.84  5129.1   89.83  5138.1   90.86
  5169.7   90.82  5245.1   92.44  5296.2   92.49  5301.5   93.26  5382.5   92.55
#Mann= 4 ,-1 , 0
  4602.5     .05       0  4712.3      .1       0  5005.9     .07       0
  5011.9      .1       0
Bank Sta=5005.9,5011.9
XS Rating Curve= 0 ,0
Exp/Cntr=0.3,0.1

Type RM Length L Ch R = 1 ,21875   ,253,253,253
BEGIN DESCRIPTION:
UNT040 IN BACR 28.0
END DESCRIPTION:
XS GIS Cut Line= 3
      2352582.15     13136799.94      2353022.86     13136571.88
      2353460.44     13136254.48
#Sta/Elev= 30
  4429.2    92.3  4436.4   92.24  4554.6   92.42  4598.9   90.94  4621.1    92.4
  4637.6   90.53  4665.3   90.49    4704   87.96  4753.9   87.23    4789   88.48
  4814.7   89.08  4827.4    88.1    4859   88.59  4864.6   87.49  4881.1   87.56
  4921.4   85.12  4954.7   84.89  4982.2   83.01  4990.3    82.9  4993.5   80.91
  4996.2   80.41  4999.5   80.91    5005   81.61  5011.2   83.99    5032   85.72
  5126.4    91.3  5226.9   93.07  5247.8   92.22  5366.6   92.44    5466   92.55
#Mann= 9 ,-1 , 0
  4429.2     .05       0  4436.4      .1       0    4789     .05       0
  4827.4      .1       0  4921.4     .05       0  4982.2      .1       0
  4993.5     .07       0  4999.5      .1       0  5366.6     .05       0
Bank Sta=4993.5,4999.5
XS Rating Curve= 0 ,0
Exp/Cntr=0.3,0.1

Type RM Length L Ch R = 1 ,21622   ,410,410,410
BEGIN DESCRIPTION:
UNT040 IN BACR 27.0
END DESCRIPTION:
XS GIS Cut Line= 3
      2353001.29      13136870.8      2353331.03     13136642.75
      2353549.79     13136464.04
#Sta/Elev= 30
  4694.7   94.13  4730.5    93.6  4745.3   92.96  4787.6   93.35  4867.7   92.71
  4903.5   91.47  4918.3   89.98    4922   89.19  4924.4   88.68  4933.2   88.27
  4954.2   86.29  4960.2    83.3    4969   82.84  4975.1   81.08  4982.2   80.24
  4993.1   79.85  4995.8   79.35  4999.1   79.85  5040.7   81.48  5055.1   81.67
  5090.6   83.55  5104.3   85.25  5126.1   86.31  5132.6   88.18  5161.3   91.62
    5190   92.35  5210.5   92.31  5246.3   91.99  5253.9   92.33  5378.1   92.51
#Mann= 5 ,-1 , 0
  4694.7     .05       0    4922      .1       0  4993.1     .07       0
  4999.1      .1       0  5210.5     .05       0
Bank Sta=4993.1,4999.1
XS Rating Curve= 0 ,0
Exp/Cntr=0.3,0.1

Type RM Length L Ch R = 1 ,21212   ,427,427,427
BEGIN DESCRIPTION:
Mapping XS b3577932
END DESCRIPTION:
XS GIS Cut Line= 3
      2353375.62     13137423.76      2353570.64     13137068.55
      2353626.36     13136553.18
#Sta/Elev= 30
  4442.1   92.11  4478.1   92.43  4484.2   92.05    4516   92.36  4521.7   91.84
    4587   91.96  4597.4   92.61  4603.1   91.87  4619.2   92.27  4662.8   91.24
  4706.4   91.02  4744.3   89.32    4750   87.97  4793.6   88.85  4803.6   88.32
  4815.4   85.86  4837.9   83.21  4881.5   81.89  4957.2   79.91  4996.9   77.49
  4999.7   76.99  5002.9   77.49    5010   79.16  5120.6    87.2  5130.7   88.84
  5140.7   89.42  5145.8   90.53  5154.6   90.71  5201.1   91.87  5365.7   92.43
#Mann= 5 ,-1 , 0
  4442.1     .05       0  4881.5      .1       0  4996.9     .07       0
  5002.9      .1       0  5154.6     .05       0
Bank Sta=4996.9,5002.9
XS Rating Curve= 0 ,0
Exp/Cntr=0.3,0.1

Type RM Length L Ch R = 1 ,20785   ,321,321,321
BEGIN DESCRIPTION:
UNT040 IN BACR 26.0
END DESCRIPTION:
XS GIS Cut Line= 3
      2353713.17     13137354.61      2353894.97     13137228.27
      2354144.47     13136741.59
#Sta/Elev= 30
  4619.4    91.2  4636.4   91.36  4722.4   89.58    4735   89.89  4807.6   87.37
  4858.5   84.72  4864.9   83.63  4880.7   82.95  4887.3   82.14  4932.3   79.56
  4972.3   77.83  4996.7   76.61  4999.5   76.11  5002.7   76.61  5008.3   77.28
  5030.5   78.19  5044.7   78.08  5052.7   79.09  5067.1   79.38  5089.6   82.08
  5102.7   86.01  5112.1   87.03  5119.3   88.46  5134.6   87.44    5208   87.47
  5224.5   88.43  5235.9   87.78  5256.2   89.11  5335.6   90.64  5387.7   90.94
#Mann= 5 ,-1 , 0
  4619.4     .05       0  4972.3      .1       0  4996.7     .07       0
  5002.7      .1       0  5256.2     .05       0
Bank Sta=4996.7,5002.7
XS Rating Curve= 0 ,0
Exp/Cntr=0.3,0.1

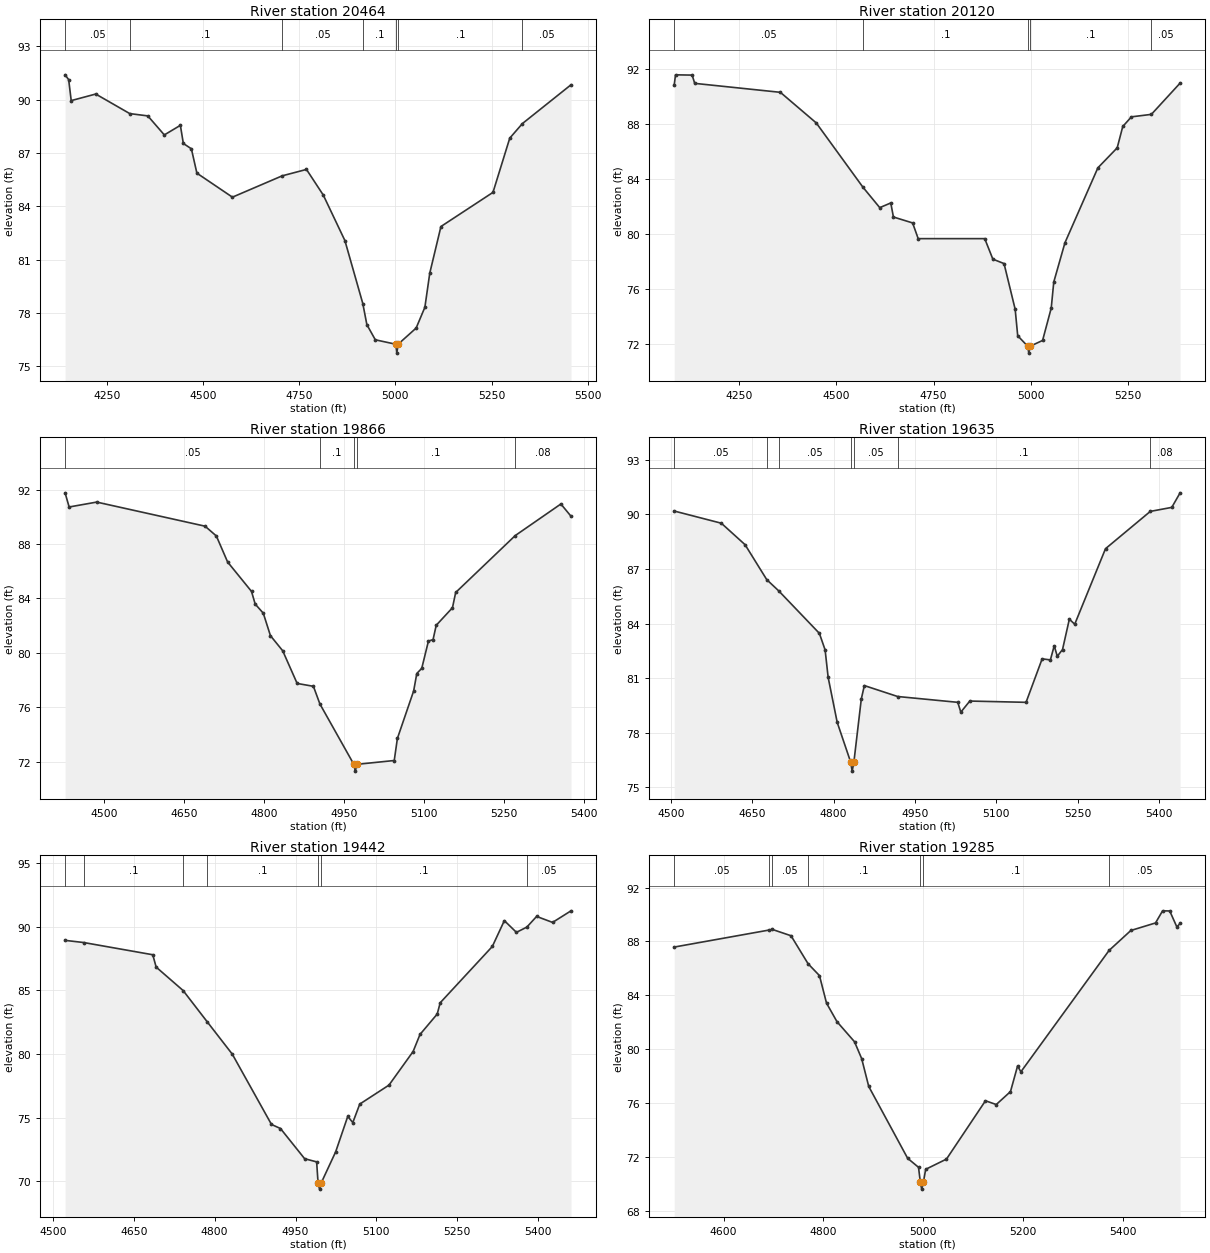
Type RM Length L Ch R = 1 ,20464   ,344,344,344
BEGIN DESCRIPTION:
UNT040 IN BACR 25.0
END DESCRIPTION:
XS GIS Cut Line= 3
      2353723.83     13137855.55      2354051.18     13137465.52
      2354538.68      13136824.8
#Sta/Elev= 30
    4142    91.4  4151.3   91.13  4157.9   89.95  4221.6   90.32    4310   89.22
  4356.9   89.09  4399.8   88.02  4441.5   88.56  4449.2   87.54  4470.1   87.24
  4484.4   85.87  4576.7   84.52    4706   85.72  4769.1   86.08  4812.7   84.64
  4868.9   82.08  4915.4   78.54    4926   77.35  4947.9    76.5  5001.1   76.25
  5003.8   75.75  5007.1   76.25    5054   77.16  5076.7   78.33  5089.4   80.25
  5118.4   82.87  5253.6   84.79  5297.2   87.84  5330.1   88.66  5456.3   90.84
#Mann= 7 ,-1 , 0
    4142     .05       0    4310      .1       0    4706     .05       0
  4915.4      .1       0  5001.1     .07       0  5007.1      .1       0
  5330.1     .05       0
Bank Sta=5001.1,5007.1
XS Rating Curve= 0 ,0
Exp/Cntr=0.3,0.1

Type RM Length L Ch R = 1 ,20120   ,254,254,254
BEGIN DESCRIPTION:
Mapping XS 1008ea6a
END DESCRIPTION:
XS GIS Cut Line= 3
      2353890.99     13137994.81      2354371.54     13137569.98
      2354789.27     13137061.73
#Sta/Elev= 30
    4084    90.8  4087.4   91.55  4130.1   91.53  4136.7   90.93  4356.7   90.28
  4448.8   88.06  4568.8   83.39  4611.9   81.91  4640.2   82.25    4647   81.23
  4696.3    80.8  4710.6   79.66  4881.5   79.66  4902.4   78.17  4931.1   77.85
  4959.7   74.53  4966.2   72.61  4991.9   71.85  4994.7   71.35  4997.9   71.85
  5030.1   72.27  5052.3   74.62  5058.8   76.51  5087.5   79.36  5172.1    84.8
  5221.7   86.25    5236    87.8  5258.2    88.5  5309.5   88.68  5383.3   90.95
#Mann= 5 ,-1 , 0
    4084     .05       0  4568.8      .1       0  4991.9     .07       0
  4997.9      .1       0  5309.5     .05       0
Bank Sta=4991.9,4997.9
XS Rating Curve= 0 ,0
Exp/Cntr=0.3,0.1

Type RM Length L Ch R = 1 ,19866   ,231,231,231
BEGIN DESCRIPTION:
UNT040 IN BACR 24.0
END DESCRIPTION:
XS GIS Cut Line= 2
      2354340.93     13138071.86      2354850.03     13137271.21
#Sta/Elev= 30
  4426.4   91.76    4434   90.72  4485.7   91.08  4688.9   89.31  4710.1   88.59
  4731.2   86.68    4776   84.52  4782.9   83.59  4798.1   82.92  4811.5   81.27
  4834.5   80.16  4861.6   77.76  4892.1   77.55  4904.3   76.25  4967.9   71.82
  4970.6   71.32  4973.9   71.82  5043.7    72.1  5049.6   73.72  5080.1   77.21
    5086   78.49  5095.3   78.87  5107.8   80.87  5116.5   80.98  5122.4   82.03
  5152.9   83.32  5158.9   84.44  5270.6   88.62  5356.2   90.94  5375.2   90.04
#Mann= 5 ,-1 , 0
  4426.4     .05       0  4904.3      .1       0  4967.9     .07       0
  4973.9      .1       0  5270.6     .08       0
Bank Sta=4967.9,4973.9
XS Rating Curve= 0 ,0
Exp/Cntr=0.3,0.1

Type RM Length L Ch R = 1 ,19635   ,193,193,193
BEGIN DESCRIPTION:
UNT040 IN BACR 23.0
END DESCRIPTION:
XS GIS Cut Line= 3
      2354480.11     13138171.86      2354628.24     13138060.47
      2354967.31     13137393.44
#Sta/Elev= 30
  4505.7   90.18  4592.7   89.51  4636.5   88.33  4676.5   86.41  4698.7   85.79
  4773.6   83.46  4784.2   82.55  4789.8   81.04  4806.5   78.57  4831.3   76.39
  4834.1   75.89  4837.3   76.39    4851   79.86  4856.6   80.59    4918   79.99
    5029   79.67  5034.6   79.13  5051.2   79.74    5155   79.67  5184.7   82.06
  5199.9      82    5207   82.78  5212.6    82.2  5222.3   82.57  5234.9   84.24
  5244.8   83.96  5301.6   88.11  5384.3   90.16  5423.9   90.38  5439.3   91.18
#Mann= 7 ,-1 , 0
  4505.7     .05       0  4676.5      .1       0  4698.7     .05       0
  4831.3     .07       0  4837.3     .05       0    4918      .1       0
  5384.3     .08       0
Bank Sta=4831.3,4837.3
XS Rating Curve= 0 ,0
Exp/Cntr=0.3,0.1

Type RM Length L Ch R = 1 ,19442   ,157,157,157
BEGIN DESCRIPTION:
UNT040 IN BACR 22.0
END DESCRIPTION:
XS GIS Cut Line= 3
      2354612.71     13138269.59      2354793.17     13138134.25
      2355111.94     13137496.22
#Sta/Elev= 30
  4522.4   88.92  4556.9   88.75  4685.1   87.79  4691.4   86.82  4741.4   84.98
    4786   82.53  4832.7   79.98  4905.4   74.46  4922.1   74.14  4966.9   71.77
  4989.2   71.52  4991.8   69.88  4994.6   69.38  4997.8   69.88  5024.5   72.31
  5046.9   75.09  5056.3   74.61  5069.2   76.06  5123.4   77.55  5168.2   80.19
    5181   81.53  5212.9   83.13  5218.5   84.02  5315.2   88.44  5337.5   90.47
  5359.9   89.55  5379.2   89.96  5397.4    90.8    5427   90.33  5461.2   91.24
#Mann= 7 ,-1 , 0
  4522.4     .05       0  4556.9      .1       0  4741.4     .05       0
    4786      .1       0  4991.8     .07       0  4997.8      .1       0
  5379.2     .05       0
Bank Sta=4991.8,4997.8
XS Rating Curve= 0 ,0
Exp/Cntr=0.3,0.1

Type RM Length L Ch R = 1 ,19285   ,510,510,510
BEGIN DESCRIPTION:
UNT040 IN BACR 21.0
END DESCRIPTION:
XS GIS Cut Line= 2
      2354687.71     13138396.86      2355353.57     13137632.92
#Sta/Elev= 30
    4501   87.58  4690.6   88.84  4697.5   88.89    4735   88.42  4769.2   86.34
    4792   85.46  4806.1   83.42  4827.1   82.04  4862.2   80.55  4876.5    79.3
  4890.7   77.23  4968.6    71.9  4990.4   71.23  4994.1   70.11  4996.8   69.61
  5000.1   70.11  5004.7   71.08  5046.4   71.84  5124.5   76.17  5146.1   75.89
  5174.6   76.85  5188.8   78.75  5195.5   78.32  5372.1   87.33  5415.7   88.81
  5465.1   89.37  5479.3   90.27  5493.6   90.26  5507.8   89.08  5514.4   89.33
#Mann= 7 ,-1 , 0
    4501     .05       0  4690.6      .1       0  4697.5     .05       0
  4769.2      .1       0  4994.1     .07       0  5000.1      .1       0
  5372.1     .05       0
Bank Sta=4994.1,5000.1
XS Rating Curve= 0 ,0
Exp/Cntr=0.3,0.1

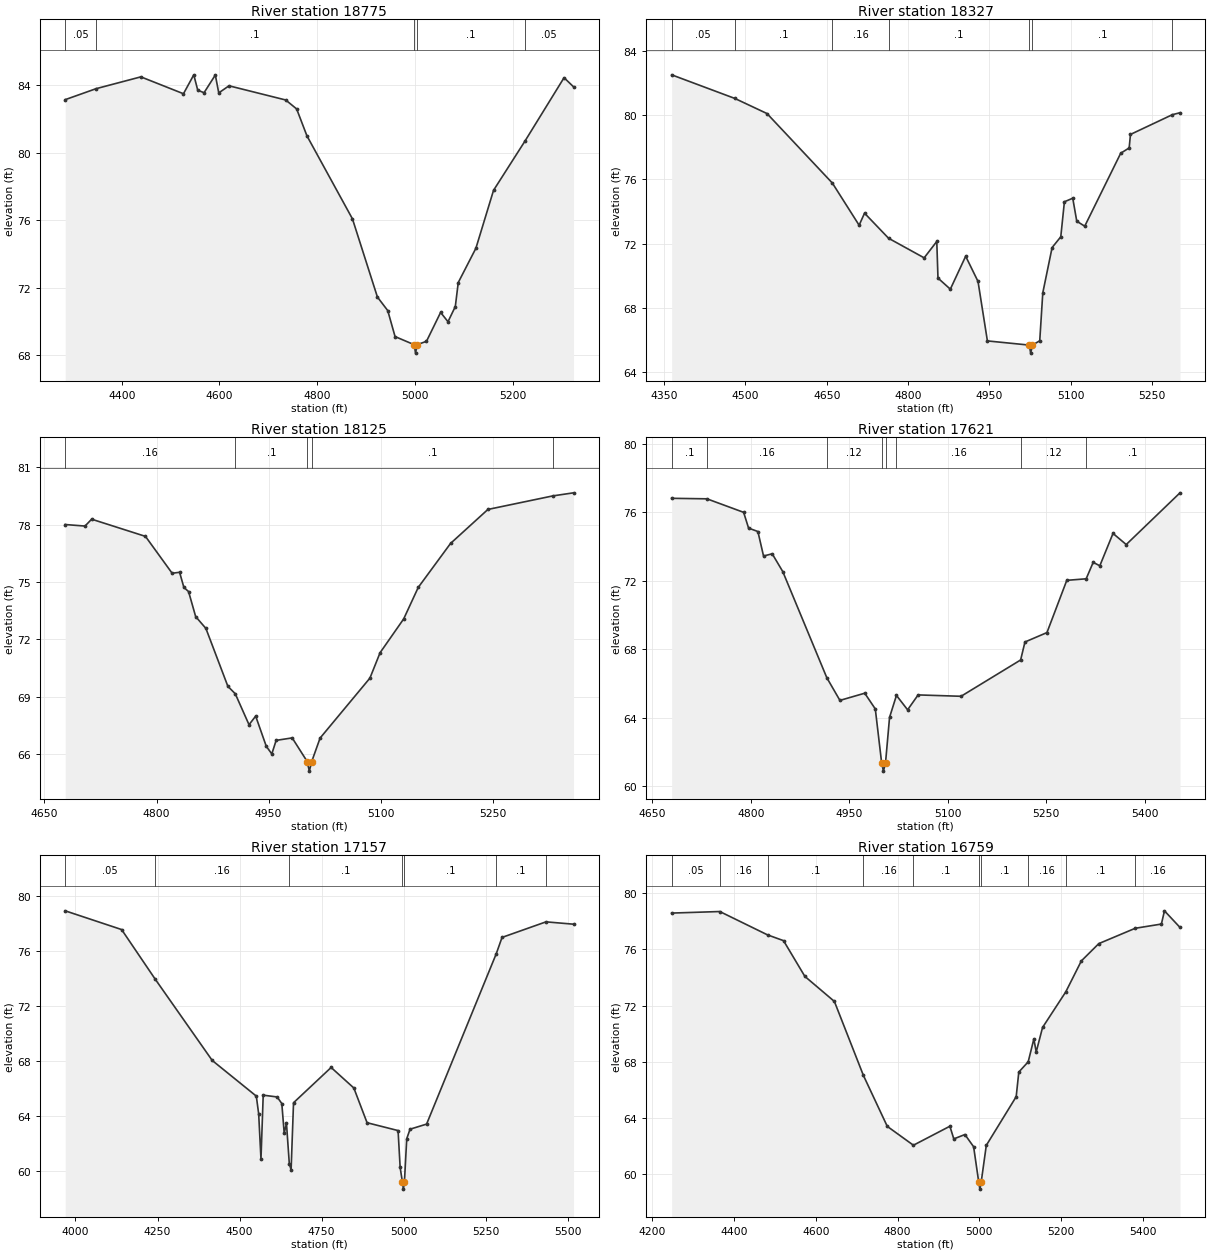
Type RM Length L Ch R = 1 ,18775   ,448,448,448
BEGIN DESCRIPTION:
UNT040 IN BACR 20.0
END DESCRIPTION:
XS GIS Cut Line= 2
      2354791.82      13138736.2      2355658.39      13138160.8
#Sta/Elev= 30
  4284.4   83.14  4347.6   83.79  4439.2   84.49  4526.4   83.49  4547.5   84.61
  4555.6    83.7  4568.5   83.55  4591.6    84.6  4598.6   83.54  4619.6   83.96
  4735.6   83.12    4758   82.59    4779      81  4872.2   76.08  4923.3   71.45
  4944.4   70.65  4959.4   69.11  4998.5   68.63  5001.3   68.13  5004.5   68.63
  5023.7   68.83  5052.6   70.54  5067.7   69.99  5082.7   70.89  5088.7   72.31
  5124.8   74.34  5160.9   77.77  5225.3   80.69  5305.2   84.44  5324.6    83.9
#Mann= 5 ,-1 , 0
  4284.4     .05       0  4347.6      .1       0  4998.5     .07       0
  5004.5      .1       0  5225.3     .05       0
Bank Sta=4998.5,5004.5
XS Rating Curve= 0 ,0
Exp/Cntr=0.3,0.1

Type RM Length L Ch R = 1 ,18327   ,202,202,202
BEGIN DESCRIPTION:
Mapping XS 1436b240
END DESCRIPTION:
XS GIS Cut Line= 4
      2354871.84     13138827.65      2355358.76     13138833.81
      2355685.41     13138679.73      2355731.65     13138602.67
#Sta/Elev= 30
  4363.8   82.51  4480.4   81.04  4539.7    80.1  4660.4   75.77  4709.7   73.15
  4719.7    73.9    4764   72.34  4829.7   71.12    4853   72.14  4855.2   69.86
    4878   69.17  4906.3   71.22  4929.1   69.65  4946.4   65.95  5023.5   65.69
  5026.3   65.19  5029.5   65.69    5043   65.96  5048.6   68.94  5065.8   71.76
  5081.8   72.43  5088.5   74.61  5103.9   74.83  5111.3    73.4    5126   73.09
  5192.4   77.63    5208   77.96  5210.4    78.8  5287.7   80.03  5301.8   80.15
#Mann= 7 ,-1 , 0
  4363.8     .05       0  4480.4      .1       0  4660.4     .16       0
    4764      .1       0  5023.5     .07       0  5029.5      .1       0
  5287.7     .05       0
Bank Sta=5023.5,5029.5
XS Rating Curve= 0 ,0
Exp/Cntr=0.3,0.1

Type RM Length L Ch R = 1 ,18125   ,504,504,504
BEGIN DESCRIPTION:
UNT040 IN BACR 19.0
END DESCRIPTION:
XS GIS Cut Line= 4
       2355284.8     13139111.16      2355694.66     13138873.87
      2355787.11       13138803.      2355774.78     13138713.63
#Sta/Elev= 30
  4677.8   78.01  4704.3   77.93  4713.2   78.29  4785.2   77.39  4820.9   75.46
  4830.9   75.51  4836.6   74.72  4842.9    74.5  4852.4   73.19  4866.1   72.57
  4895.5   69.54  4905.4   69.15  4923.8   67.53  4932.7   67.98  4946.9    66.4
  4954.3      66  4960.1   66.71  4981.6   66.84  5001.7    65.6  5004.5    65.1
  5007.7    65.6  5018.9   66.83  5085.6   69.97  5099.2    71.3  5130.8   73.07
  5150.3   74.72  5193.5   77.02  5243.5    78.8  5330.5   79.51  5358.1   79.67
#Mann= 5 ,-1 , 0
  4677.8     .16       0  4905.4      .1       0  5001.7     .07       0
  5007.7      .1       0  5330.5     .05       0
Bank Sta=5001.7,5007.7
XS Rating Curve= 0 ,0
Exp/Cntr=0.3,0.1

Type RM Length L Ch R = 1 ,17621   ,464,464,464
BEGIN DESCRIPTION:
Mapping XS 75137a1b
END DESCRIPTION:
XS GIS Cut Line= 3
      2355565.27     13139484.02      2355944.27     13139274.49
      2355907.29     13138935.47
#Sta/Elev= 30
  4679.5    76.8  4733.2   76.77  4789.1   75.98  4796.6   75.06  4810.8   74.86
  4819.4   73.43  4832.6   73.56  4848.7   72.52  4915.8   66.32  4935.7      65
  4973.5   65.42  4989.6    64.5  4999.2   61.37    5002   60.87  5005.2   61.37
  5011.3   64.01  5021.8   65.29  5038.8   64.45  5054.8   65.32  5120.2   65.24
  5210.9   67.36  5217.5   68.41    5251   68.96  5281.2   72.01  5310.7    72.1
  5321.4   73.06  5331.5   72.86  5351.6   74.75  5371.7    74.1  5453.6   77.12
#Mann= 8 ,-1 , 0
  4679.5      .1       0  4733.2     .16       0  4915.8     .12       0
  4999.2     .07       0  5005.2     .12       0  5021.8     .16       0
  5210.9     .12       0  5310.7      .1       0
Bank Sta=4999.2,5005.2
XS Rating Curve= 0 ,0
Exp/Cntr=0.3,0.1

Type RM Length L Ch R = 1 ,17157   ,398,398,398
BEGIN DESCRIPTION:
UNT040 IN BACR 18.0
END DESCRIPTION:
XS GIS Cut Line= 3
      2355217.02     13140359.22      2355765.54     13139767.55
      2356502.05     13139675.11
#Sta/Elev= 30
  3968.7   78.92  4140.6   77.56  4242.1   73.99  4416.7   68.06  4551.1   65.47
  4558.3   64.18  4565.3    60.9  4572.1   65.54  4614.6   65.41  4628.8   64.93
  4636.1   62.78    4643    63.5  4651.6   60.58  4657.1   60.11  4664.5   64.99
  4779.1   67.55  4848.3   66.06  4888.6   63.54  4983.1   62.97  4989.4    60.3
  4996.4   59.22  4999.2   58.72  5002.4   59.22  5009.5   62.38  5019.6   63.07
    5070   63.44  5282.4   75.81  5299.9   76.99  5433.9   78.12  5517.8   77.95
#Mann= 7 ,-1 , 0
  3968.7     .05       0  4242.1     .16       0  4651.6      .1       0
  4996.4     .07       0  5002.4      .1       0  5282.4      .1       0
  5433.9     .05       0
Bank Sta=4996.4,5002.4
XS Rating Curve= 0 ,0
Exp/Cntr=0.3,0.1

Type RM Length L Ch R = 1 ,16759   ,559,559,559
BEGIN DESCRIPTION:
UNT040 IN BACR 17.0
END DESCRIPTION:
XS GIS Cut Line= 2
      2355437.65     13140493.15      2356500.16     13139847.31
#Sta/Elev= 30
  4247.5   78.58  4365.2   78.69    4482   77.03  4521.1   76.62  4573.3   74.08
  4645.5    72.3  4716.5   67.04  4774.9   63.42  4838.8   62.08    4928   63.43
  4937.6   62.53  4964.8   62.84  4986.1   61.97  4998.6   59.46  5001.4   58.96
  5004.6   59.46  5017.1   62.07  5090.2   65.53  5096.6   67.28  5119.6   68.01
  5133.4   69.63  5139.2   68.71  5154.7   70.45  5211.5   72.98  5249.6   75.18
  5292.3   76.41  5381.4    77.5  5445.4    77.8  5452.9   78.74  5490.9   77.56
#Mann= 10 ,-1 , 0
  4247.5     .05       0  4365.2     .16       0    4482      .1       0
  4716.5     .16       0  4838.8      .1       0  4998.6     .07       0
  5004.6      .1       0  5119.6     .16       0  5211.5      .1       0
  5381.4     .16       0
Bank Sta=4998.6,5004.6
XS Rating Curve= 0 ,0
Exp/Cntr=0.3,0.1

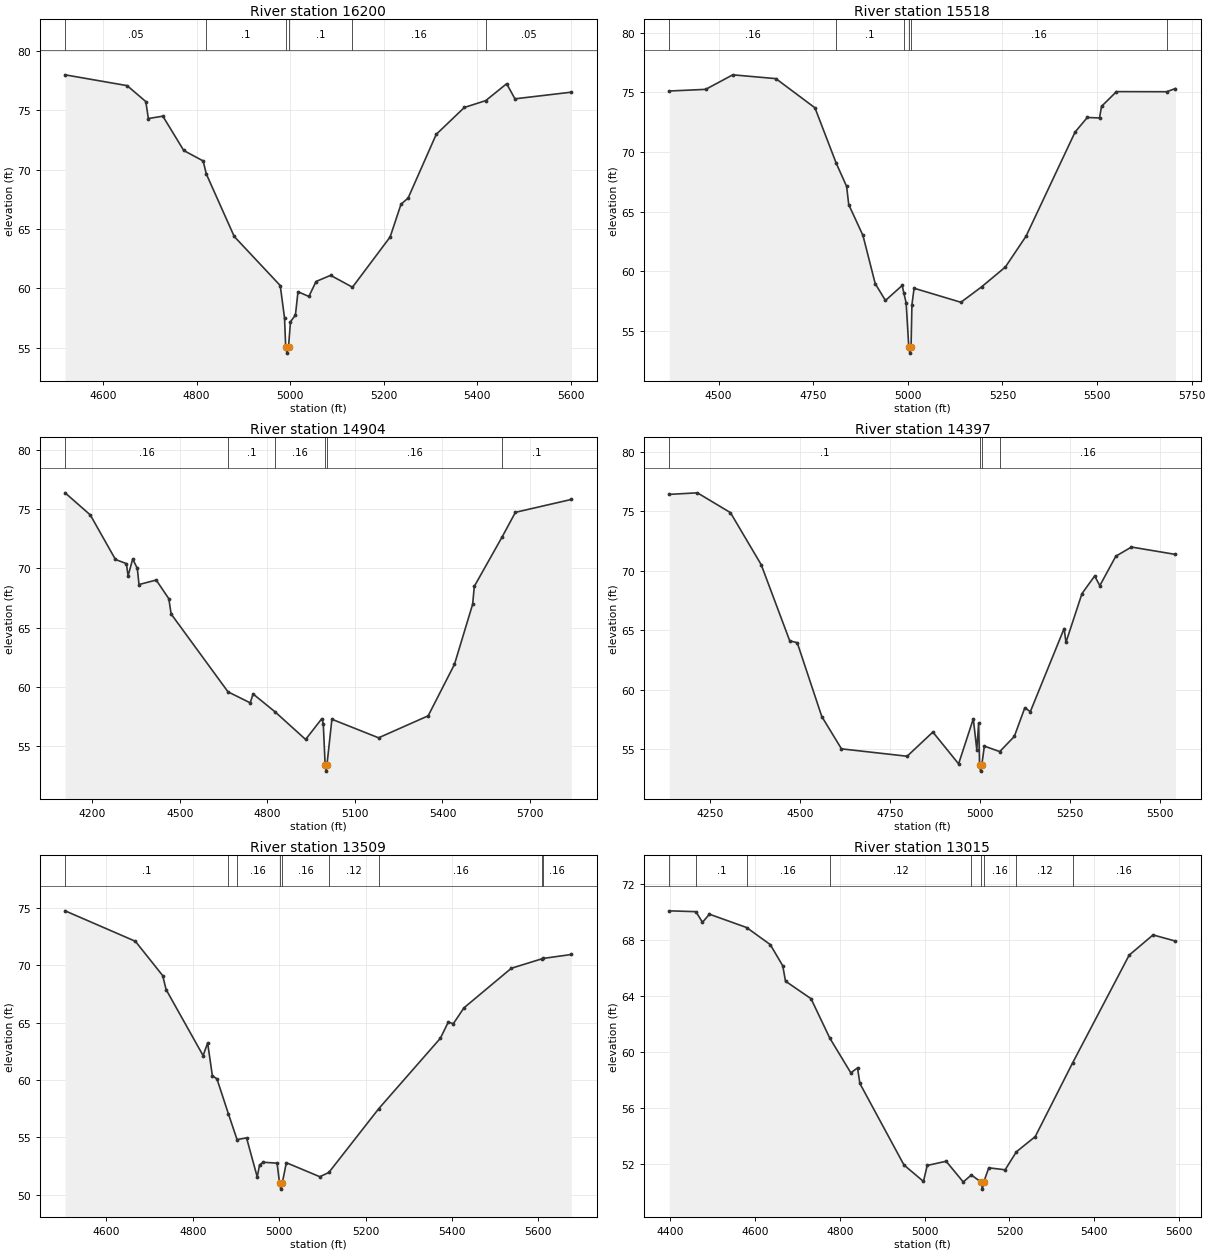
Type RM Length L Ch R = 1 ,16200   ,682,682,682
BEGIN DESCRIPTION:
UNT040 IN BACR 16.0
END DESCRIPTION:
XS GIS Cut Line= 3
      2355695.99     13140781.35      2356014.78     13140642.75
      2356686.97     13140344.76
#Sta/Elev= 30
  4518.8   77.98  4651.5   77.07  4691.4   75.73  4696.9    74.3  4727.9    74.5
  4772.6   71.61  4814.1   70.73  4820.9   69.63  4880.6   64.37    4979   60.24
  4988.2   57.51  4990.7   55.05  4993.5   54.55  4996.7   55.05  5000.9   57.19
  5011.5   57.76    5017   59.72  5040.3   59.32  5055.6   60.58  5086.8    61.1
  5133.5    60.1  5214.1   64.33  5237.4   67.09  5252.5    67.6  5312.7   72.97
  5372.8   75.23  5418.6   75.81  5463.3   77.23  5481.1   75.96  5601.7   76.52
#Mann= 6 ,-1 , 0
  4518.8     .05       0  4820.9      .1       0  4990.7     .07       0
  4996.7      .1       0  5133.5     .16       0  5418.6     .05       0
Bank Sta=4990.7,4996.7
XS Rating Curve= 0 ,0
Exp/Cntr=0.3,0.1

Type RM Length L Ch R = 1 ,15518   ,614,614,614
BEGIN DESCRIPTION:
UNT040 IN BACR 15.0
END DESCRIPTION:
XS GIS Cut Line= 3
      2355834.63     13141079.31      2356215.73     13141176.32
      2357116.54     13140892.22
#Sta/Elev= 30
  4369.5   75.12  4465.8   75.26  4537.3   76.48  4651.3   76.16  4754.5   73.71
  4810.7   69.06  4838.2   67.11  4843.8   65.58  4881.4   62.99  4913.7   58.95
  4940.8   57.53    4985   58.79  4989.5   58.16  4995.5   57.33  5002.5   53.61
  5005.3   53.11  5008.5   53.61  5010.8   57.18  5016.5   58.56  5140.2   57.38
  5194.7   58.67  5257.7   60.34  5312.4   62.93  5441.9   71.67  5474.2    72.9
  5506.6   72.86  5511.8   73.83  5551.3   75.07  5683.9   75.06  5707.3   75.33
#Mann= 6 ,-1 , 0
  4369.5     .16       0  4810.7      .1       0  4989.5     .16       0
  5002.5     .07       0  5008.5     .16       0  5683.9     .05       0
Bank Sta=5002.5,5008.5
XS Rating Curve= 0 ,0
Exp/Cntr=0.3,0.1

Type RM Length L Ch R = 1 ,14904   ,507,507,507
BEGIN DESCRIPTION:
UNT040 IN BACR 14.0
END DESCRIPTION:
XS GIS Cut Line= 4
      2355772.21     13141446.56       2356160.3     13141668.32
      2357088.86     13141654.46      2357407.64     13141488.14
#Sta/Elev= 30
  4106.6    76.4  4192.9   74.53  4279.2   70.76  4316.7   70.41  4322.4   69.37
  4338.3    70.8  4354.1   70.01  4359.9   68.64  4418.9   69.02  4462.1   67.44
    4470   66.15    4665   59.56    4741   58.63    4751   59.38  4827.1   57.85
    4931   55.53  4986.5   57.29  4991.5   56.87    4998   53.35  5000.8   52.85
    5004   53.35  5021.1   57.24  5181.1   55.67  5351.1   57.53  5441.1   61.88
  5503.5   66.97  5509.3   68.49  5605.3    72.7  5650.1   74.75  5841.8   75.84
#Mann= 6 ,-1 , 0
  4106.6     .16       0    4665      .1       0  4827.1     .16       0
    4998     .07       0    5004     .16       0  5605.3      .1       0
Bank Sta=4998,5004
XS Rating Curve= 0 ,0
Exp/Cntr=0.3,0.1

Type RM Length L Ch R = 1 ,14397   ,888,888,888
BEGIN DESCRIPTION:
UNT040 IN BACR 13.0
END DESCRIPTION:
XS GIS Cut Line= 3
      2355734.54     13142461.89      2356027.53     13142244.86
      2357047.48     13142027.85
#Sta/Elev= 30
    4136   76.41  4214.2   76.54    4306   74.88  4391.6   70.51  4470.9   64.12
  4491.8   63.96  4560.1   57.76  4614.8   55.05  4797.3   54.43  4868.9   56.46
  4940.4   53.79  4981.3   57.57    4991   54.98  4996.1   57.22  4998.8   53.68
  5001.5   53.18  5004.8   53.68    5012   55.28  5054.8   54.82  5095.3   56.09
  5124.5    58.5  5139.8   58.17  5233.8   65.15  5238.9   63.99  5283.4   68.08
  5318.7   69.56    5333   68.75  5377.5   71.22    5421   71.99  5543.4   71.37
#Mann= 4 ,-1 , 0
    4136      .1       0  4998.8     .07       0  5004.8      .1       0
  5054.8     .16       0
Bank Sta=4998.8,5004.8
XS Rating Curve= 0 ,0
Exp/Cntr=0.3,0.1

Type RM Length L Ch R = 1 ,13509   ,494,494,494
BEGIN DESCRIPTION:
UNT040 IN BACR 12.0
END DESCRIPTION:
XS GIS Cut Line= 3
      2355966.29      13142929.5      2356188.02     13142901.78
      2357073.88     13142562.66
#Sta/Elev= 30
  4504.5   74.72  4667.2   72.07  4730.5   69.08  4738.3   67.87    4824   62.12
  4834.5   63.22  4845.4   60.38  4856.1   60.09  4882.5   57.06  4902.6   54.81
  4924.6   54.96  4949.3   51.56  4954.7   52.61  4963.2   52.84  4995.3   52.76
  5001.1      51  5003.8    50.5  5007.1      51  5016.7    52.8  5094.2   51.58
  5115.1   51.95  5230.8   57.51  5373.3   63.63  5391.5   65.03  5403.3    64.9
    5428   66.28  5537.5   69.72  5608.8   70.55  5611.7   70.58  5676.5   70.92
#Mann= 9 ,-1 , 0
  4504.5      .1       0  4882.5     .12       0  4902.6     .16       0
  5001.1     .07       0  5007.1     .16       0  5115.1     .12       0
  5230.8     .16       0  5608.8      .1       0  5611.7     .16       0
Bank Sta=5001.1,5007.1
XS Rating Curve= 0 ,0
Exp/Cntr=0.3,0.1

Type RM Length L Ch R = 1 ,13015   ,630,630,630
BEGIN DESCRIPTION:
UNT040 IN BACR 11.0
END DESCRIPTION:
XS GIS Cut Line= 4
      2356070.17      13143262.1      2356305.82     13143359.13
      2356977.99     13143102.74      2357136.57     13142951.05
#Sta/Elev= 30
  4397.8   70.08  4460.7   70.02  4476.1   69.26  4492.5   69.84  4580.1   68.89
    4636   67.67  4665.4   66.16  4671.9   65.06  4732.1   63.81  4776.3      61
  4825.9   58.52  4841.7   58.87  4847.3   57.76  4951.3   51.94  4997.2   50.77
  5006.1   51.91  5050.7   52.21    5091   50.73  5110.1   51.23  5133.3   50.72
  5136.1   50.22  5139.3   50.72  5151.2   51.74  5189.8    51.6  5216.2   52.88
  5260.8   53.97  5349.1   59.24  5482.3   66.92  5538.6   68.36  5591.5   67.92
#Mann= 9 ,-1 , 0
  4397.8     .16       0  4460.7      .1       0  4580.1     .16       0
  4776.3     .12       0  5110.1     .16       0  5133.3     .07       0
  5139.3     .16       0  5216.2     .12       0  5349.1     .16       0
Bank Sta=5133.3,5139.3
XS Rating Curve= 0 ,0
Exp/Cntr=0.3,0.1