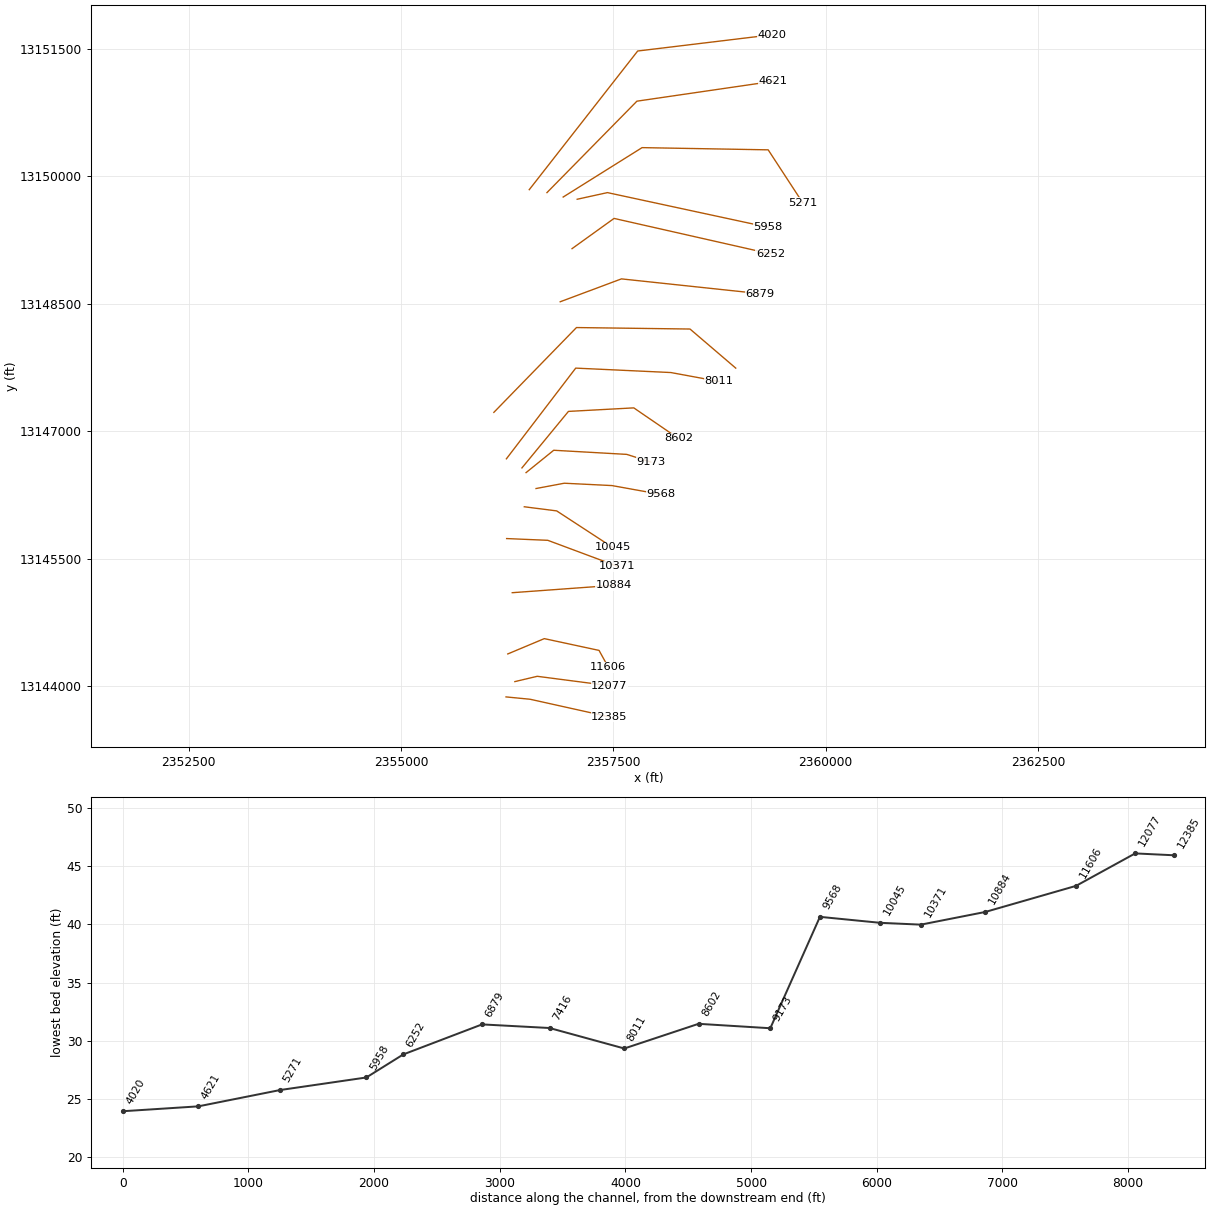
HEC-RAS study UNT040 IN BACR.prj: UNT040 IN BACR Base Level Engineering

--- UNT040 IN BACR.g01 (geometry) --- (continued)

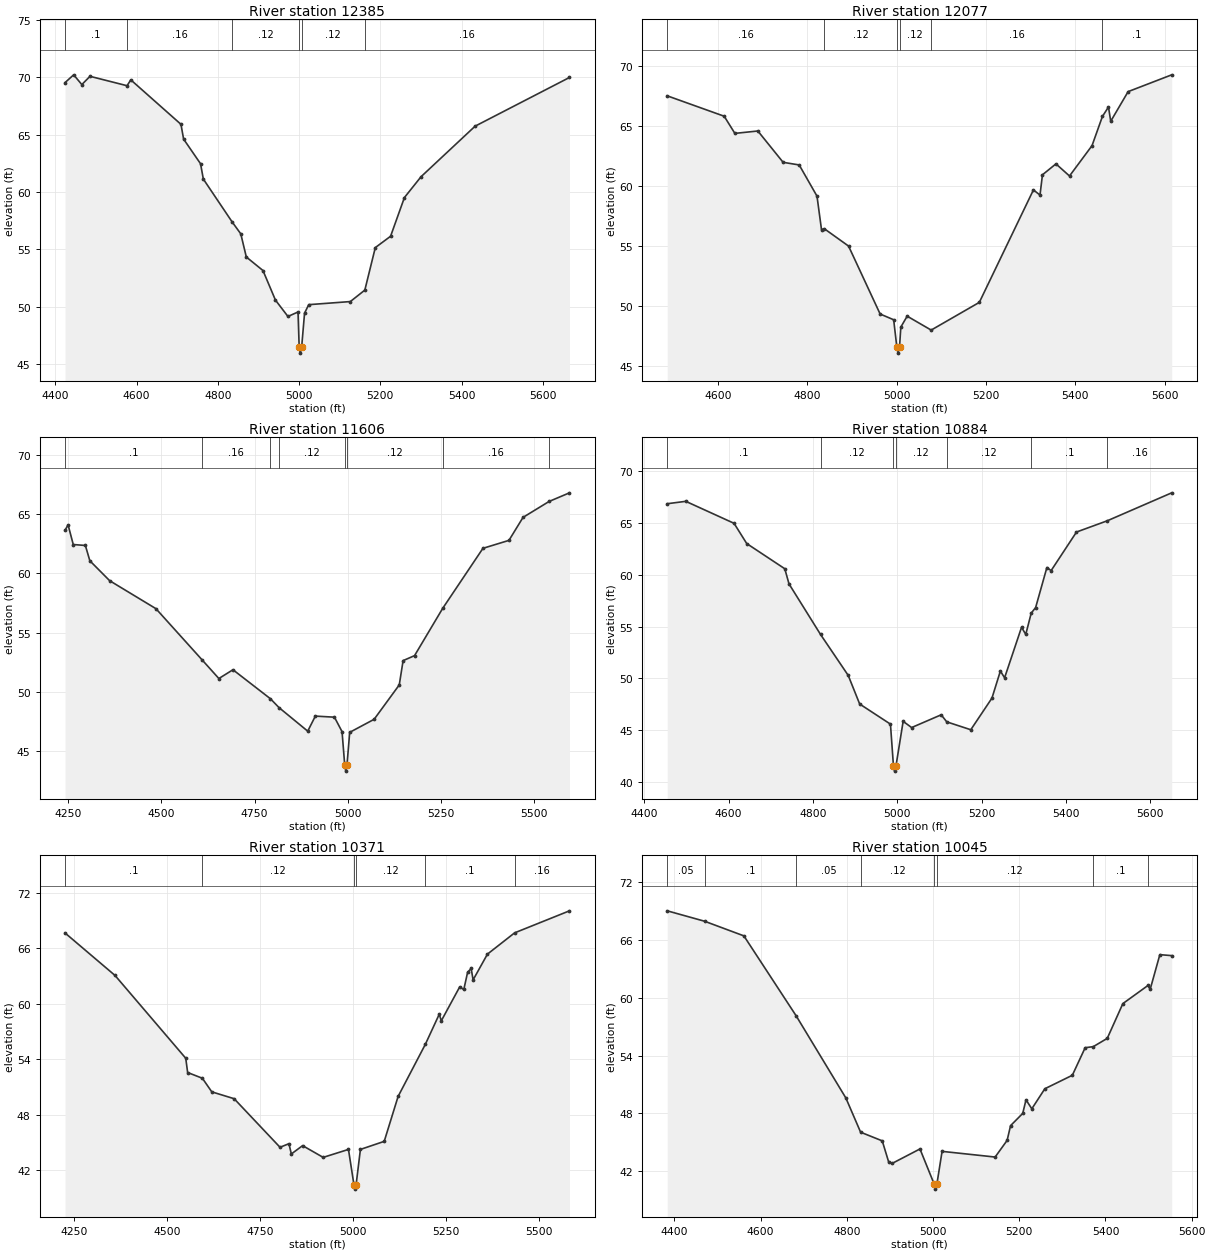
Type RM Length L Ch R = 1 ,12385   ,308,308,308
BEGIN DESCRIPTION:
UNT040 IN BACR 10.0
END DESCRIPTION:
XS GIS Cut Line= 3
      2356236.48     13143871.93      2356520.63      13143844.2
      2357454.46     13143636.69
#Sta/Elev= 30
  4423.7   69.55    4445   70.23  4465.1   69.38  4485.2    70.1  4576.4   69.28
  4585.7   69.79  4709.2   65.91  4715.7   64.62  4757.4   62.47  4764.3   61.13
  4835.4   57.38  4856.5   56.35  4870.1   54.33  4911.1   53.15  4941.8   50.57
  4972.6   49.14  4997.4   49.53  5000.3   46.44    5003   45.94  5006.3   46.44
  5013.5   49.43  5023.8   50.17  5126.2   50.44  5161.9   51.44  5187.7   55.15
  5225.3   56.14  5259.4   59.52  5300.4   61.34  5433.5   65.75  5665.8      70
#Mann= 6 ,-1 , 0
  4423.7      .1       0  4576.4     .16       0  4835.4     .12       0
  5000.3     .07       0  5006.3     .12       0  5161.9     .16       0
Bank Sta=5000.3,5006.3
XS Rating Curve= 0 ,0
Exp/Cntr=0.3,0.1

Type RM Length L Ch R = 1 ,12077   ,471,471,471
BEGIN DESCRIPTION:
UNT040 IN BACR 9.0
END DESCRIPTION:
XS GIS Cut Line= 3
       2356340.5      13144052.1      2356603.79     13144114.46
      2357454.45      13144003.8
#Sta/Elev= 30
  4487.1   67.54  4614.5   65.84  4638.4   64.41  4689.8   64.61  4746.3      62
  4782.3   61.78  4822.1   59.18  4832.2   56.38  4838.3   56.47  4892.7   55.02
  4963.3   49.36  4993.6   48.88  5000.7    46.6  5003.4    46.1  5006.7    46.6
  5009.6   48.27  5023.8   49.18  5077.5   48.02  5185.2   50.33  5306.2    59.7
  5320.9   59.27  5326.4   60.96  5356.6   61.87  5386.9   60.86  5437.3   63.39
  5460.5   65.82  5474.1   66.61  5479.1   65.42    5518   67.89  5615.5   69.29
#Mann= 6 ,-1 , 0
  4487.1     .16       0  4838.3     .12       0  5000.7     .07       0
  5006.7     .12       0  5077.5     .16       0  5460.5      .1       0
Bank Sta=5000.7,5006.7
XS Rating Curve= 0 ,0
Exp/Cntr=0.3,0.1

Type RM Length L Ch R = 1 ,11606   ,722,722,722
BEGIN DESCRIPTION:
UNT040 IN BACR 8.0
END DESCRIPTION:
XS GIS Cut Line= 4
      2356257.35     13144377.79      2356686.94     13144557.95
      2357331.39     13144419.36      2357441.33      13144220.1
#Sta/Elev= 30
  4241.9   63.62  4250.1   64.08    4264   62.42  4296.5   62.34  4308.5   61.05
  4361.6   59.37  4485.7   57.01  4609.8   52.68  4654.4   51.12  4692.2   51.86
  4792.8   49.41  4815.6   48.67  4892.7   46.68  4913.1   47.95  4964.3   47.86
  4984.7   46.64  4991.9   43.81  4994.7   43.31  4997.9   43.81  5005.2   46.58
  5070.7   47.68  5138.1   50.58  5148.4   52.63  5179.1   53.05  5254.6   57.04
  5362.5    62.1  5432.2   62.77    5470   64.71  5539.7   66.05  5594.5   66.78
#Mann= 8 ,-1 , 0
  4241.9      .1       0  4609.8     .16       0  4792.8      .1       0
  4815.6     .12       0  4991.9     .07       0  4997.9     .12       0
  5254.6     .16       0  5539.7      .1       0
Bank Sta=4991.9,4997.9
XS Rating Curve= 0 ,0
Exp/Cntr=0.3,0.1

Type RM Length L Ch R = 1 ,10884   ,513,513,513
BEGIN DESCRIPTION:
UNT040 IN BACR 7.0
END DESCRIPTION:
XS GIS Cut Line= 2
      2356309.68      13145098.6      2357502.93     13145185.38
#Sta/Elev= 30
  4454.5   66.85  4498.5   67.08    4613   64.96    4643   63.01  4733.3   60.58
  4743.3   59.12    4818   54.25  4883.7    50.3  4910.9   47.54  4983.9    45.6
    4991   41.57  4993.7   41.07    4997   41.57    5014   45.87  5034.1   45.27
  5104.2    46.5  5117.4   45.82  5174.4   45.06  5224.6   48.11  5244.6   50.72
  5254.6   50.07  5294.8   54.94  5304.8   54.25  5317.7    56.3  5328.2   56.84
  5354.9    60.7  5364.9    60.4  5425.1   64.12  5498.4   65.21  5650.9    67.9
#Mann= 7 ,-1 , 0
  4454.5      .1       0    4818     .12       0    4991     .07       0
    4997     .12       0  5117.4     .12       0  5317.7      .1       0
  5498.4     .16       0
Bank Sta=4991,4997
XS Rating Curve= 0 ,0
Exp/Cntr=0.3,0.1

Type RM Length L Ch R = 1 ,10371   ,326,326,326
BEGIN DESCRIPTION:
UNT040 IN BACR 6.0
END DESCRIPTION:
XS GIS Cut Line= 3
      2356243.46     13145735.97      2356728.52     13145715.19
      2357544.44     13145410.95
#Sta/Elev= 30
  4226.5   67.66  4360.9   63.07  4551.1   54.12  4556.2   52.58  4595.8   51.96
  4621.1   50.49  4681.2   49.75  4804.6    44.5  4828.5   44.89    4835   43.78
  4865.3   44.68  4920.6   43.41  4988.6   44.27  5003.2   40.48    5006   39.98
  5009.2   40.48  5020.7   44.27  5084.7   45.14  5122.1      50  5195.2   55.62
  5232.8   58.89  5238.1   58.16  5287.5   61.82  5298.7   61.55  5308.8   63.39
  5318.4   63.83  5323.7   62.59  5362.2   65.37  5435.3   67.67  5582.8   70.05
#Mann= 6 ,-1 , 0
  4226.5      .1       0  4595.8     .12       0  5003.2     .07       0
  5009.2     .12       0  5195.2      .1       0  5435.3     .16       0
Bank Sta=5003.2,5009.2
XS Rating Curve= 0 ,0
Exp/Cntr=0.3,0.1

Type RM Length L Ch R = 1 ,10045   ,477,477,477
BEGIN DESCRIPTION:
UNT040 IN BACR 5.0
END DESCRIPTION:
XS GIS Cut Line= 3
      2356451.33     13146110.17      2356832.47     13146061.66
      2357490.77     13145632.04
#Sta/Elev= 30
  4383.4   69.03    4470   67.95  4561.2   66.43  4682.2   58.15  4797.8    49.6
    4832   46.05  4882.2   45.15  4897.3   42.93  4905.2   42.81  4969.7   44.31
  5002.9   40.64  5005.7   40.14  5008.9   40.64    5021   44.06  5144.1   43.47
  5171.9    45.2  5179.9   46.73  5208.1      48  5215.7   49.41  5229.2   48.48
  5259.4   50.56  5323.2   51.96  5352.9   54.82  5371.7   54.93  5404.2   55.79
  5440.4    59.4  5498.6   61.28  5503.7   60.87  5526.2   64.48  5553.7   64.38
#Mann= 8 ,-1 , 0
  4383.4     .05       0    4470      .1       0  4682.2     .05       0
    4832     .12       0  5002.9     .07       0  5008.9     .12       0
  5371.7      .1       0  5498.6     .16       0
Bank Sta=5002.9,5008.9
XS Rating Curve= 0 ,0
Exp/Cntr=0.3,0.1

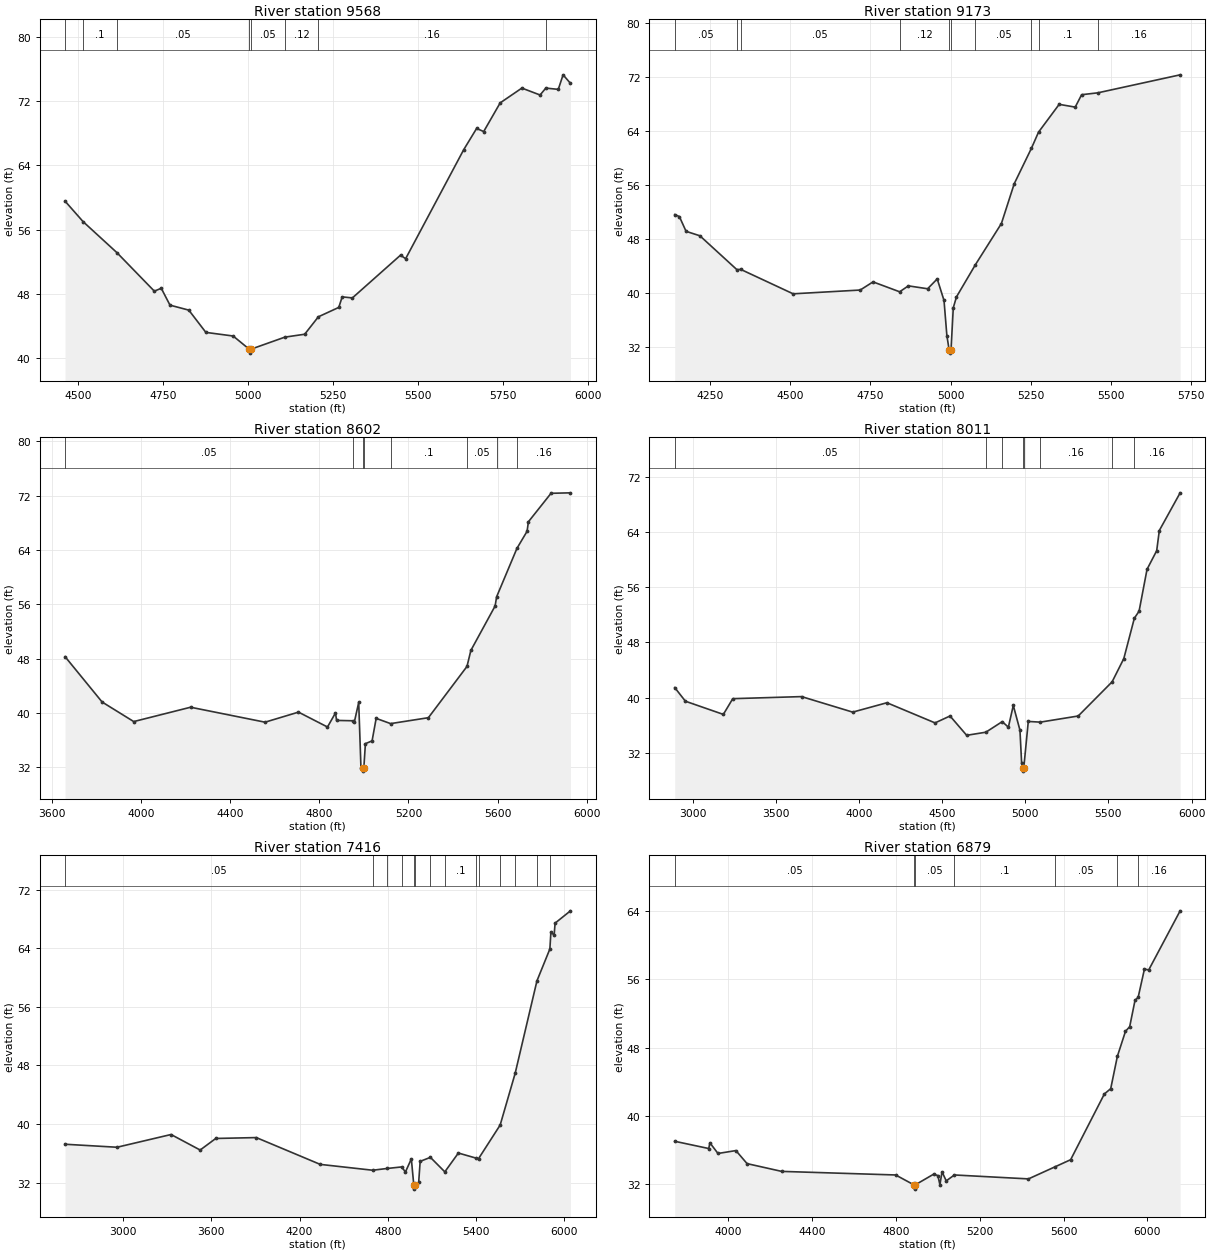
Type RM Length L Ch R = 1 ,9568    ,395,395,395
BEGIN DESCRIPTION:
UNT040 IN BACR 4.0
END DESCRIPTION:
XS GIS Cut Line= 4
      2356589.93     13146324.99      2356922.55     13146387.35
      2357483.84     13146359.64      2358059.03     13146255.69
#Sta/Elev= 30
  4462.5   59.56  4515.5   57.01  4614.7   53.16  4724.8   48.36  4745.1   48.72
  4770.8   46.62  4826.1      46  4876.2   43.23  4956.3   42.78  5003.3   41.15
  5006.1   40.65  5009.3   41.15  5108.3   42.64  5166.5      43  5206.7   45.17
  5266.7   46.34  5276.7   47.65  5306.7   47.52  5448.1   52.84  5463.1    52.4
  5633.8   65.97  5671.7   68.61  5692.4   68.22  5740.9   71.79  5804.6   73.63
  5858.1   72.77    5875   73.63  5911.6   73.47  5925.7   75.28  5947.4   74.22
#Mann= 8 ,-1 , 0
  4462.5     .05       0  4515.5      .1       0  4614.7     .05       0
  5003.3     .04       0  5009.3     .05       0  5108.3     .12       0
  5206.7     .16       0    5875     .05       0
Bank Sta=5003.3,5009.3
XS Rating Curve= 0 ,0
Exp/Cntr=0.3,0.1

Type RM Length L Ch R = 1 ,9173    ,571,571,571
BEGIN DESCRIPTION:
UNT040 IN BACR 3.0
END DESCRIPTION:
XS GIS Cut Line= 4
      2356472.16     13146512.11      2356797.82     13146775.41
      2357657.08      13146726.9      2357941.22     13146636.81
#Sta/Elev= 30
  4139.2   51.64  4153.7   51.34  4174.6   49.15  4217.7   48.49  4333.1   43.47
  4345.4    43.5  4508.7   39.88  4718.1   40.44  4758.2   41.65  4841.2   40.18
  4868.4   41.06  4928.5   40.63  4958.5   42.09  4979.7   38.89  4988.6   33.69
  4995.6   31.58  4998.3   31.08  5001.6   31.58  5008.6   37.81  5018.6   39.43
  5077.8   44.21  5158.8   50.31  5198.9   56.22  5252.7   61.49  5274.6   63.86
  5339.1   67.99  5389.2   67.58  5409.2   69.42  5459.8    69.7  5716.7   72.37
#Mann= 10 ,-1 , 0
  4139.2     .05       0  4333.1      .1       0  4345.4     .05       0
  4841.2     .12       0  4995.6     .07       0  5001.6     .12       0
  5077.8     .05       0  5252.7     .16       0  5274.6      .1       0
  5459.8     .16       0
Bank Sta=4995.6,5001.6
XS Rating Curve= 0 ,0
Exp/Cntr=0.3,0.1

Type RM Length L Ch R = 1 ,8602    ,591,591,591
BEGIN DESCRIPTION:
Mapping XS 70a680da
END DESCRIPTION:
XS GIS Cut Line= 4
      2356423.63     13146567.54      2356971.06     13147232.76
      2357740.24     13147274.34      2358266.86     13146914.02
#Sta/Elev= 30
  3657.6    48.3  3823.9   41.63    3966   38.75  4221.4   40.86  4555.8   38.66
    4706   40.14  4836.2   37.95  4872.1   40.02  4877.1   38.92  4948.8   38.87
  4956.4   38.62  4976.4   41.56  4986.5   31.98  4993.5   31.96  4996.2   31.46
  4999.5   31.96  5006.5    35.5  5036.5   35.91  5054.8   39.22  5119.7   38.45
  5289.4   39.32  5462.7   46.86  5480.2   49.22    5589   55.75  5595.9   57.11
  5687.1   64.23  5732.6   66.74  5738.6   68.14  5840.2   72.33  5927.5    72.4
#Mann= 8 ,-1 , 0
  3657.6     .05       0  4948.8     .12       0  4993.5     .07       0
  4999.5     .12       0  5119.7      .1       0  5462.7     .05       0
  5595.9      .1       0  5687.1     .16       0
Bank Sta=4993.5,4999.5
XS Rating Curve= 0 ,0
Exp/Cntr=0.3,0.1

Type RM Length L Ch R = 1 ,8011    ,595,595,595
BEGIN DESCRIPTION:
Mapping XS f38613d8
END DESCRIPTION:
XS GIS Cut Line= 4
      2356240.81     13146674.67       2357056.8      13147742.4
      2358176.59     13147690.32      2358740.82     13147586.15
#Sta/Elev= 30
  2892.9   41.45  2957.1   39.47  3185.1   37.56  3241.8   39.84  3655.4   40.14
  3962.8   37.89  4168.6   39.25  4457.9   36.33    4548   37.33  4648.1   34.53
  4763.4   34.98  4861.7   36.51  4898.8   35.71  4928.4   38.86  4968.4   35.27
  4978.5    30.5  4985.5   29.84  4988.2   29.34  4991.5   29.84  5018.5   36.54
  5090.8   36.44  5318.8   37.33  5522.5   42.28  5592.8   45.65  5656.2    51.5
  5684.6   52.52  5732.5   58.59  5790.5   61.28  5806.3   64.21  5931.5   69.67
#Mann= 8 ,-1 , 0
  2892.9     .05       0  4763.4      .1       0  4861.7     .12       0
  4985.5     .07       0  4991.5     .12       0  5090.8     .16       0
  5522.5     .05       0  5656.2     .16       0
Bank Sta=4985.5,4991.5
XS Rating Curve= 0 ,0
Exp/Cntr=0.3,0.1

Type RM Length L Ch R = 1 ,7416    ,537,537,537
BEGIN DESCRIPTION:
Mapping XS 531e906d
END DESCRIPTION:
XS GIS Cut Line= 4
      2356093.25     13147221.56      2357065.48     13148219.83
      2358402.29     13148202.47      2358940.46     13147742.43
#Sta/Elev= 30
  2604.4   37.23  2957.9   36.82  3325.5   38.56  3523.5   36.44  3629.7   38.02
  3905.5   38.14  4340.1   34.48  4697.2   33.68  4795.4   33.92  4893.5   34.13
  4920.2   33.45  4960.2   35.23  4977.2    31.6    4980    31.1  4983.2    31.6
  5010.2   32.04  5020.2   34.89  5089.8   35.44    5188   33.46  5280.2   36.03
  5401.5   35.33  5417.3   35.26  5564.4   39.85  5666.3    46.9  5814.8   59.55
  5902.7    63.9  5909.7    66.2  5931.7    65.8  5938.2   67.43  6042.8   69.11
#Mann= 14 ,-1 , 0
  2604.4     .05       0  4697.2      .1       0  4795.4     .05       0
  4893.5     .12       0  4977.2     .07       0  4983.2     .12       0
  5089.8     .05       0    5188      .1       0  5401.5     .16       0
  5417.3      .1       0  5564.4     .16       0  5666.3     .05       0
  5814.8     .16       0  5902.7      .1       0
Bank Sta=4977.2,4983.2
XS Rating Curve= 0 ,0
Exp/Cntr=0.3,0.1

Type RM Length L Ch R = 1 ,6879    ,627,627,627
BEGIN DESCRIPTION:
Mapping XS ebcc732f
END DESCRIPTION:
XS GIS Cut Line= 3
      2356874.49     13148523.65        2357595.     13148792.75
      2359226.97     13148619.14
#Sta/Elev= 30
  3745.5   37.02  3907.8   36.17  3913.1   36.84  3951.8   35.59  4037.2   35.93
  4090.5    34.4  4255.4   33.49  4798.9   33.07  4886.4   31.91  4889.2   31.41
  4892.4   31.91    4980   33.16  5000.4      33  5010.1   31.92  5020.2   33.44
  5040.3   32.38  5079.3   33.07  5432.5   32.61  5559.5   34.03  5633.6   34.86
  5794.5   42.57  5824.7   43.19  5856.4   46.98  5895.1   49.91  5915.2   50.46
  5940.7   53.56  5955.4   53.88  5985.6   57.22  6005.7    57.1  6155.8   64.04
#Mann= 7 ,-1 , 0
  3745.5     .05       0  4886.4     .03       0  4892.4     .05       0
  5079.3      .1       0  5559.5     .05       0  5856.4      .1       0
  5955.4     .16       0
Bank Sta=4886.4,4892.4
XS Rating Curve= 0 ,0
Exp/Cntr=0.3,0.1

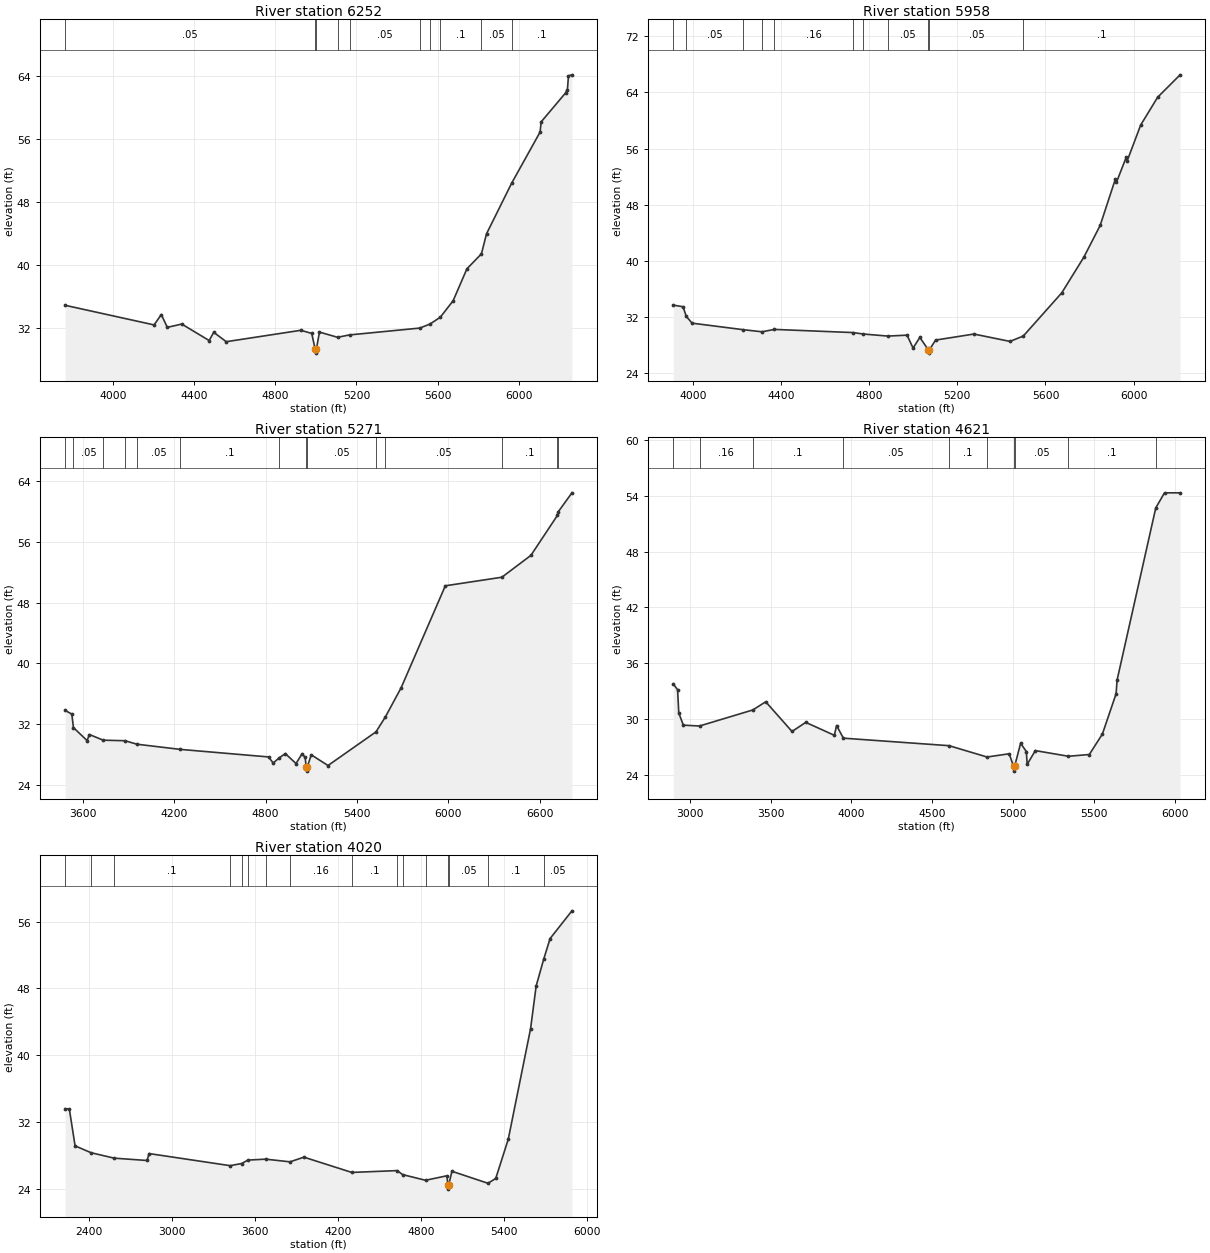
Type RM Length L Ch R = 1 ,6252    ,294,294,294
BEGIN DESCRIPTION:
Mapping XS fb6bbff8
END DESCRIPTION:
XS GIS Cut Line= 3
      2357013.37     13149148.63      2357508.19     13149504.55
      2359348.47     13149087.89
#Sta/Elev= 30
  3765.2    34.9  4203.4   32.41    4239   33.73  4268.4    32.1  4339.6   32.52
  4474.6   30.43  4497.3   31.47  4558.8   30.28  4926.6   31.73    4980   31.33
  4996.7   29.33  4999.4   28.83  5002.7   29.33    5018    31.5    5107   30.84
  5166.1   31.14  5512.1   32.01  5562.4   32.52  5613.3   33.39  5676.4   35.48
  5744.3   39.53  5815.8   41.43  5840.8   43.97  5964.7    50.4  6104.8   56.89
    6110   58.18  6230.1   61.85  6239.4   62.28  6244.5   64.02  6261.6   64.15
#Mann= 10 ,-1 , 0
  3765.2     .05       0  4996.7    .035       0  5002.7     .05       0
    5107     .08       0  5166.1     .05       0  5512.1     .08       0
  5562.4     .05       0  5613.3      .1       0  5815.8     .05       0
  5964.7      .1       0
Bank Sta=4996.7,5002.7
XS Rating Curve= 0 ,0
Exp/Cntr=0.3,0.1

Type RM Length L Ch R = 1 ,5958    ,687,687,687
BEGIN DESCRIPTION:
Mapping XS e0bf5249
END DESCRIPTION:
XS GIS Cut Line= 3
      2357074.17     13149730.25      2357430.07     13149808.37
      2359322.42     13149400.39
#Sta/Elev= 30
  3910.6   33.69  3955.2   33.46  3969.4   32.09  3996.1   31.12  4225.4    30.2
  4313.4   29.89  4369.7   30.23  4726.3   29.78  4773.7   29.57  4884.5   29.28
  4971.7   29.41  4998.9   27.57  5029.6   29.09  5067.5   27.35  5070.2   26.85
  5073.5   27.35  5101.2   28.71  5275.1   29.57  5438.8   28.52  5499.4   29.29
    5674   35.45    5774   40.52    5848   45.04  5916.8   51.62  5921.9   51.18
  5966.1   54.74  5971.2   54.29  6032.1   59.36  6108.9   63.31  6210.8   66.51
#Mann= 11 ,-1 , 0
  3910.6     .08       0  3969.4     .05       0  4225.4     .16       0
  4313.4     .05       0  4369.7     .16       0  4726.3     .05       0
  4773.7      .1       0  4884.5     .05       0  5067.5     .03       0
  5073.5     .05       0  5499.4      .1       0
Bank Sta=5067.5,5073.5
XS Rating Curve= 0 ,0
Exp/Cntr=0.3,0.1

Type RM Length L Ch R = 1 ,5271    ,650,650,650
BEGIN DESCRIPTION:
Mapping XS 6bb82ed7
END DESCRIPTION:
XS GIS Cut Line= 4
       2356909.2     13149756.27      2357838.05     13150337.89
      2359322.43     13150311.85      2359730.41     13149686.85
#Sta/Elev= 30
  3484.4   33.78  3528.3   33.29    3539   31.51  3628.5    29.8  3643.8    30.6
  3734.4   29.85  3877.3   29.78  3955.6   29.32  4238.6   28.64    4820   27.64
    4850   26.84  4890.4   27.53    4930   28.08  5000.1   26.77  5040.1   28.07
  5060.1   27.57  5067.1   26.27  5069.8   25.77  5073.1   26.27  5100.1   27.92
  5210.1   26.51  5525.1   30.95  5585.9   32.89  5690.2   36.77  5980.2   50.21
  6351.4   51.34  6541.9   54.22  6716.5   59.51  6722.6      60  6811.3   62.47
#Mann= 14 ,-1 , 0
  3484.4     .08       0    3539     .05       0  3734.4     .16       0
  3877.3      .1       0  3955.6     .05       0  4238.6      .1       0
  4890.4     .05       0  5067.1     .03       0  5073.1     .05       0
  5525.1      .1       0  5585.9     .05       0  6351.4      .1       0
  6716.5     .05       0  6722.6      .1       0
Bank Sta=5067.1,5073.1
XS Rating Curve= 0 ,0
Exp/Cntr=0.3,0.1

Type RM Length L Ch R = 1 ,4621    ,601,601,601
BEGIN DESCRIPTION:
Mapping XS 55696463
END DESCRIPTION:
XS GIS Cut Line= 3
      2356718.26     13149808.37      2357777.29     13150884.76
      2359382.95      13151119.1
#Sta/Elev= 30
    2899   33.75  2925.8   33.14  2932.9   30.64  2961.2   29.32  3061.2   29.23
  3391.1   30.96  3470.4   31.84    3633   28.64  3717.8   29.62  3894.6   28.23
  3908.7   29.28  3950.3   27.92  4603.9   27.11  4838.6   25.89  4975.4   26.24
  5002.7   24.87  5005.5   24.37  5008.7   24.87  5046.1   27.37  5081.4   26.48
  5086.6    25.1  5137.1   26.58    5342   25.97  5470.6   26.16  5551.4   28.36
  5636.3   32.71  5642.4   34.18  5881.5   52.72  5935.5   54.34  6031.7   54.34
#Mann= 10 ,-1 , 0
    2899     .05       0  3061.2     .16       0  3391.1      .1       0
  3950.3     .05       0  4603.9      .1       0  4838.6     .05       0
  5002.7     .03       0  5008.7     .05       0    5342      .1       0
  5881.5     .05       0
Bank Sta=5002.7,5008.7
XS Rating Curve= 0 ,0
Exp/Cntr=0.3,0.1

Type RM Length L Ch R = 1 ,4020    ,0,0,0
BEGIN DESCRIPTION:
UNT040 IN BACR 1.0
END DESCRIPTION:
XS GIS Cut Line= 3
      2356509.93      13149843.1      2357785.97     13151475.04
      2359364.28     13151665.83
#Sta/Elev= 30
  2230.8   33.58    2261   33.56  2302.8   29.13  2418.7   28.31  2585.1   27.66
  2822.8   27.38  2837.3   28.21    3423   26.76  3506.5   27.02  3551.5   27.43
  3679.9   27.54  3855.5   27.22  3955.9   27.78  4301.8   25.95  4629.8   26.17
  4669.1   25.69  4834.6   25.01  4989.1   25.55  4996.2   24.45  4998.9   23.95
  5002.2   24.45  5025.1   26.09  5285.7   24.65  5341.7   25.23  5432.3   29.93
  5593.5   43.18  5633.8   48.29  5688.1   51.49  5734.5   53.97  5892.2   57.29
#Mann= 16 ,-1 , 0
  2230.8     .05       0  2418.7     .16       0  2585.1      .1       0
    3423     .16       0  3506.5      .1       0  3551.5     .16       0
  3679.9      .1       0  3855.5     .16       0  4301.8      .1       0
  4629.8     .16       0  4669.1      .1       0  4834.6     .05       0
  4996.2     .03       0  5002.2     .05       0  5285.7      .1       0
  5688.1     .05       0
Bank Sta=4996.2,5002.2
XS Rating Curve= 0 ,0
Exp/Cntr=0.3,0.1

Chan Stop Cuts=-1
Use User Specified Reach Order=0
Composite Channel Slope=5