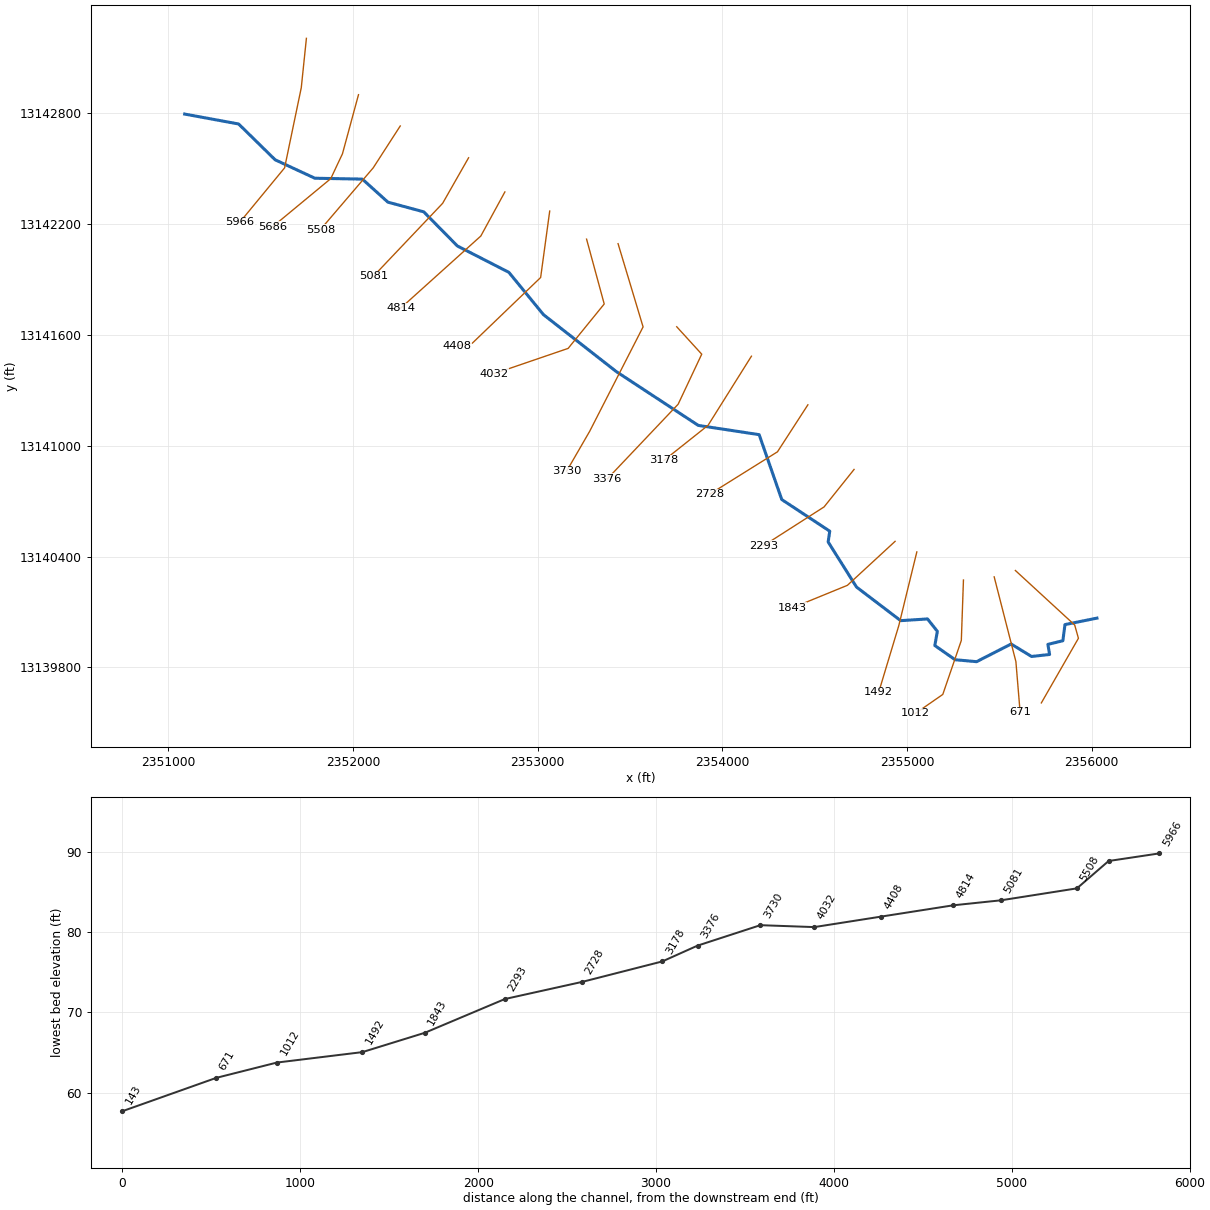
--- UNT041 IN BACR.prj (project) ---

Proj Title=UNT041 IN BACR Base Level Engineering
Current Plan=p01
Default Exp/Contr=0.3,0.1
English Units
Geom File=g01
Flow File=f01
Plan File=p01
Y Axis Title=Elevation
X Axis Title(PF)=Main Channel Distance
X Axis Title(XS)=Station
BEGIN DESCRIPTION:
UNT041 IN BACR
END DESCRIPTION:
DSS Export Rating Curves= 0
DSS Export Rating Curve Sorted= 0
DSS Export Volume Flow Curves= 0
DXF OffsetX= 0
DXF OffsetY= 0
DXF ScaleX= 1
DXF ScaleY= 10

--- UNT041 IN BACR.p01 (plan) ---

Plan Title=Multiple Run
Short Identifier=Multiple
Geom File=g01
Flow File=f01
Subcritical Flow
K Sum by GR= 0
Std Step Tol= 0.01
Critical Tol= 0.01
Num of Std Step Trials= 20
Max Error Tol= 0.3
Flow Tol Ratio= 0.001
Split Flow NTrial= 30
Split Flow Tol= 0.02
Split Flow Ratio= 0.02
Log Output Level= 0
Friction Slope Method= 1
Unsteady Friction Slope Method= 2
Unsteady Bridges Friction Slope Method= 1
Parabolic Critical Depth
Global Vel Dist=  1 , 1 , 1
Global Log Level= 0
CheckData=True
Encroach Param= -1, 0, 0, 0
BEGIN DESCRIPTION:
Multiple Run
END DESCRIPTION:

--- UNT041 IN BACR.f01 (steady flow) ---

Flow Title=Multiple
Program Version=4.10
Number of Profiles= 7
Profile Names=10-year,25-year,50-year,1pct_min,100-year,1pct_plu,500-year
River Rch & RM=UNT041 IN BACR,Reach-1         ,5966
     322     431     518     455     615     832     878
Boundary for River Rch & Prof#=UNT041 IN BACR,Reach-1         , 1
Up Type= 0
Dn Type= 3
Dn Slope=0.005
Boundary for River Rch & Prof#=UNT041 IN BACR,Reach-1         , 2
Up Type= 0
Dn Type= 3
Dn Slope=0.005
Boundary for River Rch & Prof#=UNT041 IN BACR,Reach-1         , 3
Up Type= 0
Dn Type= 3
Dn Slope=0.005
Boundary for River Rch & Prof#=UNT041 IN BACR,Reach-1         , 4
Up Type= 0
Dn Type= 3
Dn Slope=0.005
Boundary for River Rch & Prof#=UNT041 IN BACR,Reach-1         , 5
Up Type= 0
Dn Type= 3
Dn Slope=0.005
Boundary for River Rch & Prof#=UNT041 IN BACR,Reach-1         , 6
Up Type= 0
Dn Type= 3
Dn Slope=0.005
Boundary for River Rch & Prof#=UNT041 IN BACR,Reach-1         , 7
Up Type= 0
Dn Type= 3
Dn Slope=0.005
DSS Import GetInterval= 0
DSS Import GetPeak= 0
DSS Import FillOption= 0

--- UNT041 IN BACR.g01 (geometry) ---

Geom Title=Existing Conditions
Program Version=4.10

River Reach=UNT041 IN BACR  ,Reach-1
Reach XY= 30
      2351088.39     13142796.18       2351380.6     13142742.49
      2351578.24     13142548.53      2351793.57     13142448.73
      2352050.43     13142444.02      2352188.72     13142319.27
      2352382.74     13142266.84      2352565.06     13142081.87
      2352843.73     13141939.21      2353031.15     13141710.07
      2353425.14     13141402.01      2353869.19     13141110.39
      2354198.85     13141060.29       2354321.3     13140708.96
      2354581.17     13140537.64      2354572.58      13140479.1
      2354726.14     13140235.03      2354965.08     13140053.16
      2355110.59     13140062.37      2355163.78     13139995.33
      2355150.07     13139918.51      2355260.03     13139841.52
      2355376.22     13139831.04      2355563.25     13139926.69
      2355673.59     13139859.17      2355771.53     13139869.92
      2355762.27     13139924.59      2355843.45     13139944.49
       2355854.6     13140031.76      2356027.72     13140066.85

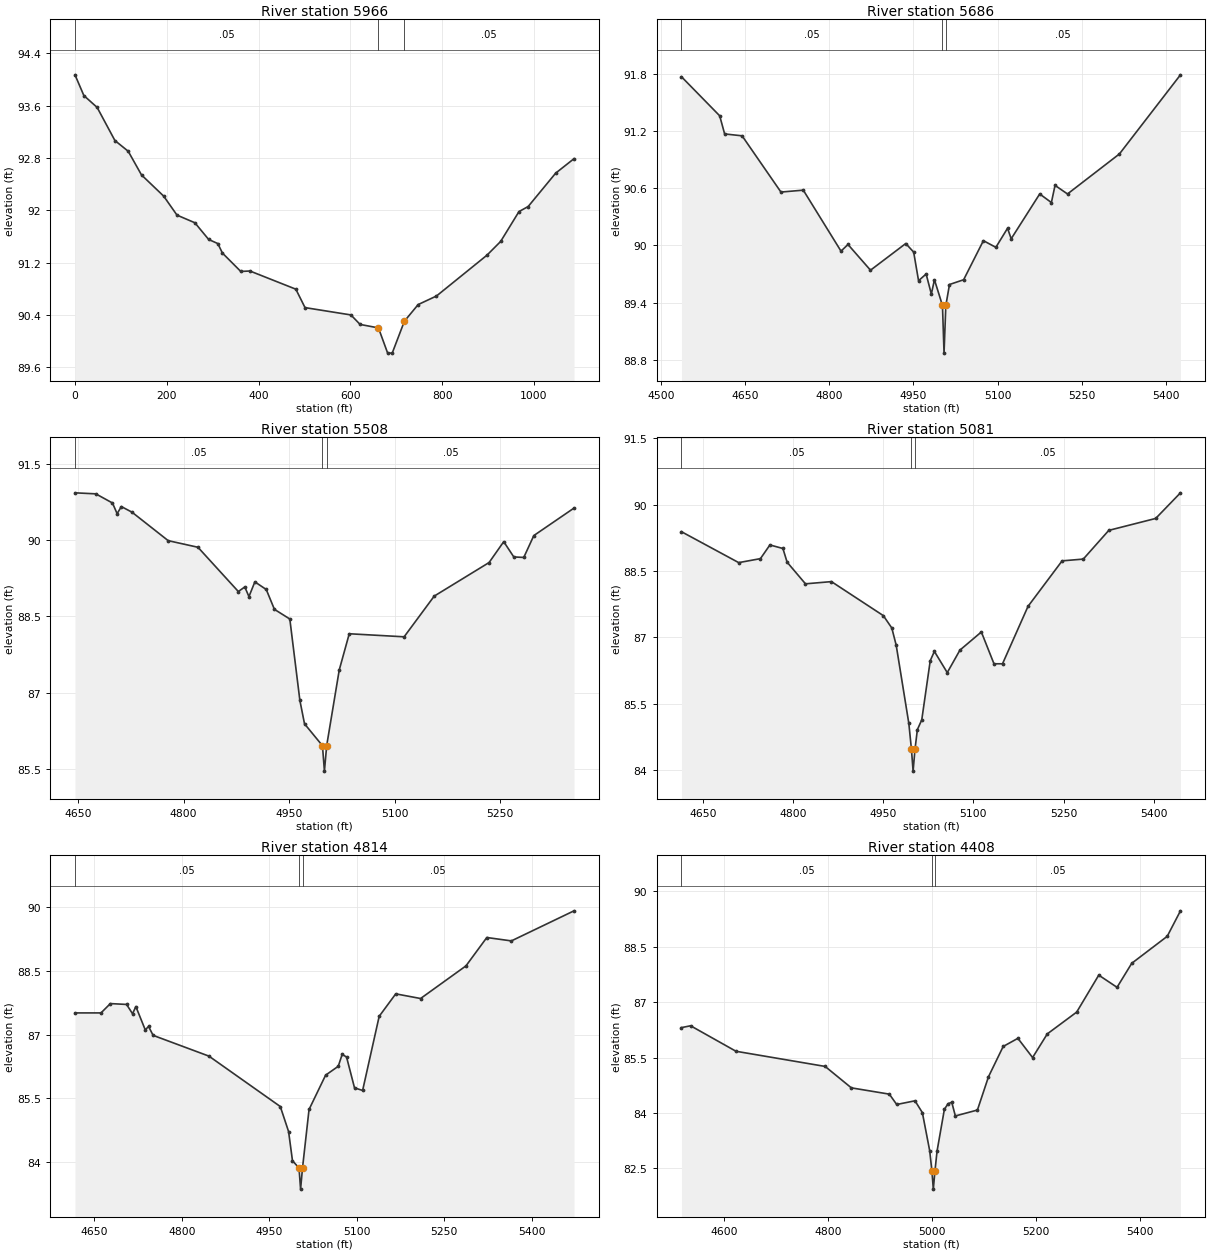
Type RM Length L Ch R = 1 ,5966    ,285,285,285
BEGIN DESCRIPTION:
UNT041 IN BACR 6.0
END DESCRIPTION:
XS GIS Cut Line= 4
     2351747.535     13143206.26     2351719.757      13142938.9
     2351629.479     13142504.87     2351386.424     13142209.73
#Sta/Elev= 30
       0 94.071919.32144 93.7552 48.3036 93.573186.94649 93.0678115.9286 92.9038
144.9108 92.5416193.2144 92.2178222.1966 91.9275261.1769 91.8106291.1713 91.5557
311.1676 91.4925321.1657 91.3477361.1583 91.0665381.1546 91.0732481.1361 90.7953
501.1324 90.5137601.1138 90.4017621.1101 90.2566661.1027 90.2035681.0989 89.8195
691.0971 89.8179717.6503 90.3057747.6082   90.56787.5521 90.6911897.3979 91.3142
927.3559 91.5252967.2999 91.9818987.2718 92.05861047.188 92.56891087.132 92.7901
#Mann= 3 , 0 , 0
       0     .05       0661.1027    .035       0717.6503     .05       0
Bank Sta=661.1027,717.6503
XS Rating Curve= 0 ,0
Exp/Cntr=0.3,0.1

Type RM Length L Ch R = 1 ,5686    ,178,178,178
BEGIN DESCRIPTION:
Mapping XS 123984dc
END DESCRIPTION:
XS GIS Cut Line= 4
      2352029.57      13142901.1       2351942.8     13142581.21
      2351879.33      13142446.5      2351564.61     13142186.17
#Sta/Elev= 30
  4536.8   91.77  4604.9   91.36  4613.7   91.17  4644.8   91.15    4714   90.56
  4753.8   90.58    4821   89.94  4833.4   90.01  4873.5   89.74  4936.3   90.02
  4950.4   89.93  4959.1   89.63  4972.6    89.7  4981.9   89.49  4987.4   89.64
  5001.7   89.37  5004.5   88.87  5007.7   89.37  5014.2   89.59  5039.4   89.64
  5074.6   90.05  5096.8   89.98  5117.6   90.18  5124.1   90.07  5174.9   90.54
  5195.7   90.45  5202.2   90.63  5224.4   90.54  5316.9   90.96  5425.6   91.79
#Mann= 3 ,-1 , 0
  4536.8     .05       0  5001.7    .035       0  5007.7     .05       0
Bank Sta=5001.7,5007.7
XS Rating Curve= 0 ,0
Exp/Cntr=0.3,0.1

Type RM Length L Ch R = 1 ,5508    ,427,427,427
BEGIN DESCRIPTION:
Mapping XS fdaa889f
END DESCRIPTION:
XS GIS Cut Line= 3
      2352255.56     13142731.67      2352109.25     13142505.04
      2351823.61     13142170.83
#Sta/Elev= 30
  4645.7   90.93  4675.3   90.91    4699   90.73  4705.6   90.52  4711.6   90.66
  4726.7   90.55  4778.2   89.99  4820.5   89.86  4877.9   88.99  4887.1   89.08
    4893   88.89  4901.4   89.18  4917.6   89.03  4929.2   88.64  4951.1   88.45
  4965.4   86.85    4972   86.39  4997.5   85.96  5000.3   85.46  5003.5   85.96
  5021.4   87.45  5035.6   88.16  5113.6    88.1  5156.4    88.9  5234.4   89.56
  5255.2   89.97  5269.5   89.67  5283.7   89.66    5298   90.09  5355.1   90.63
#Mann= 3 ,-1 , 0
  4645.7     .05       0  4997.5    .035       0  5003.5     .05       0
Bank Sta=4997.5,5003.5
XS Rating Curve= 0 ,0
Exp/Cntr=0.3,0.1

Type RM Length L Ch R = 1 ,5081    ,267,267,267
BEGIN DESCRIPTION:
UNT041 IN BACR 5.0
END DESCRIPTION:
XS GIS Cut Line= 3
      2352625.62     13142559.54      2352485.06     13142312.83
      2352109.25     13141916.94
#Sta/Elev= 30
  4614.6   89.39  4709.8   88.69  4745.9   88.78  4761.7   89.09  4783.3   89.01
  4790.3    88.7  4820.8   88.21    4864   88.26  4950.3   87.49  4964.4   87.21
  4971.7   86.82  4992.7   85.05    4997   84.47  4999.8   83.97    5003   84.47
  5006.9   84.91  5014.2   85.13  5028.3   86.47  5035.2   86.68  5056.6    86.2
  5077.7   86.71  5113.3   87.12  5134.3    86.4  5148.5    86.4  5190.9    87.7
  5247.6   88.73  5282.8   88.77  5325.2   89.42  5403.2   89.69  5444.4   90.27
#Mann= 3 ,-1 , 0
  4614.6     .05       0    4997    .035       0    5003     .05       0
Bank Sta=4997,5003
XS Rating Curve= 0 ,0
Exp/Cntr=0.3,0.1

Type RM Length L Ch R = 1 ,4814    ,406,406,406
BEGIN DESCRIPTION:
Mapping XS 99b74ed1
END DESCRIPTION:
XS GIS Cut Line= 3
      2352822.13     13142374.53      2352691.94     13142135.85
      2352257.91     13141745.23
#Sta/Elev= 30
  4616.9   87.51  4661.5   87.51  4677.6   87.73  4705.4   87.71  4715.6   87.49
  4721.3   87.66  4737.4   87.11  4743.1   87.19  4750.9   86.98  4846.6   86.49
    4969    85.3  4983.2   84.71  4989.9   84.02  5001.1   83.85  5003.8   83.35
  5007.1   83.85  5018.3   85.23  5046.7   86.04  5068.4   86.25  5075.1   86.53
  5082.6   86.47  5096.3   85.74  5110.2   85.68  5138.6   87.43    5167   87.96
  5209.6   87.85  5287.4   88.62  5323.2   89.29  5365.3   89.21  5472.7   89.92
#Mann= 3 ,-1 , 0
  4616.9     .05       0  5001.1    .035       0  5007.1     .05       0
Bank Sta=5001.1,5007.1
XS Rating Curve= 0 ,0
Exp/Cntr=0.3,0.1

Type RM Length L Ch R = 1 ,4408    ,376,376,376
BEGIN DESCRIPTION:
UNT041 IN BACR 4.0
END DESCRIPTION:
XS GIS Cut Line= 4
      2353064.88     13142270.93      2353015.77     13141911.21
      2352645.71     13141555.49       2352562.6     13141541.16
#Sta/Elev= 30
  4517.4   86.31    4535   86.36  4622.4   85.67    4794   85.26  4844.5   84.68
  4917.6   84.51  4931.8   84.23    4967   84.33  4981.2   84.01  4995.3   82.98
  4999.5   82.44  5002.3   81.94  5005.5   82.44  5009.5   82.97  5023.6    84.1
  5030.6   84.25  5037.8   84.29  5044.7   83.92  5087.2   84.08  5108.5   84.98
  5136.8    85.8  5165.1   86.02  5193.4    85.5  5221.7   86.14  5278.3   86.73
  5320.8   87.73    5356    87.4  5384.3   88.05  5452.6   88.78  5478.1   89.47
#Mann= 3 ,-1 , 0
  4517.4     .05       0  4999.5    .035       0  5005.5     .05       0
Bank Sta=4999.5,5005.5
XS Rating Curve= 0 ,0
Exp/Cntr=0.3,0.1

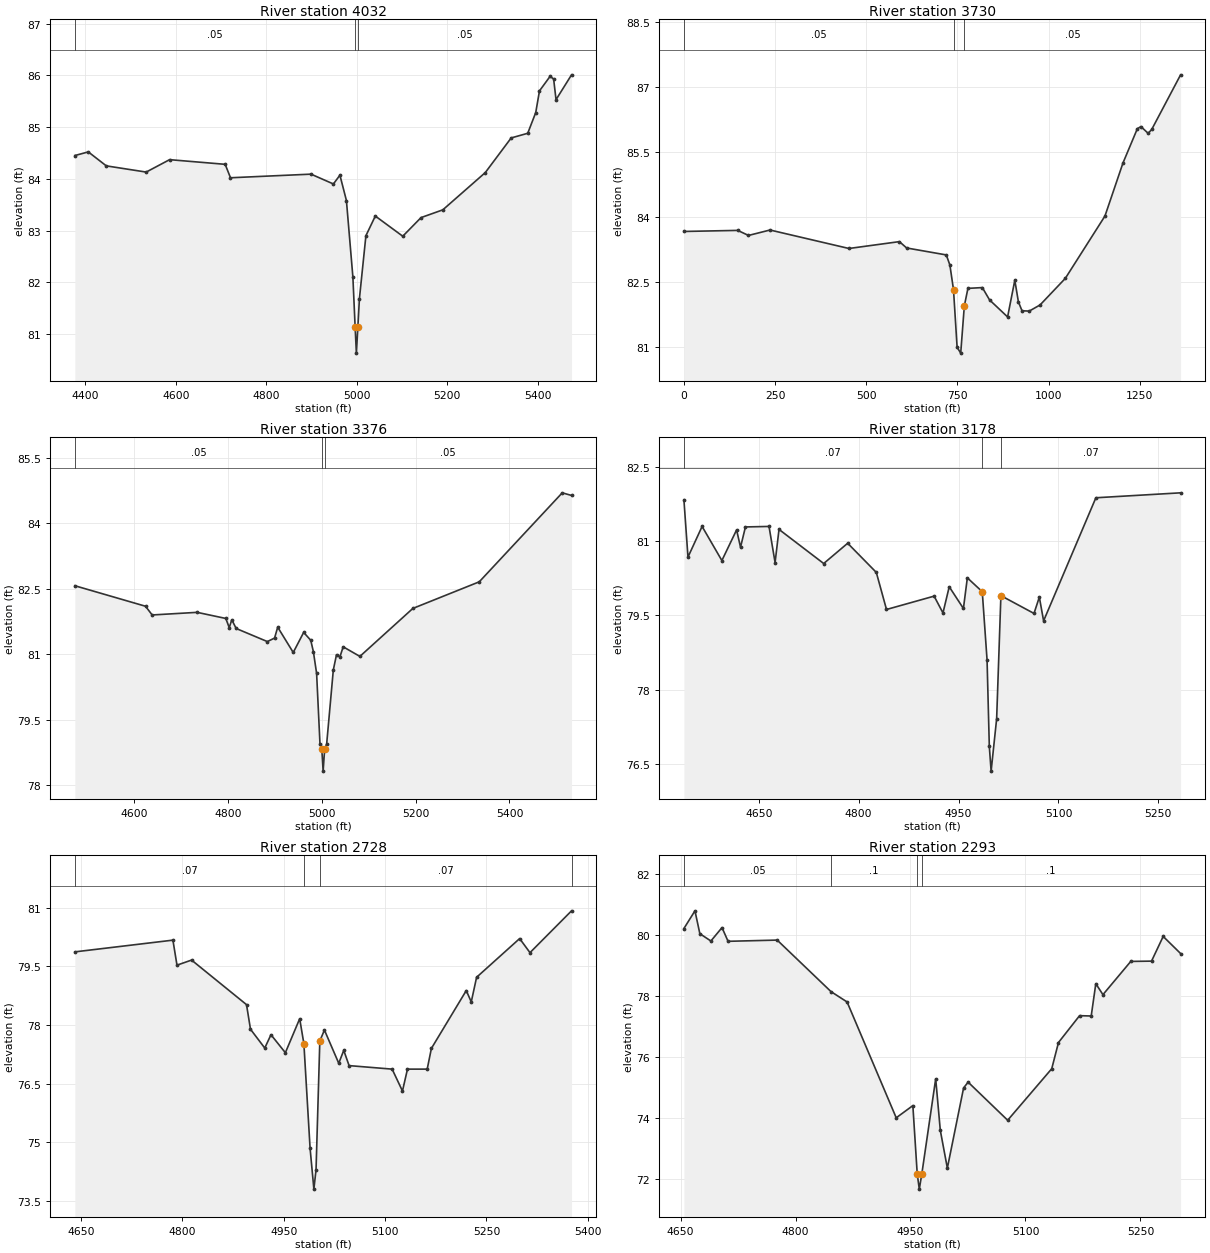
Type RM Length L Ch R = 1 ,4032    ,303,303,303
BEGIN DESCRIPTION:
Mapping XS dca22ca7
END DESCRIPTION:
XS GIS Cut Line= 4
      2353264.51     13142119.01      2353360.02     13141767.77
      2353164.64     13141527.38      2352762.78     13141389.88
#Sta/Elev= 30
  4376.7   84.45  4406.4   84.52  4446.2   84.25  4534.4   84.13  4586.2   84.37
  4709.1   84.28  4720.9   84.02    4899   84.09  4948.5    83.9  4962.9   84.07
  4977.3   83.58  4991.6    82.1  4996.6   81.13  4999.3   80.63  5002.6   81.13
    5006   81.68  5020.4    82.9  5041.2   83.28  5101.9   82.89  5142.3   83.25
  5190.5    83.4  5284.4   84.12  5341.7   84.79  5378.3   84.88    5396   85.28
  5404.3    85.7  5427.7   85.98  5435.6   85.93  5440.9   85.53  5475.2   86.01
#Mann= 3 ,-1 , 0
  4376.7     .05       0  4996.6    .035       0  5002.6     .05       0
Bank Sta=4996.6,5002.6
XS Rating Curve= 0 ,0
Exp/Cntr=0.3,0.1

Type RM Length L Ch R = 1 ,3730    ,353,353,353
BEGIN DESCRIPTION:
UNT041 IN BACR 3.0
END DESCRIPTION:
XS GIS Cut Line= 4
     2353435.035     13142094.28     2353570.452     13141643.76
     2353281.389     13141078.66     2353156.389     13140862.51
#Sta/Elev= 30
       0 83.6707147.5854 83.6952177.1025  83.579236.1366 83.7041452.5952 83.2787
590.9462 83.4368 610.725 83.2907719.5084 83.1303729.3979 82.8969739.2873 82.3299
749.1767  81.004759.0661 80.8692768.9555 81.9554778.8449 82.3603818.4025 82.3785
838.1813 82.0943887.6284 81.7026907.4072 82.5472917.2966 82.0482 927.186 81.8446
946.9648 81.8371976.6331 81.97821045.859   82.591154.582 84.02551203.969 85.2463
1243.478 86.03771253.355 86.0852 1273.11   85.931282.988 86.02151362.006 87.2774
#Mann= 3 , 0 , 0
       0     .05       0739.2873    .035       0768.9555     .05       0
Bank Sta=739.2873,768.9555
XS Rating Curve= 0 ,0
Exp/Cntr=0.3,0.1

Type RM Length L Ch R = 1 ,3376    ,198,198,198
BEGIN DESCRIPTION:
Mapping XS 430e64fc
END DESCRIPTION:
XS GIS Cut Line= 4
      2353752.59      13141644.5      2353887.98     13141496.09
      2353760.38     13141225.25      2353376.31     13140820.43
#Sta/Elev= 30
  4473.9   82.57  4624.4    82.1  4638.6    81.9  4734.4   81.96  4795.5   81.82
  4802.8   81.61  4808.3   81.79  4817.6   81.59    4884   81.29  4899.4   81.37
  4906.1   81.62  4939.2   81.04  4961.4    81.5  4976.5   81.32  4982.1   81.06
    4989   80.56  4996.2   78.94  5000.1   78.82  5002.9   78.32  5006.1   78.82
  5010.4   78.94  5024.6   80.64  5031.4   80.99  5038.7   80.94  5045.6   81.17
  5081.2   80.95  5194.1   82.05  5335.6   82.66  5512.4    84.7  5532.2   84.64
#Mann= 3 ,-1 , 0
  4473.9     .05       0  5000.1    .035       0  5006.1     .05       0
Bank Sta=5000.1,5006.1
XS Rating Curve= 0 ,0
Exp/Cntr=0.3,0.1

Type RM Length L Ch R = 1 ,3178    ,450,450,450
BEGIN DESCRIPTION:
Mapping XS de6be4ae
END DESCRIPTION:
XS GIS Cut Line= 3
      2354157.11     13141485.15       2353922.3     13141110.83
      2353684.41     13140921.67
#Sta/Elev= 30
  4537.6   81.84  4543.7   80.68  4564.9    81.3  4594.6   80.61  4616.7   81.23
  4622.6   80.88    4630   81.29  4665.4    81.3  4674.5   80.57  4680.4   81.24
  4747.5   80.55  4783.5   80.96  4826.5   80.37  4841.8   79.62  4913.3   79.89
  4926.6   79.55    4936   80.08  4957.3   79.64  4963.2   80.26  4985.6   79.98
  4992.8    78.6  4996.2   76.85  4998.9   76.35  5007.2   77.41  5013.6    79.9
  5063.3   79.54  5071.3   79.87  5077.7   79.39  5156.2   81.88  5283.4   81.98
#Mann= 3 , 0 , 0
  4537.6     .07       0  4985.6    .035       0  5013.6     .07       0
Bank Sta=4985.6,5013.6
XS Rating Curve= 0 ,0
Exp/Cntr=0.3,0.1

Type RM Length L Ch R = 1 ,2728    ,435,435,435
BEGIN DESCRIPTION:
UNT041 IN BACR 2.0
END DESCRIPTION:
XS GIS Cut Line= 3
      2354462.74     13141221.88       2354298.1      13140967.4
      2353931.84     13140738.49
#Sta/Elev= 30
    4641   79.87  4786.1   80.17  4792.1   79.53  4813.7   79.66    4895   78.52
  4900.9   77.89    4922   77.41  4931.2   77.75  4952.5   77.29  4973.7   78.16
  4979.9   77.52  4989.1   74.84  4994.7    73.8  4997.9    74.3  5003.5   77.59
  5010.3   77.87  5031.5   77.02  5038.9   77.35  5046.8   76.96  5110.5   76.87
  5125.8   76.31  5133.2   76.87  5162.4   76.87  5168.6    77.4  5220.2   78.88
  5227.6   78.59  5235.5   79.22  5299.2   80.21  5314.5   79.85    5376   80.92
#Mann= 4 ,-1 , 0
    4641     .07       0  4979.9    .035       0  5003.5     .07       0
    5376      .1       0
Bank Sta=4979.9,5003.5
XS Rating Curve= 0 ,0
Exp/Cntr=0.3,0.1

Type RM Length L Ch R = 1 ,2293    ,450,450,450
BEGIN DESCRIPTION:
Mapping XS 08194c4e
END DESCRIPTION:
XS GIS Cut Line= 3
      2354712.74     13140871.88      2354550.55     13140669.05
      2354223.55     13140459.66
#Sta/Elev= 30
  4654.4   80.21  4668.8   80.79  4675.2   80.04  4689.6    79.8  4704.1   80.24
    4712   79.79  4776.1   79.83  4846.3   78.14  4867.3    77.8  4931.4      74
  4953.1    74.4  4958.8   72.16  4961.5   71.66  4964.8   72.16  4982.9   75.28
  4988.9   73.59  4998.1   72.35  5019.3   74.98  5025.2   75.17  5076.8   73.92
  5134.3   75.61  5143.1   76.47  5170.6   77.35  5185.8   77.34  5191.8    78.4
  5201.1   78.04  5237.4   79.13  5264.5   79.14  5279.7   79.95  5302.4   79.39
#Mann= 4 ,-1 , 0
  4654.4     .05       0  4846.3      .1       0  4958.8     .07       0
  4964.8      .1       0
Bank Sta=4958.8,4964.8
XS Rating Curve= 0 ,0
Exp/Cntr=0.3,0.1

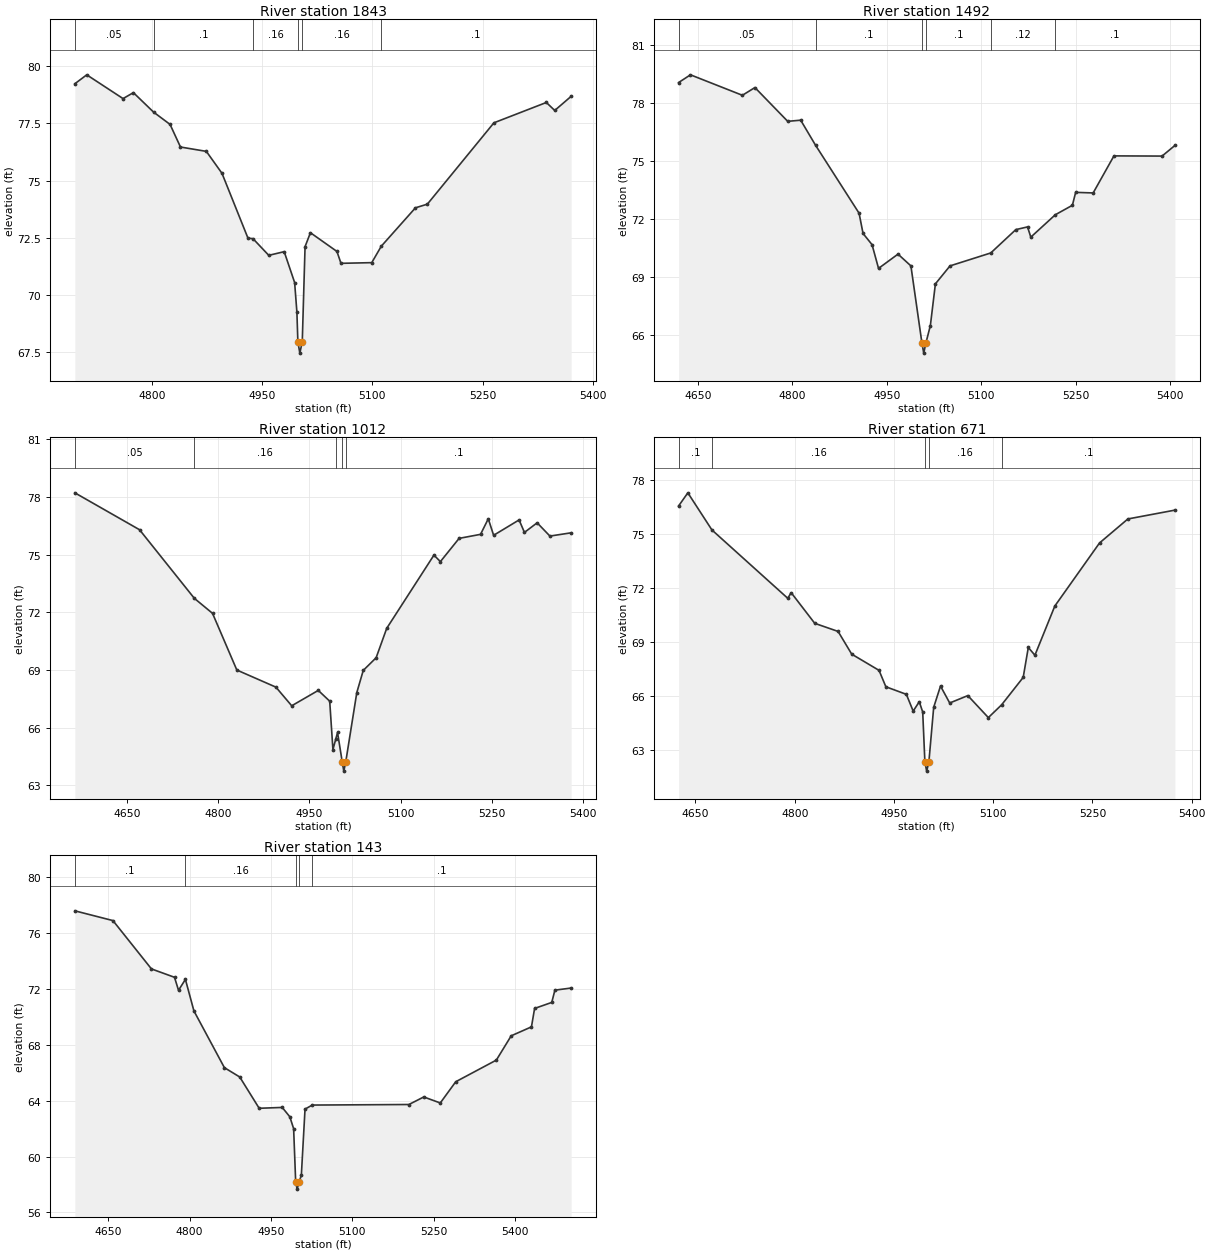
Type RM Length L Ch R = 1 ,1843    ,351,351,351
BEGIN DESCRIPTION:
Mapping XS 7f363b9a
END DESCRIPTION:
XS GIS Cut Line= 3
      2354934.95     13140482.57      2354676.77     13140244.48
      2354376.48      13140121.5
#Sta/Elev= 30
    4695   79.24  4711.2   79.63  4760.6   78.59  4774.7   78.85  4802.1      78
  4824.6   77.46  4838.8   76.47    4874   76.28  4895.3   75.32  4930.7   72.48
  4937.5   72.46    4959   71.73    4980   71.89  4994.2   70.54  4997.3   69.24
  4998.6   67.95  5001.3   67.45  5004.6   67.95  5008.4   72.11  5015.7   72.72
  5051.8    71.9  5057.3   71.38  5099.2   71.41  5112.2   72.13  5158.7   73.81
  5174.9   73.97  5265.5   77.53  5336.9   78.42  5348.3   78.07  5370.7   78.69
#Mann= 6 ,-1 , 0
    4695     .05       0  4802.1      .1       0  4937.5     .16       0
  4998.6     .07       0  5004.6     .16       0  5112.2      .1       0
Bank Sta=4998.6,5004.6
XS Rating Curve= 0 ,0
Exp/Cntr=0.3,0.1

Type RM Length L Ch R = 1 ,1492    ,480,480,480
BEGIN DESCRIPTION:
Mapping XS ecb3f7a8
END DESCRIPTION:
XS GIS Cut Line= 3
      2355052.58     13140425.24      2354955.04     13140026.45
      2354846.02     13139664.97
#Sta/Elev= 30
  4619.3   79.06  4638.2   79.46  4720.6    78.4  4740.5    78.8  4792.6   77.05
  4813.2   77.11  4836.8   75.81  4905.9   72.29  4912.2   71.24  4926.5   70.66
  4936.8   69.43  4967.7   70.17  4988.2   69.56  5005.8   65.54  5008.6   65.04
  5011.8   65.54  5019.1   66.47  5027.1   68.63  5050.3   69.56    5115   70.23
  5154.8   71.44  5173.4   71.58  5178.6   71.05  5217.5   72.21  5244.6    72.7
  5249.8   73.37  5277.6   73.34  5310.6   75.26    5387   75.25  5407.4    75.8
#Mann= 6 ,-1 , 0
  4619.3     .05       0  4836.8      .1       0  5005.8     .07       0
  5011.8      .1       0    5115     .12       0  5217.5      .1       0
Bank Sta=5005.8,5011.8
XS Rating Curve= 0 ,0
Exp/Cntr=0.3,0.1

Type RM Length L Ch R = 1 ,1012    ,341,341,341
BEGIN DESCRIPTION:
Mapping XS 1c2a68bd
END DESCRIPTION:
XS GIS Cut Line= 4
      2355305.03      13140273.2      2355293.55     13139946.13
      2355193.14     13139653.52      2355045.17     13139551.07
#Sta/Elev= 30
    4564   78.22  4670.4    76.3  4760.6   72.73  4790.5   71.95  4830.5      69
  4894.8   68.11  4920.8   67.14  4964.5   67.94  4983.3   67.38  4988.6   64.86
  4993.3   65.41  4996.2   65.75  5003.8   64.24  5006.5   63.74  5009.8   64.24
  5027.9   67.83  5038.5   68.98  5059.7   69.64  5077.1   71.17  5154.8   74.98
  5165.4   74.64  5196.2   75.85  5231.5   76.06  5244.2   76.87    5253   76.01
  5294.9   76.81  5303.7   76.16  5324.6   76.66  5345.6   75.97  5380.6   76.14
#Mann= 5 ,-1 , 0
    4564     .05       0  4760.6     .16       0  4993.3      .1       0
  5003.8     .07       0  5009.8      .1       0
Bank Sta=5003.8,5009.8
XS Rating Curve= 0 ,0
Exp/Cntr=0.3,0.1

Type RM Length L Ch R = 1 ,671     ,528,528,528
BEGIN DESCRIPTION:
Mapping XS c89fd5aa
END DESCRIPTION:
XS GIS Cut Line= 3
      2355471.41     13140290.39      2355589.03     13139831.38
      2355611.98     13139555.98
#Sta/Elev= 30
  4624.5   76.54  4638.5   77.27  4674.9   75.21  4789.5   71.42  4794.7   71.73
  4830.3   70.03  4865.6   69.58  4886.2   68.32  4927.5   67.42  4937.8   66.51
  4968.8   66.09  4979.1   65.16  4988.3   65.68  4993.5   65.11  4996.8   62.33
  4999.5   61.83  5002.8   62.33  5010.1   65.37  5020.4   66.55  5034.3   65.61
  5061.7   66.02  5092.7    64.8  5112.8   65.51  5145.4   67.03  5153.1   68.69
  5163.1   68.26  5193.2   70.99  5260.8   74.49  5303.6   75.82  5374.7   76.31
#Mann= 5 ,-1 , 0
  4624.5      .1       0  4674.9     .16       0  4996.8     .07       0
  5002.8     .16       0  5112.8      .1       0
Bank Sta=4996.8,5002.8
XS Rating Curve= 0 ,0
Exp/Cntr=0.3,0.1

Type RM Length L Ch R = 1 ,143     ,0,0,0
BEGIN DESCRIPTION:
UNT041 IN BACR 1.0
END DESCRIPTION:
XS GIS Cut Line= 4
      2355586.13     13140324.83      2355907.46     13140029.32
      2355927.54      13139957.6      2355726.75     13139607.65
#Sta/Elev= 30
  4588.7    77.6  4658.9    76.9  4729.8   73.44  4772.3   72.84  4779.7   71.91
  4792.4   72.69  4808.1   70.43  4864.2   66.37  4892.5    65.7  4928.3   63.46
  4970.8   63.52  4984.8   62.85  4991.8      62  4995.6   58.17  4998.3   57.67
  5001.6   58.17    5006   58.65  5012.8    63.4  5026.1   63.69  5204.2   63.73
  5231.6   64.27    5262   63.84  5290.5   65.36  5365.3   66.91  5392.7   68.65
    5430   69.29  5435.8   70.61  5467.4   71.04  5473.2   71.92  5503.2   72.07
#Mann= 5 ,-1 , 0
  4588.7      .1       0  4792.4     .16       0  4995.6     .07       0
  5001.6     .16       0  5026.1      .1       0
Bank Sta=4995.6,5001.6
XS Rating Curve= 0 ,0
Exp/Cntr=0.3,0.1
Stream Node=UNT041 IN BACR  ,Reach-1         , 0 , 0 ,Upstream end
Stream Node=UNT041 IN BACR  ,Reach-1         , 0 , 1 ,Downstream end

Chan Stop Cuts=-1
Use User Specified Reach Order=0
Composite Channel Slope=5