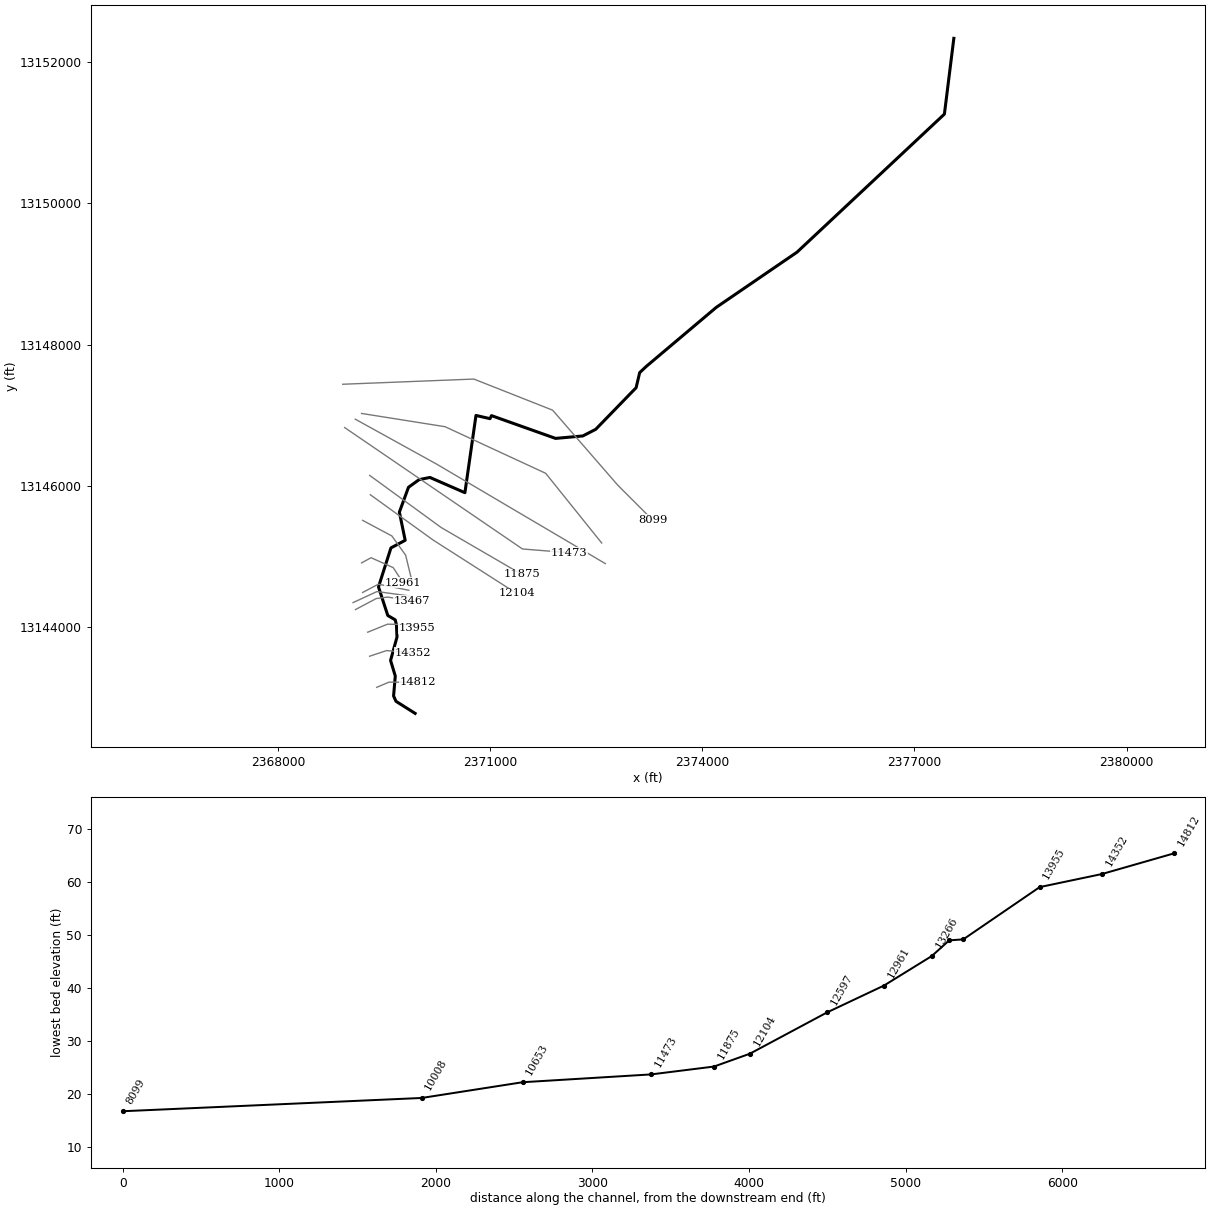
--- UNT042 IN BACR.prj (project) ---

Proj Title=UNT042 IN BACR Base Level Engineering
Current Plan=p01
Default Exp/Contr=0.3,0.1
English Units
Geom File=g01
Flow File=f01
Plan File=p01
Y Axis Title=Elevation
X Axis Title(PF)=Main Channel Distance
X Axis Title(XS)=Station
BEGIN DESCRIPTION:
UNT042 IN BACR
END DESCRIPTION:
DSS Export Rating Curves= 0
DSS Export Rating Curve Sorted= 0
DSS Export Volume Flow Curves= 0
DXF OffsetX= 0
DXF OffsetY= 0
DXF ScaleX= 1
DXF ScaleY= 10

--- UNT042 IN BACR.p01 (plan) ---

Plan Title=Multiple Run
Short Identifier=Multiple
Geom File=g01
Flow File=f01
Subcritical Flow
K Sum by GR= 0
Std Step Tol= 0.01
Critical Tol= 0.01
Num of Std Step Trials= 20
Max Error Tol= 0.3
Flow Tol Ratio= 0.001
Split Flow NTrial= 30
Split Flow Tol= 0.02
Split Flow Ratio= 0.02
Log Output Level= 0
Friction Slope Method= 1
Unsteady Friction Slope Method= 2
Unsteady Bridges Friction Slope Method= 1
Parabolic Critical Depth
Global Vel Dist=  1 , 1 , 1
Global Log Level= 0
CheckData=True
Encroach Param= -1, 0, 0, 0
BEGIN DESCRIPTION:
Multiple Run
END DESCRIPTION:

--- UNT042 IN BACR.f01 (steady flow) ---

Flow Title=Multiple
Program Version=4.10
Number of Profiles= 7
Profile Names=10-year,25-year,50-year,1pct_min,100-year,1pct_plu,500-year
River Rch & RM=UNT042 IN BACR,Reach-1         ,14812
     304     413     501     447     604     817     885
River Rch & RM=UNT042 IN BACR,Reach-1         ,11875
     718    1003    1240    1119    1513    2046    2277
River Rch & RM=UNT042 IN BACR,Reach-1         ,11473
     718    1003    1240    1119    1513    2046    2277
River Rch & RM=UNT042 IN BACR,Reach-1         ,10008
     718    1003    1240    1119    1513    2046    2277
River Rch & RM=UNT042 IN BACR,Reach-1         ,8099
     718    1003    1240    1119    1513    2046    2277
Boundary for River Rch & Prof#=UNT042 IN BACR,Reach-1         , 1
Up Type= 0
Dn Type= 3
Dn Slope=0.0018
Boundary for River Rch & Prof#=UNT042 IN BACR,Reach-1         , 2
Up Type= 0
Dn Type= 3
Dn Slope=0.0018
Boundary for River Rch & Prof#=UNT042 IN BACR,Reach-1         , 3
Up Type= 0
Dn Type= 3
Dn Slope=0.0018
Boundary for River Rch & Prof#=UNT042 IN BACR,Reach-1         , 4
Up Type= 0
Dn Type= 3
Dn Slope=0.0018
Boundary for River Rch & Prof#=UNT042 IN BACR,Reach-1         , 5
Up Type= 0
Dn Type= 3
Dn Slope=0.0018
Boundary for River Rch & Prof#=UNT042 IN BACR,Reach-1         , 6
Up Type= 0
Dn Type= 3
Dn Slope=0.0018
Boundary for River Rch & Prof#=UNT042 IN BACR,Reach-1         , 7
Up Type= 0
Dn Type= 3
Dn Slope=0.0018
DSS Import GetInterval= 0
DSS Import GetPeak= 0
DSS Import FillOption= 0

--- UNT042 IN BACR.g01 (geometry) ---

Geom Title=Existing Conditions
Program Version=4.10

River Reach=UNT042 IN BACR  ,Reach-1
Reach XY= 30
      2369937.72     13142782.52      2369666.89     13142953.38
      2369632.95     13143028.51      2369657.03     13143311.42
      2369590.45     13143531.82      2369681.23     13143863.19
      2369673.36     13144036.26      2369656.06     13144106.29
      2369550.92     13144167.95      2369419.51     13144572.67
      2369595.68     13145124.48      2369797.15     13145232.22
      2369715.04     13145631.16      2369843.66     13145982.29
      2369993.66     13146090.62      2370147.13     13146121.87
       2370641.8     13145906.01      2370798.51     13146999.44
      2370997.12      13146953.6      2371017.72     13146996.86
      2371924.19     13146674.35      2372309.61     13146709.08
       2372491.9     13146802.83      2373063.48     13147391.77
      2373113.83     13147605.31      2373205.84     13147692.11
      2374197.16     13148528.92      2375339.52     13149310.17
      2377424.14     13151264.36      2377557.72     13152336.85

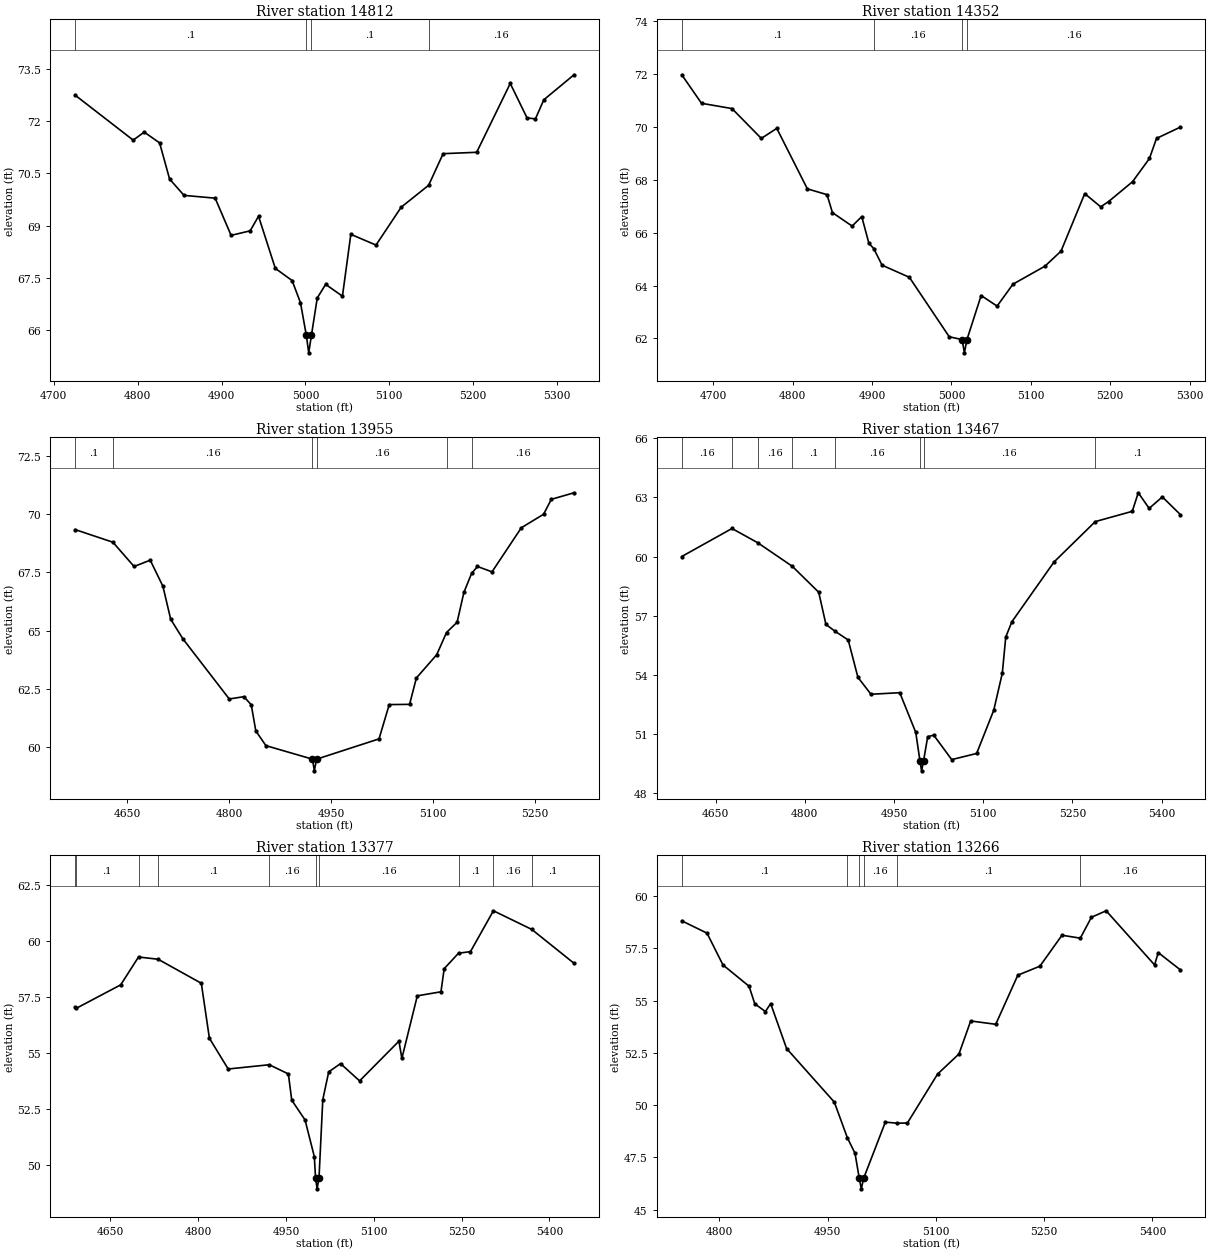
Type RM Length L Ch R = 1 ,14812   ,460,460,460
BEGIN DESCRIPTION:
UNT042 IN BACR 14.0
END DESCRIPTION:
XS GIS Cut Line= 3
      2369394.16     13143151.01      2369567.63      13143224.4
      2369973.68      13143224.4
#Sta/Elev= 30
  4725.7   72.75  4794.7   71.46  4807.9   71.69  4826.2   71.38  4838.1   70.34
  4855.3   69.87  4892.4   69.79  4911.4   68.72  4934.1   68.85  4944.1   69.27
  4964.1   67.77  4984.1   67.42  4994.1   66.78  5001.1   65.84  5003.9   65.34
  5007.1   65.84  5014.1   66.92  5024.1   67.31  5044.1   66.97  5054.1   68.75
  5084.1   68.44  5114.1   69.53  5146.8   70.16  5164.1   71.07  5204.1   71.11
  5244.1   73.09  5264.1    72.1  5274.1   72.07  5284.1   72.62  5320.1   73.34
#Mann= 4 ,-1 , 0
  4725.7      .1       0  5001.1     .07       0  5007.1      .1       0
  5146.8     .16       0
Bank Sta=5001.1,5007.1
XS Rating Curve= 0 ,0
Exp/Cntr=0.3,0.1

Type RM Length L Ch R = 1 ,14352   ,397,397,397
BEGIN DESCRIPTION:
UNT042 IN BACR 13.0
END DESCRIPTION:
XS GIS Cut Line= 3
      2369294.12     13143591.35      2369534.28      13143671.4
      2369907.85     13143638.04
#Sta/Elev= 30
  4660.3   71.98  4685.2    70.9  4723.6    70.7  4760.5   69.57    4780   69.95
  4818.5   67.66  4843.3   67.44  4850.1   66.76  4874.9   66.25    4887   66.61
    4896    65.6  4902.1    65.4  4912.6   64.77    4947   64.31  4997.2   62.06
  5013.5   61.95  5016.3   61.45  5019.5   61.95  5037.4   63.62  5057.5   63.22
  5077.5   64.05  5117.7   64.73    5138    65.3  5167.9   67.48    5188   66.98
    5198   67.18  5228.1   67.93  5249.4   68.81  5258.3   69.57  5288.5      70
#Mann= 4 ,-1 , 0
  4660.3      .1       0  4902.1     .16       0  5013.5     .07       0
  5019.5     .16       0
Bank Sta=5013.5,5019.5
XS Rating Curve= 0 ,0
Exp/Cntr=0.3,0.1

Type RM Length L Ch R = 1 ,13955   ,488,488,488
BEGIN DESCRIPTION:
UNT042 IN BACR 12.0
END DESCRIPTION:
XS GIS Cut Line= 4
      2369267.44      13143931.6      2369547.62     13144045.01
      2369854.51     13144038.34      2369967.96     13143984.95
#Sta/Elev= 30
  4573.1   69.33  4628.5   68.79  4659.7   67.75  4683.5   68.02  4702.2    66.9
  4713.6   65.49  4731.8   64.64  4799.9   62.07  4821.5   62.17  4832.3   61.82
    4839    60.7  4853.9   60.07  4922.5   59.49  4925.2   58.99  4928.5   59.49
  5020.5   60.36  5035.5   61.83  5065.5   61.84  5075.5   62.97  5105.5   63.97
  5119.9   64.92  5135.5   65.36  5145.5   66.64  5156.8   67.45  5165.5   67.75
  5186.9   67.52  5230.1   69.41  5262.9   69.99  5274.3   70.63  5307.7   70.91
#Mann= 6 ,-1 , 0
  4573.1      .1       0  4628.5     .16       0  4922.5     .07       0
  4928.5     .16       0  5119.9      .1       0  5156.8     .16       0
Bank Sta=4922.5,4928.5
XS Rating Curve= 0 ,0
Exp/Cntr=0.3,0.1

Type RM Length L Ch R = 1 ,13467   ,90,90,90
BEGIN DESCRIPTION:
Mapping XS 64f7e3ea
END DESCRIPTION:
XS GIS Cut Line= 4
      2369093.56     13144251.53      2369387.86     13144407.79
      2369549.32     13144428.62      2369887.82     13144373.94
#Sta/Elev= 30
    4593      60  4677.5   61.42  4720.7    60.7  4778.7   59.51  4823.4   58.19
  4835.5   56.56  4850.5   56.22    4873   55.77  4889.3   53.88  4911.3   53.02
  4959.7    53.1  4986.6   51.09  4993.7   49.64  4996.4   49.14  4999.7   49.64
  5006.7   50.87  5016.8   50.95  5047.1   49.71    5089   50.02  5117.8   52.21
  5132.2   54.09    5138   55.92  5148.2   56.69  5219.1   59.72  5288.6   61.77
  5350.8   62.29  5360.9   63.23  5379.2   62.44  5401.4   63.02  5431.9   62.12
#Mann= 8 ,-1 , 0
    4593     .16       0  4677.5      .1       0  4720.7     .16       0
  4778.7      .1       0  4850.5     .16       0  4993.7     .07       0
  4999.7     .16       0  5288.6      .1       0
Bank Sta=4993.7,4999.7
XS Rating Curve= 0 ,0
Exp/Cntr=0.3,0.1

Type RM Length L Ch R = 1 ,13377   ,111,111,111
BEGIN DESCRIPTION:
UNT042 IN BACR 11.0
END DESCRIPTION:
XS GIS Cut Line= 3
       2369059.7     13144350.48      2369398.27     13144506.75
      2369872.97      13144441.9
#Sta/Elev= 30
    4590   57.05  4591.4   56.99  4667.6   58.04    4698   59.28  4731.5   59.18
  4805.3   58.11  4819.1   55.66  4851.2   54.29  4921.4   54.48    4954   54.07
  4959.8    52.9  4982.5   52.02  4998.4   50.38  5000.4   49.45  5003.1   48.95
  5006.4   49.45  5012.8   52.92  5022.9   54.16  5043.1   54.53  5075.7   53.76
  5142.9   55.53  5147.9   54.76  5174.3   57.55  5214.7   57.73  5220.2   58.76
  5244.7   59.45  5265.1   59.52  5304.3   61.34  5369.8   60.51    5442      59
#Mann= 10 ,-1 , 0
    4590     .16       0  4591.4      .1       0    4698     .16       0
  4731.5      .1       0  4921.4     .16       0  5000.4     .07       0
  5006.4     .16       0  5244.7      .1       0  5304.3     .16       0
  5369.8      .1       0
Bank Sta=5000.4,5006.4
XS Rating Curve= 0 ,0
Exp/Cntr=0.3,0.1

Type RM Length L Ch R = 1 ,13266   ,305,305,305
BEGIN DESCRIPTION:
UNT042 IN BACR 10.0
END DESCRIPTION:
XS GIS Cut Line= 3
      2369195.16     13144493.73      2369418.49     13144611.11
      2369848.76     13144524.99
#Sta/Elev= 30
  4747.7   58.82  4782.7   58.23  4804.8   56.71    4841   55.69  4848.9   54.85
  4863.6   54.48  4870.9   54.86    4893   52.71  4959.1   50.15  4977.1   48.45
  4987.8    47.7  4993.7    46.5  4996.5      46  4999.7    46.5  5029.8   49.19
  5046.3   49.14  5060.4   49.15  5102.2   51.49  5131.8   52.45  5148.1   54.03
  5182.8   53.87  5213.4   56.22    5244   56.65  5274.6   58.13    5300   57.99
  5315.4   58.99  5335.8    59.3  5402.9   56.71    5408    57.3  5438.8   56.47
#Mann= 6 ,-1 , 0
  4747.7      .1       0  4977.1     .16       0  4993.7     .07       0
  4999.7     .16       0  5046.3      .1       0    5300     .16       0
Bank Sta=4993.7,4999.7
XS Rating Curve= 0 ,0
Exp/Cntr=0.3,0.1

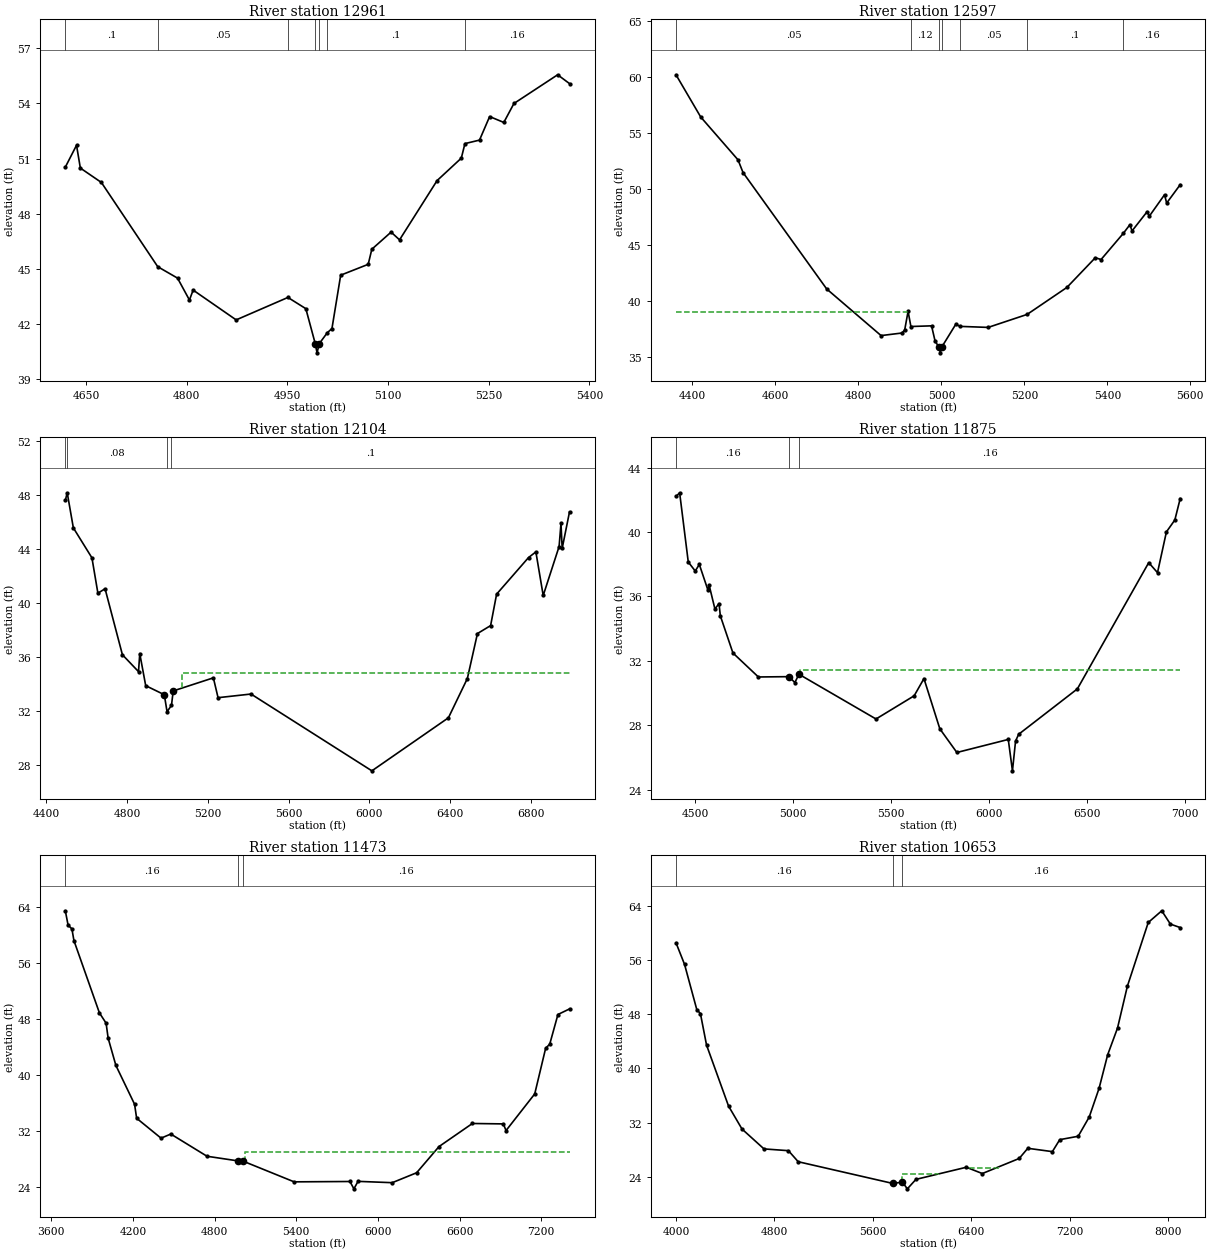
Type RM Length L Ch R = 1 ,12961   ,364,364,364
BEGIN DESCRIPTION:
Mapping XS f0a35257
END DESCRIPTION:
XS GIS Cut Line= 4
       2369180.7     13144912.33      2369314.11     13144985.71
      2369627.68      13144845.6       2369767.8     13144632.08
#Sta/Elev= 30
  4619.2   50.53  4635.9   51.72  4641.6   50.48  4672.9    49.7  4756.9   45.12
  4786.4    44.5  4804.1   43.31  4809.6   43.85  4873.7   42.23  4950.8   43.45
  4977.5   42.84  4991.5   40.94  4994.2   40.44  4997.5   40.94  5009.4   41.53
  5016.4   41.76  5029.4   44.66  5070.4   45.25  5075.8   46.07  5104.5      47
  5117.1   46.58    5173    49.8  5209.1   51.02  5214.5   51.81  5236.2      52
  5251.3   53.28  5272.4   52.96  5287.5   53.99  5352.6   55.55  5370.3   55.07
#Mann= 7 ,-1 , 0
  4619.2      .1       0  4756.9     .05       0  4950.8     .12       0
  4991.5     .07       0  4997.5     .12       0  5009.4      .1       0
  5214.5     .16       0
Bank Sta=4991.5,4997.5
XS Rating Curve= 0 ,0
Exp/Cntr=0.3,0.1

Type RM Length L Ch R = 1 ,12597   ,493,493,493
BEGIN DESCRIPTION:
UNT042 IN BACR 9.0
END DESCRIPTION:
XS GIS Cut Line= 4
      2369195.16     13145514.55      2369609.23     13145293.23
      2369803.21     13145022.21      2369900.81     13144621.62
#Sta/Elev= 30
  4360.4   60.19    4420   56.42  4509.8    52.6    4522   51.46  4723.6   41.07
  4854.6   36.91    4905   37.14  4911.5   37.41  4919.7   39.07  4926.5   37.72
  4976.3   37.78  4984.9    36.4  4994.6   35.87  4997.4   35.37  5000.6   35.87
  5034.5   37.91  5045.6   37.73  5112.6   37.64  5206.6    38.8  5302.5   41.21
  5370.9   43.86  5384.8    43.7  5438.3   46.03  5454.3   46.81  5459.4   46.25
    5496   47.98  5501.1   47.57  5537.7   49.48  5542.9   48.74  5575.5   50.38
#Mann= 7 ,-1 , 0
  4360.4     .05       0  4926.5     .12       0  4994.6     .07       0
  5000.6     .12       0  5045.6     .05       0  5206.6      .1       0
  5438.3     .16       0
#XS Ineff= 2 , 0
       0 4919.77   39.06               0
Permanent Ineff=
       T       F
Bank Sta=4994.6,5000.6
XS Rating Curve= 0 ,0
Exp/Cntr=0.3,0.1

Type RM Length L Ch R = 1 ,12104   ,229,229,229
BEGIN DESCRIPTION:
UNT042 IN BACR 8.0
END DESCRIPTION:
XS GIS Cut Line= 3
      2369303.62     13145877.43      2370193.41     13145235.05
      2371371.79     13144481.24
#Sta/Elev= 30
  4494.3   47.62  4503.7   48.19  4534.1   45.59  4626.1   43.37  4655.6   40.75
  4691.1   41.08    4777   36.19  4856.7   34.94  4862.9   36.28  4892.3    33.9
  4984.4   33.23    4998   31.97  5019.9   32.44  5028.5   33.51  5227.3   34.48
  5250.5   33.01  5413.7   33.28  6012.1   27.59    6391   31.52  6484.8   34.43
  6534.7   37.76  6599.9   38.35  6629.6   40.68  6787.6   43.39    6824   43.81
  6860.3   40.58    6939   44.21  6948.3   45.92  6954.2   44.07  6990.6   46.78
#Mann= 4 ,-1 , 0
  4494.3     .05       0  4503.7     .08       0    4998     .05       0
  5019.9      .1       0
#XS Ineff= 2 , 0
       0                 5070.45       0   34.86
Permanent Ineff=
       F       T
Bank Sta=4984.4,5028.5
XS Rating Curve= 0 ,0
Exp/Cntr=0.3,0.1

Type RM Length L Ch R = 1 ,11875   ,402,402,402
BEGIN DESCRIPTION:
Mapping XS 5af5cd04
END DESCRIPTION:
XS GIS Cut Line= 3
      2369294.96     13146150.86      2370306.26       13145413.
      2371447.78     13144748.92
#Sta/Elev= 30
  4402.9   42.21  4421.5   42.44  4465.5   38.14  4501.1   37.58  4521.9   37.99
    4566   36.39  4572.1    36.7  4601.5   35.22  4622.4   35.56  4629.1    34.8
  4693.4   32.49  4823.2      31    4980   31.02  5009.3   30.65  5030.2   31.17
  5423.4   28.39    5618   29.83    5668    30.9    5749   27.78  5835.9   26.31
  6098.2   27.12  6119.5   25.17  6135.4   27.02  6151.2   27.44  6450.7   30.26
  6814.8    38.1  6859.6   37.48    6905   40.01    6948   40.75  6975.4   42.08
#Mann= 3 , 0 , 0
  4402.9     .16       0    4980     .16       0  5030.2     .16       0
#XS Ineff= 2 , 0
       0                 5038.07       0   31.41
Permanent Ineff=
       F       T
Bank Sta=4980,5030.2
XS Rating Curve= 0 ,0
Exp/Cntr=0.3,0.1

Type RM Length L Ch R = 1 ,11473   ,820,820,820
BEGIN DESCRIPTION:
UNT042 IN BACR 7.0
END DESCRIPTION:
XS GIS Cut Line= 3
      2368940.81     13146827.93      2371456.43     13145109.18
      2372112.66      13145057.1
#Sta/Elev= 30
  3702.9   63.47  3723.4   61.41  3751.4   60.88  3766.3    59.2  3953.5   48.86
  4002.6   47.39  4017.6   45.25  4074.6   41.34  4211.9   35.79  4226.9   33.79
  4406.3   30.94  4478.1   31.53  4744.3   28.35  4974.6   27.68  5010.5   27.64
  5384.3   24.69  5794.4   24.74  5823.6   23.69  5853.7   24.76    6105   24.57
  6284.4   25.99    6449   29.74  6694.2   33.04  6921.4   32.98  6941.5   32.03
  7152.2   37.27  7232.4    43.8  7262.5   44.39  7322.7   48.63  7407.9   49.43
#Mann= 3 , 0 , 0
  3702.9     .16       0  4974.6     .16       0  5010.5     .16       0
#XS Ineff= 2 , 0
       0                    5025       0   28.94
Permanent Ineff=
       F       T
Bank Sta=4974.6,5010.5
XS Rating Curve= 0 ,0
Exp/Cntr=0.3,0.1

Type RM Length L Ch R = 1 ,10653   ,645,645,645
XS GIS Cut Line= 3
     2369090.985    13146946.561     2370245.499     13146308.54
     2372628.311     13144902.29
#Sta/Elev= 30
    4000 58.5034 4069.54 55.3181 4168.89 48.6653  4198.7 48.0542 4248.37 43.4156
 4427.19 34.4238 4536.48 31.0398  4715.3  28.107    4914  27.846 4993.48 26.2156
 5760.74 23.0217 5840.67 23.2005 5880.64 22.2181 5950.59 23.6135 6360.25 25.4009
 6490.15 24.4739 6789.91 26.6966 6859.85 28.1968 7059.69 27.7057 7119.64 29.4701
 7269.52 29.9701 7359.44 32.8192 7439.38 37.0436 7509.32 41.9949 7589.26 45.9278
 7669.19 52.0865 7839.06  61.496 7948.97 63.2237 8018.91 61.2613 8098.85 60.7481
#Mann= 3 , 0 , 0
    4000     .16       0 5760.74     .16       0 5840.67     .16       0
#XS Ineff= 2 ,-1
 5840.95 6138.4824.36832 6380.69 6644.51   25.32
Permanent Ineff=
       T       T
Bank Sta=5760.74,5840.67
XS Rating Curve= 0 ,0
Exp/Cntr=0.3,0.1

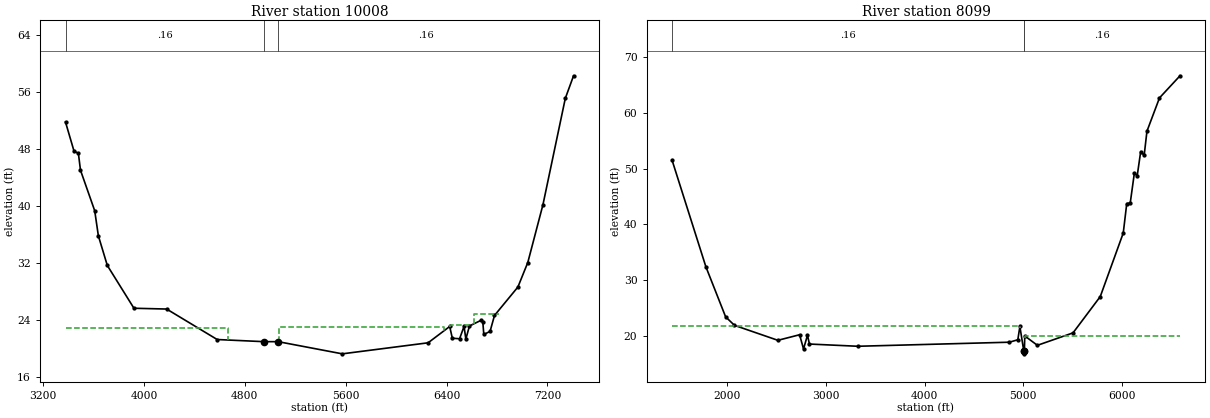
Type RM Length L Ch R = 1 ,10008   ,1909,1909,1909
BEGIN DESCRIPTION:
UNT042 IN BACR 6.0
END DESCRIPTION:
XS GIS Cut Line= 4
      2369180.35     13147027.59      2370360.95     13146840.08
      2371784.56     13146180.36      2372576.21     13145194.26
#Sta/Elev= 30
  3378.5   51.79  3446.7   47.67  3480.5   47.43  3497.3   45.03  3610.1   39.34
  3639.1   35.82    3710   31.66  3921.3   25.65  4180.4   25.54  4581.4   21.26
  4950.4   20.96    5065   20.96  5573.5   19.25  6254.1    20.8  6425.3   23.09
  6446.2   21.44  6503.7   21.37    6539    23.1  6553.4   21.33  6582.2   23.17
  6673.4   23.95  6687.8   23.76  6695.8   21.97  6745.4    22.4  6780.6   24.64
  6966.2   28.63  7044.6   32.07  7164.6   40.17  7342.2   55.12  7407.5   58.29
#Mann= 3 , 0 , 0
  3378.5     .16       0  4950.4     .16       0    5065     .16       0
#XS Ineff= 4 ,-1
 3378.49 4663.4422.88258  5068.9 6378.3522.98357 6425.72 6607.8223.27208
 6616.21 6816.0824.90724
Permanent Ineff=
       T       T       T       T
Bank Sta=4950.4,5065
XS Rating Curve= 0 ,0
Exp/Cntr=0.3,0.1

Type RM Length L Ch R = 1 ,8099    ,0,0,0
BEGIN DESCRIPTION:
UNT042 IN BACR 1.0
END DESCRIPTION:
XS GIS Cut Line= 5
      2368913.84     13147440.87      2370768.53     13147514.25
      2371882.69     13147073.93      2372803.37     13146013.14
      2373295.89     13145520.62
#Sta/Elev= 30
  1437.4    51.6  1781.6   32.39  1981.7    23.4  2071.8   21.87  2512.1   19.18
  2732.3   20.18  2772.3   17.63  2812.4   20.09  2832.4   18.51  3323.4   18.11
  4861.4   18.84  4946.9   19.28  4967.8   21.67  5007.5   17.25  5010.3   16.75
  5013.5   17.25  5017.3   19.97  5145.4   18.28  5507.2   20.52  5783.5   27.04
  6016.8   38.46  6052.2   43.75  6087.5   43.84    6130   49.29  6158.2   48.72
  6193.6   53.09    6229   52.42  6257.2   56.75  6384.5   62.74  6592.7   66.71
#Mann= 3 , 0 , 0
  1437.4     .16       0  5007.5     .16       0  5013.5     .16       0
#XS Ineff= 2 , 0
       0  4965.4   21.84 5016.74       0   20.01
Permanent Ineff=
       T       T
Bank Sta=5007.5,5013.5
XS Rating Curve= 0 ,0
Exp/Cntr=0.3,0.1

Chan Stop Cuts=-1
Use User Specified Reach Order=0
Composite Channel Slope=5