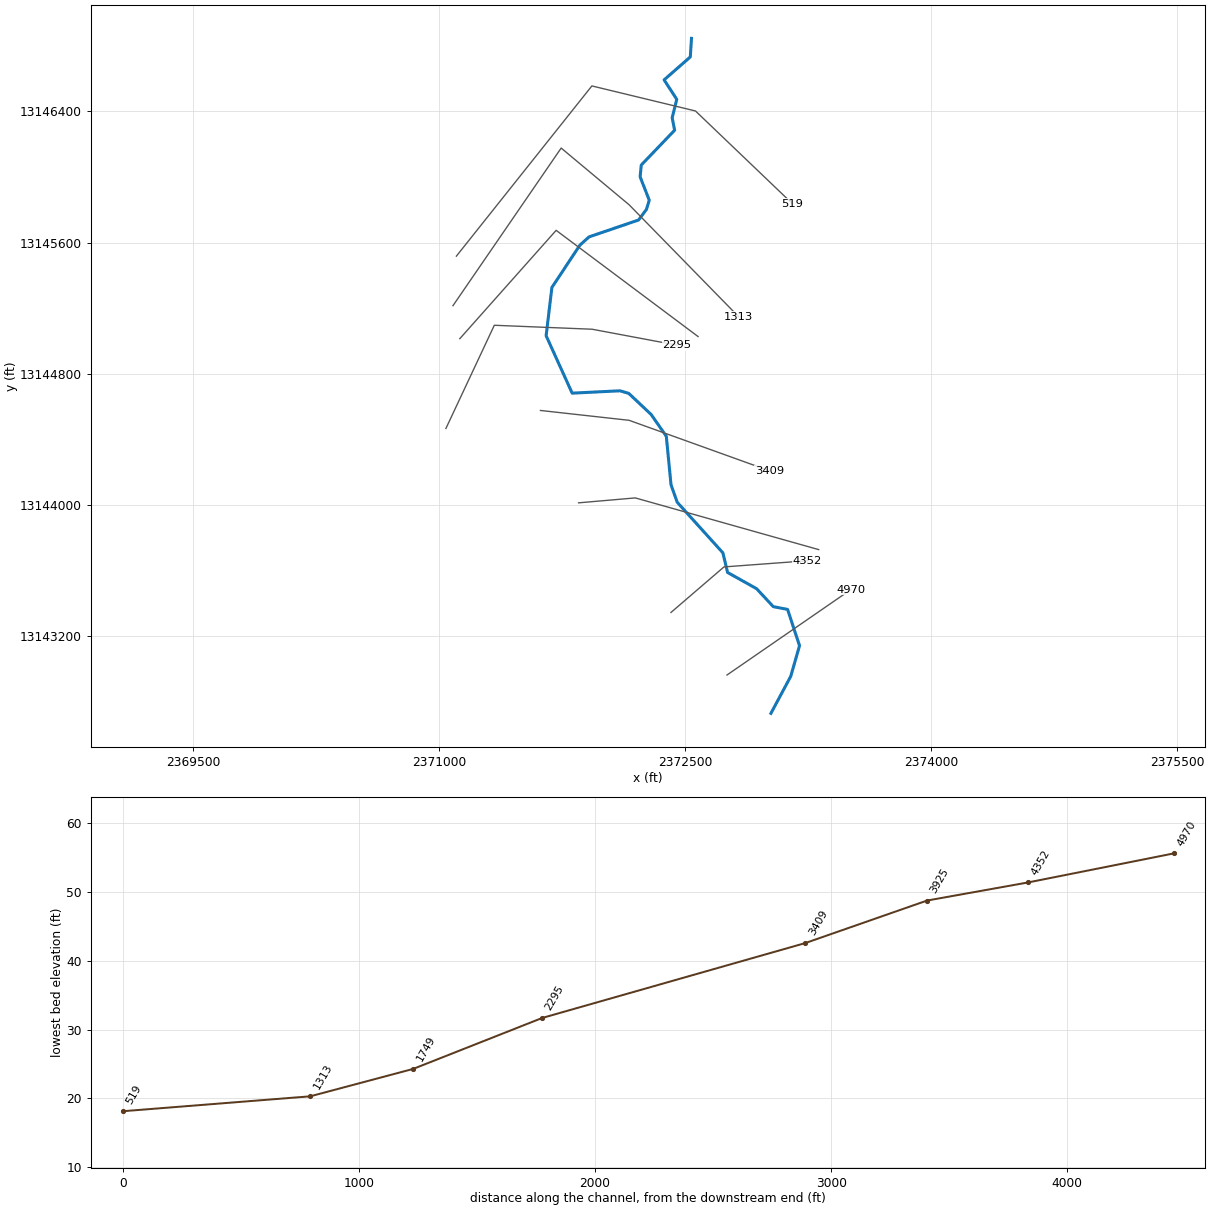
--- UNT0421 IN BACR.prj (project) ---

Proj Title=UNT0421 IN BACR Base Level Engineering
Current Plan=p01
Default Exp/Contr=0.3,0.1
English Units
Geom File=g01
Flow File=f01
Plan File=p01
Y Axis Title=Elevation
X Axis Title(PF)=Main Channel Distance
X Axis Title(XS)=Station
BEGIN DESCRIPTION:
UNT0421 IN BACR
END DESCRIPTION:
DSS Export Rating Curves= 0
DSS Export Rating Curve Sorted= 0
DSS Export Volume Flow Curves= 0
DXF OffsetX= 0
DXF OffsetY= 0
DXF ScaleX= 1
DXF ScaleY= 10

--- UNT0421 IN BACR.p01 (plan) ---

Plan Title=Multiple Run
Short Identifier=Multiple
Geom File=g01
Flow File=f01
Subcritical Flow
K Sum by GR= 0
Std Step Tol= 0.01
Critical Tol= 0.01
Num of Std Step Trials= 20
Max Error Tol= 0.3
Flow Tol Ratio= 0.001
Split Flow NTrial= 30
Split Flow Tol= 0.02
Split Flow Ratio= 0.02
Log Output Level= 0
Friction Slope Method= 1
Unsteady Friction Slope Method= 2
Unsteady Bridges Friction Slope Method= 1
Parabolic Critical Depth
Global Vel Dist=  1 , 1 , 1
Global Log Level= 0
CheckData=True
Encroach Param= -1, 0, 0, 0
BEGIN DESCRIPTION:
Multiple Run
END DESCRIPTION:

--- UNT0421 IN BACR.f01 (steady flow) ---

Flow Title=Multiple
Number of Profiles=7
Profile Names=10-year,25-year,50-year,1pct_min,100-year,1pct_plu,500-year
River Rch & RM= UNT0421 IN BACR,Reach-1,4970
     150     195     231     201     272     368     379
River Rch & RM= UNT0421 IN BACR,Reach-1,4352
     223     298     359     318     430     581     621
Boundary for River Rch & Prof#=UNT0421 IN BACR,Reach-1,1
Up Type=0
Dn Type=3
Dn Slope=0.005
Boundary for River Rch & Prof#=UNT0421 IN BACR,Reach-1,2
Up Type=0
Dn Type=3
Dn Slope=0.005
Boundary for River Rch & Prof#=UNT0421 IN BACR,Reach-1,3
Up Type=0
Dn Type=3
Dn Slope=0.005
Boundary for River Rch & Prof#=UNT0421 IN BACR,Reach-1,4
Up Type=0
Dn Type=3
Dn Slope=0.005
Boundary for River Rch & Prof#=UNT0421 IN BACR,Reach-1,5
Up Type=0
Dn Type=3
Dn Slope=0.005
Boundary for River Rch & Prof#=UNT0421 IN BACR,Reach-1,6
Up Type=0
Dn Type=3
Dn Slope=0.005
Boundary for River Rch & Prof#=UNT0421 IN BACR,Reach-1,7
Up Type=0
Dn Type=3
Dn Slope=0.005

--- UNT0421 IN BACR.g01 (geometry) ---

Geom Title=Existing Conditions
Program Version=4.10

River Reach=UNT0421 IN BACR ,Reach-1
Reach XY= 30
      2373022.25     13142728.43      2373143.34       13142955.
      2373196.73     13143141.19      2373123.81     13143362.55
      2373036.57     13143379.48      2372935.01     13143488.85
      2372757.93     13143587.81      2372729.28      13143707.6
      2372450.63     13144016.19      2372412.87     13144122.97
      2372384.23     13144418.54      2372291.78     13144551.35
      2372155.06     13144680.26      2372101.68     13144695.88
      2371810.01     13144681.56      2371651.16     13145031.82
      2371686.31     13145326.09      2371856.88      13145583.9
      2371912.87     13145634.68      2372214.96     13145737.55
      2372262.61     13145801.44      2372280.32     13145858.21
      2372224.59     13146000.92      2372231.36     13146072.79
      2372435.01     13146285.29      2372419.91     13146361.33
      2372447.94      13146473.7      2372370.72     13146592.32
      2372530.52     13146732.11      2372537.77     13146845.69

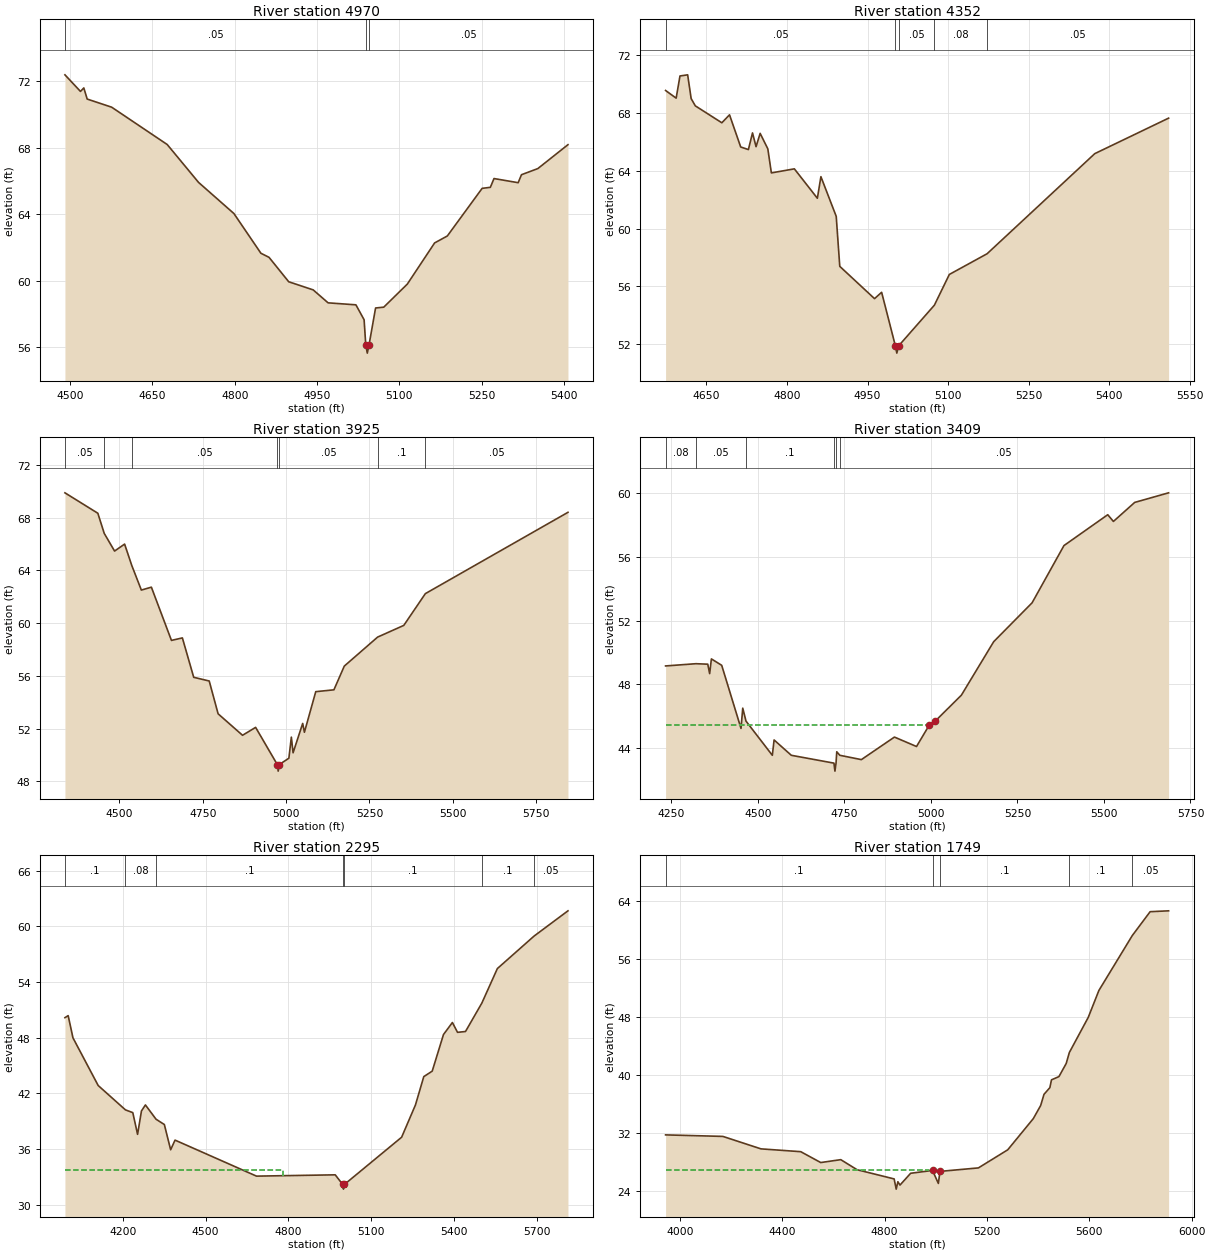
Type RM Length L Ch R = 1 ,4970    ,618,618,618
BEGIN DESCRIPTION:
UNT044 IN BACR 18.0
END DESCRIPTION:
XS GIS Cut Line= 2
      2372754.34     13142962.41      2373508.57     13143482.57
#Sta/Elev= 30
  4490.8    72.4  4519.1    71.4  4525.2   71.61  4531.3   70.94  4575.9   70.45
  4677.1    68.2  4734.1   65.92  4798.6   64.04  4847.7   61.65  4862.6    61.4
  4898.4   59.93    4943   59.44  4970.1   58.66  5020.8   58.54  5035.7   57.64
  5038.7   56.13  5041.5   55.63  5044.7   56.13  5056.6   58.35  5071.5    58.4
  5114.4   59.79  5164.1   62.27  5187.3   62.69  5250.7   65.56  5265.6   65.62
  5272.3   66.15  5316.3    65.9  5322.3   66.38  5352.1   66.75    5407   68.19
#Mann= 3 ,-1 , 0
  4490.8     .05       0  5038.7    .035       0  5044.7     .05       0
Bank Sta=5038.7,5044.7
XS Rating Curve= 0 ,0
Exp/Cntr=0.3,0.1

Type RM Length L Ch R = 1 ,4352    ,427,427,427
BEGIN DESCRIPTION:
UNT044 IN BACR 7.0
END DESCRIPTION:
XS GIS Cut Line= 3
      2372412.81     13143344.04      2372735.79     13143621.66
       2373244.7     13143659.37
#Sta/Elev= 30
  4574.1   69.53  4593.8      69  4600.9   70.53  4615.2   70.61  4621.7   68.97
  4629.4   68.47  4678.8    67.3  4693.1   67.85  4713.9   65.63  4728.2   65.45
  4735.9    66.6  4742.5   65.65  4750.1   66.57  4764.4    65.5    4771   63.84
  4813.8   64.12  4856.6   62.09  4863.2   63.58  4891.7   60.84  4898.3   57.39
    4963   55.16  4976.2    55.6  5001.8    51.9  5004.5    51.4  5007.8    51.9
  5074.4   54.71  5102.2   56.83  5172.5   58.26  5372.9   65.17  5510.3   67.62
#Mann= 5 ,-1 , 0
  4574.1     .05       0  5001.8    .035       0  5007.8     .05       0
  5074.4     .08       0  5172.5     .05       0
Bank Sta=5001.8,5007.8
XS Rating Curve= 0 ,0
Exp/Cntr=0.3,0.1

Type RM Length L Ch R = 1 ,3925    ,516,516,516
BEGIN DESCRIPTION:
UNT044 IN BACR 6.0
END DESCRIPTION:
XS GIS Cut Line= 3
       2371849.4     13144012.58      2372194.93     13144042.63
      2373313.51     13143727.32
#Sta/Elev= 30
  4336.4   69.89  4435.1   68.34  4454.3   66.81  4485.3   65.47  4515.4      66
  4536.7   64.39  4565.6   62.51  4595.7   62.73  4655.9   58.69  4688.7   58.88
  4722.7   55.89  4769.2   55.61  4795.9   53.12  4869.2   51.49  4908.4   52.09
  4973.4   49.27  4976.1   48.77  4979.4   49.27  5008.2   49.75  5015.6   51.35
  5020.8   50.16  5049.6   52.39  5054.8   51.72  5088.8    54.8  5143.3   54.94
  5174.4   56.74  5274.3   58.94  5352.9   59.83  5417.6   62.24  5845.4   68.41
#Mann= 7 ,-1 , 0
  4336.4     .05       0  4454.3      .1       0  4536.7     .05       0
  4973.4    .035       0  4979.4     .05       0  5274.3      .1       0
  5417.6     .05       0
Bank Sta=4973.4,4979.4
XS Rating Curve= 0 ,0
Exp/Cntr=0.3,0.1

Type RM Length L Ch R = 1 ,3409    ,1114,1114,1114
BEGIN DESCRIPTION:
Mapping XS ea9f77a6
END DESCRIPTION:
XS GIS Cut Line= 3
      2371616.55     13144575.98      2372157.37     13144515.89
      2373013.25     13144208.07
#Sta/Elev= 30
  4233.2   49.16  4320.8    49.3  4355.1   49.27  4360.6   48.68  4365.6    49.6
  4395.4    49.2  4451.2   45.25  4456.2   46.52  4465.6   45.71  4541.7   43.57
  4546.8   44.53  4596.6   43.57  4719.8   43.08  4722.6   42.58  4725.8   43.08
  4727.9   43.79  4736.8   43.57    4799    43.3  4894.6   44.71  4958.4   44.12
  4995.8   45.48  5011.5   45.69    5088   47.33  5181.5   50.68  5292.4   53.11
  5384.5   56.69    5511   58.62  5527.4    58.2  5588.9   59.39  5686.9   59.99
#Mann= 6 ,-1 , 0
  4233.2     .08       0  4320.8     .05       0  4465.6      .1       0
  4719.8    .035       0  4725.8      .1       0  4736.8     .05       0
#XS Ineff= 2 , 0
       0 4995.61   45.48               0
Permanent Ineff=
       T       F
Bank Sta=4995.8,5011.5
XS Rating Curve= 0 ,0
Exp/Cntr=0.3,0.1

Type RM Length L Ch R = 1 ,2295    ,546,546,546
BEGIN DESCRIPTION:
UNT044 IN BACR 5.0
END DESCRIPTION:
XS GIS Cut Line= 4
      2371040.07     13144466.29       2371335.2     13145095.61
      2371931.55     13145071.47      2372450.36     13144974.11
#Sta/Elev= 30
  3991.3   50.15    4003   50.37  4020.3   47.98  4111.6   42.84  4210.1   40.22
  4236.8   39.92  4254.1   37.58  4268.1    40.1  4282.4   40.75  4320.9   39.21
  4350.9   38.64  4373.7   35.92  4389.6   36.96  4684.3   33.08  4969.1   33.22
  4996.2   32.18  4998.9   31.68  5002.2   32.18  5209.3   37.27  5259.4   40.75
  5289.5    43.8    5320   44.39  5360.7   48.33    5393   49.63  5411.6   48.57
  5440.4   48.66  5499.7   51.73  5555.7   55.44  5688.5   58.94  5811.1   61.66
#Mann= 7 ,-1 , 0
  3991.3      .1       0  4210.1     .08       0  4320.9      .1       0
  4996.2     .03       0  5002.2      .1       0  5499.7      .1       0
  5688.5     .05       0
#XS Ineff= 2 , 0
       0 4781.18    33.7               0
Permanent Ineff=
       T       F
Bank Sta=4996.2,5002.2
XS Rating Curve= 0 ,0
Exp/Cntr=0.3,0.1

Type RM Length L Ch R = 1 ,1749    ,436,436,436
BEGIN DESCRIPTION:
UNT044 IN BACR 4.0
END DESCRIPTION:
XS GIS Cut Line= 3
      2371124.69     13145013.74      2371712.34     13145674.59
      2372578.02     13145026.72
#Sta/Elev= 30
  3944.3   31.76  4168.2   31.55    4317   29.83  4472.5   29.44  4550.6   27.94
  4628.9   28.34  4692.5   26.95  4837.4   25.68  4845.5   24.27    4852   25.29
  4860.3   24.83    4902   26.46  4987.4   26.85  5010.2   25.06  5016.6   26.72
  5166.7    27.2  5281.3    29.7  5381.3   34.01  5409.9   35.81    5423   37.36
  5445.9   38.28  5452.2   39.36  5481.4   39.81  5509.8   41.62  5522.1   43.14
    5596   47.99  5637.6   51.71  5767.9   59.28  5837.7   62.58  5909.9    62.7
#Mann= 5 ,-1 , 0
  3944.3      .1       0  4987.4     .03       0  5016.6      .1       0
  5522.1      .1       0  5767.9     .05       0
#XS Ineff= 2 , 0
       0 4972.88    26.9               0
Permanent Ineff=
       T       F
Bank Sta=4987.4,5016.6
XS Rating Curve= 0 ,0
Exp/Cntr=0.3,0.1

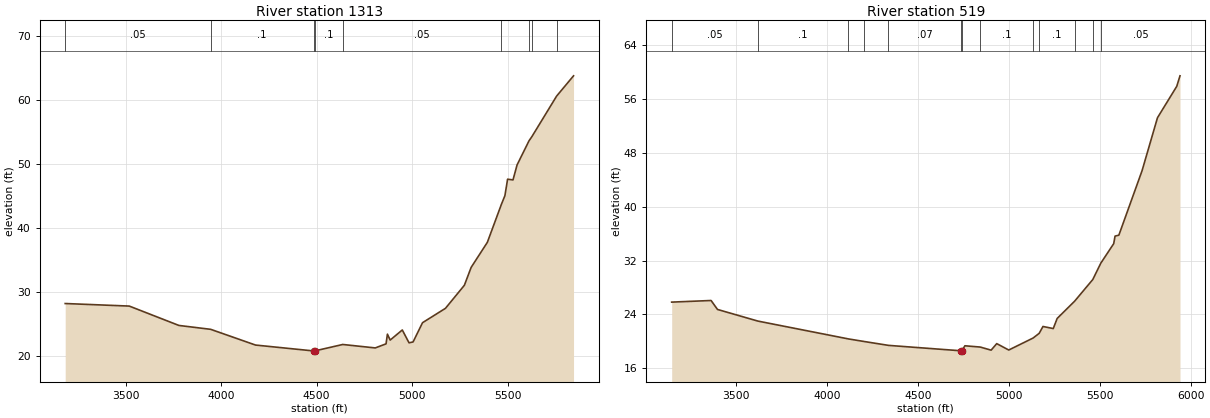
Type RM Length L Ch R = 1 ,1313    ,794,794,794
BEGIN DESCRIPTION:
UNT044 IN BACR 3.0
END DESCRIPTION:
XS GIS Cut Line= 4
        2371083.      13145215.1      2371742.93     13146176.43
      2372157.37     13145830.49      2372825.96     13145146.88
#Sta/Elev= 30
  3183.3    28.2  3518.8    27.8  3778.6   24.77  3945.3   24.16    4180    21.7
  4483.8   20.78  4486.6   20.28  4489.8   20.78  4636.8   21.79    4807   21.25
  4863.6   21.89  4870.8   23.41  4885.1   22.48  4948.6   24.06  4983.9   22.05
  5005.2   22.19  5054.6    25.2  5174.8   27.45  5273.8   31.06  5309.3   33.86
  5394.1   37.78  5467.8   43.74    5486   45.08  5500.1   47.66  5528.4   47.55
  5549.7   49.89  5612.3   53.67  5627.5   54.33  5756.9   60.67  5845.4   63.84
#Mann= 9 ,-1 , 0
  3183.3     .05       0  3945.3      .1       0  4483.8     .03       0
  4489.8      .1       0  4636.8     .05       0  5467.8      .1       0
  5612.3     .05       0  5627.5      .1       0  5756.9     .05       0
Bank Sta=4483.8,4489.8
XS Rating Curve= 0 ,0
Exp/Cntr=0.3,0.1

Type RM Length L Ch R = 1 ,519     ,0,0,0
BEGIN DESCRIPTION:
UNT044 IN BACR 1.0
END DESCRIPTION:
XS GIS Cut Line= 4
      2371103.87     13145517.24      2371930.23      13146555.4
      2372562.18     13146402.62      2373153.12     13145837.22
#Sta/Elev= 30
    3145   25.84  3361.7   26.08  3396.9   24.75  3619.1   23.02  4116.8   20.37
  4204.7   19.98  4337.1   19.41  4733.8   18.61  4736.5   18.11  4739.8   18.61
  4757.4   19.35  4841.7   19.16  4901.4    18.7  4932.3   19.67  4998.4   18.72
  5132.1    20.5  5165.8    21.2  5186.5   22.22  5243.1   21.91  5264.5   23.41
  5360.3   25.97  5460.5    29.2  5504.5   31.63  5575.5   34.53  5582.8   35.65
  5603.8   35.79  5731.2   45.36  5816.1   53.24  5922.1   57.91  5939.9   59.47
#Mann= 13 ,-1 , 0
    3145     .05       0  3619.1      .1       0  4116.8     .07       0
  4204.7      .1       0  4337.1     .07       0  4733.8     .07       0
  4739.8     .07       0  4841.7      .1       0  5132.1     .05       0
  5165.8      .1       0  5360.3     .05       0  5460.5      .1       0
  5504.5     .05       0
Bank Sta=4733.8,4739.8
XS Rating Curve= 0 ,0
Exp/Cntr=0.3,0.1

Chan Stop Cuts=-1
Use User Specified Reach Order=0
Composite Channel Slope=5