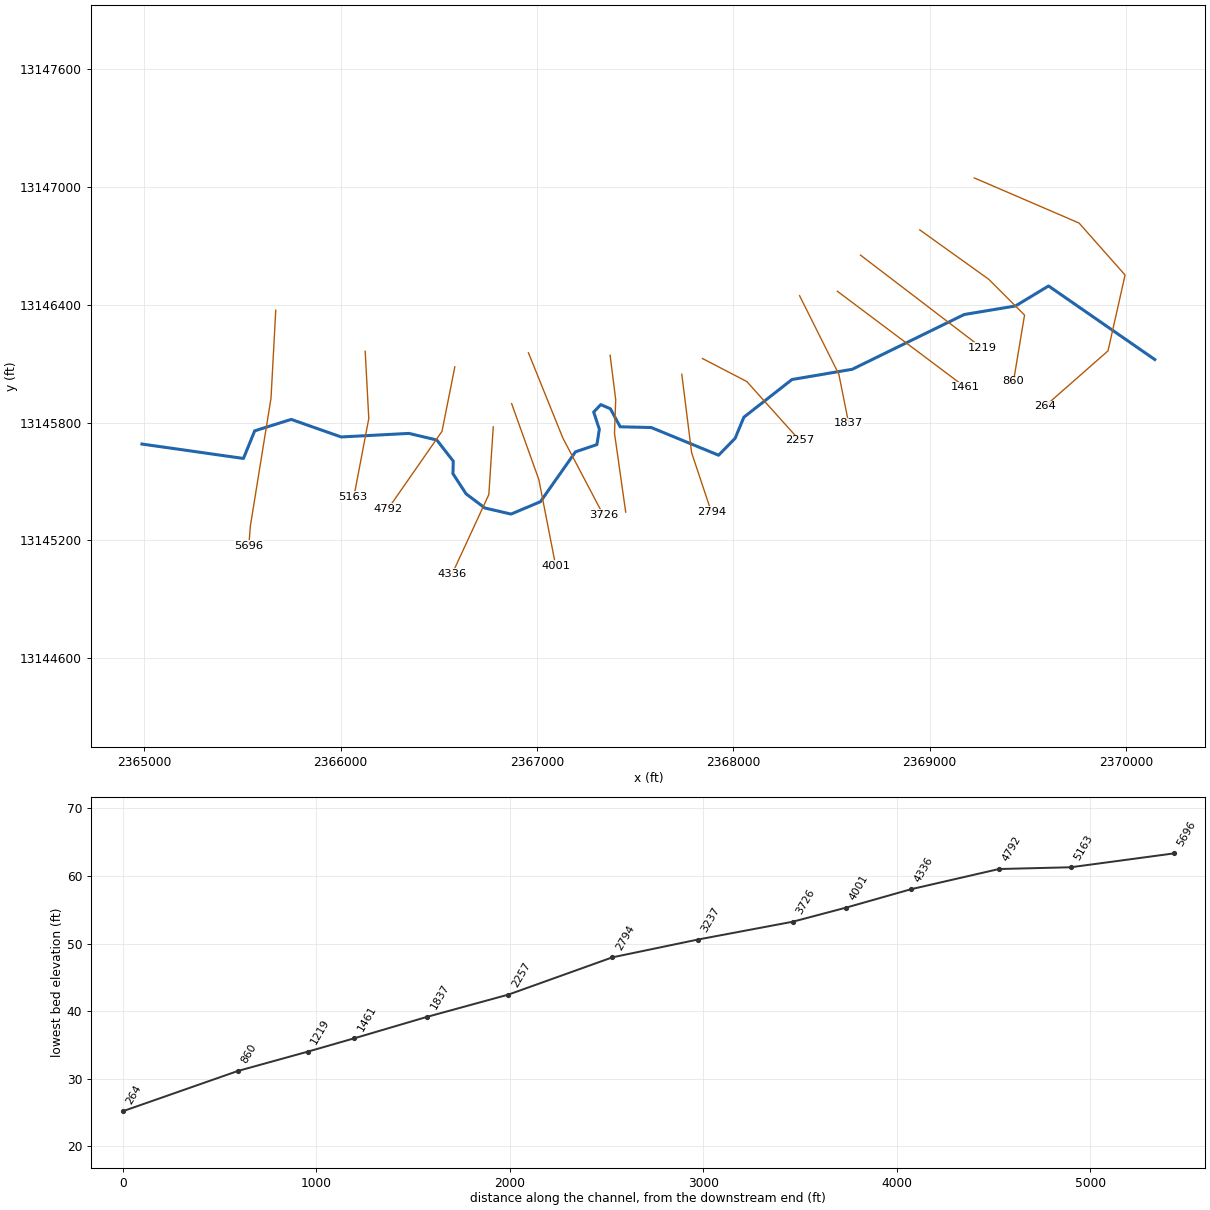
--- UNT043 IN BACR.prj (project) ---

Proj Title=UNT043 IN BACR Base Level Engineering
Current Plan=p01
Default Exp/Contr=0.3,0.1
English Units
Geom File=g01
Flow File=f01
Plan File=p01
Y Axis Title=Elevation
X Axis Title(PF)=Main Channel Distance
X Axis Title(XS)=Station
BEGIN DESCRIPTION:
UNT043 IN BACR
END DESCRIPTION:
DSS Export Rating Curves= 0
DSS Export Rating Curve Sorted= 0
DSS Export Volume Flow Curves= 0
DXF OffsetX= 0
DXF OffsetY= 0
DXF ScaleX= 1
DXF ScaleY= 10

--- UNT043 IN BACR.p01 (plan) ---

Plan Title=Multiple Run
Short Identifier=Multiple
Geom File=g01
Flow File=f01
Subcritical Flow
K Sum by GR= 0
Std Step Tol= 0.01
Critical Tol= 0.01
Num of Std Step Trials= 20
Max Error Tol= 0.3
Flow Tol Ratio= 0.001
Split Flow NTrial= 30
Split Flow Tol= 0.02
Split Flow Ratio= 0.02
Log Output Level= 0
Friction Slope Method= 1
Unsteady Friction Slope Method= 2
Unsteady Bridges Friction Slope Method= 1
Parabolic Critical Depth
Global Vel Dist=  1 , 1 , 1
Global Log Level= 0
CheckData=True
Encroach Param= -1, 0, 0, 0
BEGIN DESCRIPTION:
Multiple Run
END DESCRIPTION:

--- UNT043 IN BACR.f01 (steady flow) ---

Flow Title=Multiple
Program Version=4.10
Number of Profiles= 7
Profile Names=10-year,25-year,50-year,1pct_min,100-year,1pct_plu,500-year
River Rch & RM=UNT043 IN BACR,Reach-1         ,5696
     168     215     250     214     289     390     388
River Rch & RM=UNT043 IN BACR,Reach-1         ,5163
     287     385     463     409     553     748     795
Boundary for River Rch & Prof#=UNT043 IN BACR,Reach-1         , 1
Up Type= 0
Dn Type= 3
Dn Slope=0.005
Boundary for River Rch & Prof#=UNT043 IN BACR,Reach-1         , 2
Up Type= 0
Dn Type= 3
Dn Slope=0.005
Boundary for River Rch & Prof#=UNT043 IN BACR,Reach-1         , 3
Up Type= 0
Dn Type= 3
Dn Slope=0.005
Boundary for River Rch & Prof#=UNT043 IN BACR,Reach-1         , 4
Up Type= 0
Dn Type= 3
Dn Slope=0.005
Boundary for River Rch & Prof#=UNT043 IN BACR,Reach-1         , 5
Up Type= 0
Dn Type= 3
Dn Slope=0.005
Boundary for River Rch & Prof#=UNT043 IN BACR,Reach-1         , 6
Up Type= 0
Dn Type= 3
Dn Slope=0.005
Boundary for River Rch & Prof#=UNT043 IN BACR,Reach-1         , 7
Up Type= 0
Dn Type= 3
Dn Slope=0.005
DSS Import GetInterval= 0
DSS Import GetPeak= 0
DSS Import FillOption= 0

--- UNT043 IN BACR.g01 (geometry) ---

Geom Title=Existing Conditions
Program Version=4.10

River Reach=UNT043 IN BACR  ,Reach-1
Reach XY= 30
      2364987.42     13145691.17      2365504.56      13145617.9
      2365561.85     13145758.53      2365747.94     13145816.74
      2366002.32     13145727.38      2366347.48     13145745.44
      2366489.57     13145711.74      2366573.33     13145604.25
      2366571.83     13145540.25      2366638.65     13145437.65
      2366734.48     13145365.37      2366867.88     13145334.45
      2367017.55     13145397.59       2367196.1     13145651.69
      2367305.18     13145688.32      2367317.66     13145766.55
      2367288.74     13145854.19      2367324.82     13145892.11
      2367374.03     13145870.83      2367423.75     13145779.15
      2367582.02      13145775.4      2367925.15      13145634.4
       2368009.5      13145720.8       2368053.8      13145827.9
      2368299.01     13146019.99      2368605.95     13146072.07
      2369176.15     13146351.01      2369437.32      13146394.5
      2369606.04     13146496.56      2370147.13     13146121.87

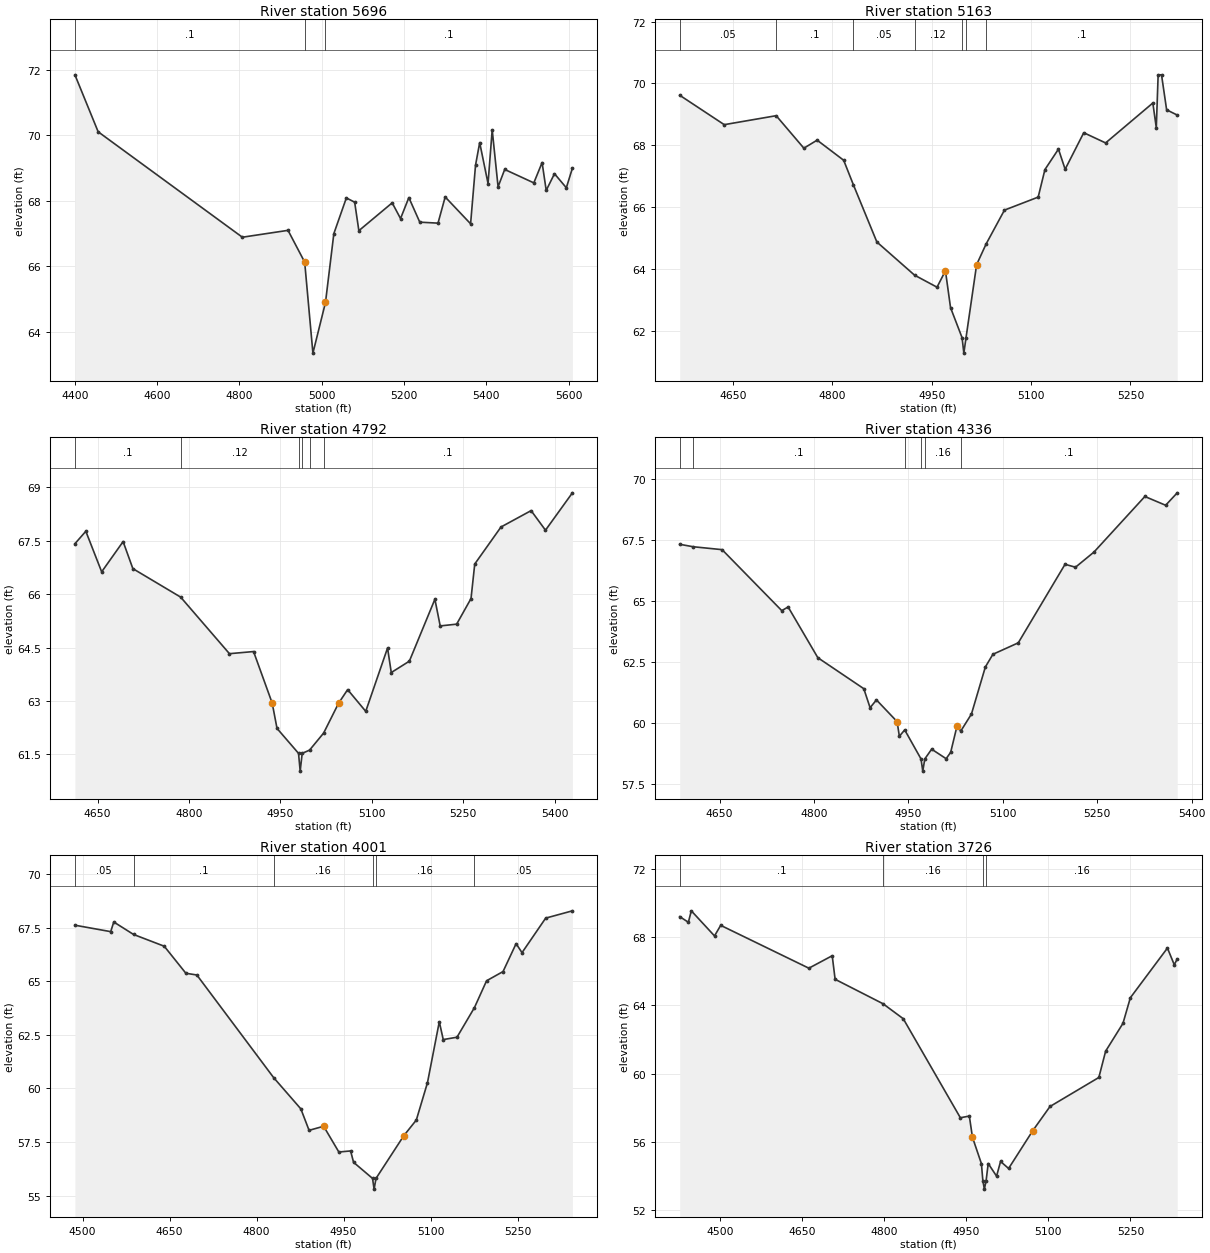
Type RM Length L Ch R = 1 ,5696    ,533,533,533
BEGIN DESCRIPTION:
UNT043 IN BACR 11.0
END DESCRIPTION:
XS GIS Cut Line= 4
       2365669.2     13146373.27      2365644.96     13145924.82
      2365539.92     13145274.41      2365531.84     13145173.38
#Sta/Elev= 30
  4400.2   71.84  4456.7    70.1  4807.2   66.88  4918.2   67.09  4958.7   66.12
  4978.7   63.34  5009.3   64.89  5029.6   66.99    5060   68.08  5080.2   67.95
  5090.4   67.08  5171.4   67.93  5191.7   67.45  5211.9   68.09  5238.5   67.34
  5282.8   67.31  5300.2   68.11    5362   67.29    5374   69.08  5384.1   69.77
  5404.4   68.52  5414.5   70.16  5428.8   68.42  5444.9   68.95  5515.7   68.54
  5535.8   69.16  5545.8   68.31  5565.9   68.82  5594.7   68.39  5609.5   68.99
#Mann= 3 , 0 , 0
  4400.2      .1       0  4958.7     .07       0  5009.3      .1       0
Bank Sta=4958.7,5009.3
XS Rating Curve= 0 ,0
Exp/Cntr=0.3,0.1

Type RM Length L Ch R = 1 ,5163    ,371,371,371
BEGIN DESCRIPTION:
UNT043 IN BACR 10.0
END DESCRIPTION:
XS GIS Cut Line= 4
      2366124.73       13146164.      2366143.08     13145821.47
      2366071.73     13145446.35      2366062.71     13145421.82
#Sta/Elev= 30
  4569.7   69.62  4636.9   68.67  4715.3   68.96  4757.1   67.91  4777.1   68.17
  4817.2   67.52  4831.8   66.73  4867.3   64.88  4924.1   63.81  4958.1   63.42
  4970.8   63.95  4978.5   62.76  4995.9   61.79  4998.6   61.29  5001.9   61.79
  5017.9   64.15  5032.3   64.82  5059.9   65.91  5110.8   66.33    5121   67.22
  5141.4   67.88  5151.5   67.23  5179.6   68.41  5212.6   68.08  5283.9   69.37
  5289.1   68.57  5291.9   70.28    5297   70.28  5304.7   69.15  5320.7   68.98
#Mann= 7 ,-1 , 0
  4569.7     .05       0  4715.3      .1       0  4831.8     .05       0
  4924.1     .12       0  4995.9     .07       0  5001.9     .12       0
  5032.3      .1       0
Bank Sta=4970.8,5017.9
XS Rating Curve= 0 ,0
Exp/Cntr=0.3,0.1

Type RM Length L Ch R = 1 ,4792    ,456,456,456
BEGIN DESCRIPTION:
UNT043 IN BACR 9.0
END DESCRIPTION:
XS GIS Cut Line= 3
      2366581.39     13146084.42      2366516.16     13145756.23
      2366240.91     13145360.69
#Sta/Elev= 30
  4612.8   67.42  4630.7   67.77  4656.7   66.63  4691.9   67.48  4707.9   66.72
  4786.3   65.92  4866.4   64.33    4906   64.39  4936.6   62.94  4944.5   62.23
  4979.8   61.53  4982.5   61.03  4985.8   61.53  4997.9   61.62    5021    62.1
  5045.6   62.94  5060.4   63.32  5090.1   62.71  5125.9   64.49    5132    63.8
  5161.7   64.12  5203.6   65.86  5212.3   65.11  5239.3   65.16  5262.9   65.88
    5269   66.85  5312.1   67.89  5361.5   68.35  5385.1    67.8  5429.3   68.85
#Mann= 6 ,-1 , 0
  4612.8      .1       0  4786.3     .12       0  4979.8     .07       0
  4985.8     .12       0  4997.9     .16       0    5021      .1       0
Bank Sta=4936.6,5045.6
XS Rating Curve= 0 ,0
Exp/Cntr=0.3,0.1

Type RM Length L Ch R = 1 ,4336    ,335,335,335
BEGIN DESCRIPTION:
UNT043 IN BACR 8.0
END DESCRIPTION:
XS GIS Cut Line= 3
      2366777.12     13145778.66      2366754.69     13145434.12
      2366567.94     13145030.17
#Sta/Elev= 30
  4586.8   67.33    4608   67.23  4654.1   67.11  4748.9   64.61    4759   64.76
  4806.2   62.68  4879.2   61.41  4889.2   60.63  4899.3   60.95  4932.1   60.06
  4935.7   59.46  4944.2   59.72  4970.1   58.53  4972.9   58.03  4976.1   58.53
    4987   58.93    5010   58.54  5017.2    58.8  5027.4   59.89  5033.2   59.67
  5050.2   60.37  5072.3    62.3  5084.3   62.82  5124.6   63.29  5198.9   66.51
  5215.5   66.39  5244.8   67.01  5325.7   69.29  5358.7   68.93  5377.1   69.44
#Mann= 6 ,-1 , 0
  4586.8     .05       0    4608      .1       0  4944.2     .16       0
  4970.1     .07       0  4976.1     .16       0  5033.2      .1       0
Bank Sta=4932.1,5027.4
XS Rating Curve= 0 ,0
Exp/Cntr=0.3,0.1

Type RM Length L Ch R = 1 ,4001    ,275,275,275
BEGIN DESCRIPTION:
Mapping XS 4a0563a0
END DESCRIPTION:
XS GIS Cut Line= 3
      2366870.88     13145896.94      2367009.53     13145509.55
      2367095.08     13145071.58
#Sta/Elev= 30
  4486.8   67.61  4548.5   67.31  4553.8   67.76  4587.8   67.18  4640.8   66.63
  4678.1   65.37    4697   65.29  4829.3   60.51  4876.3   59.05  4890.5   58.05
  4915.6   58.24  4941.8   57.04  4962.1   57.09  4967.2   56.56  4999.9   55.81
  5002.6   55.31  5005.9   55.81  5053.8    57.8  5075.4   58.53  5094.6   60.27
    5115   63.11  5121.8   62.28  5145.5   62.39  5175.6   63.77  5196.5   65.02
  5224.9   65.45  5247.4   66.75  5257.6   66.33  5298.4   67.94  5344.5   68.28
#Mann= 6 ,-1 , 0
  4486.8     .05       0  4587.8      .1       0  4829.3     .16       0
  4999.9     .07       0  5005.9     .16       0  5175.6     .05       0
Bank Sta=4915.6,5053.8
XS Rating Curve= 0 ,0
Exp/Cntr=0.3,0.1

Type RM Length L Ch R = 1 ,3726    ,489,489,489
BEGIN DESCRIPTION:
UNT043 IN BACR 7.0
END DESCRIPTION:
XS GIS Cut Line= 3
      2366956.53      13146155.8      2367131.85     13145721.57
      2367337.31       13145331.
#Sta/Elev= 30
  4425.9   69.19  4441.7   68.86  4447.1   69.53  4489.5   68.06  4500.8   68.68
    4662   66.17  4704.7    66.9    4710   65.52  4797.5   64.09  4834.6   63.21
    4939   57.41  4955.4   57.51  4961.1   56.27  4977.5   54.72  4980.1   53.73
  4982.9   53.23  4986.1   53.73  4989.9   54.73  5005.2   53.99  5012.5   54.85
  5027.2   54.44  5071.3   56.65  5102.9   58.07  5192.2   59.77  5204.6   61.31
  5236.3   62.94  5249.8   64.44  5317.6   67.35  5330.1   66.37  5335.5   66.71
#Mann= 4 ,-1 , 0
  4425.9      .1       0  4797.5     .16       0  4980.1     .07       0
  4986.1     .16       0
Bank Sta=4961.1,5071.3
XS Rating Curve= 0 ,0
Exp/Cntr=0.3,0.1

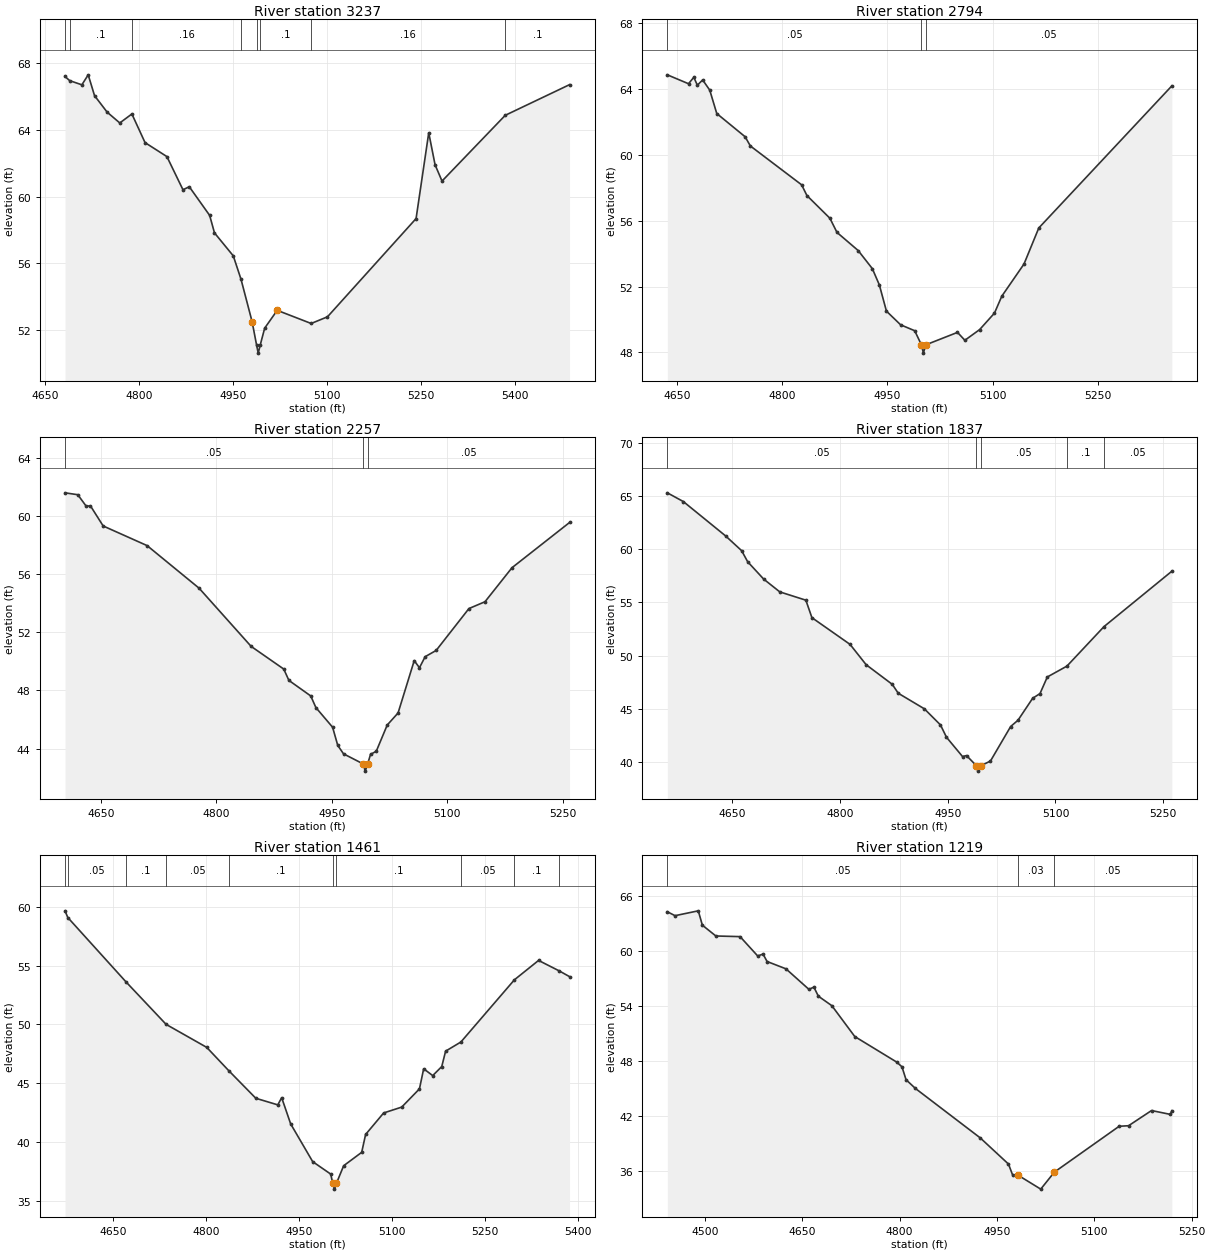
Type RM Length L Ch R = 1 ,3237    ,443,443,443
BEGIN DESCRIPTION:
UNT043 IN BACR 6.0
END DESCRIPTION:
XS GIS Cut Line= 4
      2367372.41     13146143.57      2367400.95     13145917.29
      2367394.84     13145746.04      2367451.92     13145344.41
#Sta/Elev= 30
  4682.2   67.21  4689.7   66.96  4709.1   66.71  4719.2   67.31  4729.3   66.06
  4749.4   65.07  4769.6   64.42  4788.9   64.96  4809.9   63.24  4844.8    62.4
  4870.4   60.41  4880.5   60.59    4913   58.87  4920.7   57.82  4950.7   56.44
    4963   55.04  4980.8   52.48  4987.8    51.1  4990.5    50.6  4993.8    51.1
  5000.8    52.1  5020.8   53.17    5075   52.38    5101   52.78  5242.4   58.68
  5262.6   63.83  5272.7   61.91  5283.8   60.93  5384.7   64.88  5487.3   66.72
#Mann= 8 ,-1 , 0
  4682.2     .05       0  4689.7      .1       0  4788.9     .16       0
    4963      .1       0  4987.8     .07       0  4993.8      .1       0
    5075     .16       0  5384.7      .1       0
Bank Sta=4980.8,5020.8
XS Rating Curve= 0 ,0
Exp/Cntr=0.3,0.1

Type RM Length L Ch R = 1 ,2794    ,537,537,537
BEGIN DESCRIPTION:
UNT043 IN BACR 5.0
END DESCRIPTION:
XS GIS Cut Line= 3
      2367737.72     13146046.86      2367787.72     13145646.85
      2367887.71      13145346.9
#Sta/Elev= 30
  4636.3   64.86  4666.5   64.32  4674.1   64.71  4679.1   64.23  4686.7   64.55
  4696.8   63.93  4706.8   62.51  4747.2    61.1  4754.7   60.54  4827.8   58.18
  4835.3   57.53  4868.1   56.15  4878.2   55.29  4908.4   54.19  4928.6   53.09
  4938.6    52.1  4948.7   50.51  4968.9   49.68    4989   49.32  4998.6   48.46
  5001.4   47.96  5004.6   48.46    5050   49.22  5060.5   48.74  5081.6   49.39
  5102.7   50.39  5113.2   51.42  5144.8   53.37  5165.9   55.56  5355.6   64.19
#Mann= 3 ,-1 , 0
  4636.3     .05       0  4998.6     .04       0  5004.6     .05       0
Bank Sta=4998.6,5004.6
XS Rating Curve= 0 ,0
Exp/Cntr=0.3,0.1

Type RM Length L Ch R = 1 ,2257    ,420,420,420
BEGIN DESCRIPTION:
UNT043 IN BACR 4.0
END DESCRIPTION:
XS GIS Cut Line= 3
      2367843.03     13146126.92      2368068.73     13146009.73
      2368337.08     13145711.09
#Sta/Elev= 30
  4603.2   61.59  4619.8   61.46  4630.6   60.68  4636.3   60.69  4652.8   59.31
  4709.9   57.96  4777.5   55.03  4845.1   51.03  4887.5   49.47  4894.2   48.69
  4922.6   47.62  4929.3   46.82    4951   45.47  4957.7   44.22  4965.2   43.64
  4990.6   42.95  4993.4   42.45  4996.6   42.95  5000.3    43.6  5007.8   43.82
    5022   45.62  5036.1   46.45  5057.1   50.05  5063.9   49.56  5071.3   50.32
  5085.6   50.75  5128.2   53.63  5149.1    54.1  5184.2   56.44    5259   59.55
#Mann= 3 ,-1 , 0
  4603.2     .05       0  4990.6     .03       0  4996.6     .05       0
Bank Sta=4990.6,4996.6
XS Rating Curve= 0 ,0
Exp/Cntr=0.3,0.1

Type RM Length L Ch R = 1 ,1837    ,376,376,376
BEGIN DESCRIPTION:
UNT043 IN BACR 3.0
END DESCRIPTION:
XS GIS Cut Line= 3
      2368337.74     13146446.82      2368537.72     13146046.85
      2368587.71     13145796.88
#Sta/Elev= 30
  4559.9   65.29  4582.2   64.47  4640.9   61.25  4663.3   59.86  4671.7   58.82
    4694   57.19  4716.4   55.99  4752.7   55.21  4761.1   53.57  4814.2   51.06
  4836.6   49.15  4872.9   47.31  4881.3   46.47  4917.6   45.01    4940    43.5
  4948.4   42.34  4970.7   40.53  4976.3   40.62  4990.1   39.66  4992.9   39.16
  4996.1   39.66  5009.6   40.11  5037.7   43.35  5047.9   43.94  5068.3      46
  5078.5   46.44  5088.7      48    5116   49.02  5167.6   52.73    5262   57.93
#Mann= 5 ,-1 , 0
  4559.9     .05       0  4990.1     .03       0  4996.1     .05       0
    5116      .1       0  5167.6     .05       0
Bank Sta=4990.1,4996.1
XS Rating Curve= 0 ,0
Exp/Cntr=0.3,0.1

Type RM Length L Ch R = 1 ,1461    ,242,242,242
BEGIN DESCRIPTION:
UNT043 IN BACR 2.0
END DESCRIPTION:
XS GIS Cut Line= 2
      2368530.24     13146469.45      2369181.52     13145980.99
#Sta/Elev= 30
  4571.8   59.67  4576.3    59.1  4670.1   53.63  4734.9   50.01  4800.5   48.05
  4835.8   46.08  4879.7   43.72  4915.1   43.16  4921.4   43.77  4935.9   41.54
  4971.4   38.33  5000.5   37.27  5003.8   36.49  5006.5   35.99  5009.8   36.49
  5021.4   37.98  5050.5   39.12  5056.8   40.64  5085.9   42.47  5115.1   42.97
  5143.7   44.52  5150.5   46.23  5165.1   45.65  5179.7   46.42  5185.9   47.73
  5210.6   48.51  5296.9    53.8  5335.9   55.45  5369.2   54.56  5385.9   54.07
#Mann= 10 ,-1 , 0
  4571.8     .08       0  4576.3     .05       0  4670.1      .1       0
  4734.9     .05       0  4835.8      .1       0  5003.8     .07       0
  5009.8      .1       0  5210.6     .05       0  5296.9      .1       0
  5369.2     .05       0
Bank Sta=5003.8,5009.8
XS Rating Curve= 0 ,0
Exp/Cntr=0.3,0.1

Type RM Length L Ch R = 1 ,1219    ,359,359,359
BEGIN DESCRIPTION:
Mapping XS 8c3cca76
END DESCRIPTION:
XS GIS Cut Line= 2
       2368648.3     13146653.47      2369265.95     13146181.56
#Sta/Elev= 30
  4442.1   64.32    4454   63.89  4489.8   64.42  4496.1   62.85  4516.9   61.67
  4554.2    61.6  4581.3   59.49  4589.6   59.69  4595.8   58.88  4624.9   58.08
  4660.2   55.84  4667.9   56.08  4674.8   55.09  4695.6   54.05  4730.9   50.68
  4795.4   47.89  4803.6   47.37  4809.9   45.96  4824.4      45  4924.2    39.6
  4967.7   36.74    4974   35.56  4982.3   35.53  5017.4      34  5038.4   35.86
  5138.2   40.87  5152.7   40.93  5188.1   42.59  5217.1   42.17  5219.4   42.57
#Mann= 3 , 0 , 0
  4442.1     .05       0  4982.3     .03       0  5038.4     .05       0
Bank Sta=4982.3,5038.4
XS Rating Curve= 0 ,0
Exp/Cntr=0.3,0.1

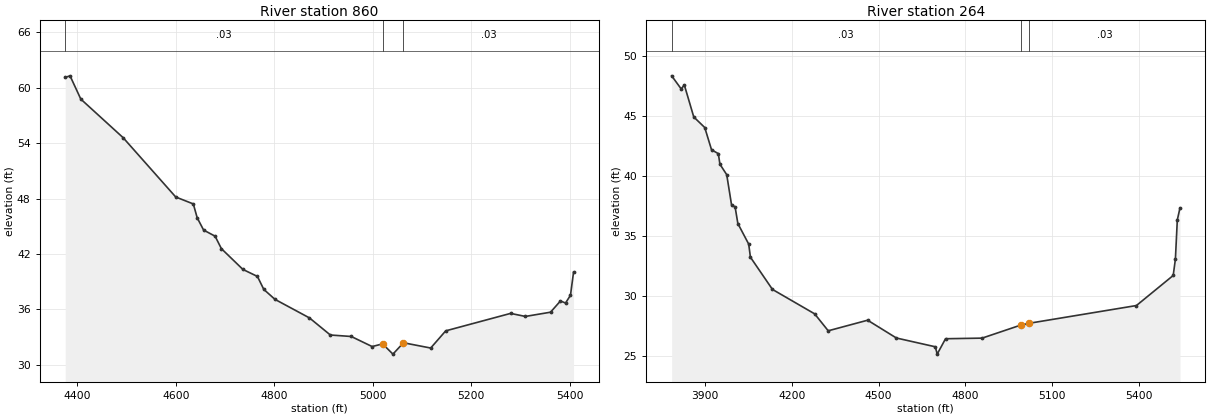
Type RM Length L Ch R = 1 ,860     ,596,596,596
BEGIN DESCRIPTION:
Mapping XS dad81c44
END DESCRIPTION:
XS GIS Cut Line= 4
      2368949.79     13146782.32      2369301.37     13146530.57
      2369483.66     13146348.28       2369427.4     13146010.75
#Sta/Elev= 30
  4375.2   61.12    4385   61.29  4406.9   58.77  4492.9   54.59  4599.7   48.17
  4635.4   47.42  4643.2   45.93  4656.3   44.59  4679.6   43.93  4692.4   42.58
  4736.1   40.33  4765.6   39.57  4778.5   38.17  4801.2   37.09  4871.3   35.08
  4913.7   33.23  4956.2   33.07  4998.6   31.98  5019.8   32.27  5040.8   31.16
  5062.2   32.39  5117.5   31.82    5148   33.68  5279.8   35.57  5309.8   35.24
  5360.9    35.7  5381.1   36.92  5391.3   36.69  5401.4   37.53  5407.6   40.02
#Mann= 3 , 0 , 0
  4375.2     .03       0  5019.8     .03       0  5062.2     .03       0
Bank Sta=5019.8,5062.2
XS Rating Curve= 0 ,0
Exp/Cntr=0.3,0.1

Type RM Length L Ch R = 1 ,264     ,0,0,0
BEGIN DESCRIPTION:
UNT043 IN BACR 1.0
END DESCRIPTION:
XS GIS Cut Line= 5
      2369227.55     13147047.08      2369761.44     13146817.03
      2369995.81     13146552.27        2369909.     13146165.98
      2369587.86      13145883.9
#Sta/Elev= 30
  3784.1   48.33    3817   47.24  3827.9   47.57  3860.5   44.91  3898.5   44.03
    3922   42.18  3945.5   41.86    3951   40.98  3974.5   40.11  3991.2    37.6
  4003.5   37.43    4013   36.05  4050.5   34.34  4056.5   33.25  4132.7   30.57
  4278.6   28.54  4325.6   27.13  4461.9   28.01  4561.4   26.53  4696.1    25.8
  4702.5   25.19  4731.4   26.47  4857.8   26.52  4991.1    27.6  5021.8   27.76
  5391.7   29.23  5518.9   31.73  5526.5   33.09  5533.1   36.35  5542.4   37.35
#Mann= 3 , 0 , 0
  3784.1     .03       0  4991.1     .03       0  5021.8     .03       0
#XS Ineff= 2 , 0
       0 4970.17   27.15               0
Permanent Ineff=
       T       F
Bank Sta=4991.1,5021.8
XS Rating Curve= 0 ,0
Exp/Cntr=0.3,0.1

Chan Stop Cuts=-1
Use User Specified Reach Order=0
Composite Channel Slope=5