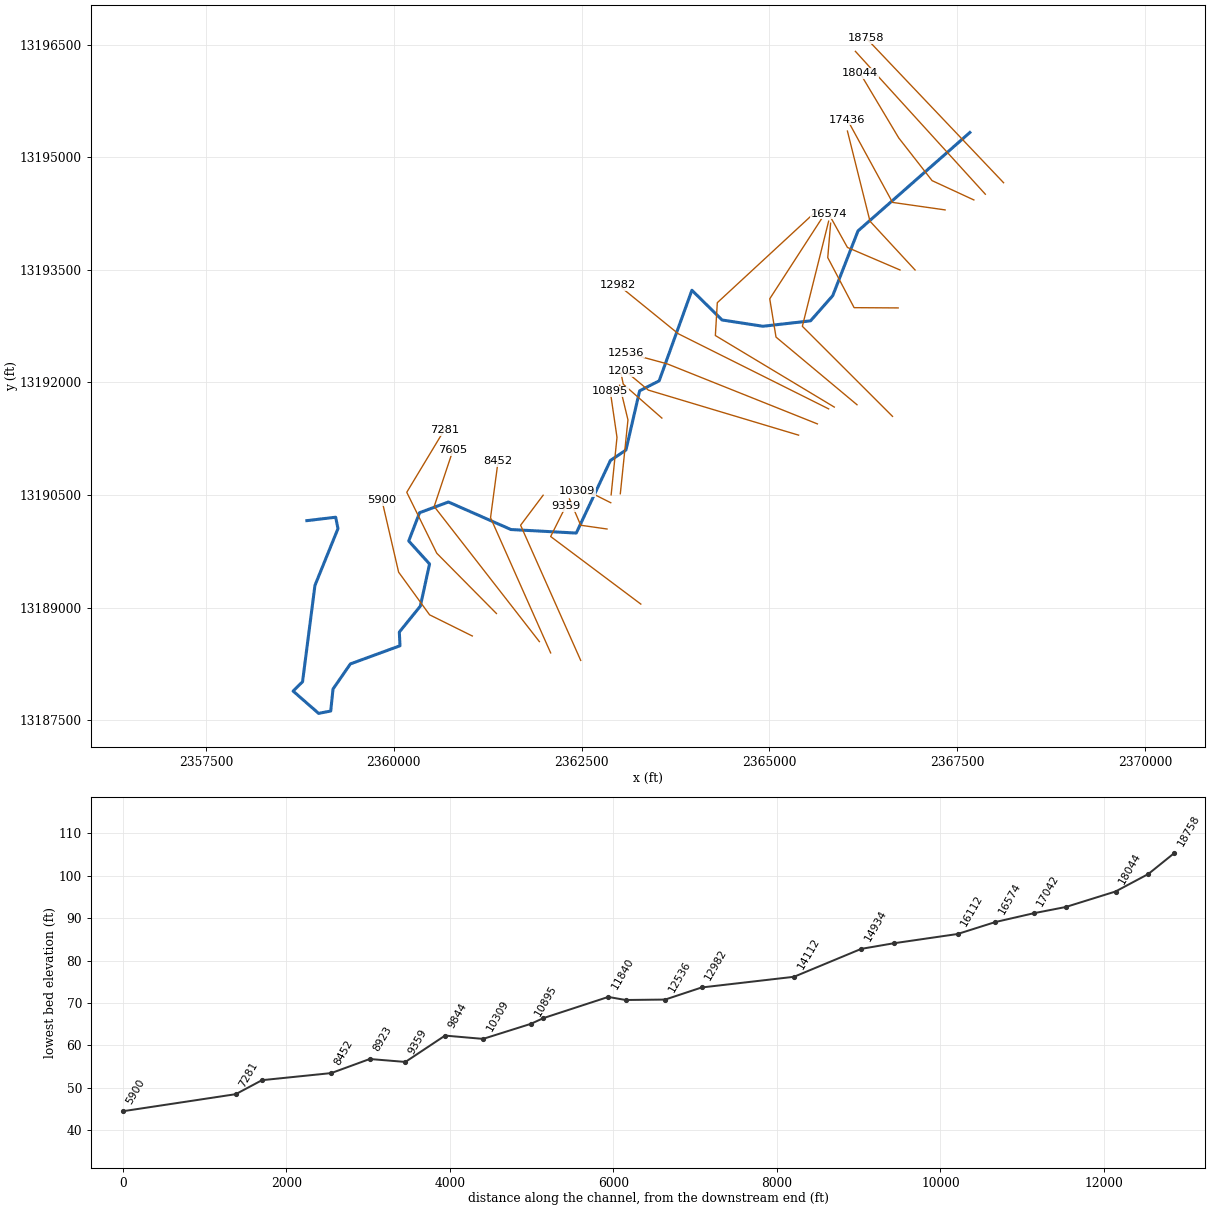
--- UNT045 IN BACR.prj (project) ---

Proj Title=UNT045 IN BACR Base Level Engineering
Current Plan=p01
Default Exp/Contr=0.3,0.1
English Units
Geom File=g01
Flow File=f01
Plan File=p01
Y Axis Title=Elevation
X Axis Title(PF)=Main Channel Distance
X Axis Title(XS)=Station
BEGIN DESCRIPTION:
UNT045 IN BACR
END DESCRIPTION:
DSS Export Rating Curves= 0
DSS Export Rating Curve Sorted= 0
DSS Export Volume Flow Curves= 0
DXF OffsetX= 0
DXF OffsetY= 0
DXF ScaleX= 1
DXF ScaleY= 10

--- UNT045 IN BACR.p01 (plan) ---

Plan Title=Multiple Run
Short Identifier=Multiple
Geom File=g01
Flow File=f01
Subcritical Flow
K Sum by GR= 0
Std Step Tol= 0.01
Critical Tol= 0.01
Num of Std Step Trials= 20
Max Error Tol= 0.3
Flow Tol Ratio= 0.001
Split Flow NTrial= 30
Split Flow Tol= 0.02
Split Flow Ratio= 0.02
Log Output Level= 0
Friction Slope Method= 1
Unsteady Friction Slope Method= 2
Unsteady Bridges Friction Slope Method= 1
Parabolic Critical Depth
Global Vel Dist=  1 , 1 , 1
Global Log Level= 0
CheckData=True
Encroach Param= -1, 0, 0, 0
BEGIN DESCRIPTION:
Multiple Run
END DESCRIPTION:

--- UNT045 IN BACR.f01 (steady flow) ---

Flow Title=Multiple
Program Version=4.10
Number of Profiles= 7
Profile Names=10-year,25-year,50-year,1pct_min,100-year,1pct_plu,500-year
River Rch & RM=UNT045 IN BACR,Reach-1         ,18758
     341     446     526     452     612     828     831
River Rch & RM=UNT045 IN BACR,Reach-1         ,18445
     492     665     802     706     954    1290    1355
River Rch & RM=UNT045 IN BACR,Reach-1         ,12982
     795    1106    1361    1220    1650    2231    2431
River Rch & RM=UNT045 IN BACR,Reach-1         ,10895
     864    1209    1494    1344    1817    2458    2700
River Rch & RM=UNT045 IN BACR,Reach-1         ,7281
    1068    1512    1883    1706    2307    3120    3478
Boundary for River Rch & Prof#=UNT045 IN BACR,Reach-1         , 1
Up Type= 0
Dn Type= 3
Dn Slope=0.005
Boundary for River Rch & Prof#=UNT045 IN BACR,Reach-1         , 2
Up Type= 0
Dn Type= 3
Dn Slope=0.005
Boundary for River Rch & Prof#=UNT045 IN BACR,Reach-1         , 3
Up Type= 0
Dn Type= 3
Dn Slope=0.005
Boundary for River Rch & Prof#=UNT045 IN BACR,Reach-1         , 4
Up Type= 0
Dn Type= 3
Dn Slope=0.005
Boundary for River Rch & Prof#=UNT045 IN BACR,Reach-1         , 5
Up Type= 0
Dn Type= 3
Dn Slope=0.005
Boundary for River Rch & Prof#=UNT045 IN BACR,Reach-1         , 6
Up Type= 0
Dn Type= 3
Dn Slope=0.005
Boundary for River Rch & Prof#=UNT045 IN BACR,Reach-1         , 7
Up Type= 0
Dn Type= 3
Dn Slope=0.005
DSS Import GetInterval= 0
DSS Import GetPeak= 0
DSS Import FillOption= 0

--- UNT045 IN BACR.g01 (geometry) ---

Geom Title=Existing Conditions
Program Version=4.10

River Reach=UNT045 IN BACR  ,Reach-1
Reach XY= 30
      2367667.25     13195327.98      2366178.36      13194016.7
        2365842.     13193154.51      2365546.74     13192819.24
       2364912.7     13192747.15      2364369.15     13192830.79
      2363967.72     13193226.85       2363531.8     13192019.99
      2363272.08     13191887.12      2363089.72     13191098.29
      2362883.21     13190959.42      2362428.78     13189992.69
       2361559.2     13190039.92      2360727.24     13190406.35
      2360343.47     13190263.86      2360198.94      13189887.1
      2360475.95     13189580.97      2360353.64     13189020.01
      2360073.68     13188673.93      2360082.75     13188491.75
      2359422.43     13188249.86      2359191.23      13187915.4
       2359160.6     13187622.29      2358999.75     13187591.11
      2358660.17     13187888.08      2358785.74     13188012.39
       2358950.7     13189295.62      2359257.12     13190051.61
      2359226.67     13190203.71      2358843.66      13190158.2

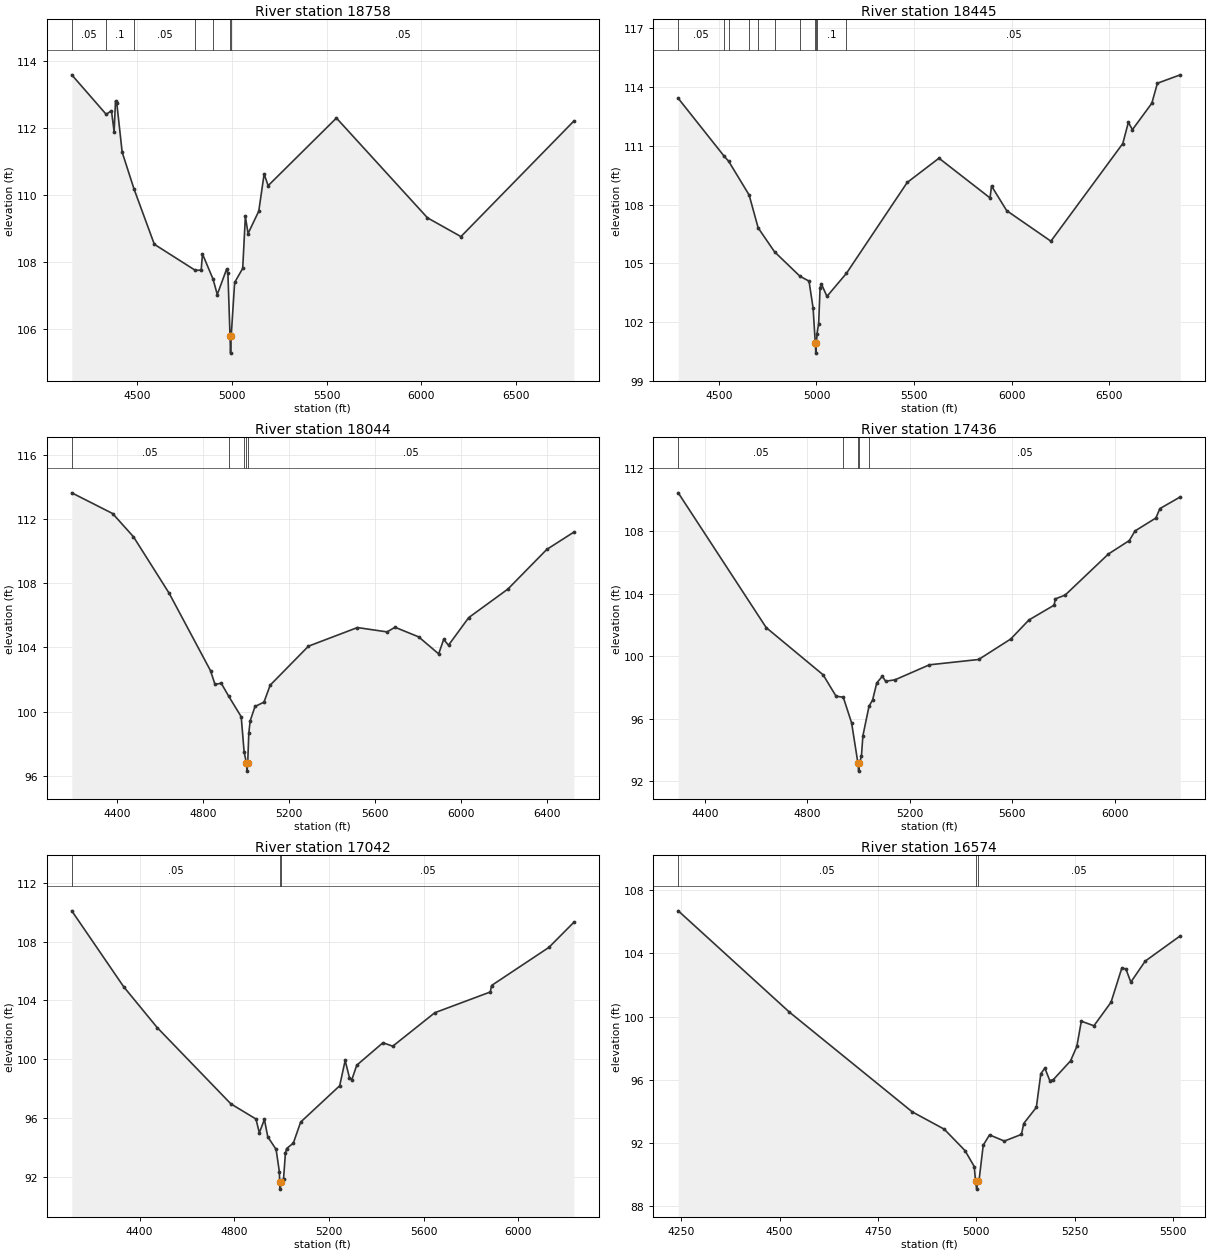
Type RM Length L Ch R = 1 ,18758   ,313,313,313
BEGIN DESCRIPTION:
UNT045 IN BACR 28.0
END DESCRIPTION:
XS GIS Cut Line= 2
       2368116.1     13194658.88      2366290.02     13196582.17
#Sta/Elev= 30
  4154.1  113.58    4336   112.4  4363.7  112.51  4377.8  111.88  4385.1   112.8
    4392  112.73  4420.3  111.27    4483  110.17  4590.2  108.52  4807.3  107.74
  4837.7  107.75  4844.6  108.23  4900.4  107.48  4922.7  107.02  4972.1  107.78
  4978.9  107.65  4990.1  105.77  4992.9  105.27  4996.1  105.77  5014.5  107.38
    5057   107.8  5071.1  109.35  5085.3  108.84  5141.9  109.51  5170.2  110.62
  5191.3  110.27  5552.1  112.29    6033  109.31  6209.8  108.75  6806.2   112.2
#Mann= 7 ,-1 , 0
  4154.1     .05       0    4336      .1       0    4483     .05       0
  4807.3     .12       0  4900.4     .05       0  4990.1     .04       0
  4996.1     .05       0
Bank Sta=4990.1,4996.1
XS Rating Curve= 0 ,0
Exp/Cntr=0.3,0.1

Type RM Length L Ch R = 1 ,18445   ,401,401,401
BEGIN DESCRIPTION:
UNT045 IN BACR 27.0
END DESCRIPTION:
XS GIS Cut Line= 2
      2367873.04     13194506.11      2366143.87     13196408.89
#Sta/Elev= 30
    4292  113.43  4524.9   110.5  4550.5  110.21    4655  108.49  4701.3  106.81
    4785  105.59  4915.1  104.34  4961.7  104.09  4982.7  102.71  4993.9  100.91
  4996.6  100.41  4999.9  100.91  5002.7  101.41    5011  101.91  5018.5  103.76
  5025.2  103.94  5053.6  103.31  5153.5  104.49  5464.5  109.13  5627.3  110.37
  5888.8  108.34  5896.3  108.95    5974  107.69  6200.4  106.13  6568.6  111.12
    6597   112.2    6618  111.83  6717.3  113.18  6745.7   114.2  6863.1  114.63
#Mann= 11 ,-1 , 0
    4292     .05       0  4524.9      .1       0  4550.5     .05       0
    4655      .1       0  4701.3     .05       0    4785      .1       0
  4915.1     .12       0  4993.9     .07       0  4999.9     .12       0
  5002.7      .1       0  5153.5     .05       0
Bank Sta=4993.9,4999.9
XS Rating Curve= 0 ,0
Exp/Cntr=0.3,0.1

Type RM Length L Ch R = 1 ,18044   ,608,608,608
BEGIN DESCRIPTION:
UNT045 IN BACR 26.0
END DESCRIPTION:
XS GIS Cut Line= 4
      2367720.24     13194429.72      2367164.72     13194686.65
      2366720.27      13195256.1      2366206.39      13196117.2
#Sta/Elev= 30
  4188.1  113.64  4378.2  112.35  4475.4   110.9  4641.4  107.38    4834  102.55
  4854.8   101.7  4883.8  101.77  4918.2  100.97  4976.9   99.68  4990.3    97.5
  5001.1   96.79  5003.8   96.29  5007.1   96.79  5012.2   98.65  5018.5   99.42
  5041.1  100.32  5082.8  100.59  5111.7  101.65  5289.9  104.08  5517.8  105.24
  5655.8  104.97  5692.8  105.26  5802.9  104.66    5896   103.6  5919.3   104.5
  5941.9  104.14  6035.8  105.86  6218.3  107.64  6399.2  110.11  6525.3  111.19
#Mann= 5 ,-1 , 0
  4188.1     .05       0  4918.2     .12       0  4990.3     .05       0
  5001.1    .035       0  5007.1     .05       0
Bank Sta=5001.1,5007.1
XS Rating Curve= 0 ,0
Exp/Cntr=0.3,0.1

Type RM Length L Ch R = 1 ,17436   ,394,394,394
BEGIN DESCRIPTION:
UNT045 IN BACR 25.0
END DESCRIPTION:
XS GIS Cut Line= 3
       2367337.7     13194296.86      2366637.72     13194396.85
      2366037.71     13195496.87
#Sta/Elev= 30
  4295.9  110.44  4639.3  101.82  4861.6    98.8  4912.1   97.43  4940.1   97.37
  4972.7   95.73  4997.5   93.14  5000.2   92.64  5003.5   93.14  5011.1    93.6
  5016.8    94.9  5040.7   96.79  5054.7   97.19  5070.9   98.28  5092.7   98.71
  5105.5   98.39  5142.1   98.48  5276.4   99.44  5468.6   99.78  5593.9  101.09
  5665.1  102.31  5762.9  103.25  5768.6  103.66  5806.5   103.9  5975.5  106.53
  6057.1  107.39    6079     108  6160.6  108.83  6176.2  109.43    6256  110.18
#Mann= 5 ,-1 , 0
  4295.9     .05       0  4940.1     .12       0  4997.5     .07       0
  5003.5     .12       0  5040.7     .05       0
Bank Sta=4997.5,5003.5
XS Rating Curve= 0 ,0
Exp/Cntr=0.3,0.1

Type RM Length L Ch R = 1 ,17042   ,468,468,468
BEGIN DESCRIPTION:
UNT045 IN BACR 24.0
END DESCRIPTION:
XS GIS Cut Line= 3
      2366937.74     13193496.84      2366337.72     13194146.85
      2366037.73     13195346.81
#Sta/Elev= 30
  4113.5  110.09  4332.7  104.93  4474.4  102.15  4785.8   96.96  4891.8   95.93
    4906   94.99  4927.5    95.9  4941.7   94.72  4976.9   93.86    4991   92.31
  4991.7   91.66  4994.5   91.16  4997.7   91.66  5008.4   91.88  5016.2   93.59
  5021.3   93.92  5049.7   94.29  5080.6   95.72  5245.5   98.19  5268.7   99.91
  5286.7   98.75    5297   98.61  5317.7   99.59  5428.5  101.12  5469.7  100.88
  5647.5  103.16    5882  104.57  5887.2  105.01  6129.4   107.6    6235  109.31
#Mann= 3 ,-1 , 0
  4113.5     .05       0  4991.7    .035       0  4997.7     .05       0
Bank Sta=4991.7,4997.7
XS Rating Curve= 0 ,0
Exp/Cntr=0.3,0.1

Type RM Length L Ch R = 1 ,16574   ,462,462,462
BEGIN DESCRIPTION:
UNT045 IN BACR 23.0
END DESCRIPTION:
XS GIS Cut Line= 3
      2366737.69     13193496.87      2366037.72     13193796.85
      2365787.73     13194246.83
#Sta/Elev= 30
  4242.2  106.69    4525  100.28  4836.9   93.98  4918.5   92.88  4971.1   91.53
  4994.7   90.52    4998   89.59  5000.8   89.09    5004   89.59  5006.6   89.59
  5017.5   91.87  5033.5   92.52  5071.2   92.13  5114.7   92.55  5120.4   93.24
  5152.5   94.26  5163.9   96.39  5174.2   96.74  5186.8   95.95  5195.9   96.02
  5239.4    97.2  5255.4   98.11  5266.9   99.71  5298.9   99.42  5342.4  100.91
  5369.8  103.07  5380.1  103.02  5392.7  102.18  5429.3  103.51  5518.5  105.11
#Mann= 3 ,-1 , 0
  4242.2     .05       0    4998     .03       0    5004     .05       0
Bank Sta=4998,5004
XS Rating Curve= 0 ,0
Exp/Cntr=0.3,0.1

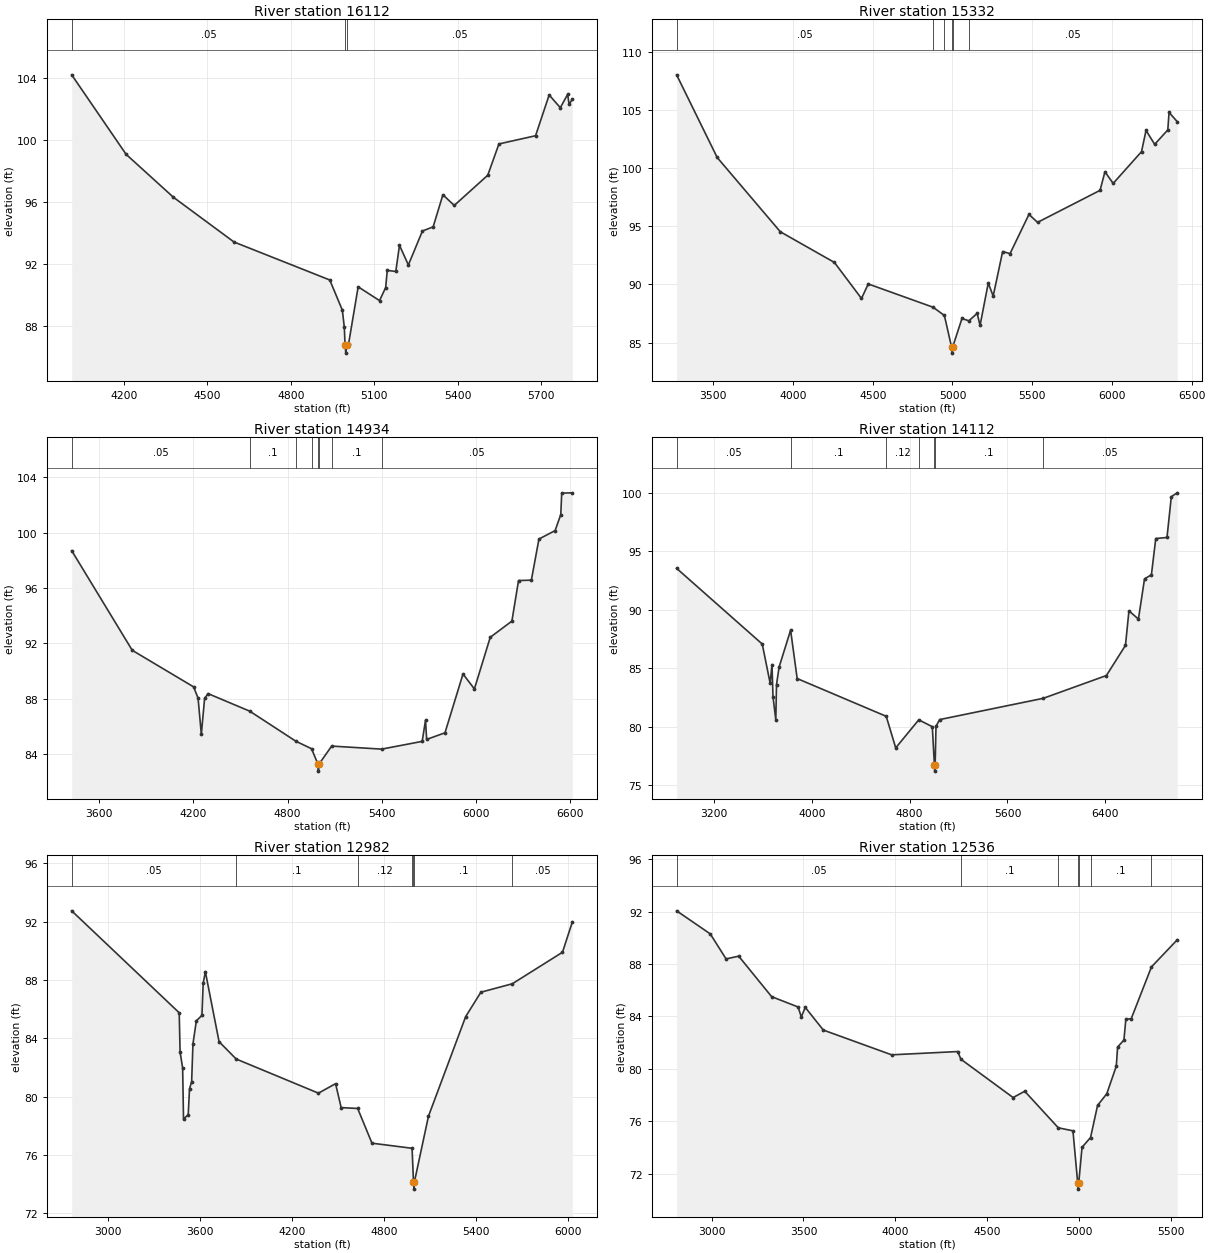
Type RM Length L Ch R = 1 ,16112   ,780,780,780
BEGIN DESCRIPTION:
Mapping XS b657abaa
END DESCRIPTION:
XS GIS Cut Line= 4
      2366713.32     13192991.51      2366126.52     13192994.98
      2365775.83     13193661.65      2365814.02     13194119.97
#Sta/Elev= 30
  4011.9  104.23  4207.5    99.1  4377.5   96.33  4595.6   93.44  4939.8   90.99
    4985   89.04  4992.1   87.93  4994.7   86.77  4997.5   86.27  5000.7   86.77
  5007.6   86.89  5041.8   90.55  5118.7   89.66  5140.7    90.5  5146.4   91.61
  5177.1   91.54  5190.4   93.23  5222.3   91.96  5272.9   94.15  5311.4   94.42
  5346.5   96.49  5387.3    95.8  5507.7   97.75  5547.9   99.77  5679.6   100.3
  5728.5  102.93  5768.6  102.11    5795  102.97    5800  102.34  5811.9  102.64
#Mann= 3 ,-1 , 0
  4011.9     .05       0  4994.7     .03       0  5000.7     .05       0
Bank Sta=4994.7,5000.7
XS Rating Curve= 0 ,0
Exp/Cntr=0.3,0.1

Type RM Length L Ch R = 1 ,15332   ,398,398,398
BEGIN DESCRIPTION:
UNT045 IN BACR 22.0
END DESCRIPTION:
XS GIS Cut Line= 3
       2366637.7     13191546.88      2365437.72     13192746.85
      2365787.72     13194146.85
#Sta/Elev= 30
  3269.7  108.03  3524.2  100.92  3920.2   94.53  4259.6   91.89  4429.3   88.79
  4471.7   90.04    4878   88.04  4949.2   87.33  4994.6   84.59  4997.4   84.09
  5000.6   84.59  5059.5   87.07  5102.5   86.87  5154.8   87.51  5172.9   86.47
  5224.4   90.12  5255.3      89  5314.6   92.83    5361   92.65  5479.5   96.02
  5533.7   95.34  5925.3   98.09  5956.3   99.69  6007.8   98.69  6185.6  101.42
    6214  103.25  6268.1  102.05  6350.5  103.29  6358.3   104.8  6409.8     104
#Mann= 6 ,-1 , 0
  3269.7     .05       0    4878      .1       0  4949.2     .12       0
  4994.6     .07       0  5000.6     .12       0  5102.5     .05       0
Bank Sta=4994.6,5000.6
XS Rating Curve= 0 ,0
Exp/Cntr=0.3,0.1

Type RM Length L Ch R = 1 ,14934   ,822,822,822
BEGIN DESCRIPTION:
Mapping XS 55d5c3fb
END DESCRIPTION:
XS GIS Cut Line= 4
      2366165.29     13191701.84      2365087.17     13192602.88
      2365003.84     13193113.29      2365691.36     13194175.82
#Sta/Elev= 30
  3425.8    98.7  3811.4    91.5  4201.8   88.86  4230.4   88.05  4251.2   85.43
  4272.1   88.03  4294.2   88.37  4559.9    87.1  4853.2   84.93  4952.8   84.39
    4994   83.27  4996.8   82.77    5000   83.27  5081.1   84.58  5399.6   84.36
  5657.5   84.92  5678.6   86.45  5685.8   85.06  5802.6   85.54  5917.3   89.79
  5989.9   88.71  6090.8   92.44  6228.6   93.61  6270.9   96.54  6352.6   96.57
  6400.8   99.54  6503.7  100.15  6539.9  101.31  6545.9  102.86  6613.6  102.88
#Mann= 8 ,-1 , 0
  3425.8     .05       0  4559.9      .1       0  4853.2     .12       0
  4952.8     .16       0    4994     .07       0    5000     .16       0
  5081.1      .1       0  5399.6     .05       0
Bank Sta=4994,5000
XS Rating Curve= 0 ,0
Exp/Cntr=0.3,0.1

Type RM Length L Ch R = 1 ,14112   ,1130,1130,1130
BEGIN DESCRIPTION:
UNT045 IN BACR 21.0
END DESCRIPTION:
XS GIS Cut Line= 4
      2365863.21     13191670.59      2364279.88     13192623.71
      2364305.92     13193061.21       2365633.4     13194289.78
#Sta/Elev= 30
  2893.9   93.54  3594.6   87.06    3659   83.71  3674.2   85.31  3682.3   82.56
  3705.3   80.58  3711.1    83.6  3732.5    85.1  3826.4   88.25  3880.1   84.11
  4608.5   80.88  4686.1   78.18  4874.7   80.58  4985.5   79.99  5002.6   76.69
  5005.3   76.19  5008.6   76.69  5015.6   80.03  5045.7    80.6  5893.1   82.42
  6409.5   84.37  6565.4   86.95  6593.7    89.9  6671.4    89.2  6721.3   92.64
  6777.5   92.99  6813.2   96.09    6905   96.18  6940.4   99.67    6989     100
#Mann= 7 ,-1 , 0
  2893.9     .05       0  3826.4      .1       0  4608.5     .12       0
  4874.7      .1       0  5002.6     .07       0  5008.6      .1       0
  5893.1     .05       0
Bank Sta=5002.6,5008.6
XS Rating Curve= 0 ,0
Exp/Cntr=0.3,0.1

Type RM Length L Ch R = 1 ,12982   ,446,446,446
BEGIN DESCRIPTION:
UNT045 IN BACR 20.0
END DESCRIPTION:
XS GIS Cut Line= 3
      2365787.76     13191646.83      2363787.72     13192646.85
      2362987.71     13193296.86
#Sta/Elev= 30
  2762.2   92.75  3463.8   85.76  3469.4   83.08  3486.2   81.97  3491.8   78.48
  3522.5   78.77  3530.9   80.54  3544.9   81.04  3553.3   83.62  3575.6   85.21
    3612   85.58  3620.3   87.79  3634.3   88.58  3723.8   83.78  3835.5   82.59
  4372.2   80.25    4484    80.9  4520.4   79.26  4628.2    79.2  4721.6   76.82
  4983.2   76.47  4992.5   74.17  4995.3   73.67  4998.5   74.17  5090.2   78.67
  5333.1    85.5  5432.2   87.17  5637.4   87.75  5964.7   89.91  6029.1   91.99
#Mann= 7 ,-1 , 0
  2762.2     .05       0  3835.5      .1       0  4628.2     .12       0
  4983.2      .1       0  4992.5     .07       0  4998.5      .1       0
  5637.4     .05       0
Bank Sta=4992.5,4998.5
XS Rating Curve= 0 ,0
Exp/Cntr=0.3,0.1

Type RM Length L Ch R = 1 ,12536   ,483,483,483
BEGIN DESCRIPTION:
UNT045 IN BACR 19.0
END DESCRIPTION:
XS GIS Cut Line= 3
      2365637.71     13191446.86      2363637.72     13192246.85
      2363087.76     13192396.84
#Sta/Elev= 30
  2809.9   92.06    2993    90.3  3079.1   88.39  3147.8    88.6  3326.9   85.51
  3470.9   84.72  3488.4   83.96    3510   84.69  3608.2   82.96  3979.8   81.07
  4339.3   81.32  4357.1   80.73  4640.8   77.81  4704.1   78.29  4886.8    75.5
  4966.5   75.27  4992.1   71.32  4994.8   70.82  4998.1   71.32  5015.8   74.01
  5062.2   74.76  5100.4   77.21  5150.5    78.1  5202.4   80.21  5209.3   81.66
  5243.8    82.2  5254.2   83.78  5283.6   83.83  5393.6   87.78    5534   89.85
#Mann= 7 ,-1 , 0
  2809.9     .05       0  4357.1      .1       0  4886.8     .12       0
  4992.1     .07       0  4998.1     .12       0  5062.2      .1       0
  5393.6     .05       0
Bank Sta=4992.1,4998.1
XS Rating Curve= 0 ,0
Exp/Cntr=0.3,0.1

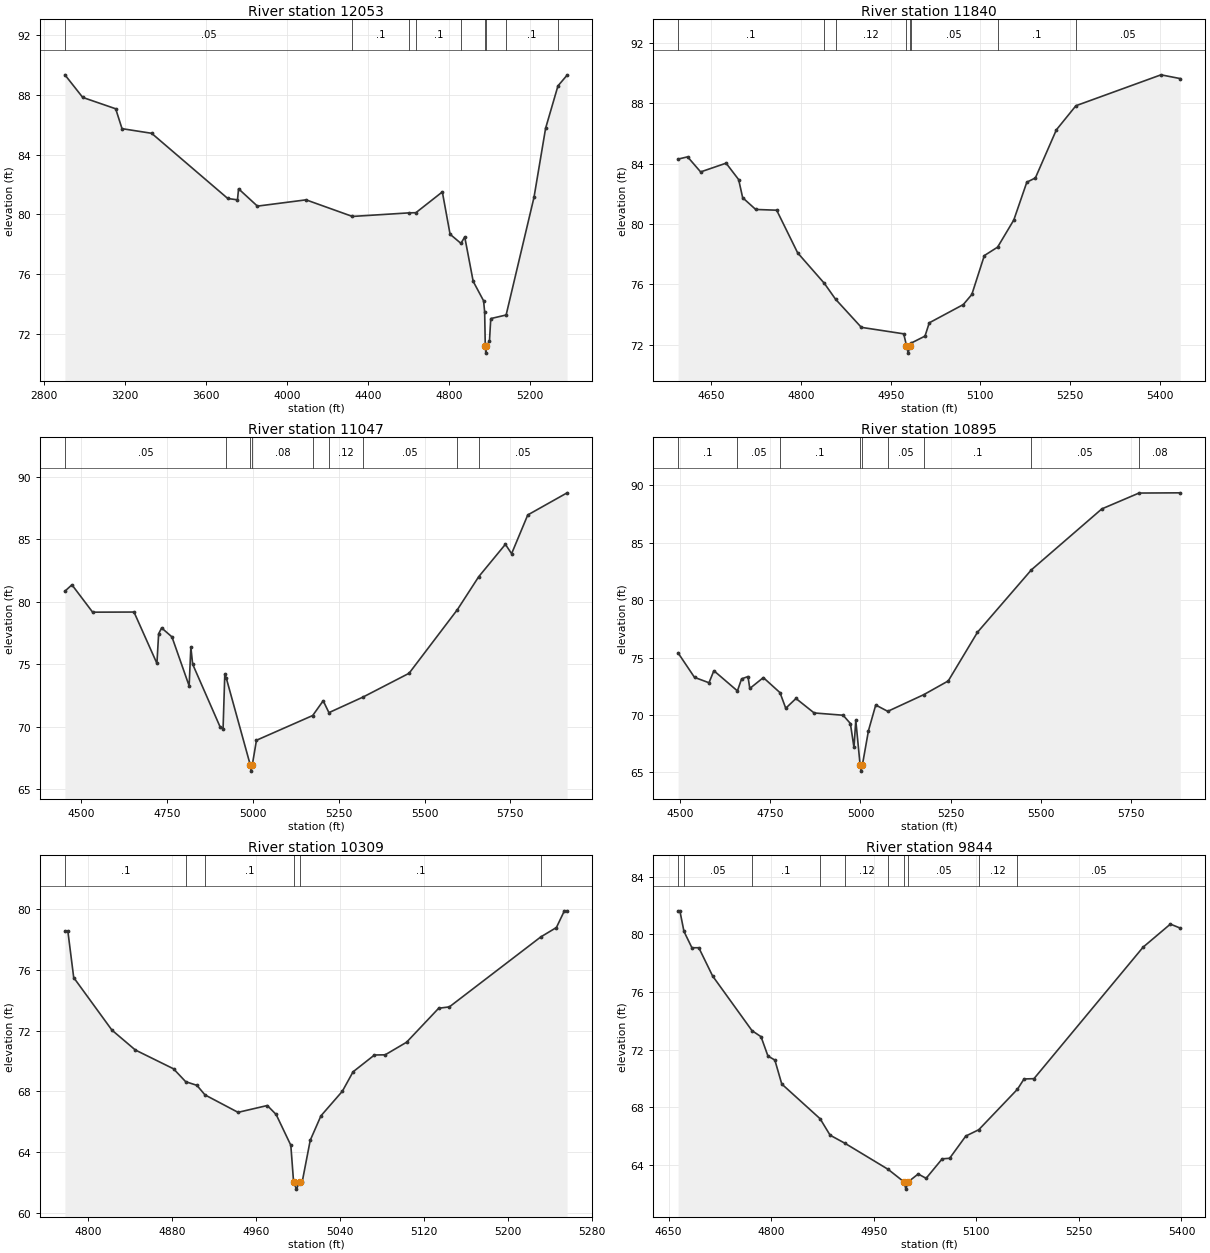
Type RM Length L Ch R = 1 ,12053   ,213,213,213
BEGIN DESCRIPTION:
UNT045 IN BACR 18.0
END DESCRIPTION:
XS GIS Cut Line= 3
      2365387.75     13191296.85      2363387.72     13191896.85
      2363087.73     13192146.85
#Sta/Elev= 30
  2903.4   89.33  2991.3   87.82    3154   87.06  3185.3   85.73  3331.5   85.42
  3707.3   81.06  3755.2   80.97  3760.4   81.71  3853.5   80.55  4093.6   80.97
  4322.3   79.86  4602.6    80.1  4635.6   80.11  4766.2    81.5  4804.4   78.67
    4858   78.06  4876.7   78.49  4918.4   75.52  4969.7   74.22    4975   73.48
  4978.1   71.22  4980.8   70.72  4984.1   71.22  4998.7   71.51  5005.2   73.03
    5081   73.27  5218.6   81.14  5275.9   85.76  5336.8   88.59    5382   89.31
#Mann= 9 ,-1 , 0
  2903.4     .05       0  4322.3      .1       0  4602.6     .05       0
  4635.6      .1       0    4858     .12       0  4978.1     .07       0
  4984.1     .12       0    5081      .1       0  5336.8     .05       0
Bank Sta=4978.1,4984.1
XS Rating Curve= 0 ,0
Exp/Cntr=0.3,0.1

Type RM Length L Ch R = 1 ,11840   ,793,793,793
BEGIN DESCRIPTION:
UNT045 IN BACR 17.0
END DESCRIPTION:
XS GIS Cut Line= 3
      2363568.02     13191524.29       2363054.1     13191975.71
      2363022.84     13192128.52
#Sta/Elev= 30
  4594.4   84.31  4610.3   84.46  4632.1   83.46  4674.7   84.04  4695.7   82.95
  4702.4   81.75  4724.2   80.97  4759.3   80.92  4794.4   78.09    4839   76.07
  4857.7   75.02  4900.9   73.15  4971.8   72.72  4976.4   71.94  4979.2   71.44
  4982.4   71.94  4983.9    72.1  5007.4   72.57  5014.5   73.45  5071.4   74.66
  5085.7   75.33  5106.6   77.91  5128.8   78.47  5155.9   80.27  5177.7   82.78
    5192   83.06  5227.1   86.25  5259.8   87.85  5402.1    89.9  5434.4   89.65
#Mann= 8 ,-1 , 0
  4594.4      .1       0    4839     .05       0  4857.7     .12       0
  4976.4     .04       0  4982.4     .12       0  4983.9     .05       0
  5128.8      .1       0  5259.8     .05       0
Bank Sta=4976.4,4982.4
XS Rating Curve= 0 ,0
Exp/Cntr=0.3,0.1

Type RM Length L Ch R = 1 ,11047   ,152,152,152
BEGIN DESCRIPTION:
UNT045 IN BACR 16.0
END DESCRIPTION:
XS GIS Cut Line= 3
      2363015.03     13190516.48       2363116.6     13191500.01
       2363005.5     13191961.77
#Sta/Elev= 30
  4451.7   80.85  4472.2   81.36  4532.5   79.17  4653.1   79.18  4719.9   75.07
  4724.9   77.44  4733.6   77.91  4763.7   77.19  4813.8   73.27  4818.8   76.37
    4824   75.01  4904.5   69.96  4912.7   69.85  4917.7   74.19  4922.2   73.88
  4991.9   66.95  4994.7   66.45  4997.9   66.95    5010   68.92  5173.9    70.9
  5204.5   72.08  5221.2   71.13  5320.8   72.38  5454.8   74.28  5595.8   79.38
  5657.8   82.01  5735.5    84.6  5753.6   83.85  5800.7   86.95  5915.4   88.72
#Mann= 9 ,-1 , 0
  4451.7     .05       0  4922.2     .08       0  4991.9     .07       0
  4997.9     .08       0  5173.9     .05       0  5221.2     .12       0
  5320.8     .05       0  5595.8     .08       0  5657.8     .05       0
Bank Sta=4991.9,4997.9
XS Rating Curve= 0 ,0
Exp/Cntr=0.3,0.1

Type RM Length L Ch R = 1 ,10895   ,586,586,586
BEGIN DESCRIPTION:
UNT045 IN BACR 15.0
END DESCRIPTION:
XS GIS Cut Line= 3
      2362892.84     13190501.63      2362970.76     13191267.37
      2362880.75     13191883.63
#Sta/Elev= 30
  4494.3   75.41  4539.8   73.28    4580   72.81  4593.5   73.86  4658.8    72.1
  4670.4   73.15  4688.1   73.35  4693.1   72.31  4730.7   73.26  4776.8   71.95
  4792.8   70.59  4821.2   71.44  4871.5   70.18  4951.9   69.98    4972   69.26
    4982   67.17    4987   69.54  4999.1   65.61  5001.9   65.11  5005.1   65.61
  5022.2   68.64  5042.3   70.87  5075.7   70.32  5175.3   71.77  5243.4   72.97
  5324.4   77.21  5473.9   82.65  5669.2   87.96  5772.2   89.34  5886.8   89.36
#Mann= 9 ,-1 , 0
  4494.3      .1       0  4658.8     .05       0  4776.8      .1       0
  4999.1     .07       0  5005.1      .1       0  5075.7     .05       0
  5175.3      .1       0  5473.9     .05       0  5772.2     .08       0
Bank Sta=4999.1,5005.1
XS Rating Curve= 0 ,0
Exp/Cntr=0.3,0.1

Type RM Length L Ch R = 1 ,10309   ,465,465,465
BEGIN DESCRIPTION:
UNT045 IN BACR 14.0
END DESCRIPTION:
XS GIS Cut Line= 3
      2362887.76     13190396.84      2362687.72     13190496.85
      2362437.72     13190546.86
#Sta/Elev= 30
  4777.7   78.56  4780.5   78.56  4786.1   75.49  4822.5   72.03  4844.8   70.72
  4881.2   69.48  4892.8   68.63  4903.5   68.39  4911.2   67.76  4942.7   66.61
  4970.6   67.06    4979   66.47    4993   64.44  4995.6   62.05  4998.3   61.55
  5001.6   62.05  5003.9   62.05  5011.5   64.77  5021.7   66.38  5042.1      68
  5052.3   69.28  5072.7   70.39  5082.9    70.4  5103.3   71.23  5133.9   73.47
  5144.1   73.56  5231.2   78.17  5246.1   78.79  5253.7   79.89  5256.3   79.89
#Mann= 6 ,-1 , 0
  4777.7      .1       0  4892.8     .12       0  4911.2      .1       0
  4995.6     .07       0  5001.6      .1       0  5231.2     .05       0
Bank Sta=4995.6,5001.6
XS Rating Curve= 0 ,0
Exp/Cntr=0.3,0.1

Type RM Length L Ch R = 1 ,9844    ,485,485,485
BEGIN DESCRIPTION:
UNT045 IN BACR 13.0
END DESCRIPTION:
XS GIS Cut Line= 3
      2362837.76     13190046.85      2362487.72     13190096.85
      2362337.71     13190446.87
#Sta/Elev= 30
  4663.9   81.63  4666.5   81.63  4672.5    80.2  4684.1   79.07  4694.2   79.07
  4714.4   77.11    4772   73.32  4785.2    72.9  4795.3   71.56  4805.4   71.28
  4815.5   69.62  4871.6   67.21  4886.2   66.07  4907.9   65.51  4971.1    63.7
  4994.3   62.83    4997   62.33  5000.3   62.83    5015   63.38  5026.6   63.08
  5050.1   64.43    5061   64.47  5084.6   66.01  5103.6   66.45  5160.2   69.26
  5169.8   69.97  5184.3   69.99  5343.9   79.11  5383.8   80.71  5398.3   80.43
#Mann= 10 ,-1 , 0
  4663.9     .08       0  4672.5     .05       0    4772      .1       0
  4871.6     .05       0  4907.9     .12       0  4971.1     .05       0
  4994.3     .03       0  5000.3     .05       0  5103.6     .12       0
  5160.2     .05       0
Bank Sta=4994.3,5000.3
XS Rating Curve= 0 ,0
Exp/Cntr=0.3,0.1

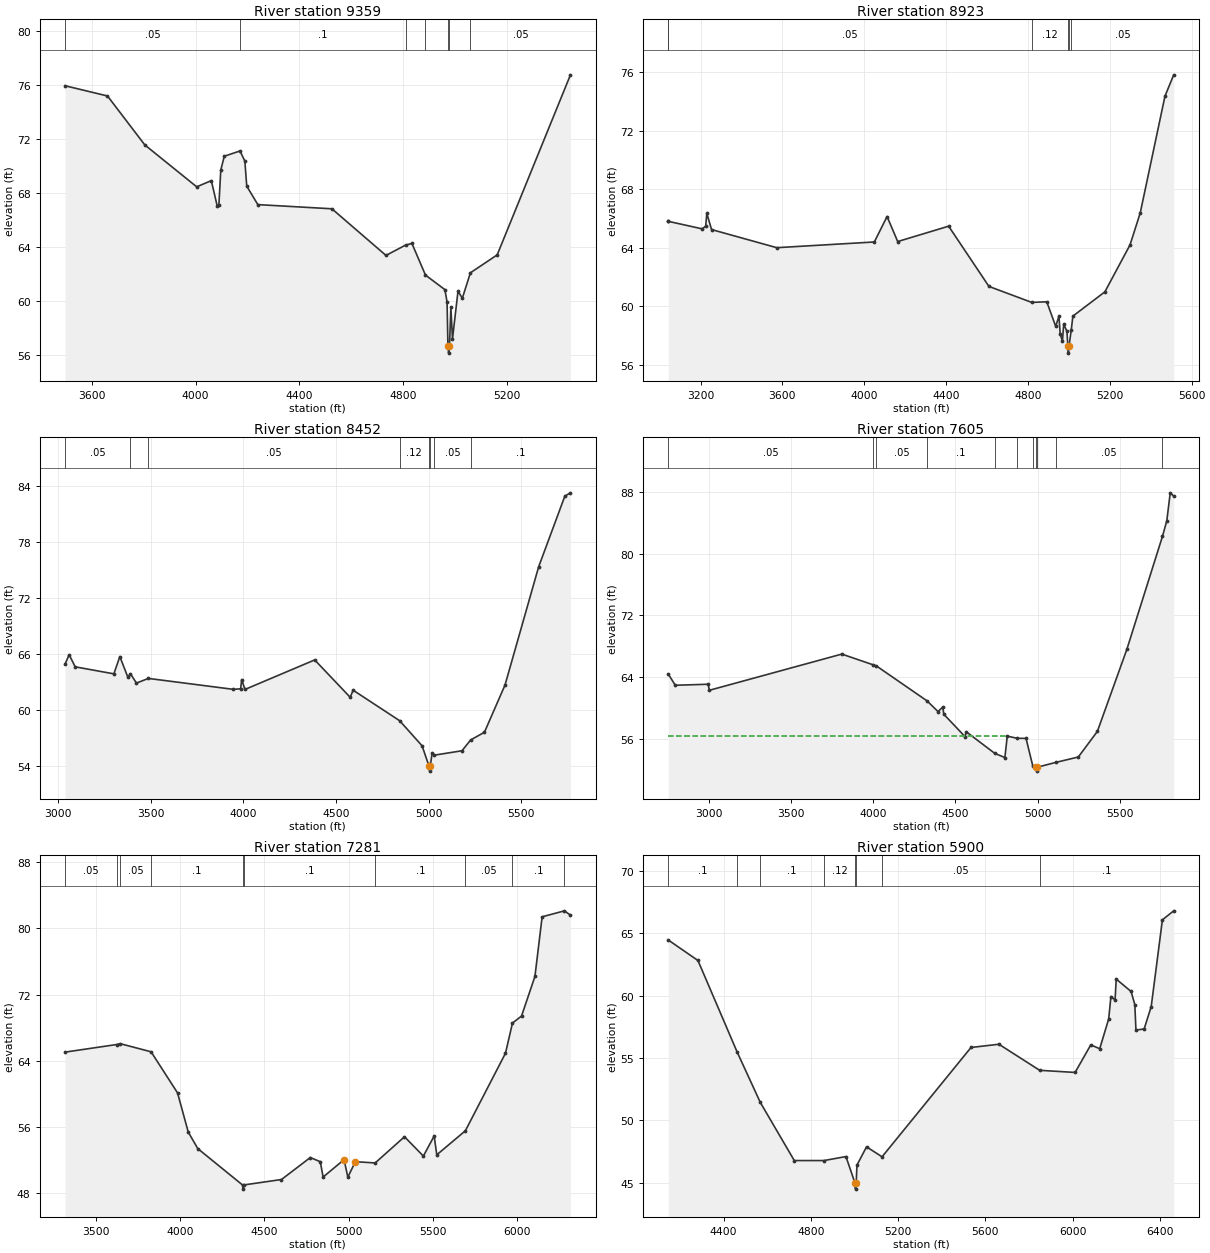
Type RM Length L Ch R = 1 ,9359    ,436,436,436
BEGIN DESCRIPTION:
UNT045 IN BACR 12.0
END DESCRIPTION:
XS GIS Cut Line= 3
      2363287.69     13189046.88      2362087.72     13189946.85
      2362287.73     13190346.88
#Sta/Elev= 30
  3496.9   75.96  3660.4    75.2  3804.1   71.57  4004.1   68.46  4060.4   68.92
  4083.3   67.02  4089.6   67.12  4096.9   69.71  4110.4   70.73  4170.9   71.12
  4189.6   70.37  4196.9   68.51  4239.6   67.14    4525   66.83  4733.3   63.37
  4809.3   64.14  4833.3   64.26  4885.5   61.91  4960.4   60.83  4968.7   59.91
    4972   56.62  4974.7   56.12    4978   56.62  4983.3   59.51  4989.6   57.18
  5010.8   60.71  5027.6    60.2  5058.6   62.08  5161.8   63.41  5444.1   76.77
#Mann= 7 ,-1 , 0
  3496.9     .05       0  4170.9      .1       0  4809.3     .05       0
  4885.5     .12       0    4972     .07       0    4978     .12       0
  5058.6     .05       0
Bank Sta=4972,4978
XS Rating Curve= 0 ,0
Exp/Cntr=0.3,0.1

Type RM Length L Ch R = 1 ,8923    ,471,471,471
BEGIN DESCRIPTION:
UNT045 IN BACR 11.0
END DESCRIPTION:
XS GIS Cut Line= 3
      2362487.71     13188296.89      2361687.72     13190096.85
       2361987.7     13190496.82
#Sta/Elev= 30
  3042.6   65.82  3043.3   65.82  3207.4   65.31  3225.2   65.48  3230.7   66.37
  3253.9   65.26  3572.6   64.02  4049.3   64.41  4111.6   66.15  4163.6   64.44
  4412.5   65.49  4609.5   61.37  4818.3   60.28    4892   60.32  4935.7   58.64
  4951.5   59.34  4957.6   58.11  4968.6   57.63  4974.7    58.8  4990.5    58.3
    4995   57.31  4997.7   56.81    5001   57.31  5011.5   58.38  5019.6   59.34
  5175.9      61  5298.8   64.21  5348.8    66.4  5469.6   74.38  5512.3   75.84
#Mann= 6 ,-1 , 0
  3042.6     .08       0  3043.3     .05       0  4818.3     .12       0
    4995     .07       0    5001     .12       0  5011.5     .05       0
Bank Sta=4995,5001
XS Rating Curve= 0 ,0
Exp/Cntr=0.3,0.1

Type RM Length L Ch R = 1 ,8452    ,847,847,847
BEGIN DESCRIPTION:
UNT045 IN BACR 10.0
END DESCRIPTION:
XS GIS Cut Line= 3
      2362087.72     13188396.85      2361287.72     13190196.85
      2361387.72     13190946.84
#Sta/Elev= 30
  3038.8   64.93  3060.7   65.95  3093.5   64.65  3302.1    63.9  3334.3   65.75
    3378   63.52  3391.5   63.92  3423.9   62.91  3488.3   63.41  3947.1   62.24
  3986.1    62.3  3991.5   63.29  4009.3   62.23  4385.5   65.39    4577   61.39
  4592.7   62.15  4843.5   58.89  4964.8    56.2  5002.8   53.99  5005.6   53.49
  5008.8   53.99  5018.7    55.4  5031.3    55.2  5180.1   55.67  5226.4   56.82
  5301.1   57.65  5412.1    62.7  5593.7   75.36    5735   82.92  5765.2   83.27
#Mann= 8 ,-1 , 0
  3038.8     .05       0  3391.5      .1       0  3488.3     .05       0
  4843.5     .12       0  5002.8     .07       0  5008.8     .12       0
  5031.3     .05       0  5226.4      .1       0
Bank Sta=5002.8,5008.8
XS Rating Curve= 0 ,0
Exp/Cntr=0.3,0.1

Type RM Length L Ch R = 1 ,7605    ,321,321,321
BEGIN DESCRIPTION:
UNT045 IN BACR 9.0
END DESCRIPTION:
XS GIS Cut Line= 3
      2361937.72     13188546.85      2360537.72     13190346.85
      2360787.71     13191096.83
#Sta/Elev= 30
  2755.1   64.39  2797.6   62.95  2996.7   63.08  3004.9    62.3  3809.3   66.99
  3998.2   65.61  4019.8   65.45  4327.6   60.92  4393.9   59.54  4422.8   60.12
  4429.2   59.19  4557.7    56.3  4565.8   56.92  4738.9   54.12  4800.2   53.58
  4814.7   56.36  4873.5   56.08  4928.7   56.06  4969.4   52.52  4989.9   52.32
  4992.7   51.82  4995.9   52.32  5109.4   52.95  5246.3   53.65  5362.2   56.97
  5541.4   67.61  5757.6   82.24  5783.9   84.25  5804.9   87.89    5826   87.46
#Mann= 11 ,-1 , 0
  2755.1     .05       0  3998.2      .1       0  4019.8     .05       0
  4327.6      .1       0  4738.9     .12       0  4873.5     .05       0
  4969.4     .12       0  4989.9     .07       0  4995.9     .12       0
  5109.4     .05       0  5757.6      .1       0
#XS Ineff= 2 , 0
         4814.86   56.38
Permanent Ineff=
       F       F
Bank Sta=4989.9,4995.9
XS Rating Curve= 0 ,0
Exp/Cntr=0.3,0.1

Type RM Length L Ch R = 1 ,7281    ,1381,1381,1381
BEGIN DESCRIPTION:
Mapping XS daeb4617
END DESCRIPTION:
XS GIS Cut Line= 4
      2361366.26     13188921.25      2360572.01     13189724.19
       2360172.7     13190535.82      2360670.96     13191363.36
#Sta/Elev= 30
    3317   65.05  3623.8   65.97  3644.3   66.07  3827.6   65.09  3984.7   60.13
  4048.3    55.4  4104.8   53.41  4370.5   49.02  4373.3   48.52  4376.5   49.02
  4601.6   49.68  4772.6   52.33  4831.9   51.83  4848.8   49.98  4973.2   52.08
  4995.5   49.96    5040   51.83  5157.7   51.68  5331.8   54.84  5443.8   52.51
  5507.9   54.93  5523.4   52.66  5693.1   55.56  5931.3   64.92  5972.7   68.56
  6026.4    69.4    6106   74.18  6148.8   81.38  6281.3    82.1  6316.9   81.57
#Mann= 10 ,-1 , 0
    3317     .05       0  3623.8      .1       0  3644.3     .05       0
  3827.6      .1       0  4370.5     .07       0  4376.5      .1       0
  5157.7      .1       0  5693.1     .05       0  5972.7      .1       0
  6281.3     .05       0
Bank Sta=4973.2,5040
XS Rating Curve= 0 ,0
Exp/Cntr=0.3,0.1

Type RM Length L Ch R = 1 ,5900    ,0,0,0
BEGIN DESCRIPTION:
UNT045 IN BACR 1.0
END DESCRIPTION:
XS GIS Cut Line= 4
      2361045.09     13188621.76      2360476.52     13188903.88
       2360064.2     13189472.45      2359842.85     13190427.27
#Sta/Elev= 30
  4146.3   64.46  4282.2   62.82  4461.8   55.49    4568   51.45  4723.9   46.79
  4860.2   46.79  4960.8   47.11  5001.9      45  5004.6    44.5  5007.9      45
  5011.1   46.42  5055.2   47.89  5126.3   47.09  5534.1   55.85  5662.1   56.11
    5849   54.02  6011.4   53.85  6083.3   56.06  6124.3   55.75  6165.4   58.14
  6175.6   59.93  6194.7   59.66  6199.9   61.33    6268   60.34  6285.2   59.29
  6290.3   57.25  6327.9   57.33  6360.4   59.13  6411.7   66.08  6463.5    66.8
#Mann= 8 ,-1 , 0
  4146.3      .1       0  4461.8     .05       0    4568      .1       0
  4860.2     .12       0  5001.9     .07       0  5007.9     .12       0
  5126.3     .05       0    5849      .1       0
Bank Sta=5001.9,5007.9
XS Rating Curve= 0 ,0
Exp/Cntr=0.3,0.1

Chan Stop Cuts=-1
Use User Specified Reach Order=0
Composite Channel Slope=5