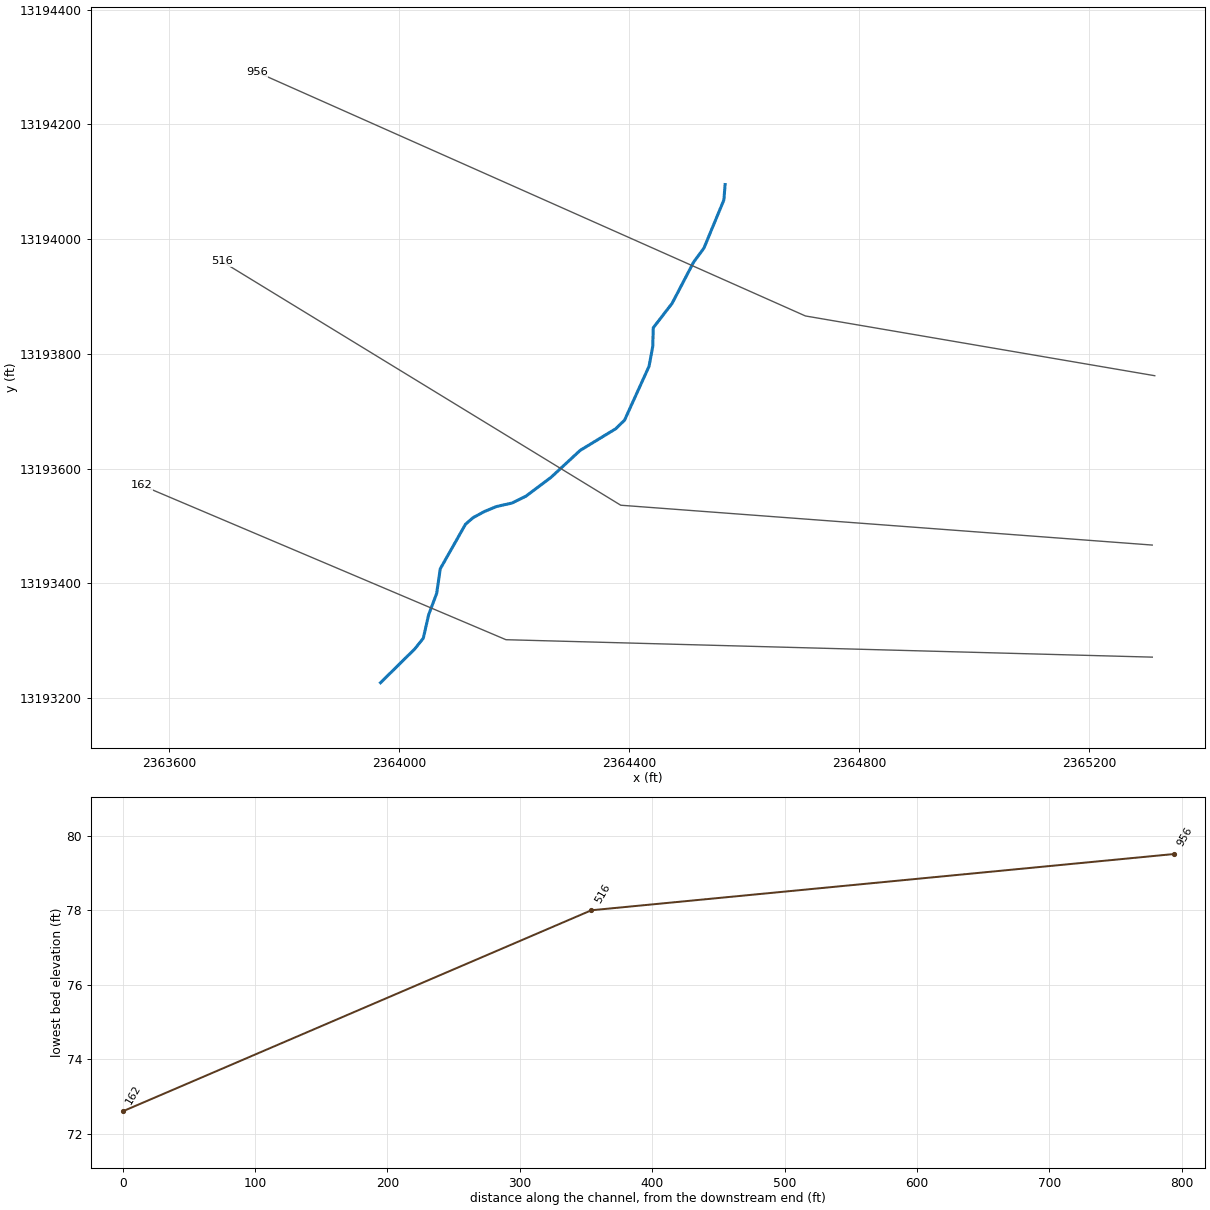
--- UNT046 IN BACR.prj (project) ---

Proj Title=UNT046 IN BACR Base Level Engineering
Current Plan=p01
Default Exp/Contr=0.3,0.1
English Units
Geom File=g01
Flow File=f01
Plan File=p01
BEGIN DESCRIPTION:
UNT046 IN BACR
END DESCRIPTION:

--- UNT046 IN BACR.p01 (plan) ---

Plan Title=Multiple Run
Short Identifier=Multiple
Geom File=g01
Flow File=f01
Subcritical Flow
K Sum by GR= 0
Std Step Tol= 0.01
Critical Tol= 0.01
Num of Std Step Trials= 20
Max Error Tol= 0.3
Flow Tol Ratio= 0.001
Split Flow NTrial= 30
Split Flow Tol= 0.02
Split Flow Ratio= 0.02
Log Output Level= 0
Friction Slope Method= 1
Unsteady Friction Slope Method= 2
Unsteady Bridges Friction Slope Method= 1
Parabolic Critical Depth
Global Vel Dist=  1 , 1 , 1
Global Log Level= 0
CheckData=True
Encroach Param= -1, 0, 0, 0
BEGIN DESCRIPTION:
Multiple Run
END DESCRIPTION:

--- UNT046 IN BACR.f01 (steady flow) ---

Flow Title=Multiple
Number of Profiles=7
Profile Names=10-year,25-year,50-year,1pct_min,100-year,1pct_plu,500-year
River Rch & RM= UNT046 IN BACR,Reach-1,956
     360     480     574     501     677     916     946
Boundary for River Rch & Prof#=UNT046 IN BACR,Reach-1,1
Up Type=0
Dn Type=3
Dn Slope=0.005
Boundary for River Rch & Prof#=UNT046 IN BACR,Reach-1,2
Up Type=0
Dn Type=3
Dn Slope=0.005
Boundary for River Rch & Prof#=UNT046 IN BACR,Reach-1,3
Up Type=0
Dn Type=3
Dn Slope=0.005
Boundary for River Rch & Prof#=UNT046 IN BACR,Reach-1,4
Up Type=0
Dn Type=3
Dn Slope=0.005
Boundary for River Rch & Prof#=UNT046 IN BACR,Reach-1,5
Up Type=0
Dn Type=3
Dn Slope=0.005
Boundary for River Rch & Prof#=UNT046 IN BACR,Reach-1,6
Up Type=0
Dn Type=3
Dn Slope=0.005
Boundary for River Rch & Prof#=UNT046 IN BACR,Reach-1,7
Up Type=0
Dn Type=3
Dn Slope=0.005

--- UNT046 IN BACR.g01 (geometry) ---

Geom Title=Existing Conditions

River Reach=UNT046 IN BACR,Reach-1
Reach XY= 24
      2364566.98     13194095.02      2364564.87     13194068.16
      2364530.25     13193984.46      2364512.06     13193959.53
      2364474.82     13193888.01      2364442.04     13193845.43
      2364441.17     13193813.12      2364434.71     13193778.20
      2364392.16     13193684.53      2364376.74     13193669.43
      2364314.89     13193631.72      2364264.37     13193584.90
      2364220.38     13193551.80      2364196.38     13193540.02
      2364168.93     13193533.74      2364148.27     13193525.14
      2364128.62     13193514.49      2364115.43     13193502.96
      2364071.55     13193425.29      2364065.30     13193382.40
      2364051.39     13193345.34      2364042.02     13193304.30
      2364027.31     13193285.80      2363967.72     13193226.85

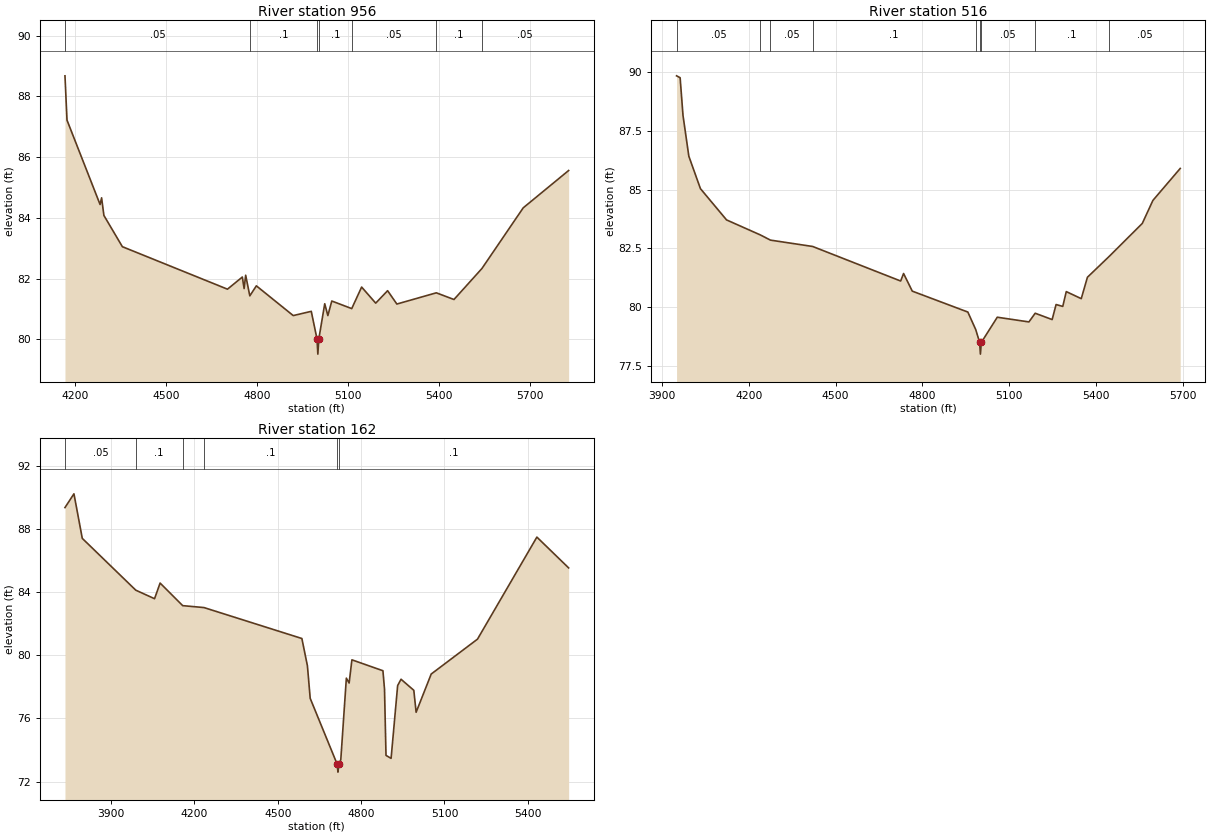
Type RM Length L Ch R = 1,956,440,440,440
BEGIN DESCRIPTION:
UNT046 IN BACR 2.0
END DESCRIPTION:
XS GIS Cut Line= 3
      2365314.31     13193761.87      2364706.69     13193866.03
      2363752.29     13194291.18
#Sta/Elev= 30
  4167.3   88.68  4174.0   87.22  4283.1   84.44  4288.1   84.66  4295.7   84.08
  4356.6   83.05  4703.3   81.65  4752.3   82.05  4758.2   81.67  4763.3   82.11
  4777.0   81.43  4798.6   81.76  4920.2   80.78  4979.7   80.92  4998.6   80.01
  5001.4   79.51  5004.6   80.01  5024.1   81.17  5034.4   80.78  5047.4   81.26
  5113.2   81.01  5145.8   81.72  5192.2   81.19  5231.5   81.60  5262.0   81.16
  5392.1   81.53  5450.4   81.31  5542.5   82.33  5678.8   84.33  5828.6   85.56
#Mann=7,-1,0
  4167.3    0.05       0  4777.0     0.1       0  4998.6    0.07       0
  5004.6     0.1       0  5113.2    0.05       0  5392.1     0.1       0
  5542.5    0.05       0
Bank Sta=4998.6,5004.6
Exp/Cntr=0.3,0.1

Type RM Length L Ch R = 1,516,354,354,354
BEGIN DESCRIPTION:
Mapping XS 9e16e5d2
END DESCRIPTION:
XS GIS Cut Line= 3
      2365309.96     13193466.73      2364385.51     13193536.17
      2363691.92     13193960.99
#Sta/Elev= 30
  3950.3   89.84  3962.6   89.76  3972.6   88.15  3992.7   86.42  4032.8   85.04
  4123.0   83.71  4240.0   83.07  4274.8   82.85  4420.6   82.58  4724.7   81.11
  4734.7   81.43  4764.8   80.68  4956.8   79.79  4984.2   79.04  4997.5   78.50
  5000.2   78.00  5003.5   78.50  5058.5   79.57  5167.9   79.37  5189.5   79.74
  5248.1   79.47  5261.7   80.11  5284.8   80.03  5296.9   80.66  5348.7   80.36
  5370.0   81.27  5445.4   82.16  5559.6   83.56  5596.3   84.54  5690.7   85.90
#Mann=9,-1,0
  3950.3    0.05       0  4240.0     0.1       0  4274.8    0.05       0
  4420.6     0.1       0  4984.2    0.05       0  4997.5    0.03       0
  5003.5    0.05       0  5189.5     0.1       0  5445.4    0.05       0
Bank Sta=4997.5,5003.5
Exp/Cntr=0.3,0.1

Type RM Length L Ch R = 1,162,0,0,0
BEGIN DESCRIPTION:
UNT046 IN BACR 1.0
END DESCRIPTION:
XS GIS Cut Line= 3
      2365310.03     13193271.41      2364185.86     13193301.80
      2363552.48     13193570.76
#Sta/Elev= 30
  3734.1   89.35  3766.4   90.22  3796.4   87.40  3988.9   84.12  4056.5   83.58
  4076.5   84.57  4157.8   83.14  4234.1   83.02  4586.7   81.06  4606.7   79.33
  4616.7   77.27  4713.8   73.10  4716.5   72.60  4719.8   73.10  4726.8   73.39
  4746.8   78.55  4756.8   78.24  4766.8   79.71  4878.4   79.02  4884.1   77.86
  4889.5   73.66  4907.8   73.47  4931.4   78.08  4943.6   78.48  4989.6   77.78
  4997.9   76.39  5052.2   78.81  5218.8   81.02  5432.5   87.48  5546.8   85.53
#Mann=6,-1,0
  3734.1    0.05       0  3988.9     0.1       0  4157.8    0.05       0
  4234.1     0.1       0  4713.8    0.07       0  4719.8     0.1       0
Bank Sta=4713.8,4719.8
Exp/Cntr=0.3,0.1

Chan Stop Cuts=-1