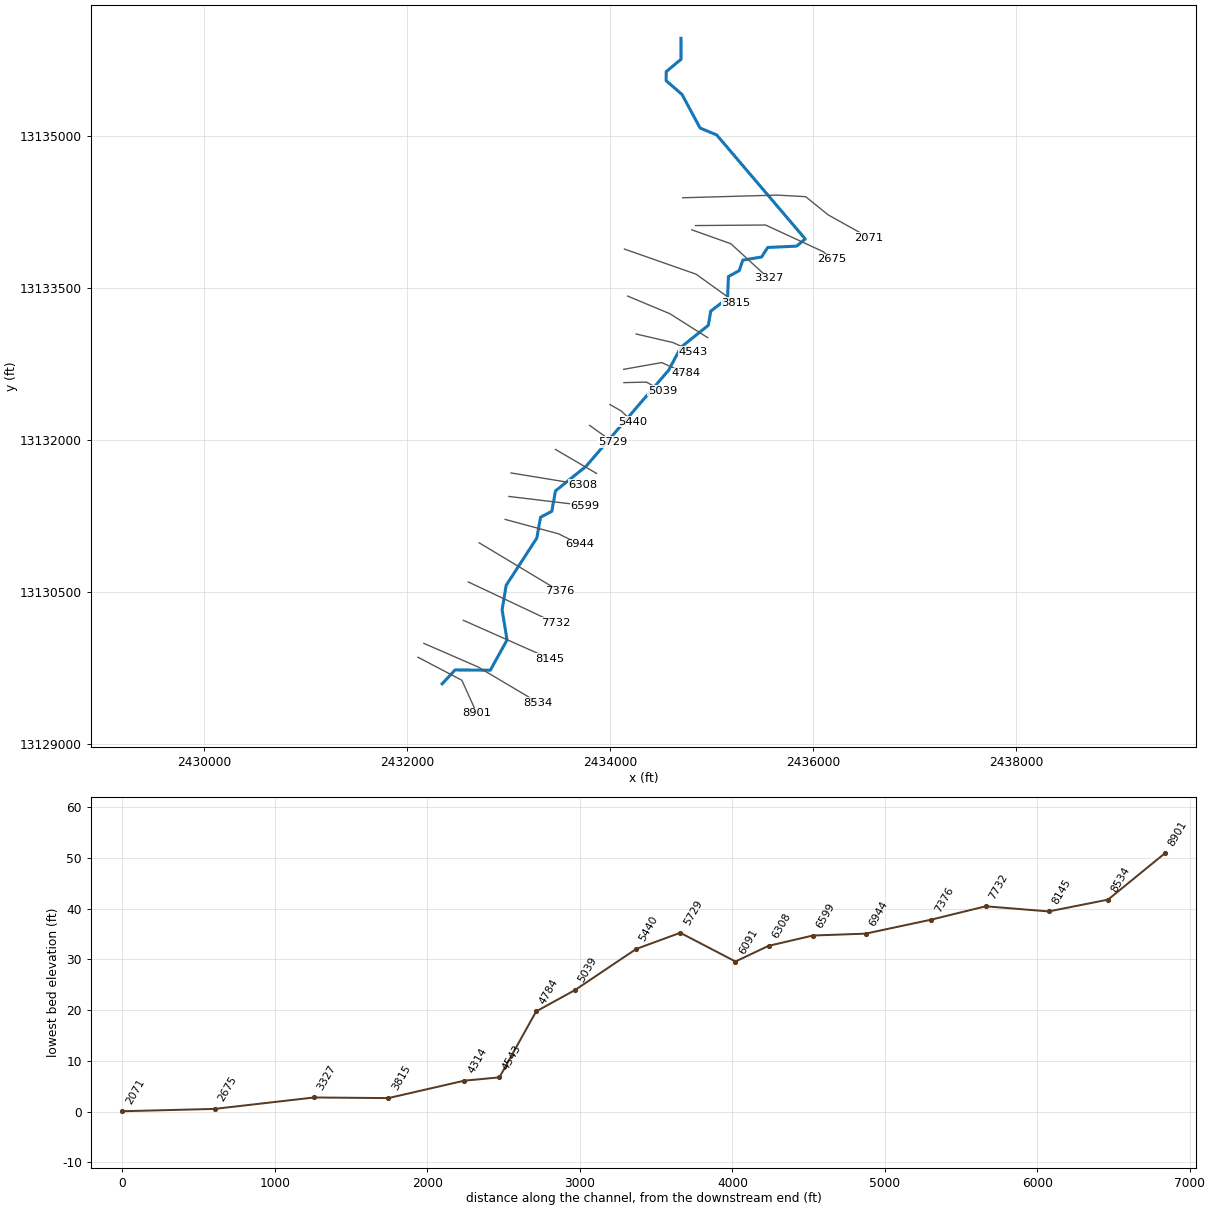
--- UNT101 IN BACR.prj (project) ---

Proj Title=UNT101 IN BACR Base Level Engineering
Current Plan=p01
Default Exp/Contr=0.3,0.1
English Units
Geom File=g01
Flow File=f01
Plan File=p01
Y Axis Title=Elevation
X Axis Title(PF)=Main Channel Distance
X Axis Title(XS)=Station
BEGIN DESCRIPTION:
UNT101 IN BACR
END DESCRIPTION:
DSS Export Rating Curves= 0
DSS Export Rating Curve Sorted= 0
DSS Export Volume Flow Curves= 0
DXF OffsetX= 0
DXF OffsetY= 0
DXF ScaleX= 1
DXF ScaleY= 10

--- UNT101 IN BACR.p01 (plan) ---

Plan Title=Multiple Run
Short Identifier=Multiple
Geom File=g01
Flow File=f01
Subcritical Flow
K Sum by GR= 0
Std Step Tol= 0.01
Critical Tol= 0.01
Num of Std Step Trials= 20
Max Error Tol= 0.3
Flow Tol Ratio= 0.001
Split Flow NTrial= 30
Split Flow Tol= 0.02
Split Flow Ratio= 0.02
Log Output Level= 0
Friction Slope Method= 1
Unsteady Friction Slope Method= 2
Unsteady Bridges Friction Slope Method= 1
Parabolic Critical Depth
Global Vel Dist=  1 , 1 , 1
Global Log Level= 0
CheckData=True
Encroach Param= -1, 0, 0, 0
BEGIN DESCRIPTION:
Multiple Run
END DESCRIPTION:

--- UNT101 IN BACR.f01 (steady flow) ---

Flow Title=Multiple
Program Version=4.10
Number of Profiles= 7
Profile Names=10-year,25-year,50-year,1pct_min,100-year,1pct_plu,500-year
River Rch & RM=UNT101 IN BACR,Reach-1         ,8901
     117     146     167     141     191     258     250
River Rch & RM=UNT101 IN BACR,Reach-1         ,8145
     233     307     365     319     431     583     606
Boundary for River Rch & Prof#=UNT101 IN BACR,Reach-1         , 1
Up Type= 0
Dn Type= 3
Dn Slope=0.005
Boundary for River Rch & Prof#=UNT101 IN BACR,Reach-1         , 2
Up Type= 0
Dn Type= 3
Dn Slope=0.005
Boundary for River Rch & Prof#=UNT101 IN BACR,Reach-1         , 3
Up Type= 0
Dn Type= 3
Dn Slope=0.005
Boundary for River Rch & Prof#=UNT101 IN BACR,Reach-1         , 4
Up Type= 0
Dn Type= 3
Dn Slope=0.005
Boundary for River Rch & Prof#=UNT101 IN BACR,Reach-1         , 5
Up Type= 0
Dn Type= 3
Dn Slope=0.005
Boundary for River Rch & Prof#=UNT101 IN BACR,Reach-1         , 6
Up Type= 0
Dn Type= 3
Dn Slope=0.005
Boundary for River Rch & Prof#=UNT101 IN BACR,Reach-1         , 7
Up Type= 0
Dn Type= 3
Dn Slope=0.005
DSS Import GetInterval= 0
DSS Import GetPeak= 0
DSS Import FillOption= 0

--- UNT101 IN BACR.g01 (geometry) ---

Geom Title=Existing Conditions
Program Version=4.10

River Reach=UNT101 IN BACR  ,Reach-1
Reach XY= 30
      2432347.72     13129596.85      2432475.03     13129733.98
       2432822.3     13129731.16      2432986.58     13130028.88
      2432938.57     13130326.86      2432977.72     13130567.31
      2433279.98     13131033.82      2433317.04     13131239.18
      2433428.15     13131298.21      2433463.87     13131498.69
       2433764.8     13131741.11      2434579.72     13132690.26
      2434698.15     13132912.88      2434970.15     13133132.52
      2434992.93     13133271.41      2435158.95     13133398.36
      2435167.63     13133612.12      2435273.97     13133670.72
       2435309.7     13133774.33      2435493.78      13133804.9
      2435555.63      13133899.3      2435838.83     13133912.32
      2435924.55     13133982.85       2435052.3     13135008.51
      2434888.46      13135076.8       2434710.4     13135408.11
      2434553.29     13135544.29      2434555.65     13135633.34
      2434700.68     13135754.64      2434700.07      13135961.1

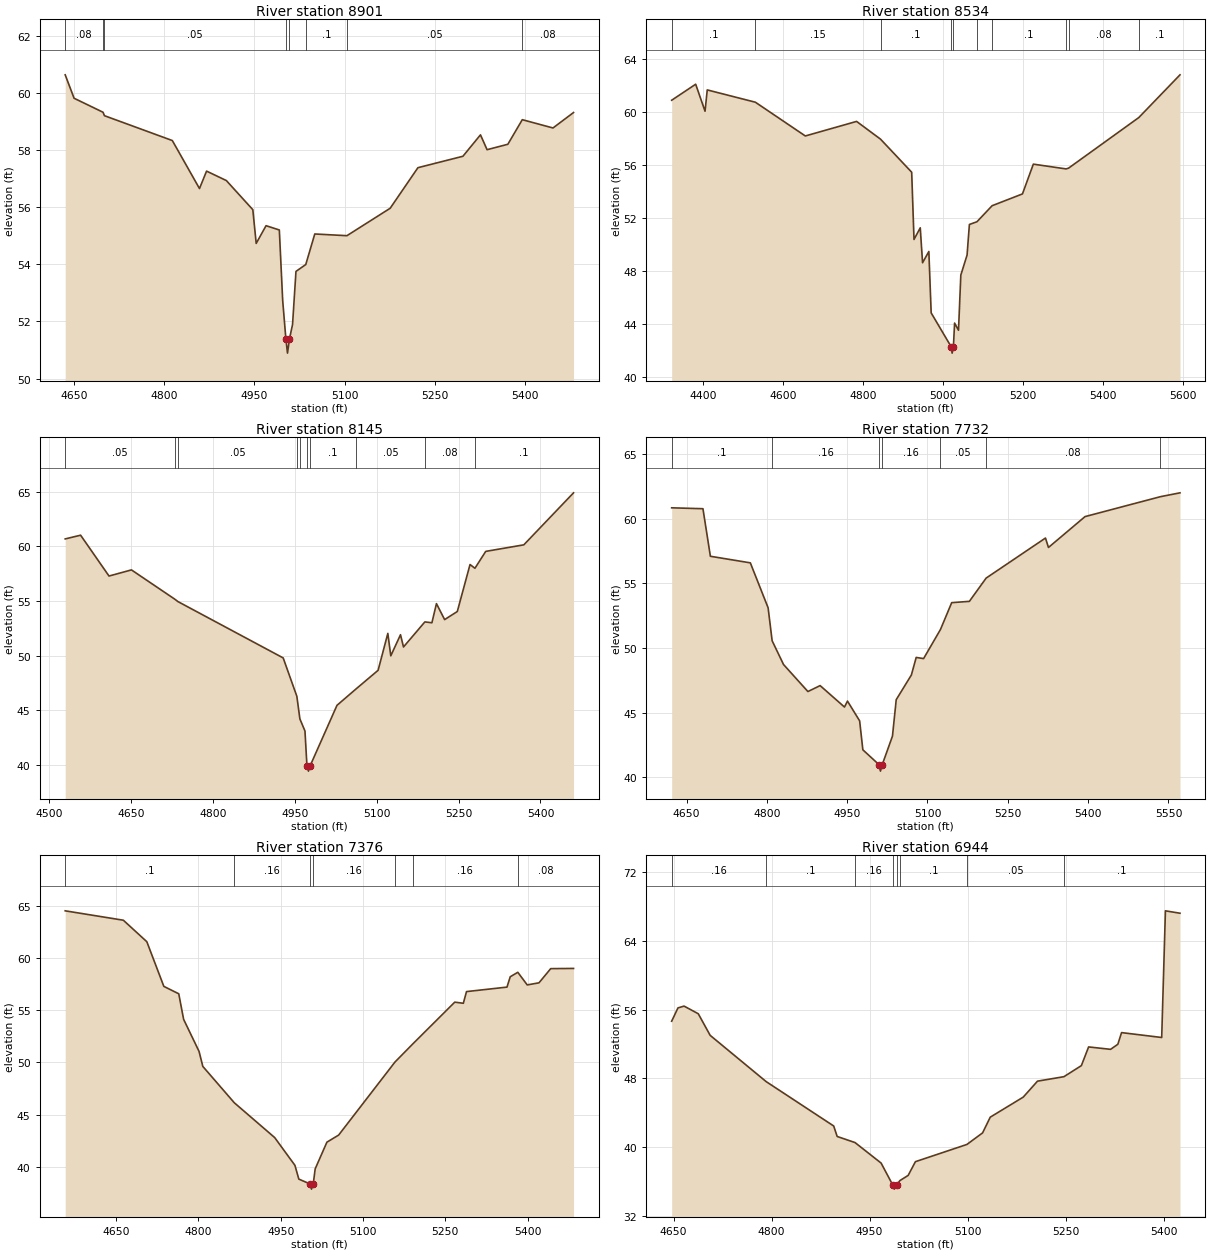
Type RM Length L Ch R = 1 ,8901    ,372,372,372
BEGIN DESCRIPTION:
UNT101 IN BACR 15.0
END DESCRIPTION:
XS GIS Cut Line= 3
      2432109.81     13129858.79      2432541.73     13129632.29
      2432689.24     13129305.66
#Sta/Elev= 30
    4635   60.63  4649.8   59.81    4698   59.32  4700.3    59.2  4813.3   58.33
  4858.5   56.65  4870.3   57.26  4903.2   56.93  4947.3   55.91  4952.9   54.73
  4969.3   55.35  4991.4    55.2    4997   52.73  5002.3   51.39    5005   50.89
  5008.3   51.39  5013.4   51.89  5019.1   53.75  5035.4   53.99  5050.4   55.06
  5103.9      55  5175.9   55.96  5222.1   57.38    5297   57.78  5326.2   58.53
  5337.2   58.01  5371.8    58.2  5395.8   59.06  5446.9   58.77  5481.1   59.31
#Mann= 8 ,-1 , 0
    4635     .08       0    4698      .1       0  4700.3     .05       0
  5002.3     .04       0  5008.3     .05       0  5035.4      .1       0
  5103.9     .05       0  5395.8     .08       0
Bank Sta=5002.3,5008.3
XS Rating Curve= 0 ,0
Exp/Cntr=0.3,0.1

Type RM Length L Ch R = 1 ,8534    ,389,389,389
BEGIN DESCRIPTION:
Mapping XS cc7bfafa
END DESCRIPTION:
XS GIS Cut Line= 3
      2432167.69     13129995.79      2432699.77     13129763.99
      2433293.22     13129412.12
#Sta/Elev= 30
    4322   60.89    4382    62.1  4405.4   60.06  4410.9   61.67  4531.2   60.74
    4656   58.19  4784.1   59.29  4843.9   57.95  4921.8   55.45  4927.6   50.37
  4943.2   51.25    4949   48.61  4964.7   49.46  4970.5   44.82  5020.1   42.28
  5022.9   41.78  5026.1   42.28    5029   44.05  5038.8   43.51  5044.6   47.68
  5060.2   49.19    5066    51.5    5085   51.71  5122.8   52.92  5198.6   53.81
  5225.8   56.06  5307.7    55.7  5313.9   55.76  5489.3   59.58  5592.3   62.81
#Mann= 10 ,-1 , 0
    4322      .1       0  4531.2     .15       0  4843.9      .1       0
  5020.1     .07       0  5026.1      .1       0    5085     .15       0
  5122.8      .1       0  5307.7     .05       0  5313.9     .08       0
  5489.3      .1       0
Bank Sta=5020.1,5026.1
XS Rating Curve= 0 ,0
Exp/Cntr=0.3,0.1

Type RM Length L Ch R = 1 ,8145    ,413,413,413
BEGIN DESCRIPTION:
Mapping XS f691ea1c
END DESCRIPTION:
XS GIS Cut Line= 2
      2432556.46      13130223.1      2433407.13     13129845.51
#Sta/Elev= 30
  4529.8   60.67    4558   61.01    4610   57.28  4651.1   57.84  4730.6   55.16
  4736.4   54.94  4928.9    49.8  4953.9    46.3  4959.5   44.23  4968.8   43.12
  4972.4   39.96  4975.2   39.46  4978.4   39.96  5027.4   45.47  5062.6   46.98
  5102.7   48.67  5120.5   52.04  5125.9   49.99  5143.7   51.92  5149.2    50.8
  5188.3   53.09  5201.2   53.01  5209.5   54.76  5224.5    53.3  5247.7   54.04
    5271   58.33    5280   57.99  5299.7   59.53  5369.5   60.13  5460.5   64.88
#Mann= 10 ,-1 , 0
  4529.8     .05       0  4730.6      .1       0  4736.4     .05       0
  4953.9     .16       0  4959.5      .1       0  4972.4     .07       0
  4978.4      .1       0  5062.6     .05       0  5188.3     .08       0
    5280      .1       0
Bank Sta=4972.4,4978.4
XS Rating Curve= 0 ,0
Exp/Cntr=0.3,0.1

Type RM Length L Ch R = 1 ,7732    ,356,356,356
BEGIN DESCRIPTION:
Mapping XS 7d133738
END DESCRIPTION:
XS GIS Cut Line= 2
      2432604.91      13130601.6      2433463.17     13130196.16
#Sta/Elev= 30
  4622.3   60.85  4680.7   60.78  4694.6    57.1  4769.2   56.59  4802.4   53.11
  4809.9   50.56  4831.2   48.72  4876.7   46.63  4899.5   47.09    4945   45.43
  4950.6   45.89  4973.3   44.36  4979.3   42.12  5009.5   40.97  5012.2   40.47
  5015.5   40.97  5034.6   43.18  5041.6      46  5069.9   47.91  5078.9   49.27
  5092.7   49.18  5124.2   51.43  5145.2   53.51  5178.2   53.61  5209.5   55.41
  5320.3   58.51  5325.9   57.78  5394.2   60.17  5534.8   61.71  5571.5   62.01
#Mann= 7 ,-1 , 0
  4622.3      .1       0  4809.9     .16       0  5009.5     .07       0
  5015.5     .16       0  5124.2     .05       0  5209.5     .08       0
  5534.8      .1       0
Bank Sta=5009.5,5015.5
XS Rating Curve= 0 ,0
Exp/Cntr=0.3,0.1

Type RM Length L Ch R = 1 ,7376    ,432,432,432
BEGIN DESCRIPTION:
Mapping XS 64a6a7ac
END DESCRIPTION:
XS GIS Cut Line= 2
      2432712.72     13130986.98      2433506.97     13130509.56
#Sta/Elev= 30
  4557.2   64.52  4663.2   63.62    4706   61.56    4737   57.28  4764.2   56.57
  4773.1   54.12  4801.2   51.05  4808.1   49.61  4865.4   46.13  4939.1   42.79
    4976   40.13  4983.1   38.81  5003.4   38.35  5006.2   37.85  5009.4   38.35
  5012.9   39.79  5034.3   42.35  5055.7   43.03  5158.4   50.03  5190.6   51.75
  5267.4   55.77    5283   55.66  5288.8   56.78  5362.6   57.21  5368.5    58.2
  5382.3   58.63  5399.5   57.42  5420.9   57.62  5442.3   58.98  5483.9      59
#Mann= 7 ,-1 , 0
  4557.2      .1       0  4865.4     .16       0  5003.4     .07       0
  5009.4     .16       0  5158.4     .05       0  5190.6     .16       0
  5382.3     .08       0
Bank Sta=5003.4,5009.4
XS Rating Curve= 0 ,0
Exp/Cntr=0.3,0.1

Type RM Length L Ch R = 1 ,6944    ,345,345,345
BEGIN DESCRIPTION:
UNT101 IN BACR 14.0
END DESCRIPTION:
XS GIS Cut Line= 3
      2432968.43     13131217.92      2433495.21     13131075.69
      2433702.77     13130971.91
#Sta/Elev= 30
  4647.2   54.66  4656.8   56.21  4666.2   56.42  4687.9   55.53  4706.1   53.01
  4791.7   47.62  4895.1   42.44  4900.4   41.22  4927.7   40.51  4967.6   38.12
  4985.3   35.58    4988   35.08  4991.3   35.58  4996.5   36.08    5009   36.68
  5020.1   38.28  5098.9   40.29  5122.9   41.64  5134.6   43.47  5185.1   45.81
  5206.9   47.67  5247.3   48.19    5274   49.48  5285.1   51.66  5318.7   51.38
  5329.8   51.97  5335.5   53.33  5396.9   52.76  5402.6   67.53  5424.9   67.25
#Mann= 8 ,-1 , 0
  4647.2     .16       0  4791.7      .1       0  4927.7     .16       0
  4985.3     .07       0  4991.3     .16       0  4996.5      .1       0
  5098.9     .05       0  5247.3      .1       0
Bank Sta=4985.3,4991.3
XS Rating Curve= 0 ,0
Exp/Cntr=0.3,0.1

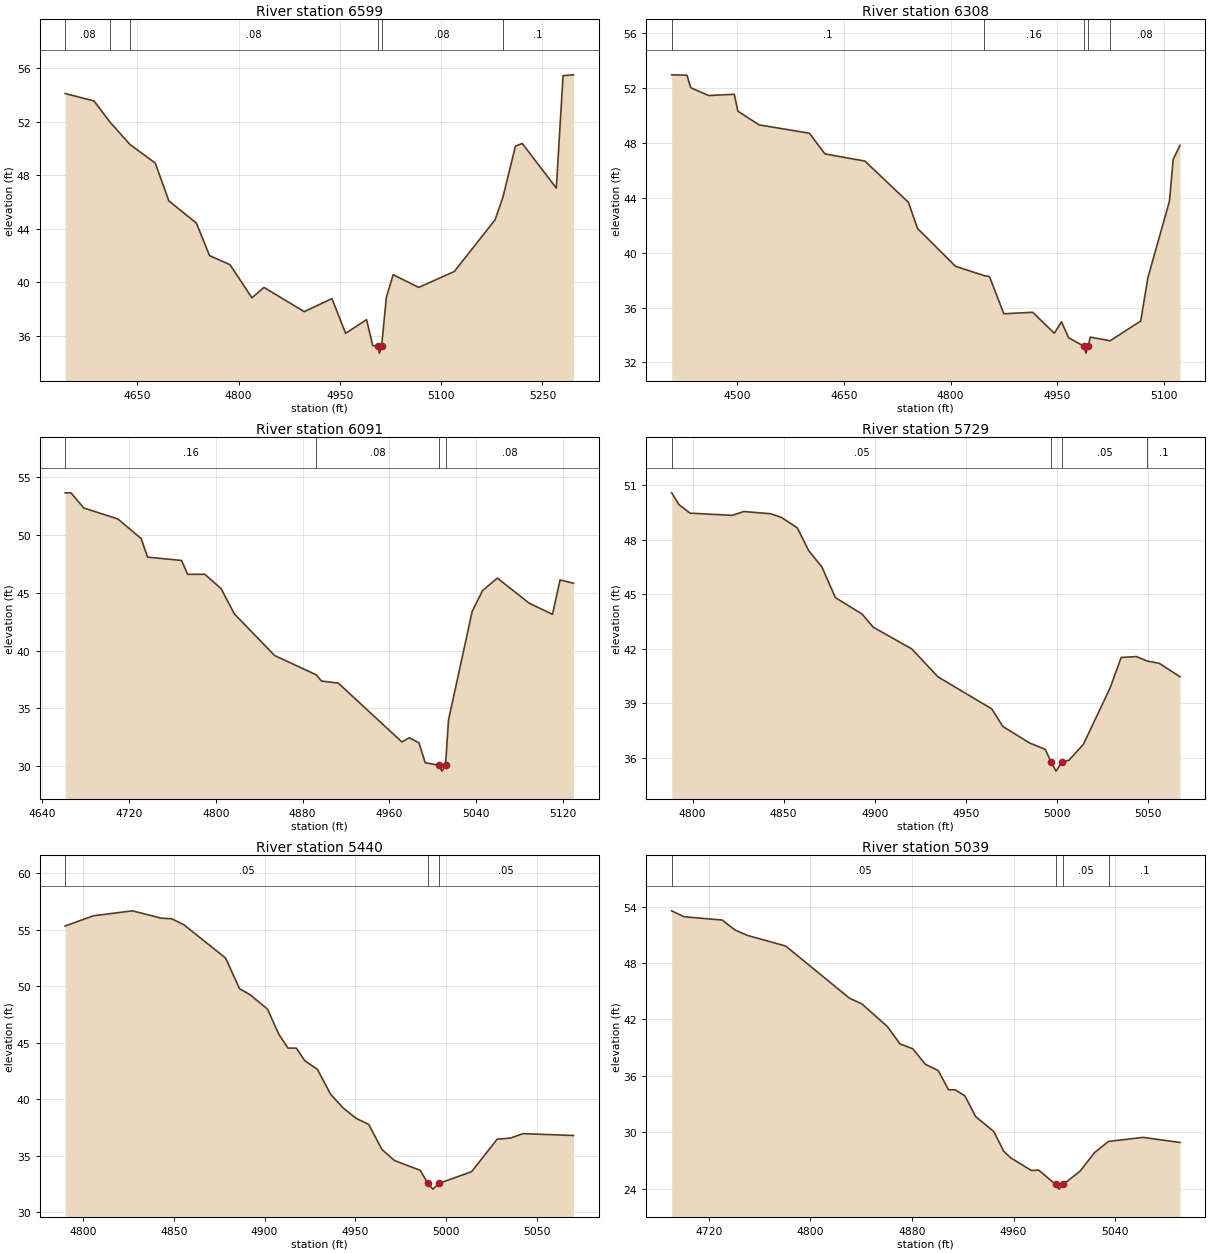
Type RM Length L Ch R = 1 ,6599    ,291,291,291
BEGIN DESCRIPTION:
Mapping XS ec270779
END DESCRIPTION:
XS GIS Cut Line= 2
      2433005.31     13131444.44      2433753.07     13131354.92
#Sta/Elev= 30
    4543    54.1  4585.7   53.55  4609.2   51.98  4639.1   50.29  4676.4   48.91
  4696.5   46.09  4737.4   44.42  4756.9   41.99  4787.1   41.32  4819.7   38.84
  4837.5   39.62  4897.1   37.81  4938.2   38.78  4958.4   36.19  4989.5   37.21
  4998.6   35.28  5005.7   35.21  5008.5   34.71  5011.7   35.21  5018.8   38.88
  5028.9   40.57  5066.8   39.62  5119.5   40.81  5179.9   44.67  5191.5   46.36
  5210.1   50.18  5220.2   50.37  5270.6   47.04  5280.6   55.44  5296.1    55.5
#Mann= 6 ,-1 , 0
    4543     .08       0  4609.2      .1       0  4639.1     .08       0
  5005.7     .07       0  5011.7     .08       0  5191.5      .1       0
Bank Sta=5005.7,5011.7
XS Rating Curve= 0 ,0
Exp/Cntr=0.3,0.1

Type RM Length L Ch R = 1 ,6308    ,217,217,217
BEGIN DESCRIPTION:
UNT101 IN BACR 13.0
END DESCRIPTION:
XS GIS Cut Line= 2
      2433026.36     13131676.23      2433732.31     13131560.32
#Sta/Elev= 30
  4407.4   52.98    4429   52.95  4434.2   52.04  4459.5   51.47  4495.5   51.56
  4500.6   50.33  4530.4   49.33  4601.3   48.72  4623.1   47.21  4679.3   46.69
  4740.6   43.68  4753.3   41.78  4806.9   39.01  4847.5   38.33  4854.7   38.26
  4874.9   35.55  4915.5   35.66  4945.9   34.13    4956   34.97  4966.1    33.8
  4987.7   33.18  4990.4   32.68  4993.7   33.18  4996.5   33.85  5024.4   33.58
  5067.5   35.02  5077.6   38.18    5108   43.77  5113.2   46.81  5122.8   47.83
#Mann= 5 ,-1 , 0
  4407.4      .1       0  4847.5     .16       0  4987.7     .07       0
  4993.7     .16       0  5024.4     .08       0
Bank Sta=4987.7,4993.7
XS Rating Curve= 0 ,0
Exp/Cntr=0.3,0.1

Type RM Length L Ch R = 1 ,6091    ,362,362,362
BEGIN DESCRIPTION:
UNT101 IN BACR 12.0
END DESCRIPTION:
XS GIS Cut Line= 2
      2433463.61     13131908.01      2433868.44     13131671.42
#Sta/Elev= 30
  4661.1   53.62  4666.4   53.62  4678.3   52.31  4709.7   51.36  4731.2   49.67
    4737   48.07  4768.4   47.78  4774.1   46.58  4789.8   46.59  4804.9   45.35
  4817.1   43.17  4854.3   39.57  4892.6   37.91  4897.5   37.37    4913   37.19
  4971.7   32.11  4978.6   32.47  4987.4   32.03  4993.2   30.32  5005.9   30.09
  5008.6   29.59  5011.9   30.09  5014.7   34.01  5036.5   43.38  5046.1   45.18
  5059.7   46.26  5089.1   44.09  5110.6   43.13  5117.6    46.1    5130   45.81
#Mann= 4 ,-1 , 0
  4661.1     .16       0  4892.6     .08       0  5005.9     .07       0
  5011.9     .08       0
Bank Sta=5005.9,5011.9
XS Rating Curve= 0 ,0
Exp/Cntr=0.3,0.1

Type RM Length L Ch R = 1 ,5729    ,289,289,289
BEGIN DESCRIPTION:
Mapping XS 916271e0
END DESCRIPTION:
XS GIS Cut Line= 2
      2433800.74     13132145.07      2434027.22     13131981.79
#Sta/Elev= 30
  4788.5   50.58  4792.5   49.93  4798.6   49.46  4821.8   49.34  4828.1   49.55
  4842.8   49.43  4848.9   49.22  4857.5   48.65  4863.7   47.41  4871.1   46.48
  4878.4   44.81  4893.1    43.9  4899.2   43.18  4920.4   41.98  4934.8   40.44
  4964.3   38.68  4970.4   37.71  4985.1    36.8  4993.7   36.45  4996.9   35.75
  4999.6   35.25  5002.9   35.75  5006.7   35.85  5014.6   36.72  5029.3   39.83
  5035.4   41.51  5043.7   41.56  5049.8   41.31  5056.3   41.19  5067.7   40.45
#Mann= 4 ,-1 , 0
  4788.5     .05       0  4996.9     .03       0  5002.9     .05       0
  5049.8      .1       0
Bank Sta=4996.9,5002.9
XS Rating Curve= 0 ,0
Exp/Cntr=0.3,0.1

Type RM Length L Ch R = 1 ,5440    ,401,401,401
BEGIN DESCRIPTION:
UNT101 IN BACR 11.0
END DESCRIPTION:
XS GIS Cut Line= 3
      2434000.95     13132350.49      2434111.55     13132287.29
      2434222.21      13132181.9
#Sta/Elev= 30
  4790.1   55.31  4805.6   56.21  4827.2   56.65    4843      56  4848.8   55.95
  4855.5   55.42  4878.5   52.48  4886.2   49.77    4892   49.24  4901.6   47.97
  4907.8   45.76  4912.9   44.52  4917.5   44.52  4922.2    43.4  4929.1   42.65
  4936.4   40.44  4943.3   39.23  4950.5   38.31  4957.4   37.78  4964.7   35.56
  4971.6   34.59  4985.8   33.72    4990   32.56  4992.8   32.06    4996   32.56
  5014.1    33.6  5028.2   36.47  5035.5   36.57  5042.4   36.96  5070.3    36.8
#Mann= 3 ,-1 , 0
  4790.1     .05       0    4990     .03       0    4996     .05       0
Bank Sta=4990,4996
XS Rating Curve= 0 ,0
Exp/Cntr=0.3,0.1

Type RM Length L Ch R = 1 ,5039    ,255,255,255
BEGIN DESCRIPTION:
UNT101 IN BACR 10.0
END DESCRIPTION:
XS GIS Cut Line= 3
       2434137.9     13132566.49      2434359.14     13132571.76
      2434517.17     13132487.48
#Sta/Elev= 30
  4690.7   53.55  4700.5   52.92  4730.5   52.57  4740.5   51.52  4750.5   50.93
  4780.5   49.81  4830.6   44.28  4840.6   43.65  4860.6   41.25  4870.6    39.4
  4880.6   38.89  4890.6   37.23  4900.6   36.58  4908.8   34.53    4914   34.53
  4921.7   33.88  4930.2   31.67  4944.4    30.1  4952.2   28.01  4957.8   27.29
  4974.1   25.95  4979.8   25.99  4993.1   24.47  4995.8   23.97  4999.1   24.47
  5012.4   25.88  5023.7   27.84  5034.8   29.04    5062   29.47  5091.1   28.93
#Mann= 4 ,-1 , 0
  4690.7     .05       0  4993.1     .03       0  4999.1     .05       0
  5034.8      .1       0
Bank Sta=4993.1,4999.1
XS Rating Curve= 0 ,0
Exp/Cntr=0.3,0.1

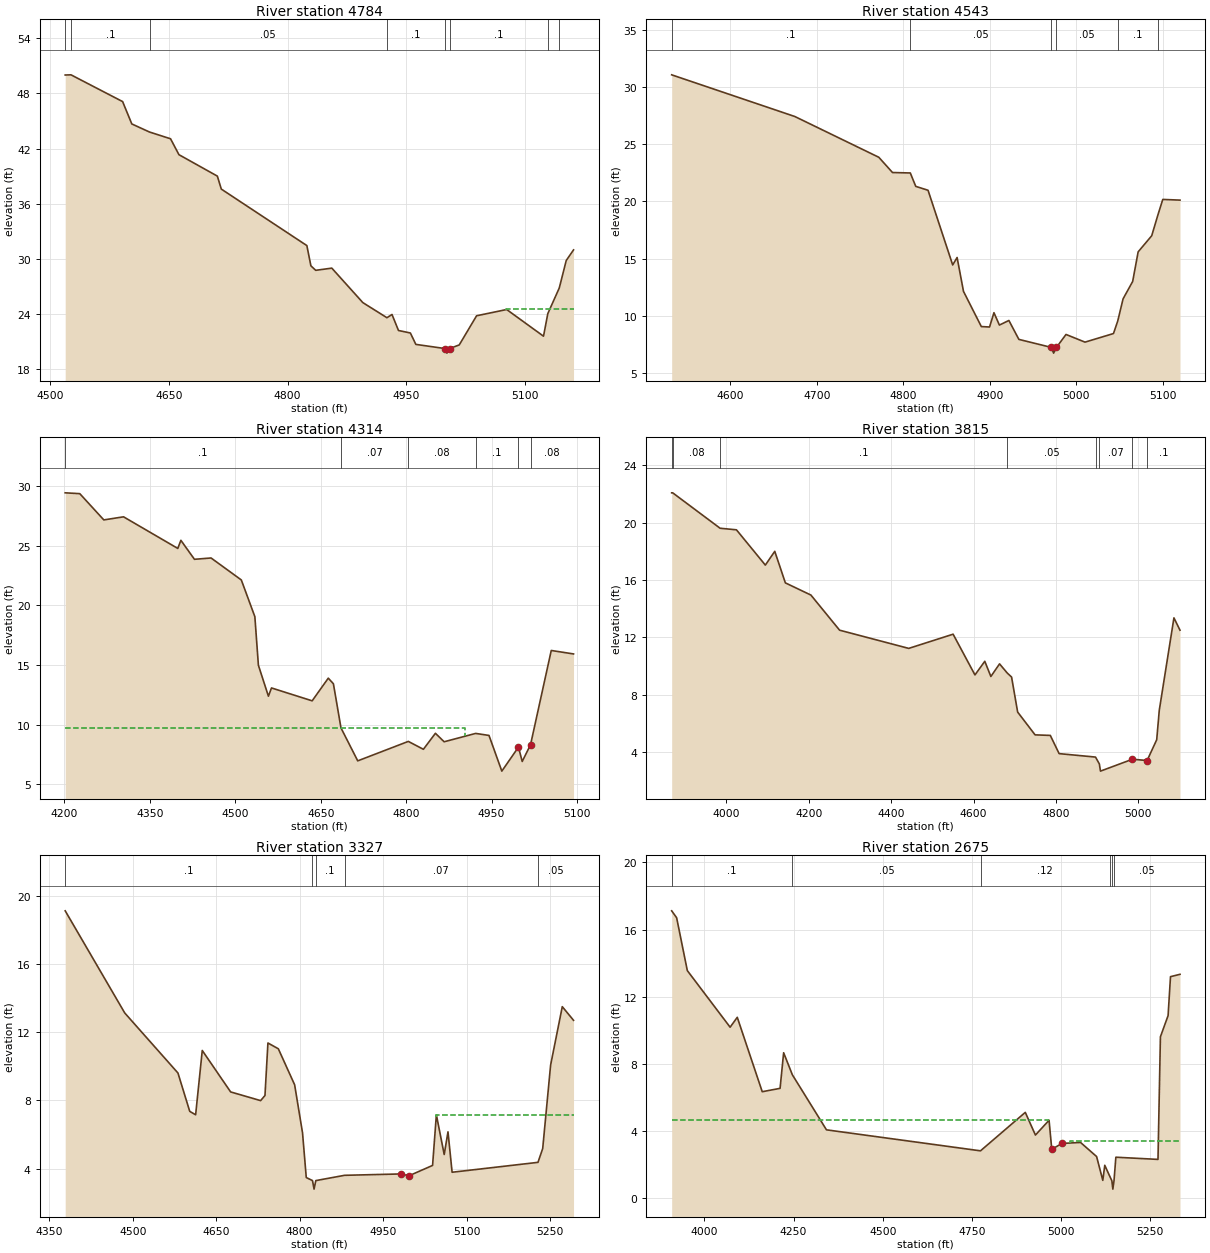
Type RM Length L Ch R = 1 ,4784    ,241,241,241
BEGIN DESCRIPTION:
Mapping XS b028b3bb
END DESCRIPTION:
XS GIS Cut Line= 3
      2434136.33     13132697.77      2434510.02     13132764.17
      2434749.56     13132657.42
#Sta/Elev= 30
  4519.3   49.99  4526.6   50.01  4591.8    47.1  4603.4   44.67  4625.8   43.79
  4652.3   43.06  4662.9   41.33  4711.4      39  4716.4   37.59  4824.4   31.45
  4829.5   29.25  4835.6   28.76  4855.9      29  4895.1   25.25  4925.5   23.61
  4931.9   23.96  4940.1   22.22  4955.1   21.95    4962   20.71  4998.6   20.26
  5001.3   19.76  5004.6   20.26  5016.8   20.65  5038.7   23.82  5076.7    24.5
  5123.2    21.6  5128.6   24.05  5143.1   26.84  5151.9   29.83  5161.1   30.98
#Mann= 8 ,-1 , 0
  4519.3     .05       0  4526.6      .1       0  4625.8     .05       0
  4925.5      .1       0  4998.6     .07       0  5004.6      .1       0
  5128.6     .05       0  5143.1      .1       0
#XS Ineff= 2 , 0
                         5076.31           24.56
Permanent Ineff=
       F       F
Bank Sta=4998.6,5004.6
XS Rating Curve= 0 ,0
Exp/Cntr=0.3,0.1

Type RM Length L Ch R = 1 ,4543    ,229,229,229
BEGIN DESCRIPTION:
UNT101 IN BACR 9.0
END DESCRIPTION:
XS GIS Cut Line= 3
      2434259.01     13133045.88      2434622.53     13132961.58
      2434817.47     13132872.02
#Sta/Elev= 30
  4532.2   31.06  4674.6   27.42  4771.7   23.86  4787.5   22.53  4808.1   22.49
  4814.4   21.32  4828.6   20.98  4857.1   14.46  4862.2   15.11  4869.6   12.15
  4890.2    9.08  4899.7    9.04  4904.8   10.29  4911.1    9.21  4922.1    9.61
  4933.6    7.96  4971.1    7.26  4973.8    6.76  4977.1    7.26  4988.1    8.39
  5010.1    7.72    5043    8.47  5047.9    9.56  5054.1    11.5  5065.2   13.02
  5071.5    15.6  5087.2   17.01  5094.3   18.81    5100   20.18  5119.9   20.12
#Mann= 6 ,-1 , 0
  4532.2      .1       0  4808.1     .05       0  4971.1     .04       0
  4977.1     .05       0  5047.9      .1       0  5094.3     .05       0
Bank Sta=4971.1,4977.1
XS Rating Curve= 0 ,0
Exp/Cntr=0.3,0.1

Type RM Length L Ch R = 1 ,4314    ,499,499,499
BEGIN DESCRIPTION:
UNT101 IN BACR 8.0
END DESCRIPTION:
XS GIS Cut Line= 3
      2434174.75     13133419.89      2434590.93     13133246.04
      2434963.81     13133009.71
#Sta/Elev= 30
  4201.4   29.44    4227   29.37  4269.2   27.17  4303.8   27.43  4399.1   24.78
  4404.5   25.46  4428.3   23.87  4457.5   23.98  4510.6   22.14  4534.4   19.06
  4540.6   14.99  4558.2    12.4  4563.6   13.09    4635   12.01  4663.3   13.91
  4672.3   13.44  4685.6    9.74    4715    6.98  4803.8    8.61  4830.3    7.95
  4851.4    9.29  4866.7    8.58  4922.1    9.28  4945.5    9.11    4968    6.12
  4997.2    8.13  5003.8    6.93  5018.4    8.33  5054.8   16.23  5093.9   15.94
#Mann= 6 ,-1 , 0
  4201.4      .1       0  4685.6     .07       0  4803.8     .08       0
  4922.1      .1       0  4997.2     .07       0  5018.4     .08       0
#XS Ineff= 2 , 0
         4903.02     9.7
Permanent Ineff=
       F       F
Bank Sta=4997.2,5018.4
XS Rating Curve= 0 ,0
Exp/Cntr=0.3,0.1

Type RM Length L Ch R = 1 ,3815    ,488,488,488
BEGIN DESCRIPTION:
UNT101 IN BACR 7.0
END DESCRIPTION:
XS GIS Cut Line= 3
      2434143.19     13133883.44      2434849.05     13133635.87
      2435243.12     13133352.14
#Sta/Elev= 30
  3867.3   22.09  3869.8   22.09  3984.8   19.62  4024.5   19.51  4094.6   17.05
  4117.5   18.01  4143.2   15.81  4205.2   14.96  4274.8   12.51  4442.6   11.24
  4550.3   12.23  4603.3    9.39  4627.2   10.34  4641.9    9.28    4663   10.16
  4681.4    9.53  4692.2    9.24  4706.9     6.8  4749.2    5.21  4786.2    5.17
  4807.6     3.9  4895.9    3.66  4905.2    3.18  4907.9    2.68  4985.5    3.51
  5021.1    3.42  5044.4    4.87  5050.6    6.92  5086.2   13.37  5100.9   12.51
#Mann= 8 ,-1 , 0
  3867.3      .1       0  3869.8     .08       0  3984.8      .1       0
  4681.4     .05       0  4895.9     .07       0  4905.2     .07       0
  4985.5     .07       0  5021.1      .1       0
Bank Sta=4985.5,5021.1
XS Rating Curve= 0 ,0
Exp/Cntr=0.3,0.1

Type RM Length L Ch R = 1 ,3327    ,652,652,652
BEGIN DESCRIPTION:
UNT101 IN BACR 6.0
END DESCRIPTION:
XS GIS Cut Line= 3
      2434806.88     13134073.11      2435191.46     13133936.13
      2435564.13     13133594.96
#Sta/Elev= 30
  4378.7   19.12  4485.7   13.13  4581.3    9.61  4602.5    7.36  4613.1    7.16
    4625   10.93    4676     8.5  4729.9    7.99  4737.7    8.29    4743   11.37
  4761.7   11.03    4791    8.92  4805.2     6.1  4811.9    3.48  4823.1     3.3
  4825.9     2.8  4829.1     3.3  4880.8    3.61  4982.1    3.69  4996.3    3.58
  5038.9    4.19  5045.7    7.16  5059.8    4.83  5066.6    6.16    5074    3.79
  5228.3    4.37  5236.8    5.18    5251   10.07    5272    13.5  5292.2    12.7
#Mann= 5 ,-1 , 0
  4378.7      .1       0  4823.1     .07       0  4829.1      .1       0
  4880.8     .07       0  5228.3     .05       0
#XS Ineff= 2 , 0
                         5045.45            7.14
Permanent Ineff=
       F       F
Bank Sta=4982.1,4996.3
XS Rating Curve= 0 ,0
Exp/Cntr=0.3,0.1

Type RM Length L Ch R = 1 ,2675    ,604,604,604
BEGIN DESCRIPTION:
UNT101 IN BACR 5.0
END DESCRIPTION:
XS GIS Cut Line= 4
      2434843.78     13134115.24      2435533.87     13134120.51
       2436102.8     13133857.12      2436181.79     13133783.39
#Sta/Elev= 30
  3908.3   17.12  3922.2   16.71  3952.2   13.56  4072.2   10.19  4092.2   10.78
  4162.2    6.35  4212.2    6.55  4222.2    8.67  4246.6    7.36  4342.3    4.08
  4774.1    2.83  4899.7    5.12  4928.1    3.77  4966.3    4.65  4973.9    2.92
  5002.4    3.27  5054.5    3.33  5099.6    2.49    5117    1.07  5122.5    1.97
  5136.6    1.31  5142.4    1.05  5145.1     .55  5148.4    1.05  5153.6    2.45
  5271.7    2.32  5278.5    9.62    5300   10.88  5306.8    13.2  5333.4   13.34
#Mann= 6 ,-1 , 0
  3908.3      .1       0  4246.6     .05       0  4774.1     .12       0
  5136.6     .05       0  5142.4     .07       0  5148.4     .05       0
#XS Ineff= 2 , 0
         4966.36    4.66 5024.55             3.4
Permanent Ineff=
       F       F
Bank Sta=4973.9,5002.4
XS Rating Curve= 0 ,0
Exp/Cntr=0.3,0.1

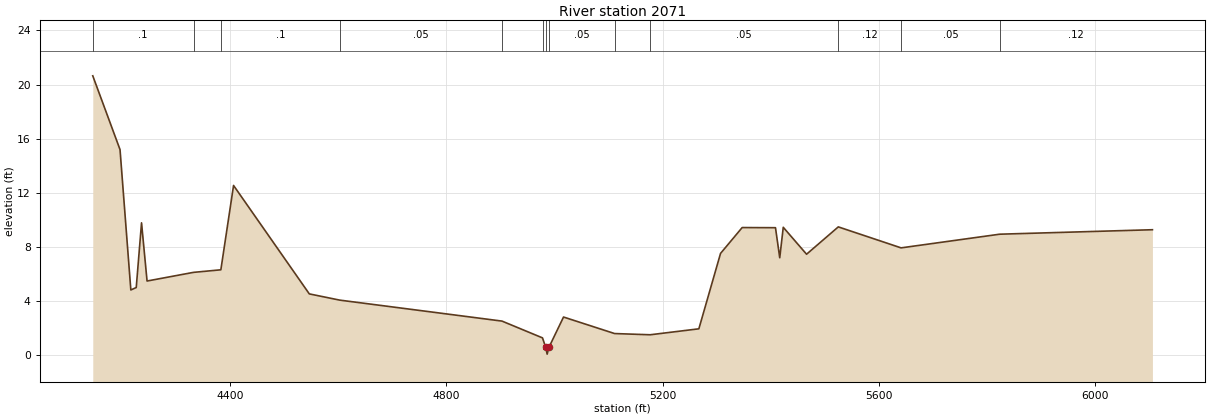
Type RM Length L Ch R = 1 ,2071    ,0,0,0
BEGIN DESCRIPTION:
UNT101 IN BACR 1.0
END DESCRIPTION:
XS GIS Cut Line= 5
      2434717.38     13134389.17      2435649.77     13134415.51
      2435928.96     13134399.71      2436150.21      13134220.6
      2436554.31     13133994.93
#Sta/Elev= 30
  4146.1   20.65  4196.5    15.2  4216.5    4.83  4226.5    5.01  4236.3    9.79
  4246.5    5.49  4332.4    6.13    4383    6.32  4406.5   12.55  4546.6    4.54
  4602.8    4.08    4903    2.53  4977.9    1.29  4983.8     .59  4986.5     .09
  4989.8     .59  5016.8    2.83  5111.2    1.61  5177.1    1.52  5267.1    1.96
  5307.2    7.53  5347.2    9.44  5408.8    9.43  5416.7    7.21  5423.2    9.46
  5466.3    7.47    5525    9.49  5641.1    7.94  5823.6    8.95    6106    9.28
#Mann= 13 ,-1 , 0
  4146.1      .1       0  4332.4     .05       0    4383      .1       0
  4602.8     .05       0    4903     .07       0  4977.9     .05       0
  4983.8     .03       0  4989.8     .05       0  5111.2     .07       0
  5177.1     .05       0    5525     .12       0  5641.1     .05       0
  5823.6     .12       0
Bank Sta=4983.8,4989.8
XS Rating Curve= 0 ,0
Exp/Cntr=0.3,0.1

Chan Stop Cuts=-1
Use User Specified Reach Order=0
Composite Channel Slope=5