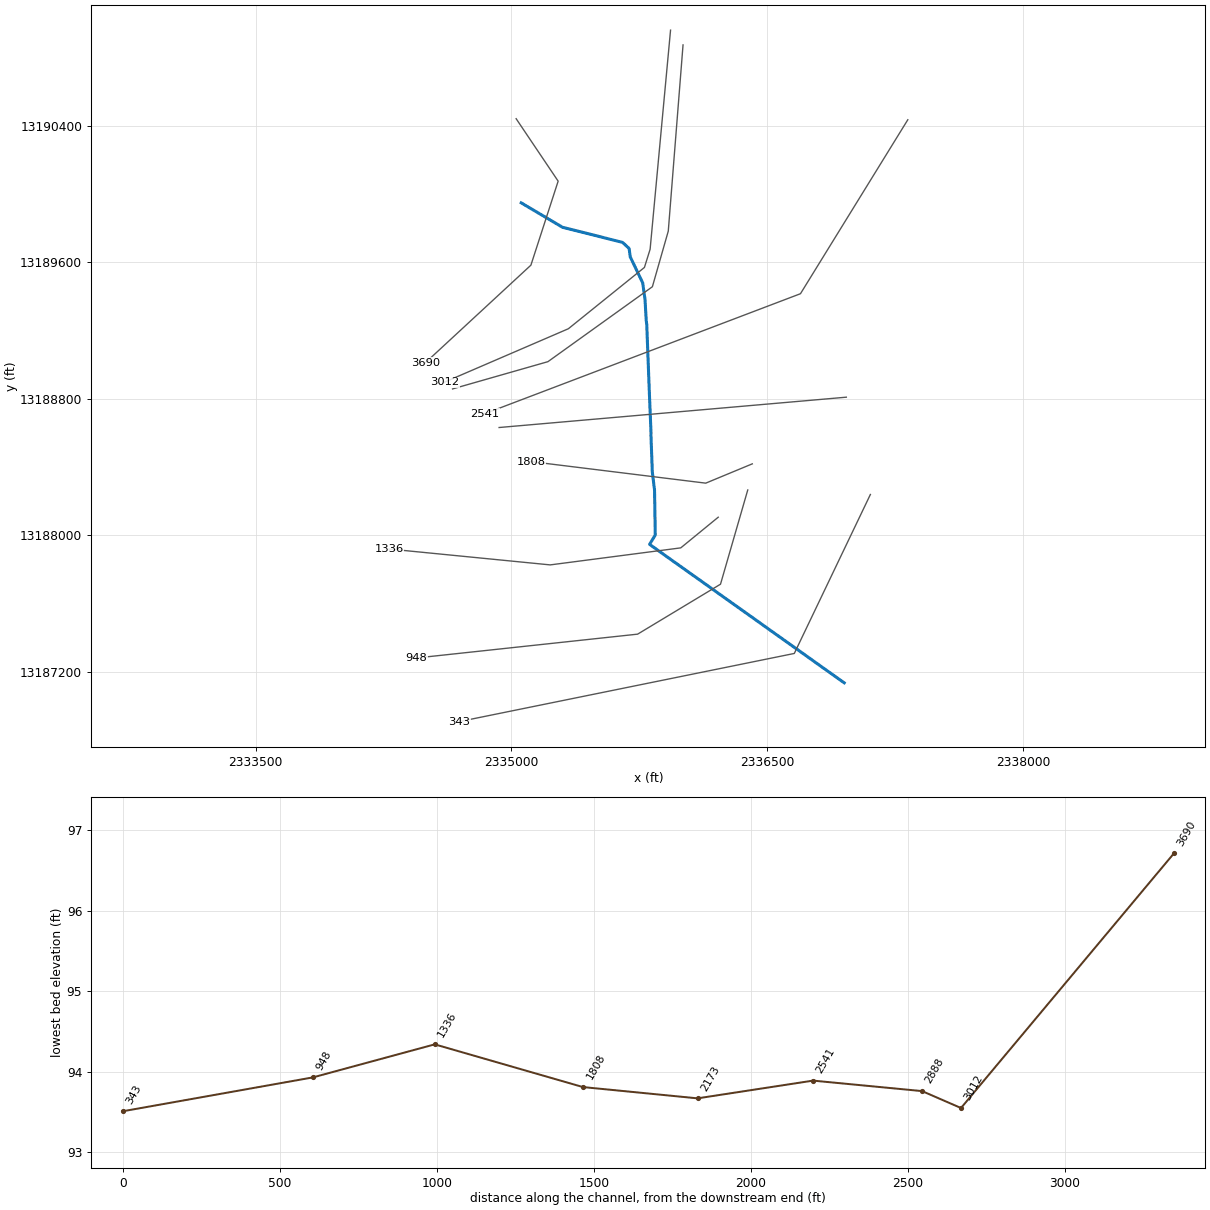
--- UNT104 IN BACR.prj (project) ---

Proj Title=UNT104 IN BACR Base Level Engineering
Current Plan=p01
Default Exp/Contr=0.3,0.1
English Units
Geom File=g01
Flow File=f01
Plan File=p01
BEGIN DESCRIPTION:
UNT104 IN BACR
END DESCRIPTION:

--- UNT104 IN BACR.p01 (plan) ---

Plan Title=Multiple Run
Short Identifier=Multiple
Geom File=g01
Flow File=f01
Subcritical Flow
K Sum by GR= 0
Std Step Tol= 0.01
Critical Tol= 0.01
Num of Std Step Trials= 20
Max Error Tol= 0.3
Flow Tol Ratio= 0.001
Split Flow NTrial= 30
Split Flow Tol= 0.02
Split Flow Ratio= 0.02
Log Output Level= 0
Friction Slope Method= 1
Unsteady Friction Slope Method= 2
Unsteady Bridges Friction Slope Method= 1
Parabolic Critical Depth
Global Vel Dist=  1 , 1 , 1
Global Log Level= 0
CheckData=True
Encroach Param= -1, 0, 0, 0
BEGIN DESCRIPTION:
Multiple Run
END DESCRIPTION:

--- UNT104 IN BACR.f01 (steady flow) ---

Flow Title=Multiple
Number of Profiles=7
Profile Names=10-year,25-year,50-year,1pct_min,100-year,1pct_plu,500-year
River Rch & RM= UNT104 IN BACR,Reach-1,3690
     643     897    1106     995    1345    1819    1997
River Rch & RM= UNT104 IN BACR,Reach-1,1336
     672     939    1159    1043    1410    1907    2096
Boundary for River Rch & Prof#=UNT104 IN BACR,Reach-1,1
Up Type=0
Dn Type=3
Dn Slope=0.005
Boundary for River Rch & Prof#=UNT104 IN BACR,Reach-1,2
Up Type=0
Dn Type=3
Dn Slope=0.005
Boundary for River Rch & Prof#=UNT104 IN BACR,Reach-1,3
Up Type=0
Dn Type=3
Dn Slope=0.005
Boundary for River Rch & Prof#=UNT104 IN BACR,Reach-1,4
Up Type=0
Dn Type=3
Dn Slope=0.005
Boundary for River Rch & Prof#=UNT104 IN BACR,Reach-1,5
Up Type=0
Dn Type=3
Dn Slope=0.005
Boundary for River Rch & Prof#=UNT104 IN BACR,Reach-1,6
Up Type=0
Dn Type=3
Dn Slope=0.005
Boundary for River Rch & Prof#=UNT104 IN BACR,Reach-1,7
Up Type=0
Dn Type=3
Dn Slope=0.005

--- UNT104 IN BACR.g01 (geometry) ---

Geom Title=Existing Conditions

River Reach=UNT104 IN BACR,Reach-1
Reach XY= 19
      2335057.50     13189949.46      2335300.07     13189806.00
      2335508.74     13189753.83      2335652.20     13189717.32
      2335684.87     13189686.92      2335690.58     13189681.29
      2335696.45     13189633.76      2335769.68     13189480.61
      2335783.57     13189381.65      2335790.52     13189258.43
      2335793.70     13189234.99      2335808.17     13188854.21
      2335818.59     13188601.89      2335818.37     13188585.03
      2335826.24     13188370.99      2335839.26     13188265.38
      2335843.60     13188002.07      2335810.20     13187947.09
      2336951.33     13187135.27

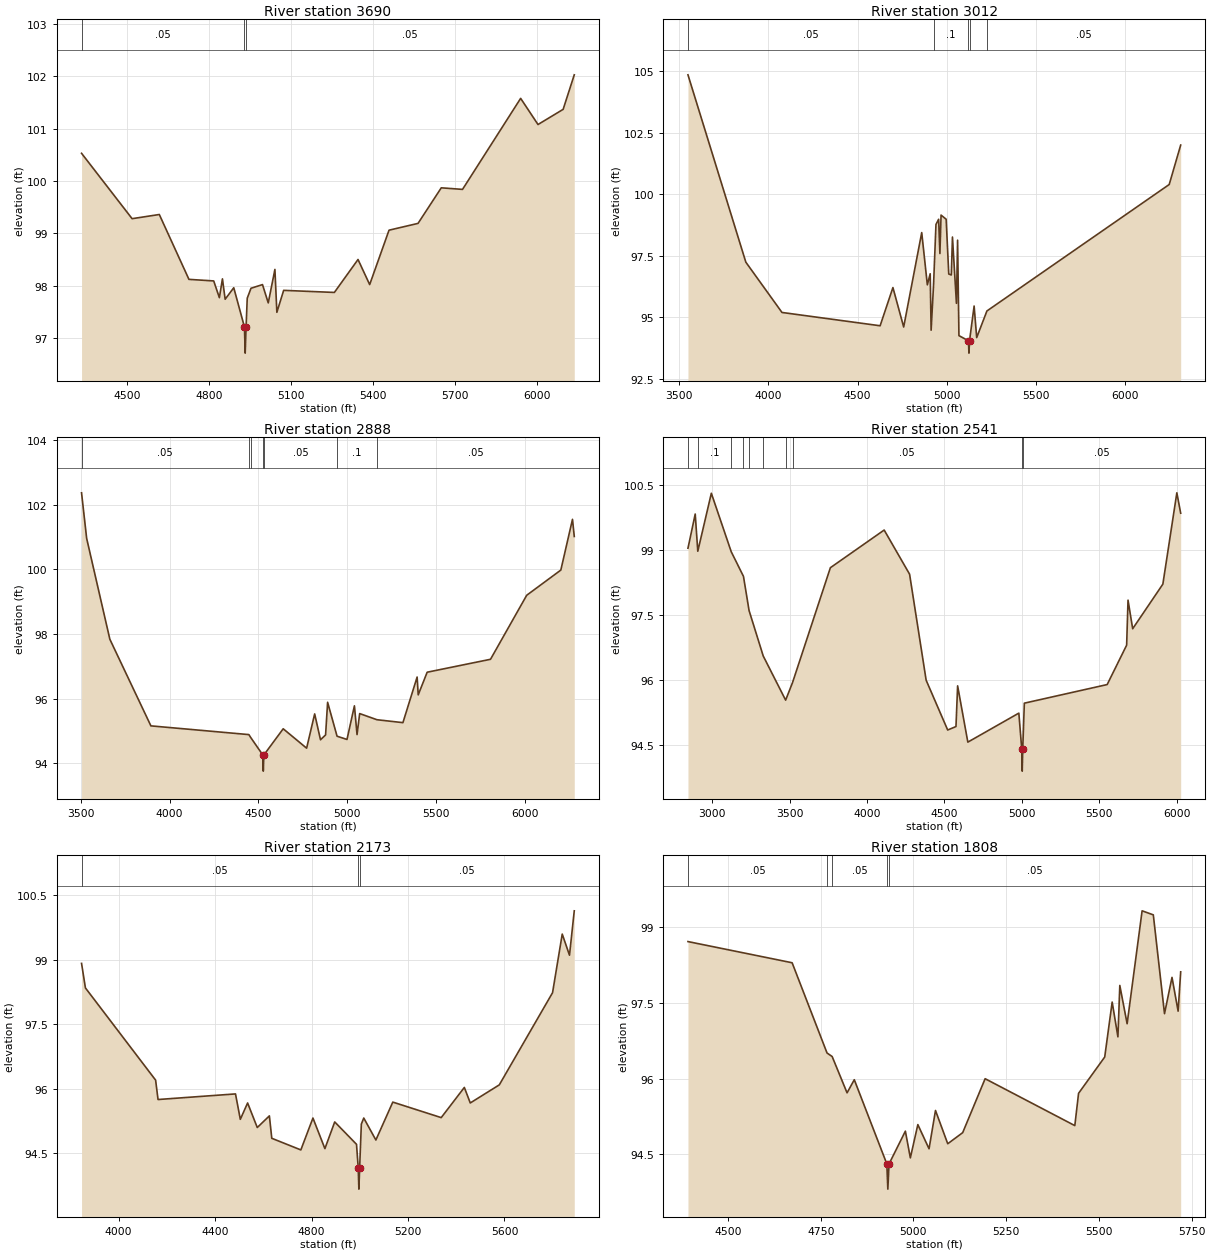
Type RM Length L Ch R = 1,3690,678,678,678
BEGIN DESCRIPTION:
UNT104 IN BACR 6.0
END DESCRIPTION:
XS GIS Cut Line= 4
      2335027.87     13190442.80      2335274.17     13190076.68
      2335114.41     13189584.10      2334495.47     13189011.75
#Sta/Elev= 30
  4333.5  100.53  4518.4   99.28  4617.9   99.36  4726.3   98.12  4816.9   98.09
  4837.6   97.77  4848.8   98.13  4858.7   97.74  4890.2   97.96  4929.3   97.21
  4932.0   96.71  4935.3   97.21  4939.5   97.76  4953.3   97.95  4995.3   98.02
  5016.4   97.67  5040.7   98.31  5047.9   97.49  5072.7   97.91  5258.2   97.87
  5344.7   98.50  5387.3   98.02  5458.1   99.06  5564.2   99.19  5649.2   99.87
  5726.9   99.84  5939.5  101.58  6003.0  101.08  6094.9  101.37  6135.6  102.03
#Mann=3,-1,0
  4333.5    0.05       0  4929.3   0.035       0  4935.3    0.05       0
Bank Sta=4929.3,4935.3
Exp/Cntr=0.3,0.1

Type RM Length L Ch R = 1,3012,124,124,124
BEGIN DESCRIPTION:
UNT104 IN BACR 5.0
END DESCRIPTION:
XS GIS Cut Line= 5
      2335933.16     13190962.03      2335813.34     13189677.29
      2335780.06     13189570.79      2335334.08     13189211.34
      2334608.55     13188898.50
#Sta/Elev= 30
  3548.5  104.84  3873.2   97.24  4076.0   95.20  4626.7   94.66  4698.6   96.21
  4758.9   94.61  4860.2   98.44  4891.7   96.32  4907.7   96.77  4912.9   94.48
  4926.5   96.31  4940.1   98.77  4955.1   98.98  4962.2   97.59  4968.7   99.15
  4997.4   98.98  5011.8   96.76  5026.2   96.72  5032.6   98.26  5055.0   95.57
  5061.4   98.13  5069.0   94.26  5122.4   94.05  5125.1   93.55  5128.4   94.05
  5154.2   95.46  5168.6   94.18  5226.0   95.26  6248.9  100.39  6313.3  101.99
#Mann=5,-1,0
  3548.5    0.05       0  4926.5     0.1       0  5122.4    0.07       0
  5128.4     0.1       0  5226.0    0.05       0
Bank Sta=5122.4,5128.4
Exp/Cntr=0.3,0.1

Type RM Length L Ch R = 1,2888,347,347,347
BEGIN DESCRIPTION:
Mapping XS d7071b8a
END DESCRIPTION:
XS GIS Cut Line= 5
      2336006.38     13190875.45      2335919.85     13189783.80
      2335826.66     13189457.63      2335214.26     13189018.30
      2334655.11     13188858.55
#Sta/Elev= 30
  3505.6  102.37  3534.3  100.96  3664.7   97.84  3895.4   95.16  4446.1   94.89
  4456.5   94.80  4524.4   94.26  4527.1   93.76  4530.4   94.26  4639.1   95.07
  4770.7   94.47  4815.9   95.53  4848.7   94.73  4877.3   94.88  4888.7   95.89
  4941.8   94.84  4997.6   94.74  5039.4   95.78  5054.1   94.89  5068.9   95.54
  5166.3   95.35  5312.0   95.26  5391.8   96.67  5398.0   96.12  5448.3   96.82
  5804.4   97.22  6007.7   99.20  6199.6   99.98  6265.1  101.55  6275.1  101.02
#Mann=7,-1,0
  3505.6    0.05       0  4446.1     0.1       0  4456.5    0.05       0
  4524.4    0.07       0  4530.4    0.05       0  4941.8     0.1       0
  5166.3    0.05       0
Bank Sta=4524.4,4530.4
Exp/Cntr=0.3,0.1

Type RM Length L Ch R = 1,2541,368,368,368
BEGIN DESCRIPTION:
UNT104 IN BACR 4.0
END DESCRIPTION:
XS GIS Cut Line= 3
      2337324.19     13190436.68      2336694.85     13189416.72
      2334841.61     13188712.27
#Sta/Elev= 30
  2843.9   99.04  2890.7   99.83  2907.3   98.97  2994.8  100.31  3123.1   98.96
  3202.2   98.39  3238.4   97.60  3329.8   96.55  3474.5   95.53  3519.4   95.94
  3763.4   98.59  4110.6   99.46  4274.7   98.44  4381.7   95.99  4520.7   94.84
  4574.2   94.92  4584.9   95.86  4650.8   94.56  4980.1   95.23  4999.1   94.39
  5001.9   93.89  5005.1   94.39  5015.6   95.46  5550.4   95.89  5676.1   96.80
  5685.0   97.84  5715.1   97.18  5909.9   98.21  6000.2  100.32  6025.0   99.85
#Mann=10,-1,0
  2843.9    0.16       0  2907.3     0.1       0  3123.1    0.05       0
  3202.2     0.1       0  3238.4    0.16       0  3329.8    0.05       0
  3474.5     0.1       0  3519.4    0.05       0  4999.1    0.03       0
  5005.1    0.05       0
Bank Sta=4999.1,5005.1
Exp/Cntr=0.3,0.1

Type RM Length L Ch R = 1,2173,365,365,365
BEGIN DESCRIPTION:
Mapping XS e58999e5
END DESCRIPTION:
XS GIS Cut Line= 2
      2336963.76     13188810.10      2334928.02     13188632.23
#Sta/Elev= 30
  3846.0   98.91  3862.1   98.34  4153.2   96.20  4163.2   95.75  4484.5   95.88
  4504.5   95.29  4534.7   95.67  4574.8   95.10  4625.0   95.37  4635.0   94.85
  4755.5   94.58  4805.7   95.32  4855.3   94.61  4896.0   95.23  4986.4   94.71
  4993.4   94.17  4996.2   93.67  4999.4   94.17  5006.4   95.18  5016.5   95.32
  5066.7   94.81  5136.9   95.69  5337.7   95.33  5433.6   96.03  5458.2   95.67
  5578.6   96.09  5799.5   98.23  5839.6   99.59  5869.7   99.10  5889.5  100.13
#Mann=3,-1,0
  3846.0    0.05       0  4993.4    0.03       0  4999.4    0.05       0
Bank Sta=4993.4,4999.4
Exp/Cntr=0.3,0.1

Type RM Length L Ch R = 1,1808,472,472,472
BEGIN DESCRIPTION:
UNT104 IN BACR 3.0
END DESCRIPTION:
XS GIS Cut Line= 3
      2336412.45     13188419.23      2336139.51     13188306.06
      2335114.45     13188432.53
#Sta/Elev= 30
  4392.2   98.72  4673.0   98.30  4767.1   96.51  4780.9   96.44  4821.1   95.72
  4840.6   95.98  4928.3   94.31  4931.0   93.81  4934.3   94.31  4978.3   94.96
  4991.7   94.43  5011.9   95.09  5042.1   94.61  5059.5   95.37  5092.5   94.71
  5132.8   94.93  5193.3   96.00  5435.1   95.07  5445.2   95.71  5515.7   96.43
  5535.8   97.52  5551.3   96.83  5556.4   97.85  5576.1   97.09  5616.5   99.33
  5646.7   99.25  5676.9   97.29  5697.1   98.01  5713.6   97.34  5720.5   98.12
#Mann=5,-1,0
  4392.2    0.05       0  4767.1     0.1       0  4780.9    0.05       0
  4928.3    0.03       0  4934.3    0.05       0
Bank Sta=4928.3,4934.3
Exp/Cntr=0.3,0.1

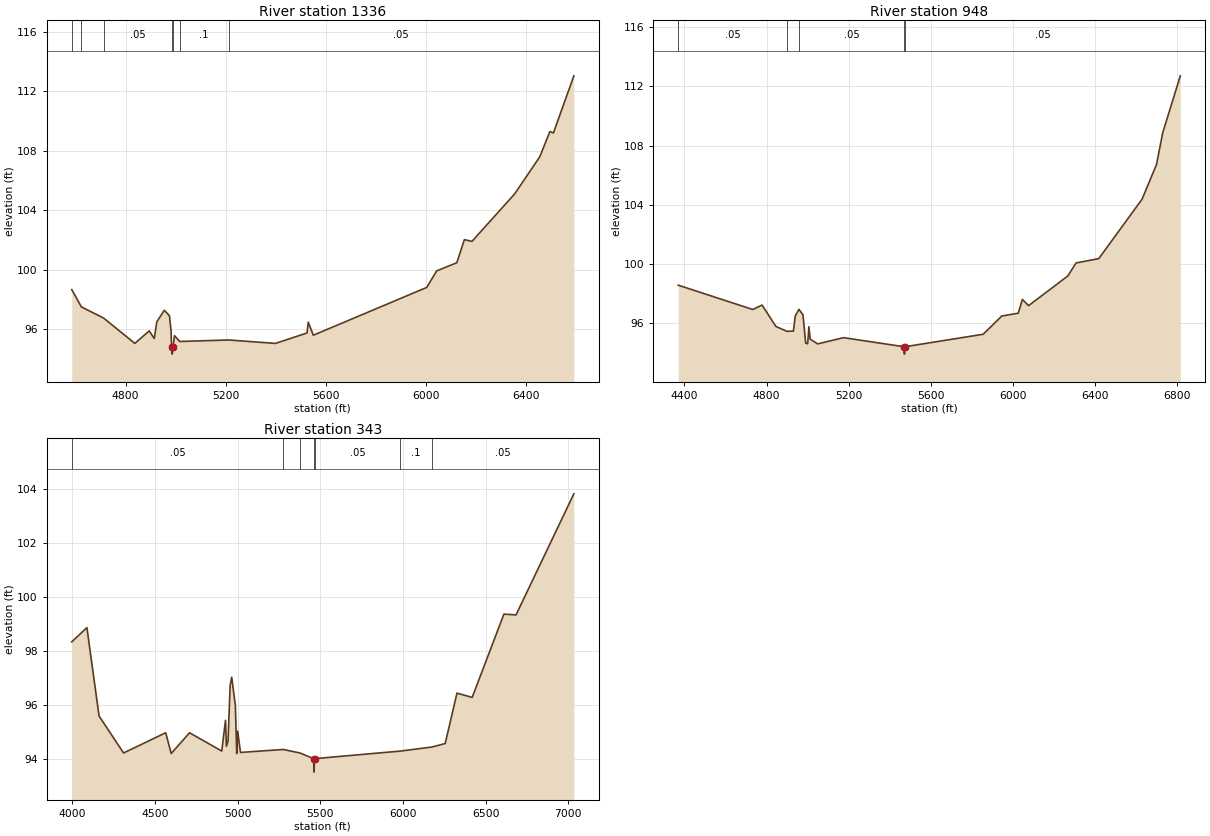
Type RM Length L Ch R = 1,1336,388,388,388
BEGIN DESCRIPTION:
Mapping XS f4b6bfea
END DESCRIPTION:
XS GIS Cut Line= 4
      2336212.76     13188106.38      2335993.07     13187926.64
      2335227.57     13187826.79      2334282.58     13187919.96
#Sta/Elev= 30
  4584.8   98.67  4623.3   97.51  4712.2   96.76  4836.8   95.06  4894.2   95.90
  4914.4   95.39  4924.5   96.51  4954.7   97.29  4974.9   96.92  4981.4   95.91
  4983.5   94.84  4986.2   94.34  4989.5   94.84  4995.1   95.58  5015.9   95.19
  5211.6   95.29  5398.4   95.06  5524.3   95.76  5529.5   96.48  5549.7   95.61
  6002.6   98.82  6042.4   99.93  6122.8  100.48  6153.0  102.03  6183.1  101.91
  6353.9  105.10  6454.4  107.60  6494.6  109.29  6508.6  109.19  6590.2  113.03
#Mann=7,-1,0
  4584.8    0.05       0  4623.3     0.1       0  4712.2    0.05       0
  4983.5    0.03       0  4989.5    0.05       0  5015.9     0.1       0
  5211.6    0.05       0
Bank Sta=4983.5,4989.5
Exp/Cntr=0.3,0.1

Type RM Length L Ch R = 1,948,605,605,605
BEGIN DESCRIPTION:
UNT104 IN BACR 2.0
END DESCRIPTION:
XS GIS Cut Line= 4
      2336385.79     13188266.07      2336226.04     13187713.63
      2335740.12     13187420.75      2334442.36     13187280.99
#Sta/Elev= 30
  4369.5   98.58  4733.0   96.94  4778.2   97.24  4845.4   95.80  4898.7   95.47
  4930.8   95.48  4940.3   96.51  4958.0   96.95  4977.6   96.58  4991.0   94.67
  5000.6   94.63  5006.5   95.78  5012.7   94.94  5049.2   94.62  5175.4   95.04
  5469.5   94.43  5472.2   93.93  5475.5   94.43  5856.3   95.27  5946.8   96.50
  6027.3   96.69  6047.4   97.62  6077.6   97.20  6268.7   99.20  6308.9  100.08
  6419.6  100.37  6630.8  104.38  6701.2  106.72  6731.3  108.85  6817.2  112.70
#Mann=5,-1,0
  4369.5    0.05       0  4898.7     0.1       0  4958.0    0.05       0
  5469.5    0.03       0  5475.5    0.05       0
Bank Sta=5469.5,5475.5
Exp/Cntr=0.3,0.1

Type RM Length L Ch R = 1,343,0,0,0
BEGIN DESCRIPTION:
UNT104 IN BACR 1.0
END DESCRIPTION:
XS GIS Cut Line= 3
      2337104.71     13188239.52      2336658.72     13187307.59
      2334695.07     13186908.20
#Sta/Elev= 30
  3996.5   98.34  4088.1   98.87  4161.7   95.59  4309.9   94.22  4564.8   94.97
  4598.0   94.20  4709.0   94.97  4903.8   94.29  4926.4   95.43  4932.0   94.47
  4941.8   94.66  4954.6   96.73  4963.9   97.03  4986.1   95.98  4994.4   94.20
  5000.0   95.03  5017.1   94.24  5275.8   94.35  5377.0   94.22  5459.1   94.01
  5461.8   93.51  5465.1   94.01  5983.7   94.29  6174.3   94.44  6255.2   94.57
  6326.7   96.44  6418.5   96.28  6610.5   99.37  6683.8   99.34  7033.5  103.83
#Mann=7,-1,0
  3996.5    0.05       0  5275.8     0.1       0  5377.0    0.05       0
  5459.1    0.03       0  5465.1    0.05       0  5983.7     0.1       0
  6174.3    0.05       0
Bank Sta=5459.1,5465.1
Exp/Cntr=0.3,0.1

Chan Stop Cuts=-1