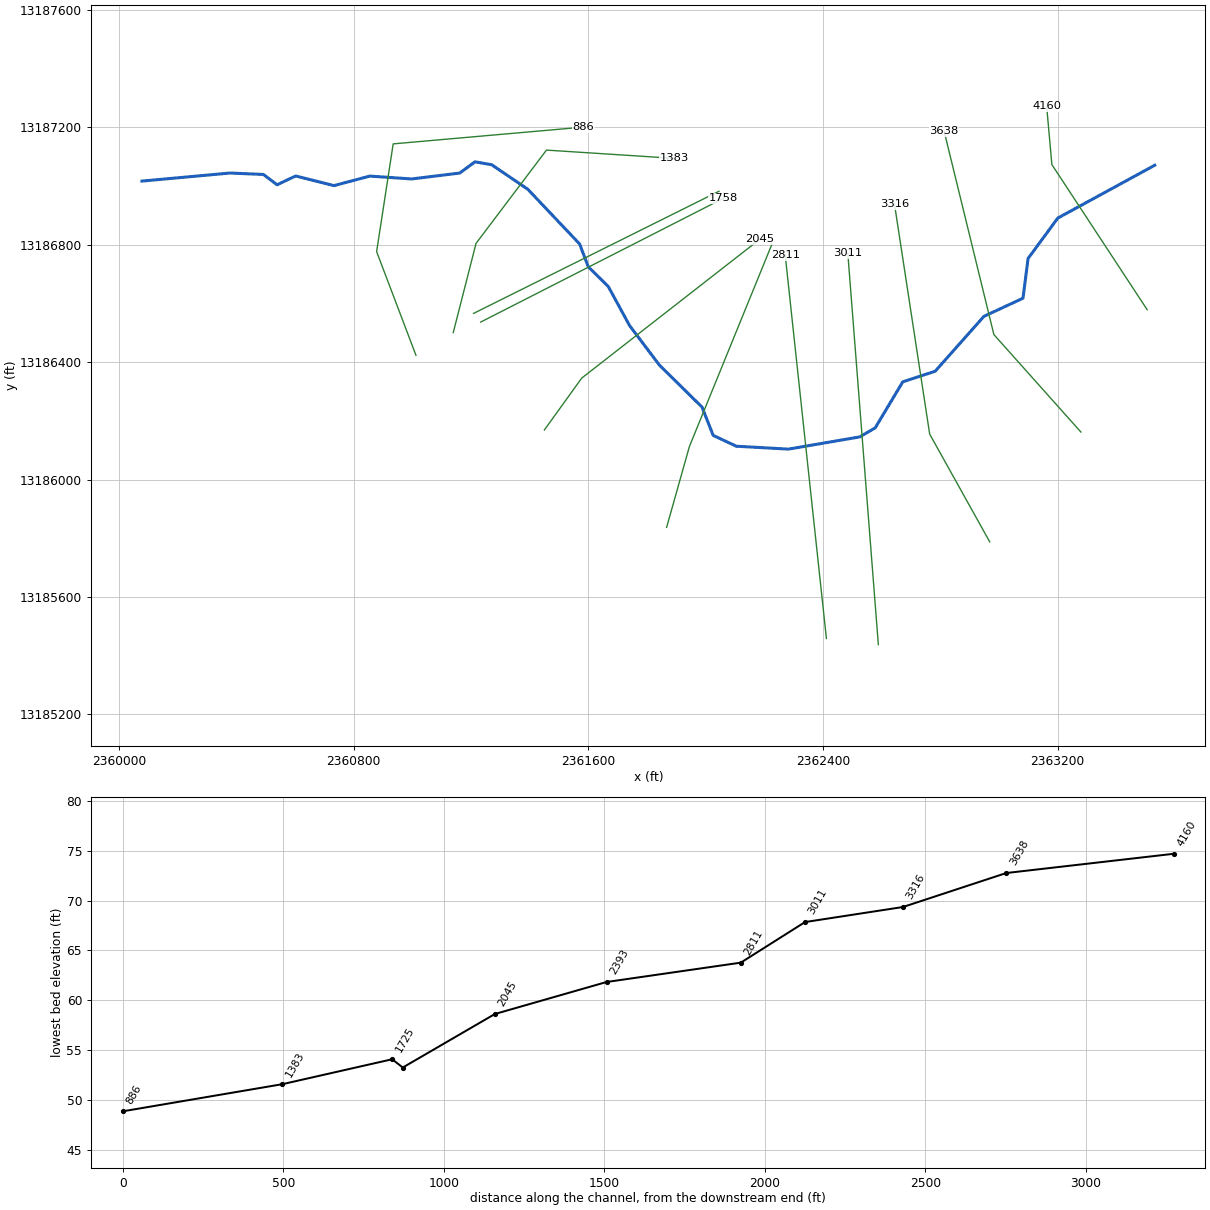
--- UNT105 IN BACR.prj (project) ---

Proj Title=UNT105 IN BACR Base Level Engineering
Current Plan=p01
Default Exp/Contr=0.3,0.1
English Units
Geom File=g01
Flow File=f01
Plan File=p01
Y Axis Title=Elevation
X Axis Title(PF)=Main Channel Distance
X Axis Title(XS)=Station
BEGIN DESCRIPTION:
UNT105 IN BACR
END DESCRIPTION:
DSS Export Rating Curves= 0
DSS Export Rating Curve Sorted= 0
DSS Export Volume Flow Curves= 0
DXF OffsetX= 0
DXF OffsetY= 0
DXF ScaleX= 1
DXF ScaleY= 10

--- UNT105 IN BACR.p01 (plan) ---

Plan Title=Multiple Run
Short Identifier=Multiple
Geom File=g01
Flow File=f01
Subcritical Flow
K Sum by GR= 0
Std Step Tol= 0.01
Critical Tol= 0.01
Num of Std Step Trials= 20
Max Error Tol= 0.3
Flow Tol Ratio= 0.001
Split Flow NTrial= 30
Split Flow Tol= 0.02
Split Flow Ratio= 0.02
Log Output Level= 0
Friction Slope Method= 1
Unsteady Friction Slope Method= 2
Unsteady Bridges Friction Slope Method= 1
Parabolic Critical Depth
Global Vel Dist=  1 , 1 , 1
Global Log Level= 0
CheckData=True
Encroach Param= -1, 0, 0, 0
BEGIN DESCRIPTION:
Multiple Run
END DESCRIPTION:

--- UNT105 IN BACR.f01 (steady flow) ---

Flow Title=Multiple
Program Version=4.10
Number of Profiles= 7
Profile Names=10-year,25-year,50-year,1pct_min,100-year,1pct_plu,500-year
River Rch & RM=UNT105 IN BACR,Reach-1         ,4160
     241     318     380     332     448     606     629
River Rch & RM=UNT105 IN BACR,Reach-1         ,2811
     312     422     510     451     610     825     881
Boundary for River Rch & Prof#=UNT105 IN BACR,Reach-1         , 1
Up Type= 0
Dn Type= 3
Dn Slope=0.005
Boundary for River Rch & Prof#=UNT105 IN BACR,Reach-1         , 2
Up Type= 0
Dn Type= 3
Dn Slope=0.005
Boundary for River Rch & Prof#=UNT105 IN BACR,Reach-1         , 3
Up Type= 0
Dn Type= 3
Dn Slope=0.005
Boundary for River Rch & Prof#=UNT105 IN BACR,Reach-1         , 4
Up Type= 0
Dn Type= 3
Dn Slope=0.005
Boundary for River Rch & Prof#=UNT105 IN BACR,Reach-1         , 5
Up Type= 0
Dn Type= 3
Dn Slope=0.005
Boundary for River Rch & Prof#=UNT105 IN BACR,Reach-1         , 6
Up Type= 0
Dn Type= 3
Dn Slope=0.005
Boundary for River Rch & Prof#=UNT105 IN BACR,Reach-1         , 7
Up Type= 0
Dn Type= 3
Dn Slope=0.005
DSS Import GetInterval= 0
DSS Import GetPeak= 0
DSS Import FillOption= 0

--- UNT105 IN BACR.g01 (geometry) ---

Geom Title=Existing Conditions
Program Version=4.10

River Reach=UNT105 IN BACR  ,Reach-1
Reach XY= 30
      2363531.43     13187070.86      2363200.73      13186890.8
      2363099.41      13186753.1      2363082.05     13186617.69
      2362948.94     13186556.05      2362782.57     13186368.84
      2362672.32     13186332.96      2362578.09     13186175.94
      2362525.43     13186145.27      2362282.37      13186103.6
      2362104.71     13186113.44      2362025.78      13186150.2
      2361987.49     13186246.92      2361841.93     13186390.19
      2361740.35      13186524.9      2361667.57     13186658.18
      2361599.91     13186724.57      2361570.05     13186802.69
      2361393.56     13186988.99      2361270.37      13187072.5
      2361213.32     13187082.49       2361161.6     13187044.22
      2360997.46     13187024.11      2360854.67     13187033.83
      2360732.56     13187001.43      2360602.12     13187034.27
      2360538.52     13187004.29      2360491.69     13187039.48
      2360377.86     13187044.27      2360077.72     13187016.85

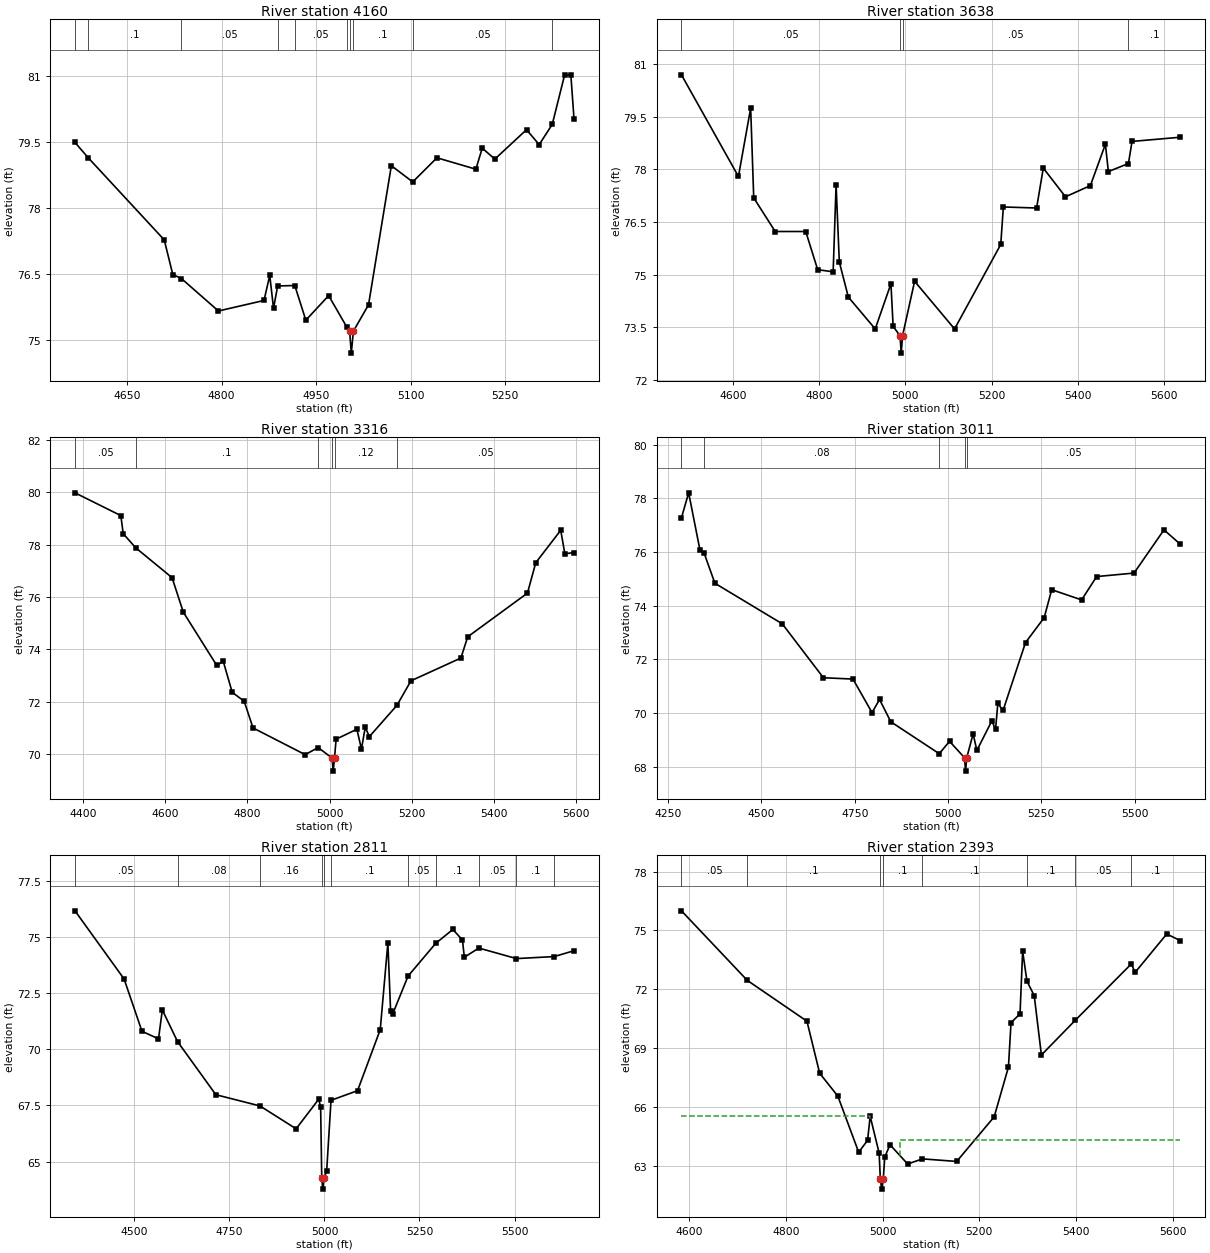
Type RM Length L Ch R = 1 ,4160    ,522,522,522
BEGIN DESCRIPTION:
UNT105 IN BACR 5.0
END DESCRIPTION:
XS GIS Cut Line= 3
      2363505.49     13186578.61       2363180.6     13187072.99
      2363162.72     13187271.81
#Sta/Elev= 30
  4567.7   79.49  4588.7   79.14  4709.2   77.27  4722.8   76.48  4736.4   76.39
  4795.1   75.65  4867.4   75.89  4876.5   76.46  4882.5   75.71    4889   76.22
  4916.2   76.23  4933.7   75.44  4969.9      76  4998.4   75.29  5003.1   75.19
  5005.8   74.69  5009.1   75.19  5033.1   75.79  5069.3   78.96  5103.2   78.59
  5141.6   79.14  5203.3   78.88  5213.4   79.36  5233.4   79.11  5283.6   79.78
  5303.7   79.44  5324.4    79.9  5343.9   81.02  5353.9   81.03  5358.9   80.03
#Mann= 10 ,-1 , 0
  4567.7     .05       0  4588.7      .1       0  4736.4     .05       0
    4889      .1       0  4916.2     .05       0  4998.4      .1       0
  5003.1     .07       0  5009.1      .1       0  5103.2     .05       0
  5324.4      .1       0
Bank Sta=5003.1,5009.1
XS Rating Curve= 0 ,0
Exp/Cntr=0.3,0.1

Type RM Length L Ch R = 1 ,3638    ,322,322,322
BEGIN DESCRIPTION:
Mapping XS b60f43eb
END DESCRIPTION:
XS GIS Cut Line= 3
      2363279.51     13186161.82      2362982.83     13186493.81
      2362813.31     13187186.02
#Sta/Elev= 30
  4480.3    80.7  4612.5    77.8  4640.9   79.75    4648   77.19  4697.8   76.23
  4768.7   76.23  4796.4   75.14  4832.3   75.08  4839.1   77.56  4846.6   75.36
  4867.5   74.36  4929.9   73.45  4966.4   74.74  4971.5   73.52  4987.4   73.26
  4990.2   72.76  4993.4   73.26  5021.3   74.81    5114   73.45  5221.2   75.86
  5227.2   76.93  5304.4    76.9  5319.9   78.04  5371.4   77.22  5429.2   77.54
    5464   78.72  5470.9   77.94  5517.5   78.17  5525.8    78.8  5638.2   78.92
#Mann= 4 ,-1 , 0
  4480.3     .05       0  4987.4     .03       0  4993.4     .05       0
  5517.5      .1       0
Bank Sta=4987.4,4993.4
XS Rating Curve= 0 ,0
Exp/Cntr=0.3,0.1

Type RM Length L Ch R = 1 ,3316    ,305,305,305
BEGIN DESCRIPTION:
Mapping XS 73ce806c
END DESCRIPTION:
XS GIS Cut Line= 3
      2362968.72     13185787.46      2362763.87     13186154.78
       2362643.8     13186938.76
#Sta/Elev= 30
  4380.7   79.98  4492.2   79.11    4498   78.42  4528.4   77.88  4616.8   76.74
  4644.2   75.42  4725.4   73.39  4741.4   73.54  4763.1   72.36  4792.2   72.02
  4813.7      71  4940.5   69.98  4972.2   70.25  5005.9   69.85  5008.7   69.35
  5011.9   69.85  5015.8   70.57  5066.4   70.95  5077.4   70.19  5086.6   71.02
  5096.8   70.67  5163.6   71.86  5197.9    72.8  5319.3   73.67  5335.9   74.48
  5481.2   76.15  5501.4   77.31  5562.1   78.55  5572.2   77.65  5594.4    77.7
#Mann= 6 ,-1 , 0
  4380.7     .05       0  4528.4      .1       0  4972.2     .12       0
  5005.9     .07       0  5011.9     .12       0  5163.6     .05       0
Bank Sta=5005.9,5011.9
XS Rating Curve= 0 ,0
Exp/Cntr=0.3,0.1

Type RM Length L Ch R = 1 ,3011    ,200,200,200
BEGIN DESCRIPTION:
UNT105 IN BACR 4.0
END DESCRIPTION:
XS GIS Cut Line= 2
      2362588.84     13185437.57      2362484.68      13186770.9
#Sta/Elev= 30
  4285.6   77.28  4304.9   78.21    4335   76.09  4346.7   75.95  4375.2   74.84
  4555.7   73.33    4666   71.32  4745.3   71.27  4796.4   70.02  4816.5   70.51
  4846.6   69.68  4976.5   68.49  5004.1   68.95  5044.2   68.34    5047   67.84
  5050.2   68.34  5067.3   69.23  5077.3   68.61  5117.4   69.71  5127.4    69.4
  5133.5   70.36  5147.5    70.1  5207.7   72.63  5257.8   73.56  5277.9    74.6
  5358.1   74.22  5398.3   75.09  5498.6   75.22  5578.8   76.83    5623   76.29
#Mann= 5 ,-1 , 0
  4285.6     .05       0  4346.7     .08       0  4976.5     .05       0
  5044.2     .04       0  5050.2     .05       0
Bank Sta=5044.2,5050.2
XS Rating Curve= 0 ,0
Exp/Cntr=0.3,0.1

Type RM Length L Ch R = 1 ,2811    ,418,418,418
BEGIN DESCRIPTION:
Mapping XS fc5cc93c
END DESCRIPTION:
XS GIS Cut Line= 2
      2362411.76      13185458.4      2362271.34     13186763.77
#Sta/Elev= 30
  4343.6   76.18  4472.8   73.14  4519.8   70.81  4563.3   70.47  4573.4   71.76
  4613.4   70.35  4714.2   67.98  4830.3   67.48  4925.4   66.46  4984.9   67.78
  4989.9   67.43  4992.8   64.27  4995.5   63.77  4998.8   64.27  5005.8   64.58
  5017.2   67.73    5087   68.16  5146.7   70.88  5166.8   74.75    5174    71.7
    5179   71.56  5219.9   73.27  5292.7   74.73  5337.8   75.35    5363   74.88
    5368   74.11  5406.1   74.52  5505.1   74.05  5604.2   74.14  5656.5    74.4
#Mann= 11 ,-1 , 0
  4343.6     .05       0  4613.4     .08       0  4830.3     .16       0
  4992.8     .07       0  4998.8     .16       0  5017.2      .1       0
  5219.9     .05       0  5292.7      .1       0  5406.1     .05       0
  5505.1      .1       0  5604.2     .05       0
Bank Sta=4992.8,4998.8
XS Rating Curve= 0 ,0
Exp/Cntr=0.3,0.1

Type RM Length L Ch R = 1 ,2393    ,348,348,348
BEGIN DESCRIPTION:
Mapping XS f9f5572c
END DESCRIPTION:
XS GIS Cut Line= 3
      2361866.85     13185836.96      2361944.54      13186112.4
       2362226.5     13186803.19
#Sta/Elev= 30
    4584      76  4720.1   72.46  4843.6   70.38  4869.9   67.73  4907.4   66.57
  4950.6   63.71    4969   64.31  4974.4   65.54    4993   63.66  4995.4   62.33
  4998.2   61.83  5001.4   62.33  5004.6   63.46  5015.4   64.09  5051.9   63.11
  5082.6   63.37  5153.4   63.24  5230.9   65.51  5260.4   68.04  5265.8   70.31
  5284.4   70.75  5289.8   73.95  5298.7   72.42  5313.8   71.68  5328.6   68.66
  5398.8   70.43  5514.8    73.3  5522.3   72.86  5587.9   74.82  5616.3   74.48
#Mann= 8 ,-1 , 0
    4584     .05       0  4720.1      .1       0  4995.4     .07       0
  5001.4      .1       0  5082.6      .1       0  5298.7      .1       0
  5398.8     .05       0  5514.8      .1       0
#XS Ineff= 2 , 0
       0 4973.52   65.54 5036.36       0   64.33
Permanent Ineff=
       T       T
Bank Sta=4995.4,5001.4
XS Rating Curve= 0 ,0
Exp/Cntr=0.3,0.1

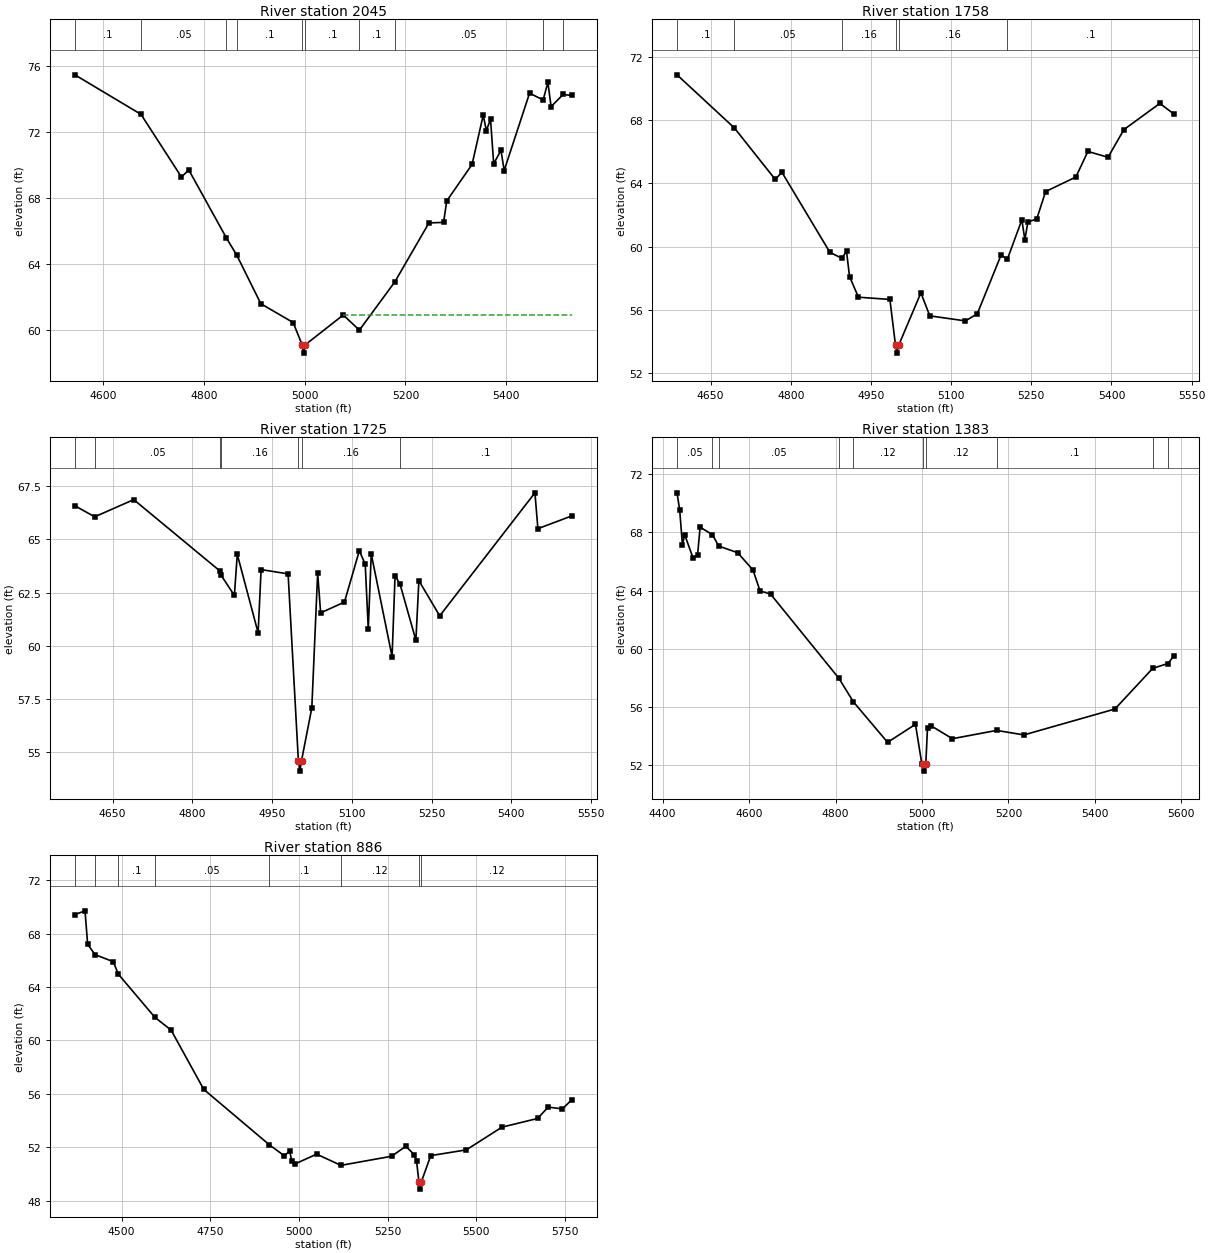
Type RM Length L Ch R = 1 ,2045    ,287,287,287
BEGIN DESCRIPTION:
UNT105 IN BACR 3.0
END DESCRIPTION:
XS GIS Cut Line= 3
      2361450.12      13186168.9      2361577.26     13186345.48
      2362183.74     13186817.98
#Sta/Elev= 30
  4543.6   75.46  4674.8   73.07  4755.1   69.28  4769.8    69.7  4844.6   65.58
  4865.1   64.54  4912.8   61.61    4977   60.47  4994.8   59.12  4997.6   58.62
  5000.8   59.12  5076.5   60.93  5108.4   60.01  5178.8   62.93  5246.6    66.5
  5275.6   66.53  5281.9   67.83  5332.2   70.04  5354.3   73.02  5360.6   72.08
  5368.8   72.78  5375.1   70.08  5389.6   70.89  5395.9   69.67  5446.3   74.35
  5473.3   73.94  5482.7      75  5489.1   73.54    5513   74.27    5530   74.21
#Mann= 10 ,-1 , 0
  4543.6      .1       0  4674.8     .05       0  4844.6      .1       0
  4865.1      .1       0  4994.8     .03       0  5000.8      .1       0
  5108.4      .1       0  5178.8     .05       0  5473.3      .1       0
    5513     .05       0
#XS Ineff= 2 , 0
       0                 5076.37       0   60.93
Permanent Ineff=
       F       T
Bank Sta=4994.8,5000.8
XS Rating Curve= 0 ,0
Exp/Cntr=0.3,0.1

Type RM Length L Ch R = 1 ,1758    ,33,33,33
BEGIN DESCRIPTION:
UNT105 IN BACR 2.0
END DESCRIPTION:
XS GIS Cut Line= 2
       2361232.9     13186536.51      2362061.03     13186958.39
#Sta/Elev= 30
  4587.3   70.87  4694.5   67.51    4771   64.25  4783.5    64.7  4873.3   59.63
  4895.4   59.26  4904.4   59.69    4910    58.1  4926.7   56.79  4985.5   56.65
    4996   53.75  4998.7   53.25    5002   53.75  5043.5   57.07  5060.1   55.61
  5126.8   55.29    5149   55.74  5193.5   59.46  5205.3    59.2  5232.4   61.69
    5238   60.42  5243.6   61.56  5260.2   61.74  5276.8   63.48  5333.4    64.4
  5355.9   66.02  5393.6   65.65  5423.2    67.4  5490.5   69.06  5516.7   68.39
#Mann= 6 ,-1 , 0
  4587.3      .1       0  4694.5     .05       0  4895.4     .16       0
    4996     .07       0    5002     .16       0  5205.3      .1       0
Bank Sta=4996,5002
XS Rating Curve= 0 ,0
Exp/Cntr=0.3,0.1

Type RM Length L Ch R = 1 ,1725    ,342,342,342
BEGIN DESCRIPTION:
Mapping XS 549aaa41
END DESCRIPTION:
XS GIS Cut Line= 2
      2361208.63     13186566.04      2362045.43     13186982.27
#Sta/Elev= 30
  4578.9   66.59  4616.2   66.07  4689.6   66.88    4852   63.51  4853.9   63.32
  4878.9   62.36  4884.4    64.3  4923.6    60.6  4929.2   63.58    4980   63.38
  4999.3   54.58    5002   54.08  5005.3   54.58  5024.6   57.06  5035.6   63.42
  5041.2   61.54    5086   62.05    5114   64.47  5125.1   63.83  5130.8   60.78
  5136.4   64.32  5175.6   59.48  5181.2   63.29  5190.5    62.9  5220.4   60.25
    5226   63.06  5265.2    61.4  5444.3    67.2  5449.9   65.51  5513.5   66.11
#Mann= 7 ,-1 , 0
  4578.9      .1       0  4616.2     .05       0    4852      .1       0
  4853.9     .16       0  4999.3     .07       0  5005.3     .16       0
  5190.5      .1       0
Bank Sta=4999.3,5005.3
XS Rating Curve= 0 ,0
Exp/Cntr=0.3,0.1

Type RM Length L Ch R = 1 ,1383    ,497,497,497
BEGIN DESCRIPTION:
Mapping XS 98064cae
END DESCRIPTION:
XS GIS Cut Line= 4
      2361139.33     13186500.83      2361217.03     13186804.59
      2361457.18     13187122.44      2361893.86     13187094.26
#Sta/Elev= 30
  4433.2   70.72  4439.4   69.52  4445.7   67.15  4450.9   67.84  4470.4   66.23
  4480.7   66.43  4486.6   68.36  4515.2   67.84  4529.6   67.06  4573.6    66.6
    4609   65.41  4625.2   63.98  4649.8   63.75  4807.8   57.96  4841.4   56.34
  4920.4   53.56  4984.9    54.8  4999.5    52.1  5002.8   52.08  5005.5   51.58
  5008.8   52.08  5012.8   54.58  5020.3   54.71  5070.3   53.81  5172.8   54.38
  5235.8   54.07  5446.3   55.85  5533.9   58.65    5569   58.98  5582.7    59.5
#Mann= 10 ,-1 , 0
  4433.2     .05       0  4515.2      .1       0  4529.6     .05       0
  4807.8      .1       0  4841.4     .12       0  5002.8     .07       0
  5008.8     .12       0  5172.8      .1       0  5533.9     .12       0
    5569      .1       0
Bank Sta=5002.8,5008.8
XS Rating Curve= 0 ,0
Exp/Cntr=0.3,0.1

Type RM Length L Ch R = 1 ,886     ,0,0,0
BEGIN DESCRIPTION:
UNT105 IN BACR 1.0
END DESCRIPTION:
XS GIS Cut Line= 4
      2361012.18     13186423.22        2360878.     13186776.34
       2360934.5     13187143.63      2361583.72     13187200.84
#Sta/Elev= 30
  4368.2   69.42  4396.8    69.7  4404.2   67.19  4425.2   66.42  4476.5   65.89
  4490.9   64.95    4594   61.72  4639.5   60.77  4731.6   56.33    4917   52.17
  4958.9   51.36  4974.2   51.71  4979.3      51  4989.3   50.75    5050   51.48
  5118.5   50.64  5261.3   51.32  5301.5   52.07  5325.9   51.42  5331.6      51
  5338.6   49.36  5341.4   48.86  5344.6   49.36  5371.8   51.37  5472.1    51.8
  5572.5    53.5  5672.9   54.15    5703      55  5743.2   54.87  5769.3   55.55
#Mann= 8 ,-1 , 0
  4368.2      .1       0  4425.2     .05       0  4490.9      .1       0
    4594     .05       0    4917      .1       0  5118.5     .12       0
  5338.6     .07       0  5344.6     .12       0
Bank Sta=5338.6,5344.6
XS Rating Curve= 0 ,0
Exp/Cntr=0.3,0.1

Chan Stop Cuts=-1
Use User Specified Reach Order=0
Composite Channel Slope=5