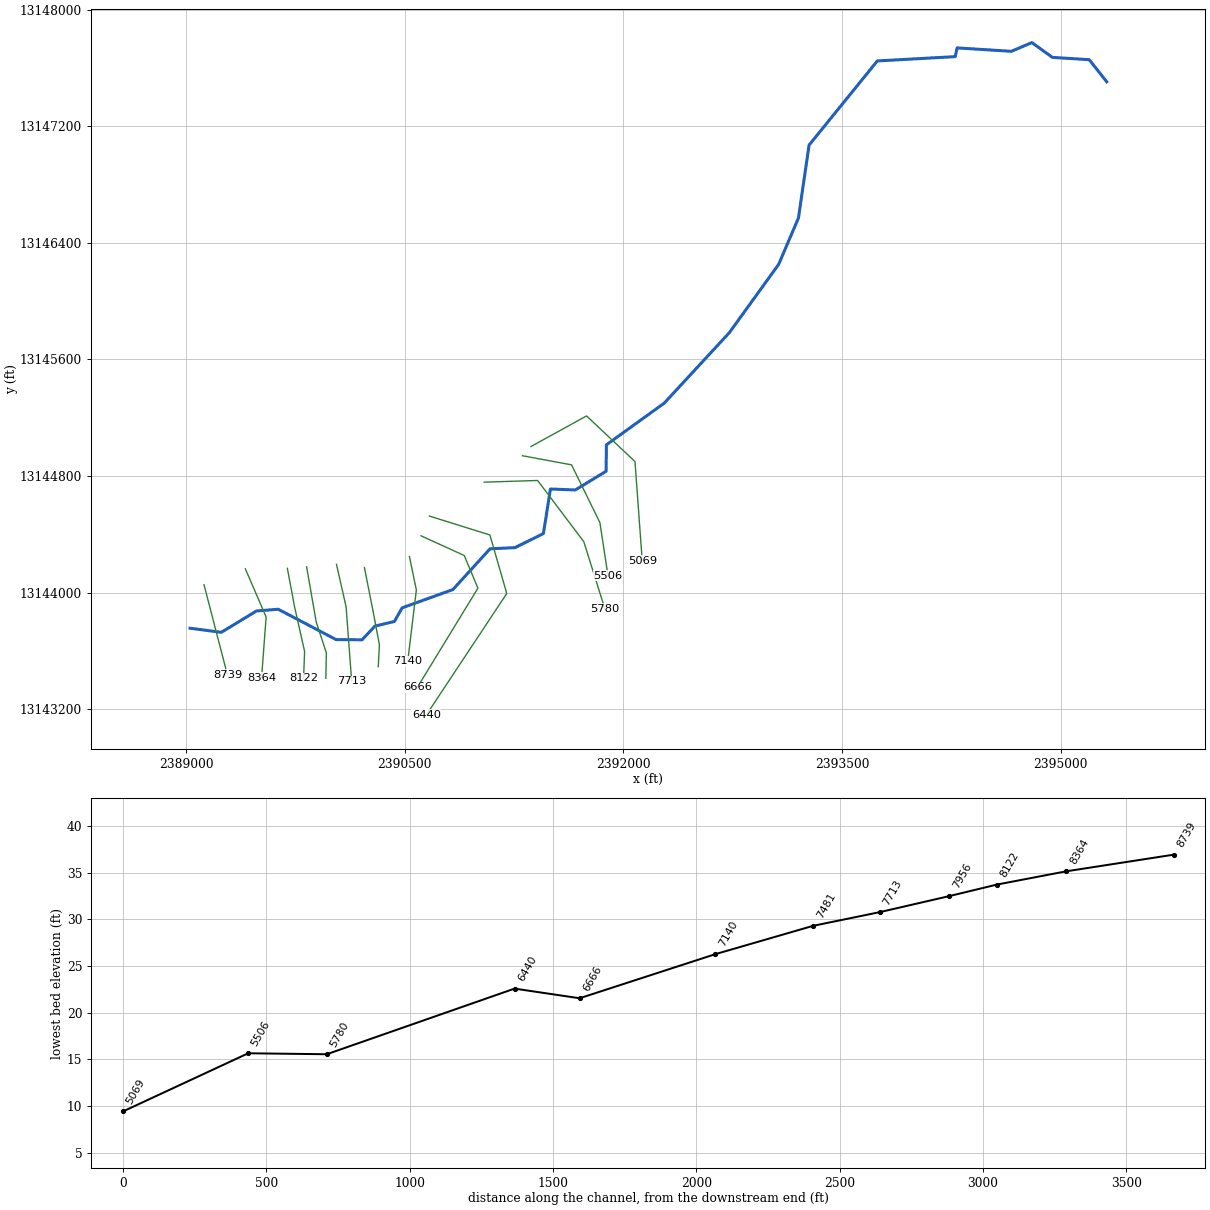
--- UNT107 IN BACR.prj (project) ---

Proj Title=UNT107 IN BACR Base Level Engineering
Current Plan=p01
Default Exp/Contr=0.3,0.1
English Units
Geom File=g01
Flow File=f01
Plan File=p01
Y Axis Title=Elevation
X Axis Title(PF)=Main Channel Distance
X Axis Title(XS)=Station
BEGIN DESCRIPTION:
UNT107 IN BACR
END DESCRIPTION:
DSS Export Rating Curves= 0
DSS Export Rating Curve Sorted= 0
DSS Export Volume Flow Curves= 0
DXF OffsetX= 0
DXF OffsetY= 0
DXF ScaleX= 1
DXF ScaleY= 10

--- UNT107 IN BACR.p01 (plan) ---

Plan Title=Multiple Run
Short Identifier=Multiple
Geom File=g01
Flow File=f01
Subcritical Flow
K Sum by GR= 0
Std Step Tol= 0.01
Critical Tol= 0.01
Num of Std Step Trials= 20
Max Error Tol= 0.3
Flow Tol Ratio= 0.001
Split Flow NTrial= 30
Split Flow Tol= 0.02
Split Flow Ratio= 0.02
Log Output Level= 0
Friction Slope Method= 1
Unsteady Friction Slope Method= 2
Unsteady Bridges Friction Slope Method= 1
Parabolic Critical Depth
Global Vel Dist=  1 , 1 , 1
Global Log Level= 0
CheckData=True
Encroach Param= -1, 0, 0, 0
BEGIN DESCRIPTION:
Multiple Run
END DESCRIPTION:

--- UNT107 IN BACR.f01 (steady flow) ---

Flow Title=Multiple
Program Version=4.10
Number of Profiles= 7
Profile Names=10-year,25-year,50-year,1pct_min,100-year,1pct_plu,500-year
River Rch & RM=UNT107 IN BACR,Reach-1         ,8739
     250     333     399     351     474     641     676
River Rch & RM=UNT107 IN BACR,Reach-1         ,8364
     329     447     542     482     652     881     951
River Rch & RM=UNT107 IN BACR,Reach-1         ,5780
     358     486     590     524     709     959    1034
Boundary for River Rch & Prof#=UNT107 IN BACR,Reach-1         , 1
Up Type= 0
Dn Type= 3
Dn Slope=0.0089
Boundary for River Rch & Prof#=UNT107 IN BACR,Reach-1         , 2
Up Type= 0
Dn Type= 3
Dn Slope=0.0089
Boundary for River Rch & Prof#=UNT107 IN BACR,Reach-1         , 3
Up Type= 0
Dn Type= 3
Dn Slope=0.0089
Boundary for River Rch & Prof#=UNT107 IN BACR,Reach-1         , 4
Up Type= 0
Dn Type= 3
Dn Slope=0.0089
Boundary for River Rch & Prof#=UNT107 IN BACR,Reach-1         , 5
Up Type= 0
Dn Type= 3
Dn Slope=0.0089
Boundary for River Rch & Prof#=UNT107 IN BACR,Reach-1         , 6
Up Type= 0
Dn Type= 3
Dn Slope=0.0089
Boundary for River Rch & Prof#=UNT107 IN BACR,Reach-1         , 7
Up Type= 0
Dn Type= 3
Dn Slope=0.0089
DSS Import GetInterval= 0
DSS Import GetPeak= 0
DSS Import FillOption= 0

--- UNT107 IN BACR.g01 (geometry) ---

Geom Title=Existing Conditions
Program Version=4.10

River Reach=UNT107 IN BACR  ,Reach-1
Reach XY= 30
      2389027.72     13143756.86      2389241.91     13143728.67
       2389483.2     13143874.98      2389632.15     13143886.96
      2390029.42     13143678.69      2390207.52     13143677.45
      2390295.56     13143771.13      2390429.11     13143802.99
      2390482.56     13143896.68      2390830.53     13144021.88
      2391085.33     13144301.49      2391256.53      13144309.5
      2391451.55     13144406.43      2391499.73     13144711.74
      2391669.78     13144704.89      2391881.59     13144833.37
      2391883.67     13145014.62      2392280.81     13145300.99
      2392726.99     13145784.06      2393065.53     13146252.81
      2393200.95     13146570.52      2393273.86     13147070.52
      2393742.09     13147647.78      2394276.47     13147677.29
      2394289.49     13147737.19      2394661.88     13147713.75
      2394802.51     13147773.64      2394943.13     13147672.08
      2395195.74     13147656.46      2395315.92     13147504.47

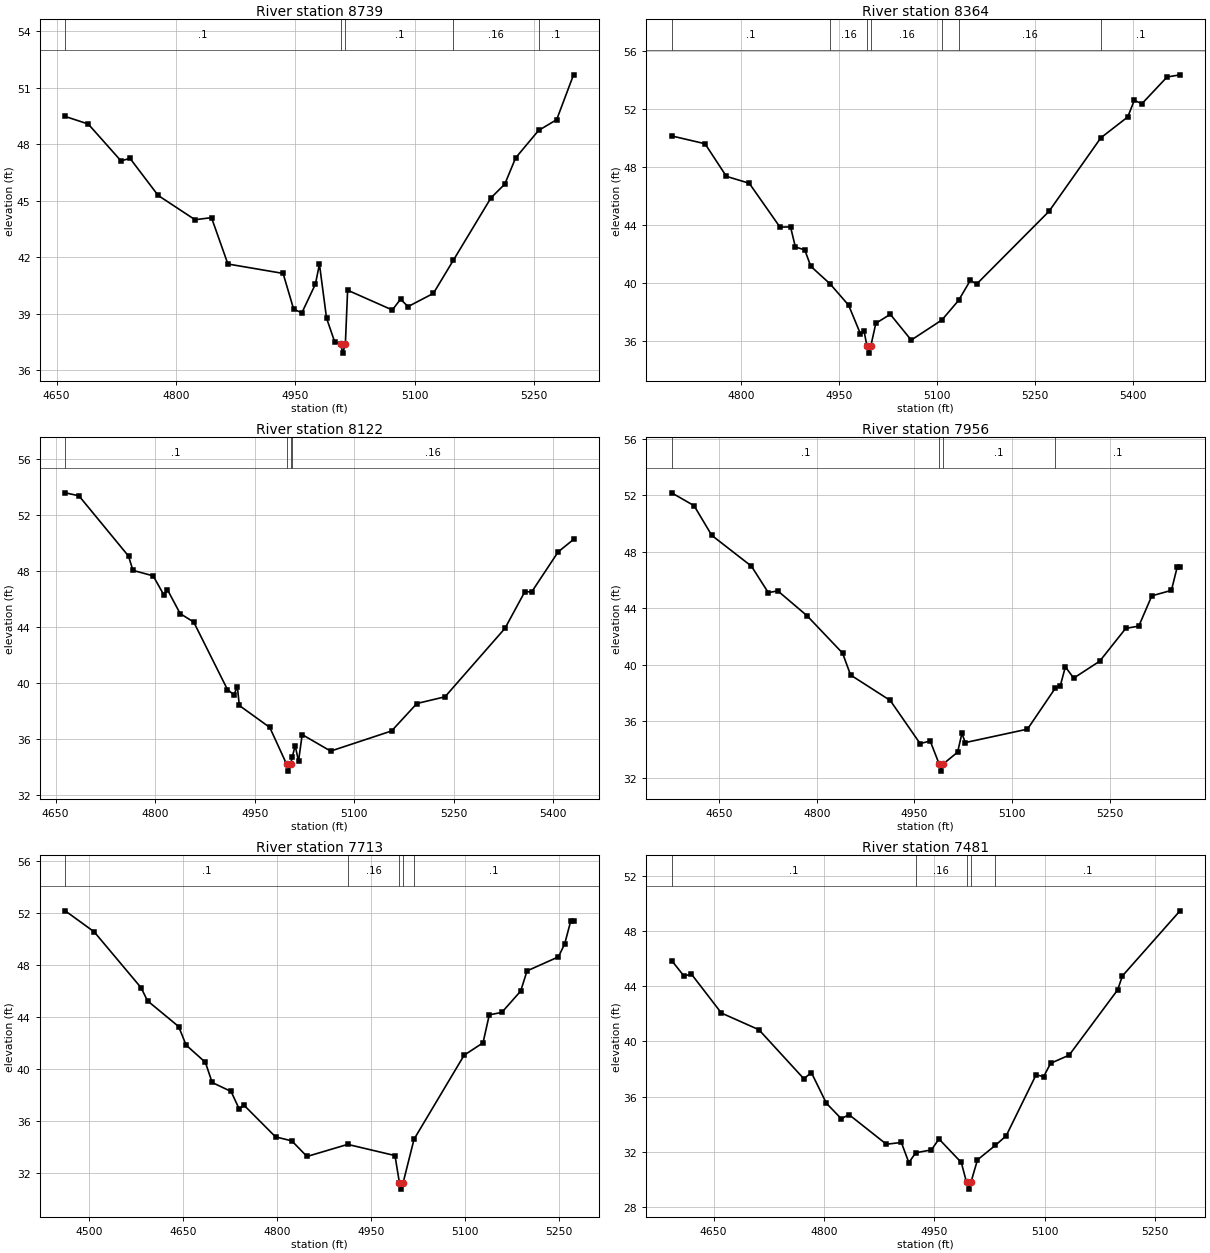
Type RM Length L Ch R = 1 ,8739    ,375,375,375
BEGIN DESCRIPTION:
UNT107 IN BACR 9.0
END DESCRIPTION:
XS GIS Cut Line= 2
      2389123.33     13144054.84      2389283.93     13143436.35
#Sta/Elev= 30
  4660.8   49.47  4689.7   49.07    4731   47.11  4742.2   47.25  4777.6   45.28
    4824   43.99  4844.7    44.1  4865.3   41.64  4934.7   41.14    4948   39.24
  4958.3   39.05  4975.3   40.57  4980.4   41.63  4989.3   38.77  4999.7   37.49
    5007   37.41  5009.7   36.91    5013   37.41  5015.8   40.25    5072    39.2
  5082.3   39.77  5091.8   39.38  5123.6   40.08  5148.6   41.83    5196   45.15
  5213.4   45.88    5227   47.27  5255.9   48.73  5278.6    49.3  5299.8   51.68
#Mann= 5 ,-1 , 0
  4660.8      .1       0    5007     .07       0    5013      .1       0
  5148.6     .16       0  5255.9      .1       0
Bank Sta=5007,5013
XS Rating Curve= 0 ,0
Exp/Cntr=0.3,0.1

Type RM Length L Ch R = 1 ,8364    ,242,242,242
BEGIN DESCRIPTION:
Mapping XS 0fc4b067
END DESCRIPTION:
XS GIS Cut Line= 3
      2389407.01     13144163.66      2389549.38     13143833.78
      2389518.13     13143417.14
#Sta/Elev= 30
  4694.4   50.13  4745.4   49.59    4778   47.34    4813   46.86    4860   43.83
  4876.1   43.85  4883.5   42.46  4897.9   42.26    4907   41.13  4936.6   39.91
  4964.9   38.44    4983   36.46  4988.4   36.67  4992.9   35.63  4995.6   35.13
  4998.9   35.63  5006.5   37.19  5028.6   37.81  5060.6   36.03  5107.5   37.42
    5133   38.77  5150.9   40.15  5160.9   39.91  5271.2   44.92  5350.5      50
  5391.6   51.44  5401.6   52.58  5413.4   52.36  5451.7    54.2  5471.5   54.35
#Mann= 7 ,-1 , 0
  4694.4      .1       0  4936.6     .16       0  4992.9     .07       0
  4998.9     .16       0  5107.5      .1       0    5133     .16       0
  5350.5      .1       0
Bank Sta=4992.9,4998.9
XS Rating Curve= 0 ,0
Exp/Cntr=0.3,0.1

Type RM Length L Ch R = 1 ,8122    ,166,166,166
BEGIN DESCRIPTION:
Mapping XS c3f2340b
END DESCRIPTION:
XS GIS Cut Line= 4
      2389695.21     13144167.12      2389743.82      13143906.7
      2389813.27     13143597.67      2389806.32     13143413.66
#Sta/Elev= 30
  4664.5   53.59  4685.1   53.38  4759.9   49.07  4766.5   48.05    4797   47.66
  4813.4   46.27  4818.4   46.68  4837.7   44.96  4858.1   44.36  4908.9   39.54
  4918.7   39.16  4923.8   39.75  4926.8    38.4  4972.7   36.83    4998   34.21
  5000.8   33.71    5004   34.21  5006.6   34.71  5010.9   35.54    5016   34.42
  5021.5   36.32  5064.4   35.14  5156.2   36.58  5194.3   38.54  5236.7   39.02
    5327   43.91  5357.1   46.54  5367.1    46.5  5407.1   49.37  5430.3   50.26
#Mann= 4 ,-1 , 0
  4664.5      .1       0    4998     .07       0    5004      .1       0
  5006.6     .16       0
Bank Sta=4998,5004
XS Rating Curve= 0 ,0
Exp/Cntr=0.3,0.1

Type RM Length L Ch R = 1 ,7956    ,243,243,243
BEGIN DESCRIPTION:
UNT107 IN BACR 7.0
END DESCRIPTION:
XS GIS Cut Line= 4
      2389827.15     13144177.57      2389893.13     13143799.06
      2389962.57     13143587.25       2389959.1     13143413.61
#Sta/Elev= 30
  4577.1   52.17  4611.5   51.26  4638.7   49.16  4699.6   46.98  4725.5   45.11
  4740.2   45.23  4785.1   43.47  4839.6   40.83  4851.9   39.28  4912.8   37.48
  4958.7   34.43  4974.2   34.61    4988   32.98  4990.8   32.48    4994   32.98
  5016.3   33.82  5022.9   35.15  5028.1    34.5  5123.6   35.45    5166   38.33
  5174.1   38.53  5181.8   39.86  5194.6   39.06  5234.6   40.26  5274.6   42.58
  5294.6   42.74  5314.6   44.88  5344.7   45.27  5353.8   46.95  5357.9   46.95
#Mann= 4 ,-1 , 0
  4577.1      .1       0    4988     .07       0    4994      .1       0
    5166      .1       0
Bank Sta=4988,4994
XS Rating Curve= 0 ,0
Exp/Cntr=0.3,0.1

Type RM Length L Ch R = 1 ,7713    ,232,232,232
BEGIN DESCRIPTION:
Mapping XS cf9f2363
END DESCRIPTION:
XS GIS Cut Line= 3
      2390032.01     13144194.92      2390097.99     13143903.23
      2390136.18     13143392.81
#Sta/Elev= 30
  4462.2   52.16  4508.5   50.54  4583.2   46.25  4593.5   45.24  4643.2   43.26
    4655   41.84  4685.8   40.51  4696.6   38.96  4726.8   38.27  4739.8   36.92
  4747.3   37.22  4797.7   34.78  4823.7   34.47  4847.9   33.27  4912.8    34.2
  4988.3   33.34  4995.3   31.26    4998   30.76  5001.3   31.26  5018.7    34.6
  5098.6   41.06  5128.7   42.01  5138.7   44.16  5158.7   44.35  5188.8   45.99
  5198.9   47.54    5249   48.62    5259   49.62  5268.6   51.37  5273.1   51.37
#Mann= 5 ,-1 , 0
  4462.2      .1       0  4912.8     .16       0  4995.3     .07       0
  5001.3     .16       0  5018.7      .1       0
Bank Sta=4995.3,5001.3
XS Rating Curve= 0 ,0
Exp/Cntr=0.3,0.1

Type RM Length L Ch R = 1 ,7481    ,341,341,341
BEGIN DESCRIPTION:
Mapping XS fffa2be2
END DESCRIPTION:
XS GIS Cut Line= 4
      2390223.67     13144173.19      2390283.04     13143872.34
      2390326.59     13143642.76      2390318.67      13143492.3
#Sta/Elev= 30
    4593   45.85  4609.7   44.73  4619.8   44.87  4660.6   42.05  4711.6   40.84
  4772.7   37.29  4782.9   37.74  4803.3   35.52  4823.7   34.39  4833.9    34.7
  4884.9   32.55  4905.2   32.68  4915.4   31.22  4924.7   31.93    4946   32.14
  4956.4   32.93  4986.7   31.23  4993.8    29.8  4996.6    29.3  4999.8    29.8
  5008.7   31.42    5033   32.47  5047.7   33.16  5088.4   37.58  5098.6   37.44
  5108.1   38.41  5133.3      39  5199.3   43.73  5205.6   44.73    5284   49.45
#Mann= 5 ,-1 , 0
    4593      .1       0  4924.7     .16       0  4993.8     .07       0
  4999.8     .16       0    5033      .1       0
Bank Sta=4993.8,4999.8
XS Rating Curve= 0 ,0
Exp/Cntr=0.3,0.1

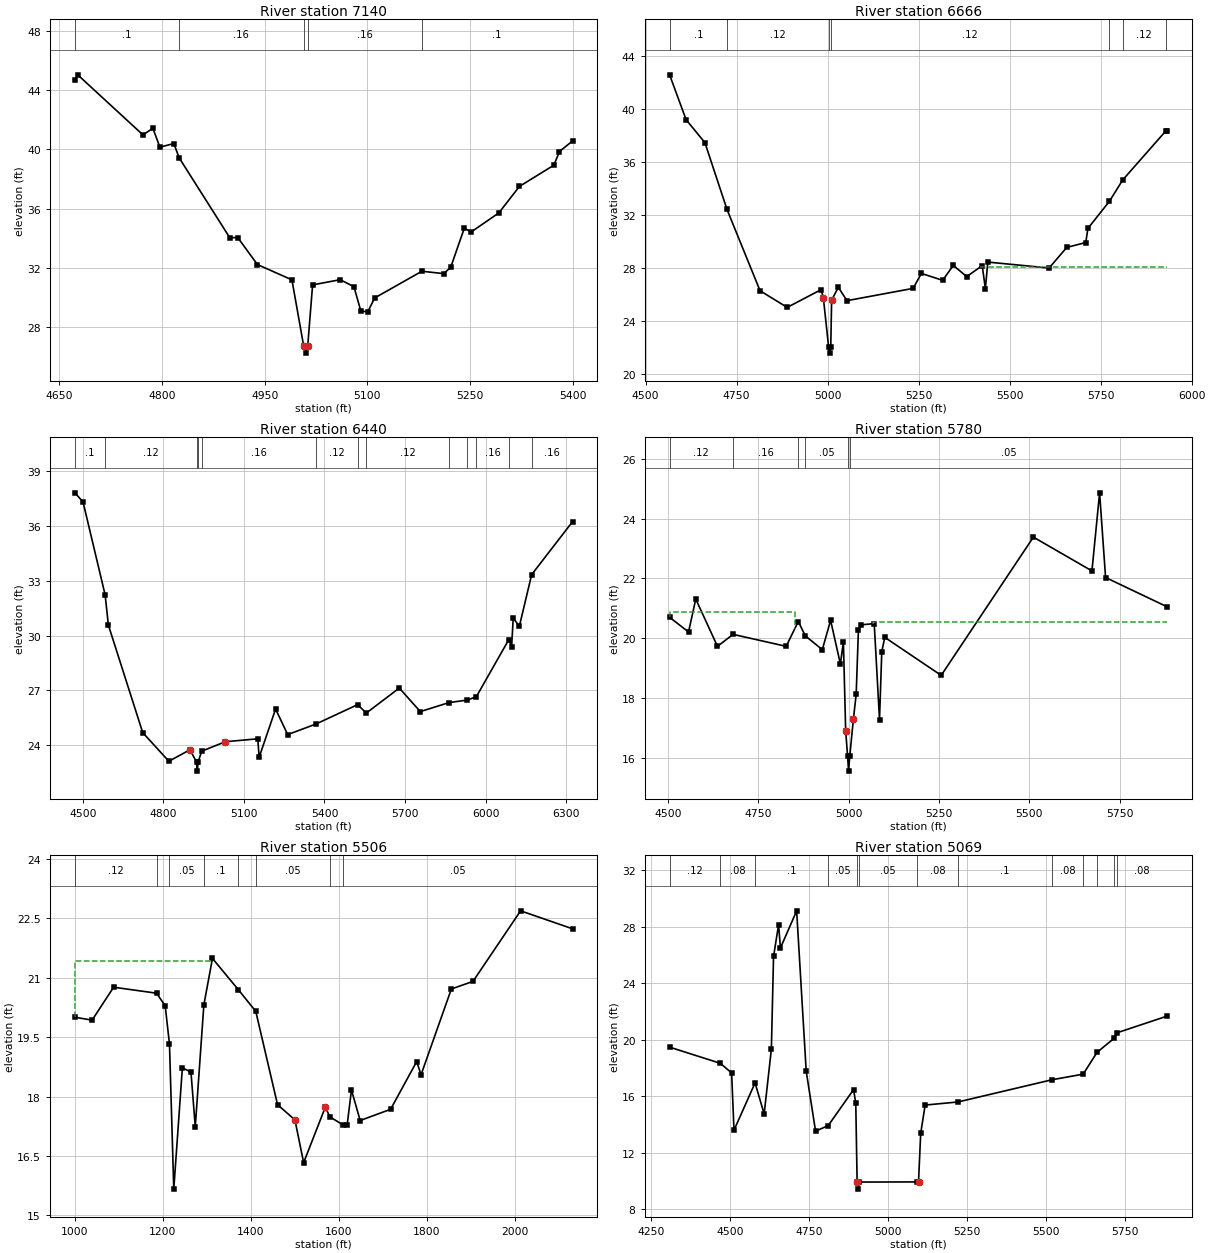
Type RM Length L Ch R = 1 ,7140    ,474,474,474
BEGIN DESCRIPTION:
UNT107 IN BACR 6.0
END DESCRIPTION:
XS GIS Cut Line= 3
      2390532.42     13144248.37      2390579.92      13144018.8
      2390520.78      13143529.9
#Sta/Elev= 30
  4672.7   44.71  4676.8   45.03  4772.1   40.98  4786.6   41.43  4796.8   40.15
  4817.2    40.4  4824.9   39.44  4898.9   34.05  4910.6   34.06  4939.3   32.24
  4989.7   31.21  5006.8   26.77  5009.6   26.27  5012.8   26.77  5019.9   30.87
  5060.2   31.22  5080.3   30.75  5090.4    29.1  5100.5   29.06  5110.6   29.99
  5179.6   31.79  5211.3   31.63  5221.6   32.05  5241.5   34.69  5251.6   34.44
  5291.9   35.72  5322.1   37.51  5372.4   38.94  5380.5   39.86  5399.6   40.57
#Mann= 5 ,-1 , 0
  4672.7      .1       0  4824.9     .16       0  5006.8     .07       0
  5012.8     .16       0  5179.6      .1       0
Bank Sta=5006.8,5012.8
XS Rating Curve= 0 ,0
Exp/Cntr=0.3,0.1

Type RM Length L Ch R = 1 ,6666    ,227,227,227
BEGIN DESCRIPTION:
UNT107 IN BACR 5.0
END DESCRIPTION:
XS GIS Cut Line= 4
      2390611.63      13144390.8      2390908.48      13144255.4
      2391002.23     13144031.44      2390586.41     13143350.53
#Sta/Elev= 30
  4565.9   42.61  4611.3   39.21  4662.9   37.48  4723.5   32.43  4814.4   26.27
    4889   25.01  4981.8   26.35  4988.2   25.75  5002.6   22.05  5005.3   21.55
  5008.6   22.05    5011   25.56  5029.4   26.53  5053.2   25.52  5234.9   26.45
  5257.5   27.58  5316.1   27.06  5345.2   28.19    5382   27.34  5424.6   28.17
  5433.3   26.44  5440.1   28.44  5608.4   27.99  5656.9   29.55  5709.1   29.92
    5715   30.99  5774.1   33.04  5810.7   34.66  5928.6   38.35  5932.8   38.36
#Mann= 7 ,-1 , 0
  4565.9      .1       0  4723.5     .12       0  5002.6     .07       0
  5008.6     .12       0  5774.1     .16       0  5810.7     .12       0
  5928.6     .16       0
#XS Ineff= 2 , 0
                         5419.09            28.1
Permanent Ineff=
       F       F
Bank Sta=4988.2,5011
XS Rating Curve= 0 ,0
Exp/Cntr=0.3,0.1

Type RM Length L Ch R = 1 ,6440    ,655,655,655
BEGIN DESCRIPTION:
Mapping XS b8b01e2b
END DESCRIPTION:
XS GIS Cut Line= 4
      2390668.88     13144526.23      2391084.52     13144396.35
      2391200.15     13143994.98      2390648.16     13143161.79
#Sta/Elev= 30
  4470.9   37.82  4501.1   37.32  4583.4   32.23  4595.4   30.58  4723.3   24.69
  4820.7   23.12  4899.2   23.75  4923.6   23.08  4926.4   22.58  4929.6   23.08
  4942.8   23.67  5030.7   24.19  5151.6   24.35  5156.8   23.34    5218   25.98
    5263   24.58  5368.4   25.16  5523.4   26.22  5555.7   25.76  5678.6   27.13
  5756.8   25.84    5863   26.33  5930.4   26.47  5965.2   26.65  6086.2   29.78
  6096.7   29.38  6102.7   30.96  6125.5   30.51  6171.3   33.34  6323.5   36.24
#Mann= 13 ,-1 , 0
  4470.9      .1       0  4583.4     .12       0  4923.6     .07       0
  4929.6     .12       0  4942.8     .16       0  5368.4     .12       0
  5523.4     .16       0  5555.7     .12       0    5863     .16       0
  5930.4     .12       0  5965.2     .16       0  6086.2     .12       0
  6171.3     .16       0
Bank Sta=4899.2,5030.7
XS Rating Curve= 0 ,0
Exp/Cntr=0.3,0.1

Type RM Length L Ch R = 1 ,5780    ,274,274,274
BEGIN DESCRIPTION:
Mapping XS b4007f3e
END DESCRIPTION:
XS GIS Cut Line= 4
      2391045.36      13144758.7      2391411.74     13144770.15
      2391728.54     13144350.29      2391873.58     13143888.46
#Sta/Elev= 30
  4504.8    20.7  4557.2   20.21  4577.2   21.31  4637.2   19.73  4680.4   20.13
  4827.3   19.73  4860.8   20.56  4880.3   20.08  4927.3   19.62  4950.2    20.6
  4977.3   19.14  4985.6   19.88  4991.9   16.91  4997.2   16.06  4999.9   15.56
  5003.2   16.06  5013.3    17.3    5021   18.13  5027.2   20.29  5035.5   20.45
  5070.9   20.49  5085.5   17.28  5091.8   19.55  5100.1   20.03  5256.2   18.76
  5511.2   23.38  5673.2   22.25  5694.4   24.86  5710.9   22.03  5881.4   21.05
#Mann= 6 ,-1 , 0
  4504.8     .12       0  4680.4     .16       0  4860.8     .12       0
  4880.3     .05       0  4997.2     .04       0  5003.2     .05       0
#XS Ineff= 2 , 0
       0 4850.91   20.88 5068.18       0   20.55
Permanent Ineff=
       T       T
Bank Sta=4991.9,5013.3
XS Rating Curve= 0 ,0
Exp/Cntr=0.3,0.1

Type RM Length L Ch R = 1 ,5506    ,437,437,437
XS GIS Cut Line= 4
     2391307.712    13144939.857     2391644.518    13144877.357
     2391838.962    13144481.523     2391894.518     13144116.94
#Sta/Elev= 30
    1000      20 1039.11 19.9276 1087.99 20.7583 1185.76 20.6073 1205.31 20.2884
 1215.09 19.3245 1224.86 15.6643 1244.42 18.7249 1263.97 18.6171 1273.75 17.2388
  1293.3 20.3131 1312.85 21.4843 1371.86 20.6939 1411.43 20.1479 1460.89 17.7949
 1500.46 17.4103 1520.25 16.3318 1569.71 17.7361  1579.6 17.4902 1609.28 17.2885
 1619.17 17.2758 1629.06 18.1645 1648.85 17.3953  1718.1 17.6786 1777.45 18.8829
 1787.34 18.5493 1856.25 20.7128 1905.48 20.9053 2013.77 22.6853  2131.9 22.2323
#Mann= 8 ,-1 , 0
    1000     .12       0 1185.76     .16       0 1215.09     .05       0
  1293.3      .1       0 1371.86     .12       0 1411.43     .05       0
  1579.6     .04       0 1609.28     .05       0
#XS Ineff= 2 , 0
       0 1313.64   21.42               0
Permanent Ineff=
       T       F
Bank Sta=1500.46,1569.71
XS Rating Curve= 0 ,0
Exp/Cntr=0.3,0.1

Type RM Length L Ch R = 1 ,5069    ,0,0,0
BEGIN DESCRIPTION:
UNT107 IN BACR 1.0
END DESCRIPTION:
XS GIS Cut Line= 4
      2391365.95     13145002.98      2391747.62      13145212.9
      2392079.69     13144899.92      2392129.26     13144221.14
#Sta/Elev= 30
  4309.6   19.49  4469.5   18.35  4505.6   17.67  4513.1   13.61  4579.7   16.96
  4608.4   14.76  4631.2   19.34  4638.1   25.91    4654   28.15  4659.9   26.51
  4711.1   29.14  4741.3   17.79  4770.9   13.54  4810.9   13.94  4891.1   16.49
  4897.9   15.52  4902.2    9.94    4905    9.44  4908.2    9.94  5091.5    9.95
  5096.2    9.94  5103.1   13.39  5117.2   15.39    5221   15.61  5517.7   17.18
  5616.6   17.58  5660.4   19.12  5715.5   20.14  5722.6    20.5  5882.1   21.69
#Mann= 13 ,-1 , 0
  4309.6     .12       0  4469.5     .08       0  4579.7      .1       0
  4810.9     .05       0  4902.2    .033       0  4908.2     .05       0
  5091.5     .08       0    5221      .1       0  5517.7     .08       0
  5616.6     .05       0  5660.4     .08       0  5715.5     .05       0
  5722.6     .08       0
Bank Sta=4902.2,5096.2
XS Rating Curve= 0 ,0
Exp/Cntr=0.3,0.1

Chan Stop Cuts=-1
Use User Specified Reach Order=0
Composite Channel Slope=5