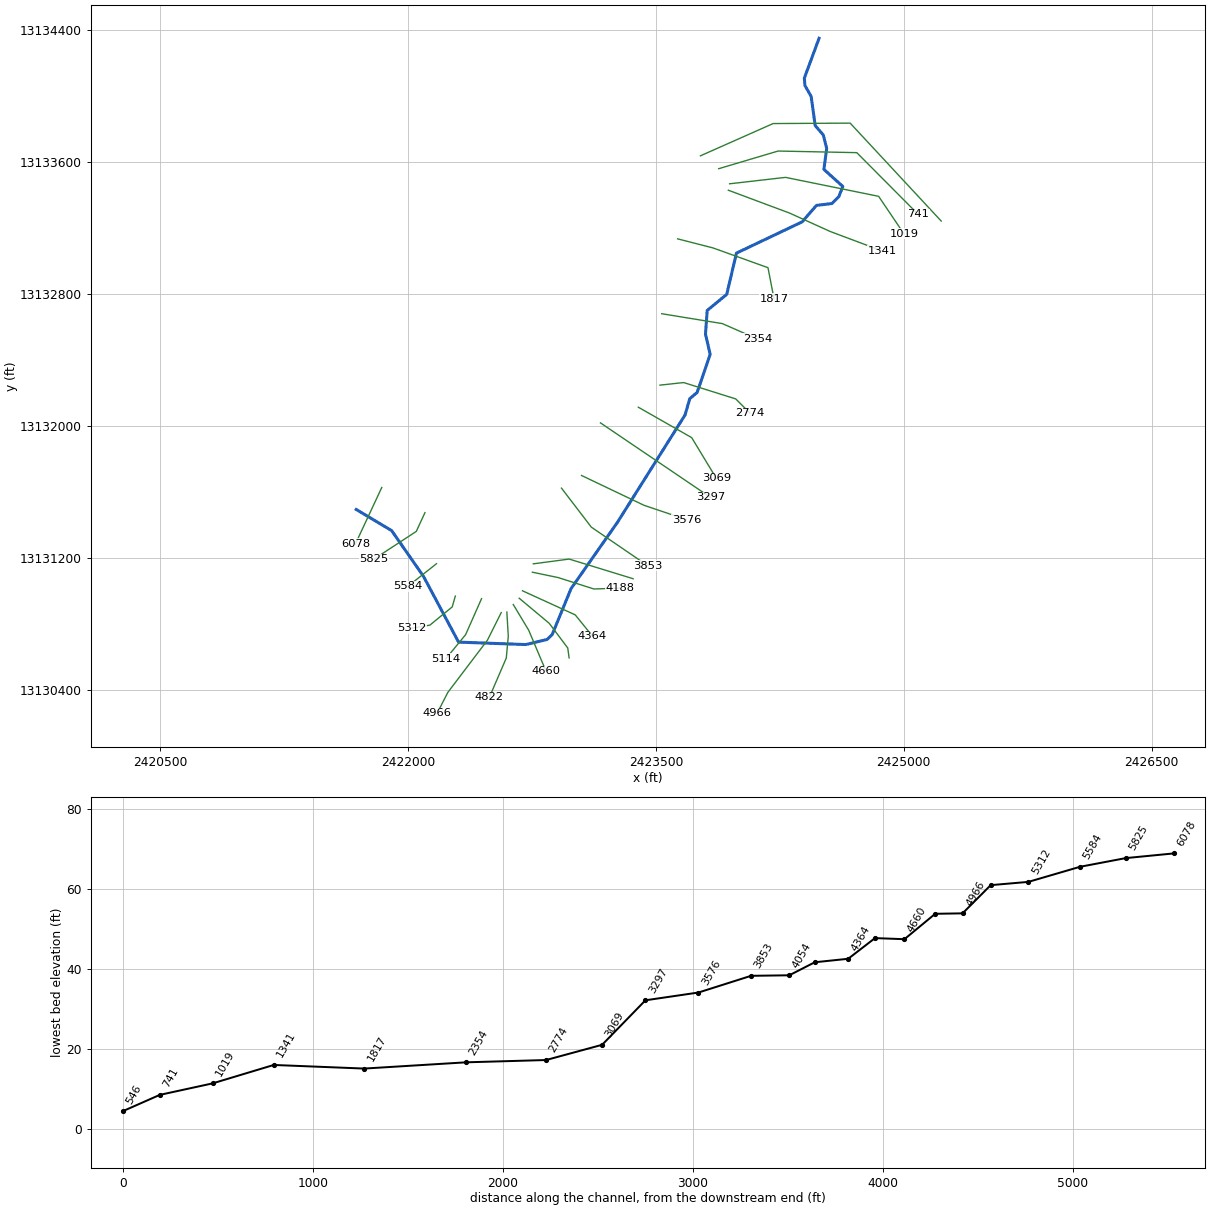
--- UNT108 IN BACR.prj (project) ---

Proj Title=UNT108 IN BACR Base Level Engineering
Current Plan=p01
Default Exp/Contr=0.3,0.1
English Units
Geom File=g01
Flow File=f01
Plan File=p01
Y Axis Title=Elevation
X Axis Title(PF)=Main Channel Distance
X Axis Title(XS)=Station
BEGIN DESCRIPTION:
UNT108 IN BACR
END DESCRIPTION:
DSS File=dss
DSS Export Rating Curves= 0
DSS Export Rating Curve Sorted= 0
DSS Export Volume Flow Curves= 0
DXF OffsetX= 0
DXF OffsetY= 0
DXF ScaleX= 1
DXF ScaleY= 10

--- UNT108 IN BACR.p01 (plan) ---

Plan Title=Multiple Run
Program Version=4.10
Short Identifier=Multiple Run
Geom File=g01
Flow File=f01
Subcritical Flow
K Sum by GR= 0
Std Step Tol= 0.01
Critical Tol= 0.01
Num of Std Step Trials= 20
Max Error Tol= 0.3
Flow Tol Ratio= 0.001
Split Flow NTrial= 30
Split Flow Tol= 0.02
Split Flow Ratio= 0.02
Log Output Level= 0
Friction Slope Method= 1
Unsteady Friction Slope Method= 2
Unsteady Bridges Friction Slope Method= 1
Parabolic Critical Depth
Global Vel Dist= 1 , 1 , 1
Global Log Level= 0
CheckData=True
Encroach Param=-1 ,0,0, 0
BEGIN DESCRIPTION:
Multiple Run
END DESCRIPTION:
Computation Interval=1HOUR
Output Interval=1HOUR
Run HTab= 0
Run UNet= 0
Run PostProcess= 0
Run WQNet= 0
UNET Theta= 1
UNET Theta Warmup= 1
UNET ZTol= 0.02
UNET ZSATol= 0.05
UNET MxIter= 20
UNET MaxInSteps= 0
UNET DtIC= 0
UNET DtMin= 0
UNET MaxCRTS= 20
UNET WFStab= 2
UNET SFStab= 1
UNET WFX= 1
UNET SFX= 1
UNET DSS MLevel= 4
UNET DZMax Abort= 100
UNET Convert EG Bridges= 0
UNET Use Existing IB Tables=-1
UNET Froude Reduction=False
UNET Froude Limit= 1
UNET Froude Power= 10
UNET Time Slicing=0,0, 5
UNET Junction Losses=0
Instantaneous Interval=1HOUR
DSS File=dss
Write IC File= 0
Write IC File at Sim End=0
Echo Input=False
Echo Parameters=False
Echo Output=False
Write Detailed= 0
WQ AD Non Conservative
WQ ULTIMATE=-1
WQ Max Comp Step=1HOUR
WQ Output Interval=15MIN
WQ Output Selected Increments= 0
WQ Output face flow=0
WQ Output face velocity=0
WQ Output face area=0
WQ Output face dispersion=0
WQ Output cell volume=0
WQ Output cell surface area=0
WQ Output cell continuity=0
WQ Output cumulative cell continuity=0
WQ Output face conc=0
WQ Output face dconc_dx=0
WQ Output face courant=0
WQ Output face peclet=0
WQ Output face adv mass=0
WQ Output face disp mass=0
WQ Output cell mass=0
WQ Output cell source sink temp=0
WQ Output cell source sink nsm=0
WQ Output MaxMinRange=-1
WQ Daily Max Min Mean=-1
WQ Daily Range=0
WQ Daily Time=0
WQ Create Restart=0
WQ Fixed Restart=0
WQ System Summary=0
WQ Use Fixed Temperature=0
Sorting and Armoring Iterations= 10
XS Update Threshold= 0.02
Hydraulics Update Threshold= 0.02
Energy Slope Method= 1
Volume Change Method= 0
XS Weighting Method= 0
Number of US Weighted Cross Sections= 1
Number of DS Weighted Cross Sections= 1
Upstream XS Weight=0.25
Main XS Weight=0.5
Downstream XS Weight=0.25
Number of DS XS's Weighted with US Boundary= 1
Upstream Boundary Weight= 1
Weight of XSs Associated with US Boundary= 0
Number of US XS's Weighted with DS Boundary= 1
Downstream Boundary Weight= 0.5
Weight of XSs Associated with DS Boundary= 0.5
Sediment Output Level= 4
Mass or Volume Output= 0
Output Increment Type= 1
Profile and TS Output Increment= 10
XS Output Flag= 0
XS Output Increment= 10
Disregard all LS=0
Disregard all Conn=0
Disregard all Breaches=0
Disregard all Pumps=0

--- UNT108 IN BACR.f01 (steady flow) ---

Flow Title=Multiple
Program Version=4.10
Number of Profiles= 7
Profile Names=10-year,25-year,50-year,1pct_min,100-year,1pct_plu,500-year
River Rch & RM=UNT108 IN BACR,Reach-1         ,6078
     109     136     156     131     177     239     229
River Rch & RM=UNT108 IN BACR,Reach-1         ,3069
     186     244     288     250     339     458     471
Boundary for River Rch & Prof#=UNT108 IN BACR,Reach-1         , 1
Up Type= 0
Dn Type= 3
Dn Slope=0.02
Boundary for River Rch & Prof#=UNT108 IN BACR,Reach-1         , 2
Up Type= 0
Dn Type= 3
Dn Slope=0.02
Boundary for River Rch & Prof#=UNT108 IN BACR,Reach-1         , 3
Up Type= 0
Dn Type= 3
Dn Slope=0.02
Boundary for River Rch & Prof#=UNT108 IN BACR,Reach-1         , 4
Up Type= 0
Dn Type= 3
Dn Slope=0.02
Boundary for River Rch & Prof#=UNT108 IN BACR,Reach-1         , 5
Up Type= 0
Dn Type= 3
Dn Slope=0.02
Boundary for River Rch & Prof#=UNT108 IN BACR,Reach-1         , 6
Up Type= 0
Dn Type= 3
Dn Slope=0.02
Boundary for River Rch & Prof#=UNT108 IN BACR,Reach-1         , 7
Up Type= 0
Dn Type= 3
Dn Slope=0.02
DSS Import GetInterval= 0
DSS Import GetPeak= 0
DSS Import FillOption= 0

--- UNT108 IN BACR.g01 (geometry) ---

Geom Title=Existing Conditions
Program Version=4.10

River Reach=UNT108 IN BACR  ,Reach-1
Reach XY= 30
      2421686.62     13131494.77       2421900.4     13131367.24
      2422092.89     13131090.77      2422305.71     13130692.18
       2422712.4     13130677.43      2422841.17     13130708.05
      2422872.42     13130737.91      2422986.31     13131015.69
      2423267.56     13131417.77      2423676.59     13132067.08
      2423705.06     13132165.69       2423749.5     13132203.19
      2423828.67     13132433.74       2423800.2     13132556.66
      2423810.62     13132699.72      2423928.67     13132796.94
      2423987.72     13133046.85      2424385.41     13133236.07
      2424471.84     13133335.65      2424565.79     13133346.93
      2424607.13     13133388.26      2424631.55     13133450.27
      2424516.94     13133553.61      2424533.85      13133679.5
      2424513.18     13133762.18      2424464.33     13133818.55
       2424439.9     13133995.17      2424402.32     13134060.93
      2424398.56     13134106.03      2424487.72     13134346.85

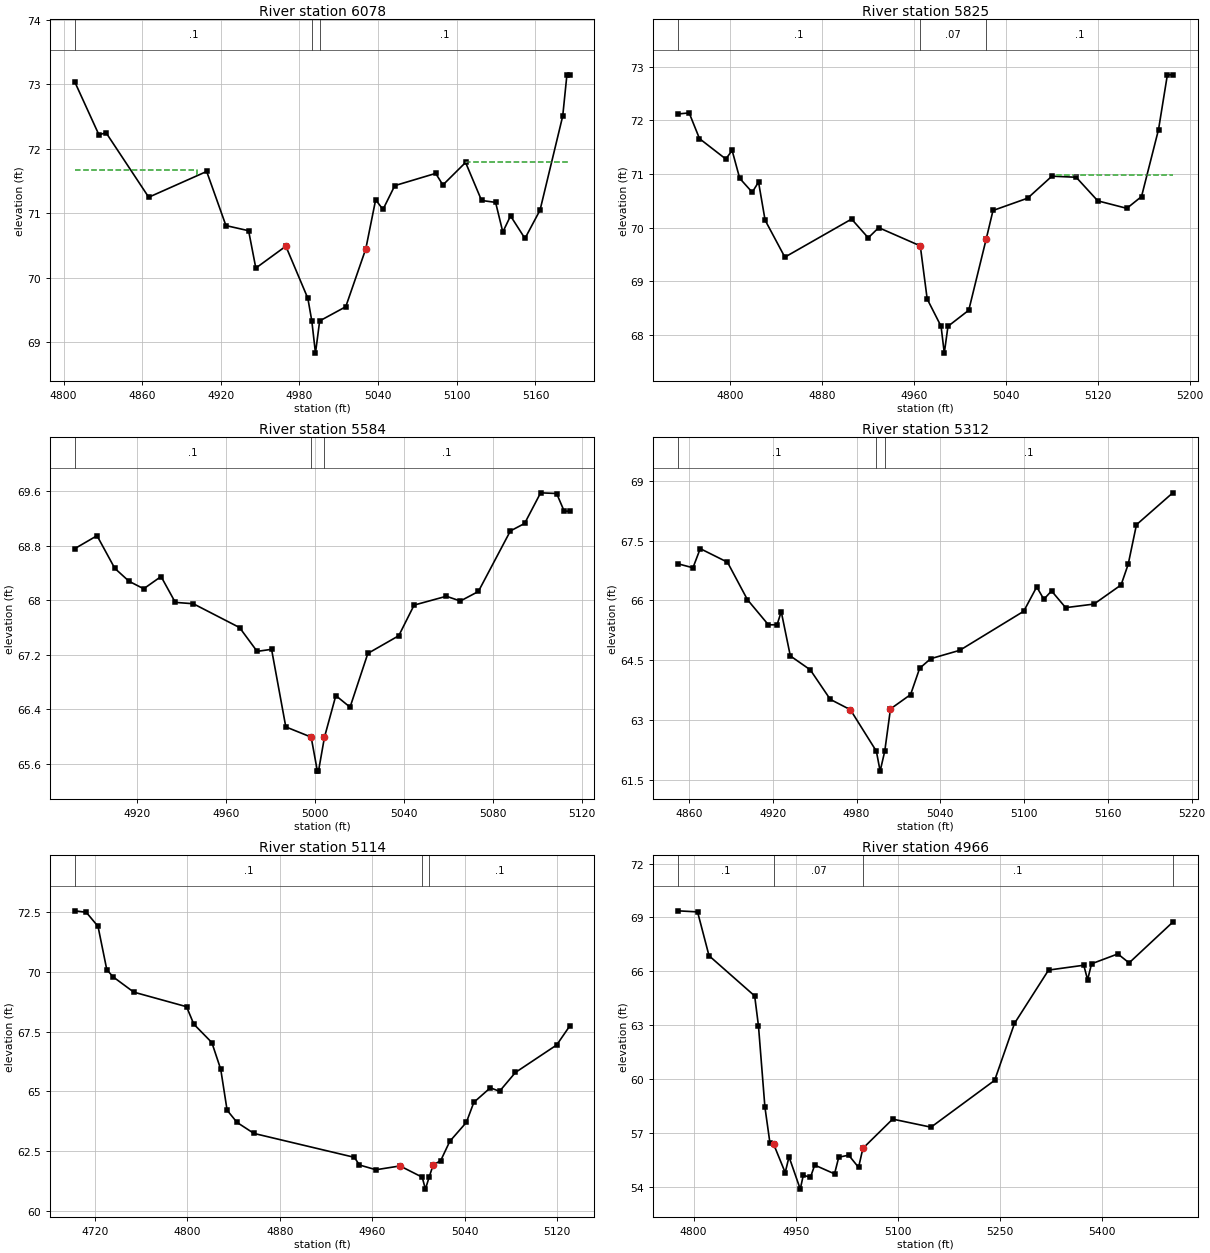
Type RM Length L Ch R = 1 ,6078    ,253,253,253
BEGIN DESCRIPTION:
UNT108 IN BACR 13.0
END DESCRIPTION:
XS GIS Cut Line= 2
      2421840.71     13131627.99      2421681.02     13131286.04
#Sta/Elev= 30
  4808.6   73.04    4827   72.22  4832.5   72.25    4865   71.25  4909.2   71.65
  4923.9   70.81  4941.2   70.73  4946.7   70.15  4969.6   70.49  4986.4   69.68
  4989.4   69.33  4992.2   68.83  4995.4   69.33  5015.3   69.55  5030.6   70.45
  5038.1   71.21  5043.7   71.06  5052.7   71.43  5083.9   71.62  5089.4   71.44
  5106.7   71.79  5118.9    71.2  5129.6   71.17  5135.1   70.71    5141   70.96
    5152   70.61  5163.5   71.05  5180.8   72.51    5184   73.15    5186   73.15
#Mann= 3 ,-1 , 0
  4808.6      .1       0  4989.4     .07       0  4995.4      .1       0
#XS Ineff= 2 , 0
       0 4901.67   71.68 5106.94       0    71.8
Permanent Ineff=
       T       T
Bank Sta=4969.6,5030.6
XS Rating Curve= 0 ,0
Exp/Cntr=0.3,0.1

Type RM Length L Ch R = 1 ,5825    ,241,241,241
BEGIN DESCRIPTION:
Mapping XS 5a6c1fe1
END DESCRIPTION:
XS GIS Cut Line= 4
      2422102.05     13131475.64      2422049.59     13131362.17
      2421846.47     13131229.36      2421795.05     13131192.95
#Sta/Elev= 30
  4754.5   72.12  4764.2   72.14  4773.2   71.66  4796.1   71.28  4801.6   71.44
  4808.2   70.92  4819.1   70.66  4824.6   70.85  4830.3   70.14  4847.5   69.45
  4905.6   70.16  4920.1   69.81  4929.2      70  4965.4   69.66  4971.4   68.67
  4983.5   68.16  4986.3   67.66  4989.5   68.16  5007.6   68.46  5022.7   69.78
  5028.7   70.32  5058.9   70.55    5080   70.96  5101.1   70.94  5119.9    70.5
  5145.2   70.36    5158   70.58  5172.8   71.83  5180.5   72.85  5185.2   72.85
#Mann= 3 , 0 , 0
  4754.5      .1       0  4965.4     .07       0  5022.7      .1       0
#XS Ineff= 2 , 0
       0                 5084.03       0   70.98
Permanent Ineff=
       F       T
Bank Sta=4965.4,5022.7
XS Rating Curve= 0 ,0
Exp/Cntr=0.3,0.1

Type RM Length L Ch R = 1 ,5584    ,272,272,272
BEGIN DESCRIPTION:
Mapping XS 0d1746d7
END DESCRIPTION:
XS GIS Cut Line= 2
        2422172.     13131166.87       2421997.5     13131028.83
#Sta/Elev= 30
  4891.9   68.76  4901.9   68.95  4909.9   68.47  4916.3   68.28  4922.9   68.17
  4930.7   68.35  4937.1   67.97  4945.2   67.95    4966    67.6  4973.9   67.25
  4980.4   67.28  4986.8   66.14  4998.2   65.99    5001   65.49  5001.5   65.49
  5004.2   65.99  5009.3    66.6  5015.7   66.43  5023.7   67.22  5037.6   67.48
  5044.5   67.93    5059   68.06  5065.3   67.99  5073.4   68.13  5087.8   69.02
  5094.2   69.13  5101.4   69.58  5108.6   69.57    5112   69.31  5114.4   69.31
#Mann= 3 ,-1 , 0
  4891.9      .1       0  4998.2     .07       0  5004.2      .1       0
Bank Sta=4998.2,5004.2
XS Rating Curve= 0 ,0
Exp/Cntr=0.3,0.1

Type RM Length L Ch R = 1 ,5312    ,198,198,198
BEGIN DESCRIPTION:
Mapping XS 97da2db1
END DESCRIPTION:
XS GIS Cut Line= 4
      2422286.01      13130970.9      2422267.32     13130905.48
      2422131.89     13130794.96      2422022.09      13130776.4
#Sta/Elev= 30
  4852.2   66.92  4862.9   66.82  4868.1    67.3  4887.6   66.96  4901.9   66.02
  4916.9   65.39  4923.1   65.39  4926.1   65.72  4932.6   64.61  4946.9   64.26
  4961.2   63.52  4975.6   63.26  4994.2   62.22  4996.9   61.72  5000.2   62.22
  5004.3   63.28  5018.7   63.64  5025.2    64.3  5033.1   64.54  5053.9   64.75
  5099.7   65.73    5109   66.34  5114.1   66.03  5119.6   66.24  5129.7   65.82
    5150   65.91  5169.4   66.39  5174.5   66.91  5180.4    67.9  5206.4    68.7
#Mann= 3 ,-1 , 0
  4852.2      .1       0  4994.2     .07       0  5000.2      .1       0
Bank Sta=4975.6,5004.3
XS Rating Curve= 0 ,0
Exp/Cntr=0.3,0.1

Type RM Length L Ch R = 1 ,5114    ,148,148,148
BEGIN DESCRIPTION:
UNT108 IN BACR 12.0
END DESCRIPTION:
XS GIS Cut Line= 3
      2422444.77     13130955.27      2422348.27     13130737.36
      2422227.84     13130590.69
#Sta/Elev= 30
  4702.5   72.55  4712.4   72.49  4722.6    71.9  4730.2   70.09  4735.6   69.79
  4753.5   69.15  4799.2   68.54  4805.5   67.81  4821.1   67.04  4828.8   65.92
  4834.3   64.21  4842.9    63.7  4857.5   63.24  4944.4   62.24  4948.8   61.92
  4963.1   61.72  4983.9   61.88  5003.1   61.41  5005.9   60.91  5009.1   61.41
  5012.6   61.92  5019.1    62.1    5027   62.91  5041.3    63.7  5047.8   64.54
  5062.1   65.15    5070      65  5083.8   65.79  5119.5   66.94  5130.6   67.72
#Mann= 3 ,-1 , 0
  4702.5      .1       0  5003.1     .07       0  5009.1      .1       0
Bank Sta=4983.9,5012.6
XS Rating Curve= 0 ,0
Exp/Cntr=0.3,0.1

Type RM Length L Ch R = 1 ,4966    ,144,144,144
BEGIN DESCRIPTION:
UNT108 IN BACR 11.0
END DESCRIPTION:
XS GIS Cut Line= 4
      2422563.86      13130870.9      2422480.55     13130704.28
      2422240.97     13130388.31      2422175.52     13130260.85
#Sta/Elev= 30
  4777.2   69.37  4805.9   69.31  4822.7   66.87  4889.7   64.63  4895.3   62.95
  4904.7   58.45  4912.1   56.44  4917.7   56.36  4934.5   54.79  4940.1   55.67
  4956.6   53.87  4961.1   54.65  4971.5   54.52  4977.8   55.21  5006.9   54.72
  5013.1   55.65  5027.7   55.76  5042.2   55.08  5048.5   56.14  5092.2   57.77
  5148.5   57.32  5241.9   59.93    5271    63.1    5321   66.07  5372.7   66.34
  5378.3   65.53  5384.1   66.42  5422.7   66.97  5439.2   66.47  5503.3   68.74
#Mann= 4 ,-1 , 0
  4777.2      .1       0  4917.7     .07       0  5048.5      .1       0
  5503.3      .1       0
Bank Sta=4917.7,5048.5
XS Rating Curve= 0 ,0
Exp/Cntr=0.3,0.1

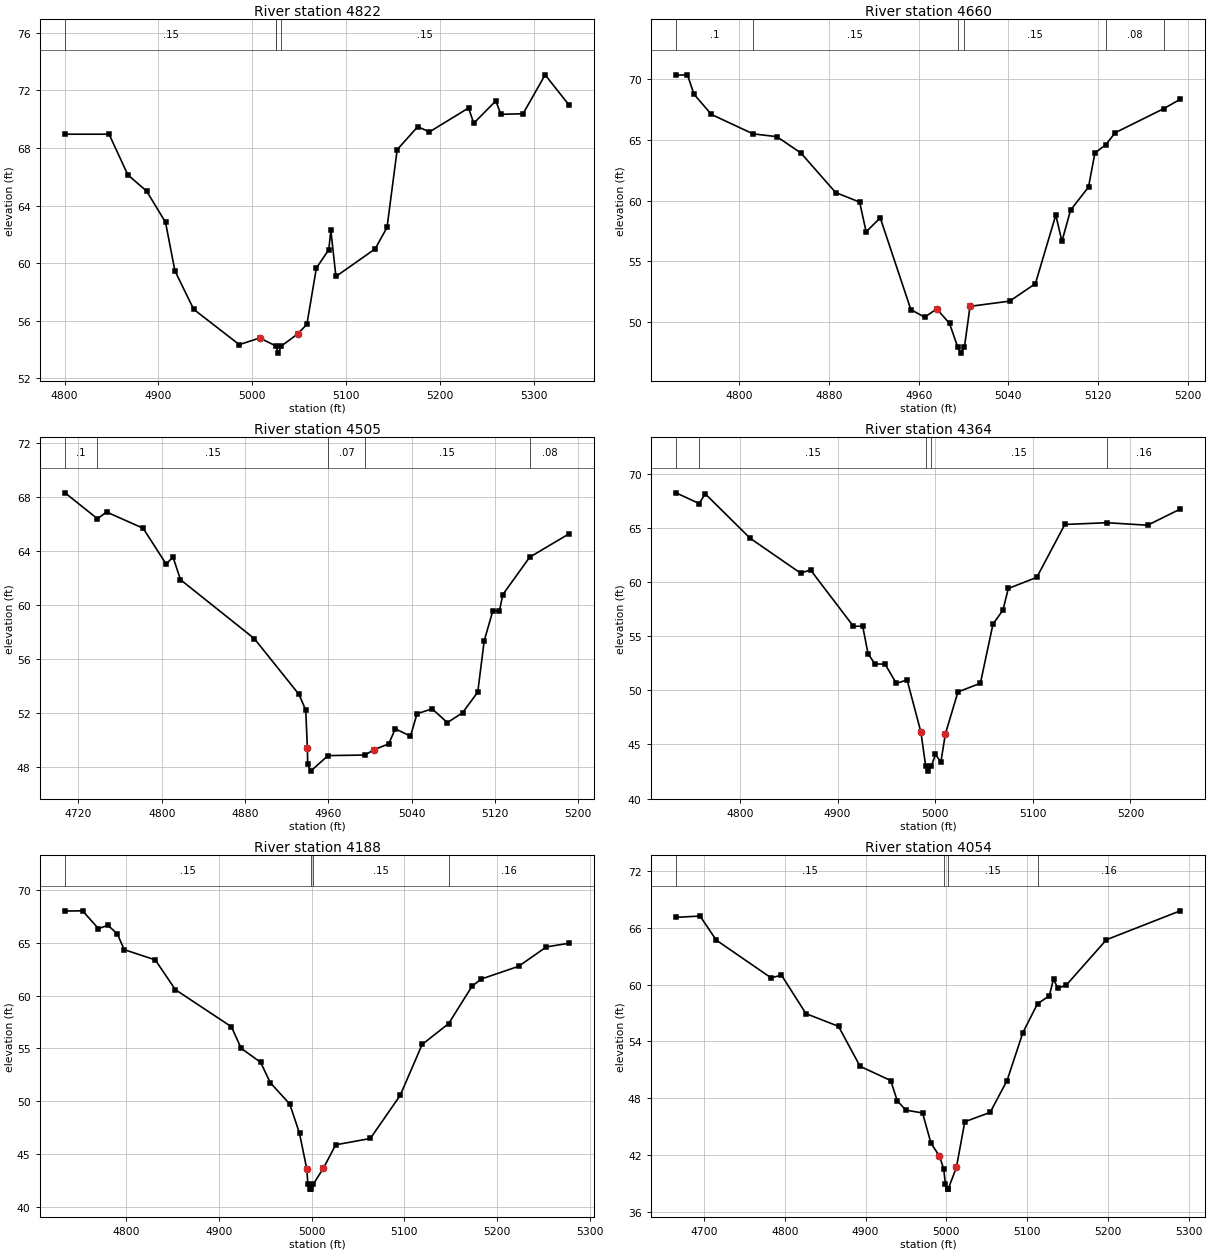
Type RM Length L Ch R = 1 ,4822    ,162,162,162
BEGIN DESCRIPTION:
Mapping XS eb3d96fd
END DESCRIPTION:
XS GIS Cut Line= 4
      2422597.95     13130873.64      2422606.63     13130727.81
      2422594.48     13130595.87      2422492.39     13130358.81
#Sta/Elev= 30
  4800.5   68.95  4847.4   68.95  4867.4   66.13  4887.4      65  4907.5   62.84
  4917.5   59.47  4937.5    56.8    4986   54.35  5007.8   54.81  5024.9   54.26
  5027.6   53.76  5030.9   54.26    5048   55.08    5058   55.76  5068.1   59.67
  5081.3   60.93  5083.5   62.27  5088.9   59.08  5130.6   60.99  5143.3   62.48
  5154.1   67.88    5176   69.47  5188.5   69.11  5230.1   70.77  5235.6   69.71
  5259.1   71.26  5264.5   70.33  5288.1   70.37  5311.6   73.07  5337.2   70.96
#Mann= 4 ,-1 , 0
  4800.5     .15       0  5024.9     .05       0  5024.9     .07       0
  5030.9     .15       0
Bank Sta=5007.8,5048
XS Rating Curve= 0 ,0
Exp/Cntr=0.3,0.1

Type RM Length L Ch R = 1 ,4660    ,155,155,155
BEGIN DESCRIPTION:
Mapping XS 30f26f78
END DESCRIPTION:
XS GIS Cut Line= 3
      2422636.81     13130919.53      2422730.55     13130763.31
      2422834.71     13130516.79
#Sta/Elev= 30
  4743.5   70.35  4753.7   70.38  4759.5   68.78  4775.1   67.11  4812.2   65.51
  4833.4   65.28  4854.8   63.94  4885.9   60.67  4907.3   59.88  4913.1   57.43
  4925.7   58.58    4953   51.01  4965.3   50.38  4976.1   51.07  4987.5   49.87
  4994.8   47.92  4997.6   47.42  5000.8   47.92  5005.8   51.28  5041.2   51.71
  5064.1   53.15  5082.3   58.81  5087.8   56.65  5095.5   59.22  5111.5   61.12
  5117.2   63.93  5127.1   64.63  5135.2    65.6  5178.6   67.59  5193.3   68.36
#Mann= 6 ,-1 , 0
  4743.5      .1       0  4812.2     .15       0  4994.8     .07       0
  5000.8     .15       0  5127.1     .08       0  5178.6     .05       0
Bank Sta=4976.1,5005.8
XS Rating Curve= 0 ,0
Exp/Cntr=0.3,0.1

Type RM Length L Ch R = 1 ,4505    ,141,141,141
BEGIN DESCRIPTION:
Mapping XS 00fea7db
END DESCRIPTION:
XS GIS Cut Line= 4
      2422672.59     13130957.85      2422854.83     13130805.58
      2422966.59     13130656.56      2422974.69     13130596.66
#Sta/Elev= 30
  4707.1   68.29  4738.3   66.37    4747   66.87  4782.1   65.67  4804.3   63.01
  4810.8   63.54    4818   61.86  4888.9    57.5  4931.8   53.37  4938.3   52.21
 4939.86    49.4  4940.2   48.19    4943   47.69  4959.7   48.84  4995.2   48.88
  5003.5   49.26    5018   49.71  5024.3   50.82  5038.9   50.28  5045.2   51.94
  5059.7    52.3  5074.3   51.28  5088.9   52.01  5103.5   53.54  5109.7   57.34
    5118   59.56  5124.3   59.55  5127.6   60.76  5153.4   63.53  5191.3   65.26
#Mann= 5 ,-1 , 0
  4707.1      .1       0  4738.3     .15       0  4959.7     .07       0
  4995.2     .15       0  5153.4     .08       0
Bank Sta=4939.86,5003.5
XS Rating Curve= 0 ,0
Exp/Cntr=0.3,0.1

Type RM Length L Ch R = 1 ,4364    ,176,176,176
BEGIN DESCRIPTION:
UNT108 IN BACR 10.0
END DESCRIPTION:
XS GIS Cut Line= 3
      2422692.38     13131002.88       2423011.8     13130857.06
      2423115.95      13130728.6
#Sta/Elev= 30
  4734.5   68.22  4758.2   67.23  4764.4   68.13  4810.5   64.02  4862.1   60.81
  4872.3    61.1  4916.3   55.89  4925.7   55.92  4931.2   53.37  4938.2   52.43
  4948.7    52.4  4960.2   50.63  4971.2   50.95 4985.42   46.11  4990.2   43.03
    4993   42.53  4996.2   43.03  5000.3   44.07  5005.8   43.36 5010.42   45.96
  5023.3   49.84  5046.3   50.64  5059.2    56.1  5069.4   57.39  5074.9   59.39
  5104.1   60.42  5132.8    65.3    5176   65.46  5217.6   65.23    5251   66.72
#Mann= 5 ,-1 , 0
  4734.5      .1       0  4758.2     .15       0  4990.2     .07       0
  4996.2     .15       0    5176     .16       0
Bank Sta=4985.42,5010.42
XS Rating Curve= 0 ,0
Exp/Cntr=0.3,0.1

Type RM Length L Ch R = 1 ,4188    ,134,134,134
BEGIN DESCRIPTION:
Mapping XS 89c6ba98
END DESCRIPTION:
XS GIS Cut Line= 4
      2422752.42     13131115.37      2422908.67     13131082.82
      2423124.81     13131013.81      2423282.32     13131019.01
#Sta/Elev= 30
  4733.7   68.02  4752.7   68.04  4769.8   66.35    4780   66.67  4790.2   65.85
  4797.6   64.36  4831.1   63.39  4852.8   60.57  4913.3   57.05  4923.8   55.01
  4944.8   53.68  4955.3   51.74  4976.3   49.72  4986.8   46.94 4994.58   43.59
  4995.8   42.16  4998.6   41.66  4999.1   41.66  5001.8   42.16  5012.5   43.63
  5025.8   45.86  5063.2   46.46  5095.4   50.54  5119.1   55.37  5147.7   57.35
  5173.1   60.91  5183.1   61.58  5223.2   62.78  5253.2   64.62  5277.8   64.97
#Mann= 4 ,-1 , 0
  4733.7     .15       0  4999.1     .07       0  5001.8     .15       0
  5147.7     .16       0
Bank Sta=4994.58,5012.5
XS Rating Curve= 0 ,0
Exp/Cntr=0.3,0.1

Type RM Length L Ch R = 1 ,4054    ,201,201,201
BEGIN DESCRIPTION:
UNT108 IN BACR 9.0
END DESCRIPTION:
XS GIS Cut Line= 3
      2422758.32     13131166.08      2422975.05     13131194.88
      2423362.53     13131075.79
#Sta/Elev= 30
  4665.4   67.09  4695.1   67.23  4715.2   64.69    4783   60.71  4795.9   60.99
  4826.2   56.93  4866.5   55.59  4893.2   51.37  4931.1   49.87  4939.1   47.76
  4949.6   46.75  4970.5   46.45    4981   43.24  4991.3   41.92  4996.6   40.58
  4998.9   38.91  5001.7   38.41  5002.2   38.41  5012.4    40.7  5022.8   45.52
  5054.2   46.51  5075.1   49.87  5094.7   54.93  5112.8   57.98  5127.4    58.8
  5132.6   60.59  5137.9   59.61  5148.4   59.94  5198.1   64.73  5289.4   67.78
#Mann= 4 ,-1 , 0
  4665.4     .15       0  4996.6     .07       0  5002.2     .15       0
  5112.8     .16       0
Bank Sta=4991.3,5012.4
XS Rating Curve= 0 ,0
Exp/Cntr=0.3,0.1

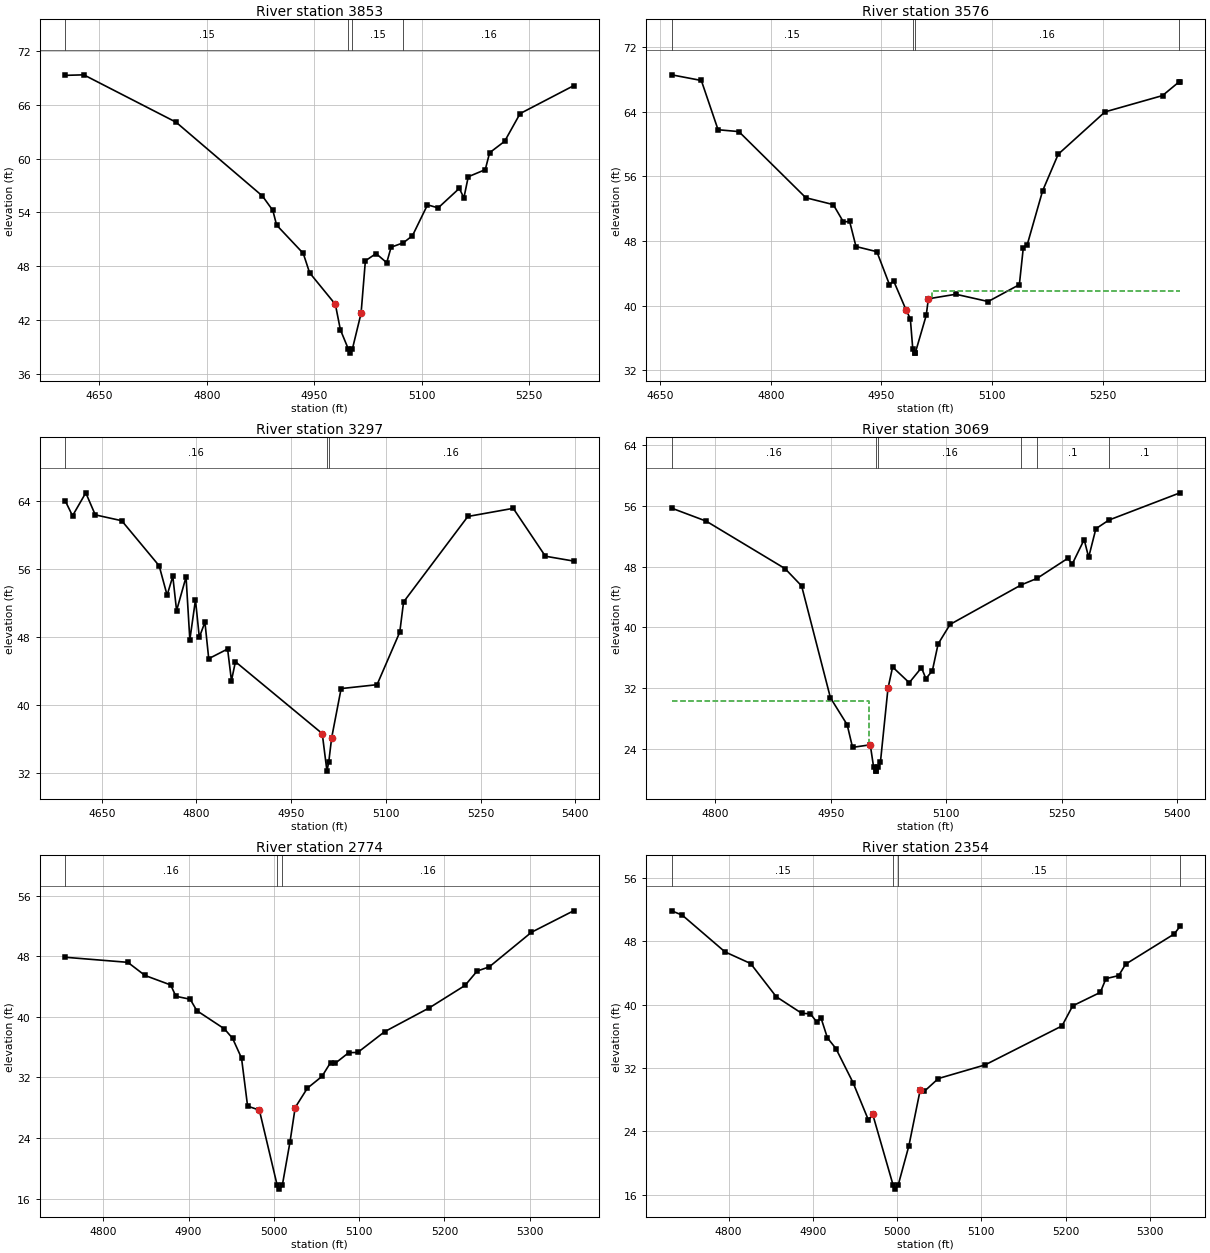
Type RM Length L Ch R = 1 ,3853    ,277,277,277
BEGIN DESCRIPTION:
Mapping XS ea2ece1e
END DESCRIPTION:
XS GIS Cut Line= 3
      2422928.47     13131624.42      2423109.02     13131388.31
      2423449.27     13131155.69
#Sta/Elev= 30
  4602.3    69.3  4628.2   69.36    4757   64.07  4877.6   55.82  4892.1   54.21
  4897.3   52.58  4934.5   49.42  4943.4   47.25  4979.3   43.73 4986.33   40.89
  4997.2   38.78    5000   38.28  5003.2   38.78  5015.2   42.73  5021.2   48.59
  5036.1    49.4    5051   48.38  5057.1   50.11  5074.1    50.6  5086.9   51.39
  5107.9   54.84  5122.8    54.5  5152.3   56.68  5158.7   55.62  5164.8   57.98
  5188.5   58.77  5194.6   60.66  5215.6   61.94  5237.1   65.03  5311.7   68.14
#Mann= 4 ,-1 , 0
  4602.3     .15       0  4997.2     .07       0  5003.2     .15       0
  5074.1     .16       0
Bank Sta=4979.3,5015.2
XS Rating Curve= 0 ,0
Exp/Cntr=0.3,0.1

Type RM Length L Ch R = 1 ,3576    ,279,279,279
BEGIN DESCRIPTION:
UNT108 IN BACR 8.0
END DESCRIPTION:
XS GIS Cut Line= 3
      2423049.96     13131700.82      2423428.47     13131520.25
       2423684.1     13131433.89
#Sta/Elev= 30
  4665.6   68.57  4705.8   67.87  4728.5   61.77  4756.7   61.54  4847.5   53.35
  4884.7    52.5  4898.4   50.36  4906.9   50.41  4915.5   47.31  4943.8   46.67
  4960.9   42.59  4966.5   43.06  4983.6   39.42  4989.2   38.35  4992.5   34.61
  4995.3   34.11  4995.8   34.11 5010.67   38.77 5013.67   40.84  5050.9    41.4
  5094.7    40.5    5137   42.59  5142.3   47.12  5147.6   47.51  5168.5    54.2
  5189.7   58.74  5253.1   63.98  5331.1      66    5354   67.73  5354.8   67.73
#Mann= 4 ,-1 , 0
  4665.6     .15       0  4992.5     .07       0  4995.8     .16       0
    5354     .08       0
#XS Ineff= 2 , 0
                         5018.56           41.82
Permanent Ineff=
       F       F
Bank Sta=4983.6,5013.67
XS Rating Curve= 0 ,0
Exp/Cntr=0.3,0.1

Type RM Length L Ch R = 1 ,3297    ,228,228,228
BEGIN DESCRIPTION:
Mapping XS 3b494358
END DESCRIPTION:
XS GIS Cut Line= 2
      2423164.47     13132019.29      2423831.14      13131567.9
#Sta/Elev= 30
  4592.1   64.07  4603.7    62.3  4624.7   65.01  4639.7   62.41  4681.6   61.72
  4740.9    56.4  4753.5   52.93  4762.5   55.16  4768.5   51.11  4783.5   55.08
  4789.5   47.67  4798.4   52.38  4804.5   47.96  4813.4   49.75  4819.4   45.44
  4849.3   46.58  4855.4   42.84  4861.7   45.08  4999.2    36.6 5006.65   32.17
  5009.6    33.3  5014.1    36.1  5029.1   41.91    5086   42.37    5122   48.57
    5128   52.13  5229.8   62.22  5301.7   63.18  5352.6   57.53  5397.2   56.96
#Mann= 3 ,-1 , 0
  4592.1     .16       0  5006.4     .07       0  5009.6     .16       0
Bank Sta=4999.2,5014.1
XS Rating Curve= 0 ,0
Exp/Cntr=0.5,0.3

Type RM Length L Ch R = 1 ,3069    ,295,295,295
BEGIN DESCRIPTION:
UNT108 IN BACR 7.0
END DESCRIPTION:
XS GIS Cut Line= 3
      2423393.75       13132114.      2423716.66     13131929.97
      2423865.97     13131683.43
#Sta/Elev= 30
  4743.6   55.71  4788.4      54  4890.7   47.75  4912.3   45.46  4949.7   30.72
  4971.4   27.18  4978.4   24.19  5001.4   24.53  5005.8   21.56  5008.6   21.06
  5009.1   21.06  5011.8   21.56  5014.6   22.24  5024.4   31.96  5030.4   34.78
    5052   32.71  5067.9   34.69  5073.6   33.25    5082   34.28  5089.5   37.82
    5105   40.39  5197.6   45.61  5217.8   46.45  5257.7   49.09  5263.6   48.34
  5279.1   51.57  5284.9   49.23  5294.3      53  5311.2   54.14  5403.5   57.73
#Mann= 6 ,-1 , 0
  4743.6     .16       0  5009.1     .07       0  5011.8     .16       0
  5197.6     .07       0  5217.8      .1       0  5311.2      .1       0
#XS Ineff= 2 , 0
       0 4999.48   30.26               0
Permanent Ineff=
       T       F
Bank Sta=5001.4,5024.4
XS Rating Curve= 0 ,0
Exp/Cntr=0.5,0.3

Type RM Length L Ch R = 1 ,2774    ,420,420,420
BEGIN DESCRIPTION:
UNT108 IN BACR 6.0
END DESCRIPTION:
XS GIS Cut Line= 4
      2423524.78     13132247.68      2423668.05     13132263.31
      2423983.15     13132164.35      2424069.07     13132078.43
#Sta/Elev= 30
  4755.4   47.87  4828.8    47.2  4848.9   45.47  4879.1   44.21  4885.1   42.72
  4901.9   42.33  4909.7   40.82    4942   38.42  4951.6   37.17  4962.1   34.56
  4969.2   28.22    4983   27.69  5003.9   17.76  5006.6   17.26  5009.9   17.76
 5018.89   23.47    5025   28.03  5039.3   30.59  5056.4   32.14  5066.4   33.96
  5071.7   33.85  5087.8   35.28  5098.3    35.3  5129.8   38.04  5182.2   41.19
  5224.1   44.15  5238.3   46.05  5252.5    46.6    5302   51.17  5351.3      54
#Mann= 3 ,-1 , 0
  4755.4     .16       0  5003.9     .07       0  5009.9     .16       0
Bank Sta=4983,5025
XS Rating Curve= 0 ,0
Exp/Cntr=0.3,0.1

Type RM Length L Ch R = 1 ,2354    ,537,537,537
BEGIN DESCRIPTION:
UNT108 IN BACR 5.0
END DESCRIPTION:
XS GIS Cut Line= 3
      2423535.25     13132679.97      2423902.42     13132620.08
      2424114.37     13132527.03
#Sta/Elev= 30
  4732.4   51.87    4745   51.32  4795.7   46.68  4826.1   45.21  4856.5   41.02
  4886.9   38.91    4897   38.86  4904.6   37.83  4909.6   38.36  4917.3   35.81
  4927.4   34.46  4947.7   30.16    4966   25.42  4971.1   26.14  4995.3   17.19
  4998.1   16.69  5001.3   17.19 5014.03   22.17  5027.5   29.25  5032.5   29.07
    5049   30.67  5104.4   32.39  5195.8   37.32  5208.5   39.86  5241.3   41.56
    5248    43.3  5263.1   43.68  5271.4   45.13    5329   48.94  5335.9    49.9
#Mann= 4 ,-1 , 0
  4732.4     .15       0  4995.3     .07       0  5001.3     .15       0
  5335.9     .05       0
Bank Sta=4971.1,5027.5
XS Rating Curve= 0 ,0
Exp/Cntr=0.3,0.1

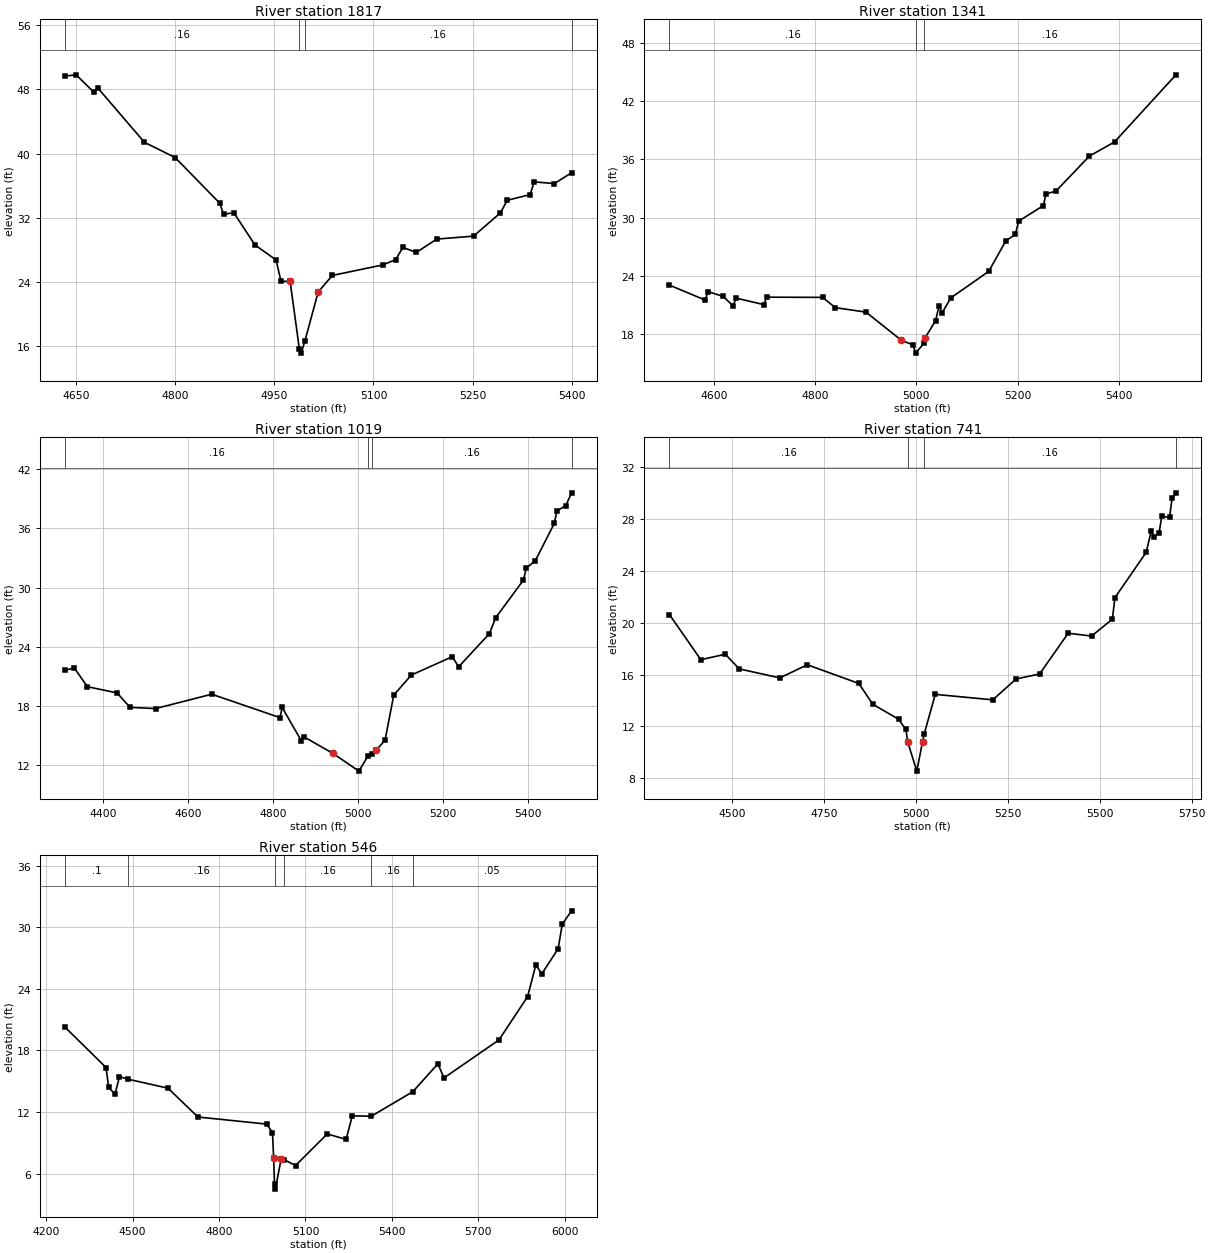
Type RM Length L Ch R = 1 ,1817    ,476,476,476
BEGIN DESCRIPTION:
UNT108 IN BACR 4.0
END DESCRIPTION:
XS GIS Cut Line= 4
      2423631.61     13133133.09      2423845.13     13133078.41
      2424178.47     13132958.62      2424214.86     13132771.44
#Sta/Elev= 30
    4634   49.65  4650.6   49.81  4677.9   47.61    4683   48.21  4753.9    41.4
  4800.3    39.5  4867.8    33.8  4873.4   32.44    4889   32.62  4920.9   28.61
  4952.8   26.74  4960.3   24.06    4974   24.09    4988   15.63  4990.8   15.13
  4996.3   16.63  5016.4   22.74  5037.8   24.81  5113.9   26.12  5133.4   26.78
  5144.6   28.31  5164.7   27.67  5195.5   29.34  5251.2   29.71  5291.9   32.61
  5302.1   34.18  5336.7   34.88  5342.8   36.47  5373.4   36.26  5399.3   37.61
#Mann= 4 ,-1 , 0
    4634     .16       0    4988     .07       0  4996.3     .16       0
  5399.3     .05       0
Bank Sta=4974,5016.4
XS Rating Curve= 0 ,0
Exp/Cntr=0.5,0.3

Type RM Length L Ch R = 1 ,1341    ,322,322,322
BEGIN DESCRIPTION:
UNT108 IN BACR 3.0
END DESCRIPTION:
XS GIS Cut Line= 4
      2423938.87     13133427.37      2424308.67     13133289.35
      2424556.07     13133177.37      2424868.54     13133060.19
#Sta/Elev= 30
  4512.5   23.04  4583.1    21.5  4588.4   22.38  4618.7   21.87  4638.3   20.89
  4643.7   21.71    4699   21.03  4704.3    21.8  4814.9   21.78  4839.8   20.72
  4900.5   20.26  4970.2   17.36  4993.3   16.88  4998.6   16.03  5015.9   17.11
  5017.5   17.62  5037.9   19.38    5045   20.94  5050.5   20.16  5068.1   21.73
  5142.9   24.46  5176.9   27.63  5195.5   28.27  5201.9   29.64  5250.7   31.24
    5256   32.45  5275.6   32.74  5341.5   36.34  5391.3   37.81  5512.5   44.73
#Mann= 3 ,-1 , 0
  4512.5     .16       0  4998.6     .07       0  5015.9     .16       0
Bank Sta=4970.2,5017.5
XS Rating Curve= 0 ,0
Exp/Cntr=0.5,0.3

Type RM Length L Ch R = 1 ,1019    ,278,278,278
BEGIN DESCRIPTION:
UNT108 IN BACR 2.0
END DESCRIPTION:
XS GIS Cut Line= 4
      2423946.28     13133466.38      2424284.51     13133505.26
      2424848.22     13133390.57      2425001.76     13133163.17
#Sta/Elev= 30
  4311.2   21.64  4332.8   21.86  4363.6   19.97  4433.4   19.34  4463.6   17.88
    4524   17.76  4655.8   19.21  4816.2   16.84  4821.3   17.87  4866.7   14.47
  4871.9   14.91  4940.7   13.22  5001.6   11.43  5023.6   13.01  5032.5   13.12
  5042.7   13.57  5063.1   14.56  5083.5   19.12  5124.8   21.15  5220.9      23
  5236.2   21.99  5308.1   25.33  5323.1   26.95  5388.3   30.76    5395   31.98
    5416    32.7  5460.7   36.48    5467   37.76    5488   38.29  5501.3   39.58
#Mann= 4 ,-1 , 0
  4311.2     .16       0  5023.6     .07       0  5032.5     .16       0
  5501.3     .05       0
Bank Sta=4940.7,5042.7
XS Rating Curve= 0 ,0
Exp/Cntr=0.3,0.1

Type RM Length L Ch R = 1 ,741     ,195,195,195
BEGIN DESCRIPTION:
Mapping XS a2b2ca01
END DESCRIPTION:
XS GIS Cut Line= 4
      2423880.21     13133557.75       2424239.8     13133664.65
      2424716.04     13133654.93      2425087.23      13133281.8
#Sta/Elev= 30
  4329.4   20.61  4414.7   17.14  4481.1   17.56  4519.5   16.43  4629.6   15.74
  4704.5   16.75  4844.5   15.31  4882.5   13.71  4952.5   12.56  4972.5   11.77
 4977.78   10.78  5002.3    8.56 5017.78   10.82  5022.5   11.43  5052.5   14.47
    5209   14.05  5272.6   15.66  5336.3   16.04  5414.1   19.18  5477.7   18.96
  5534.3   20.26  5541.3   21.92  5626.2    25.4  5640.3   27.07  5647.4   26.58
  5661.5   26.92  5668.6   28.17  5689.8    28.1  5696.9   29.59  5707.2   29.99
#Mann= 4 ,-1 , 0
  4329.4     .16       0 4977.78     .07       0  5022.5     .16       0
  5707.2     .05       0
Bank Sta=4977.78,5017.78
XS Rating Curve= 0 ,0
Exp/Cntr=0.3,0.1

Type RM Length L Ch R = 1 ,546     ,0,0,0
BEGIN DESCRIPTION:
UNT108 IN BACR 1.0
END DESCRIPTION:
XS GIS Cut Line= 4
      2423769.58     13133635.69      2424209.72     13133831.01
      2424675.86     13133833.62      2425227.02     13133240.86
#Sta/Elev= 30
  4266.1   20.26  4408.2   16.33  4417.2   14.39  4439.1   13.73  4454.7   15.44
  4485.7   15.19    4623   14.32    4727   11.51  4965.6   10.82  4985.6    9.99
 4989.58    7.52  4992.6    4.98  4995.4    4.48  5015.6     7.4  5025.6    7.36
  5065.6    6.78  5175.6    9.86    5241    9.33  5262.5   11.62  5328.8   11.59
  5472.6   13.98  5559.6    16.7  5580.6   15.32  5771.6   19.03  5870.8   23.25
  5899.2   26.33  5920.2   25.47  5976.8   27.92    5991   30.31  6023.2   31.61
#Mann= 6 ,-1 , 0
  4266.1      .1       0  4485.7     .16       0  4992.6     .07       0
  5025.6     .16       0  5328.8     .16       0  5472.6     .05       0
Bank Sta=4989.58,5015.6
XS Rating Curve= 0 ,0
Exp/Cntr=0.3,0.1

Chan Stop Cuts=-1
Use User Specified Reach Order=0
Composite Channel Slope=5