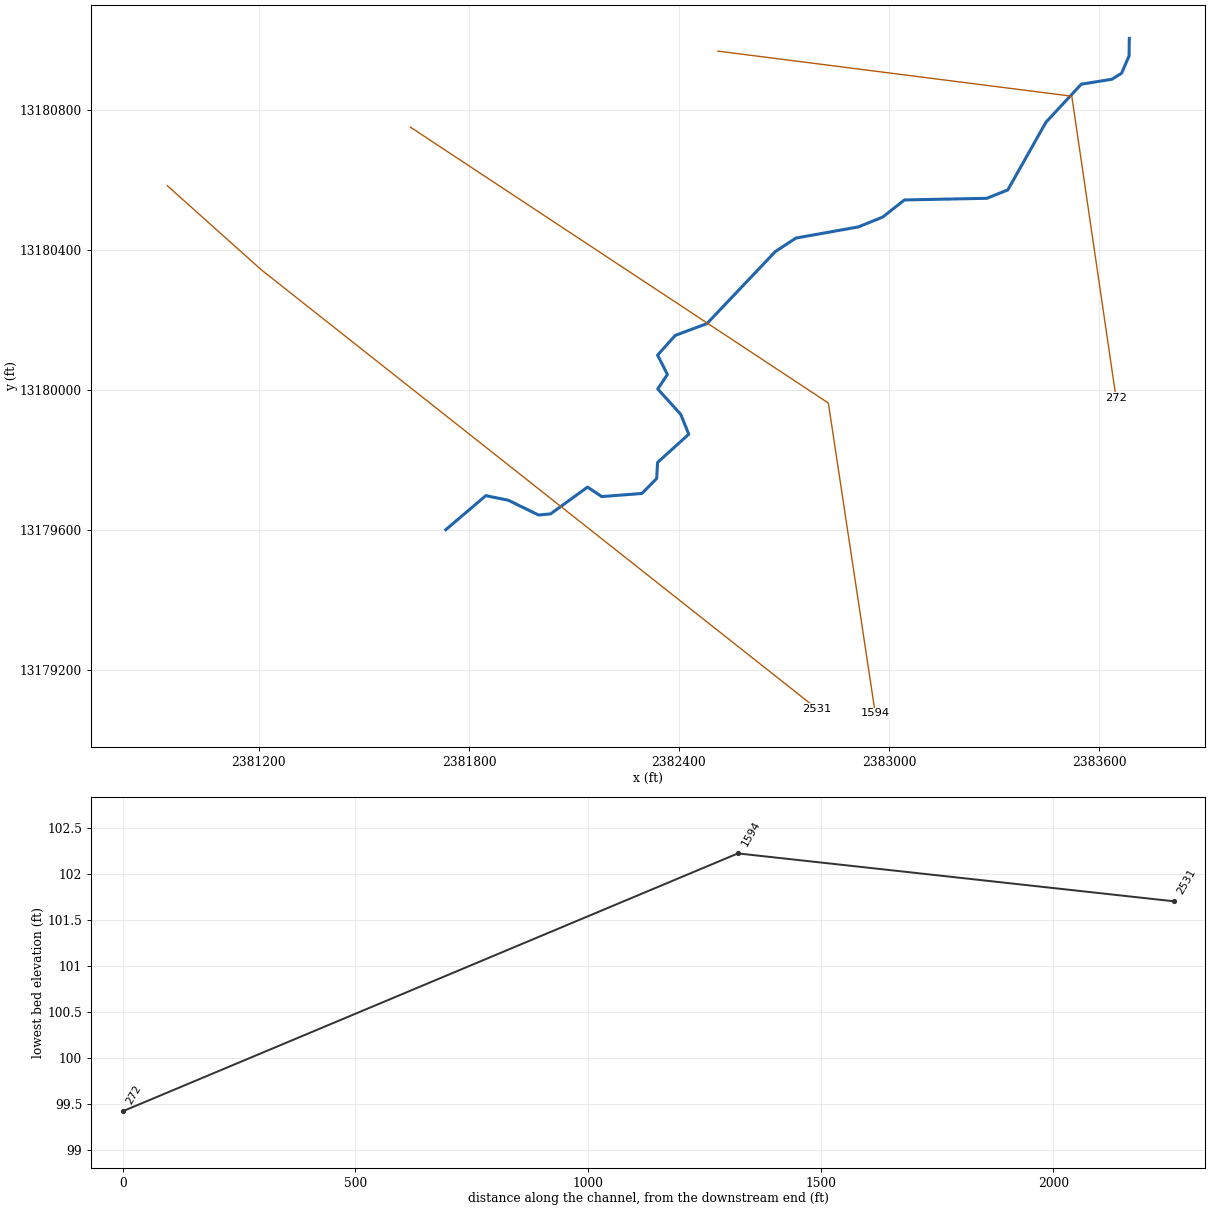
--- UNT110 IN BACR.prj (project) ---

Proj Title=UNT110 IN BACR Base Level Engineering
Current Plan=p01
Default Exp/Contr=0.3,0.1
English Units
Geom File=g01
Flow File=f01
Plan File=p01
BEGIN DESCRIPTION:
UNT110 IN BACR
END DESCRIPTION:

--- UNT110 IN BACR.p01 (plan) ---

Plan Title=Multiple Run
Short Identifier=Multiple
Geom File=g01
Flow File=f01
Subcritical Flow
K Sum by GR= 0
Std Step Tol= 0.01
Critical Tol= 0.01
Num of Std Step Trials= 20
Max Error Tol= 0.3
Flow Tol Ratio= 0.001
Split Flow NTrial= 30
Split Flow Tol= 0.02
Split Flow Ratio= 0.02
Log Output Level= 0
Friction Slope Method= 1
Unsteady Friction Slope Method= 2
Unsteady Bridges Friction Slope Method= 1
Parabolic Critical Depth
Global Vel Dist=  1 , 1 , 1
Global Log Level= 0
CheckData=True
Encroach Param= -1, 0, 0, 0
BEGIN DESCRIPTION:
Multiple Run
END DESCRIPTION:

--- UNT110 IN BACR.f01 (steady flow) ---

Flow Title=Multiple
Number of Profiles=7
Profile Names=10-year,25-year,50-year,1pct_min,100-year,1pct_plu,500-year
River Rch & RM= UNT110 IN BACR,Reach-1,2531
     151     189     216     181     245     331     317
Boundary for River Rch & Prof#=UNT110 IN BACR,Reach-1,1
Up Type=0
Dn Type=3
Dn Slope=0.005
Boundary for River Rch & Prof#=UNT110 IN BACR,Reach-1,2
Up Type=0
Dn Type=3
Dn Slope=0.005
Boundary for River Rch & Prof#=UNT110 IN BACR,Reach-1,3
Up Type=0
Dn Type=3
Dn Slope=0.005
Boundary for River Rch & Prof#=UNT110 IN BACR,Reach-1,4
Up Type=0
Dn Type=3
Dn Slope=0.005
Boundary for River Rch & Prof#=UNT110 IN BACR,Reach-1,5
Up Type=0
Dn Type=3
Dn Slope=0.005
Boundary for River Rch & Prof#=UNT110 IN BACR,Reach-1,6
Up Type=0
Dn Type=3
Dn Slope=0.005
Boundary for River Rch & Prof#=UNT110 IN BACR,Reach-1,7
Up Type=0
Dn Type=3
Dn Slope=0.005

--- UNT110 IN BACR.g01 (geometry) ---

Geom Title=Existing Conditions

River Reach=UNT110 IN BACR,Reach-1
Reach XY= 30
      2381733.62     13179600.02      2381848.20     13179697.42
      2381912.26     13179684.40      2381998.72     13179642.21
      2382033.09     13179645.33      2382138.82     13179721.90
      2382179.45     13179694.81      2382294.03     13179703.67
      2382336.22     13179746.37      2382338.82     13179792.21
      2382427.89     13179872.94      2382404.97     13179929.71
      2382339.34     13180002.10      2382366.95     13180043.77
      2382338.82     13180098.98      2382389.34     13180155.23
      2382479.97     13180189.08      2382675.28     13180394.81
      2382734.14     13180433.35      2382912.26     13180465.12
      2382982.05     13180493.25      2383044.03     13180542.21
      2383279.45     13180546.90      2383339.34     13180570.85
      2383448.20     13180764.08      2383549.24     13180872.94
      2383636.74     13180887.00      2383664.34     13180904.19
      2383685.70     13180953.67      2383686.49     13181003.90

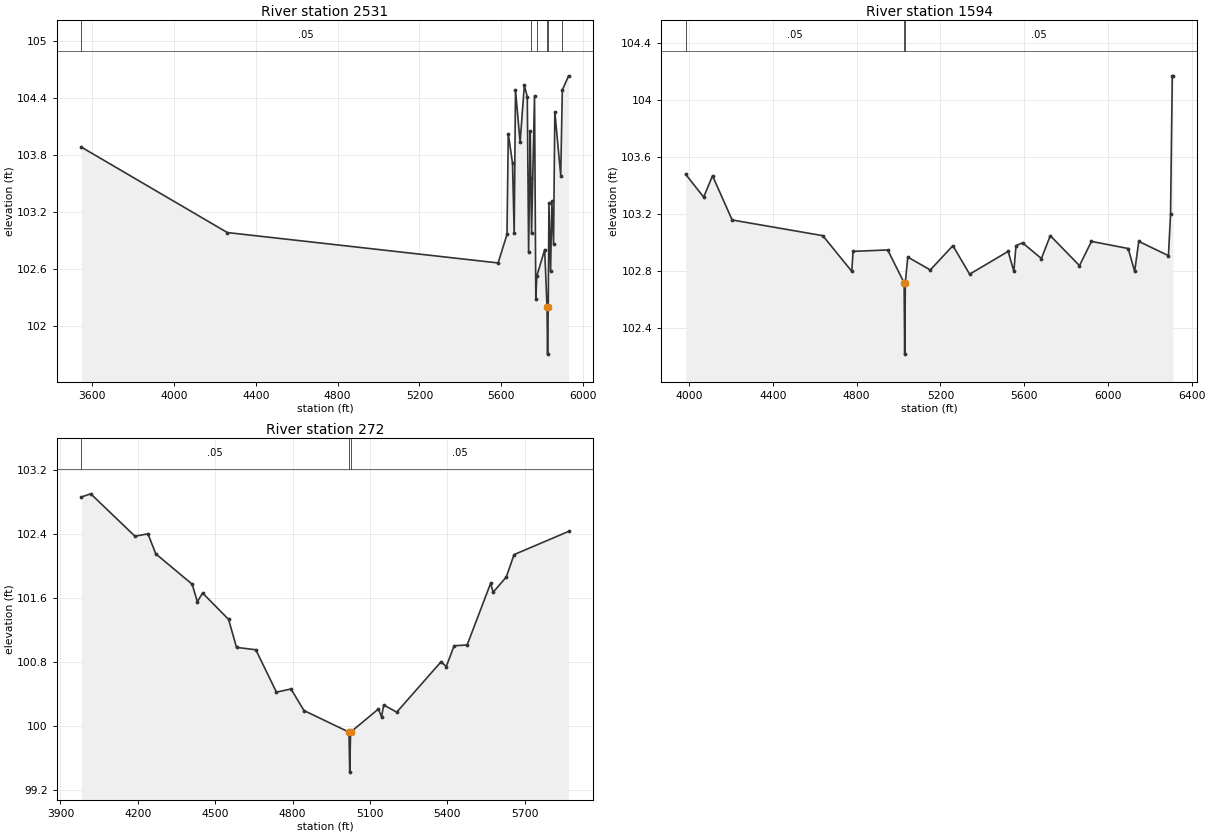
Type RM Length L Ch R = 1,2531,937,937,937
BEGIN DESCRIPTION:
UNT110 IN BACR 2.0
END DESCRIPTION:
XS GIS Cut Line= 3
      2380938.46     13180582.77      2381207.06     13180342.37
      2382793.67     13179088.85
#Sta/Elev= 30
  3546.5  103.88  4260.5  102.98  5584.5  102.66  5627.9  102.96  5634.2  104.02
  5655.0  103.71  5663.1  102.97  5669.5  104.48  5692.0  103.93  5712.8  104.53
  5727.2  104.41  5733.6  102.77  5741.7  104.05  5744.6  103.55  5748.0  102.97
  5762.5  104.42  5768.9  102.28  5773.5  102.52  5812.2  102.80  5823.6  102.20
  5826.4  101.70  5829.6  102.20  5833.0  103.29  5841.0  102.57  5847.4  103.31
  5855.5  102.86  5861.9  104.25  5890.7  103.58  5898.4  104.48  5929.0  104.63
#Mann=6,-1,0
  3546.5    0.05       0  5744.6    0.08       0  5773.5    0.05       0
  5823.6   0.035       0  5829.6    0.05       0  5898.4    0.08       0
Bank Sta=5823.6,5829.6
Exp/Cntr=0.3,0.1

Type RM Length L Ch R = 1,1594,1322,1322,1322
BEGIN DESCRIPTION:
Mapping XS df0f7c34
END DESCRIPTION:
XS GIS Cut Line= 3
      2381632.44     13180750.34      2382826.70     13179962.01
      2382960.73     13179075.47
#Sta/Elev= 30
  3983.1  103.48  4069.2  103.32  4111.3  103.47  4205.1  103.16  4638.1  103.05
  4776.6  102.80  4782.6  102.94  4948.2  102.95  5026.5  102.72  5029.3  102.22
  5032.5  102.72  5043.9  102.90  5151.7  102.81  5259.5  102.98  5339.6  102.78
  5523.4  102.94  5550.8  102.80  5560.9  102.98  5592.2  103.00  5682.3  102.89
  5724.8  103.05  5864.3  102.84  5921.3  103.01  6096.9  102.96  6127.8  102.80
  6147.5  103.01  6289.1  102.91  6299.2  103.20  6307.5  104.17  6310.7  104.17
#Mann=3,-1,0
  3983.1    0.05       0  5026.5   0.035       0  5032.5    0.05       0
Bank Sta=5026.5,5032.5
Exp/Cntr=0.3,0.1

Type RM Length L Ch R = 1,272,0,0,0
BEGIN DESCRIPTION:
UNT110 IN BACR 1.0
END DESCRIPTION:
XS GIS Cut Line= 3
      2382511.33     13180967.37      2383522.16     13180838.56
      2383648.47     13179977.78
#Sta/Elev= 30
  3981.0  102.86  4017.7  102.90  4189.1  102.37  4239.5  102.40  4269.7  102.15
  4410.8  101.77  4431.0  101.55  4451.2  101.66  4552.0  101.33  4582.8  100.98
  4657.7  100.95  4737.5  100.42  4793.9  100.46  4844.3  100.19  5018.9   99.92
  5021.7   99.42  5024.9   99.92  5133.1  100.21  5145.0  100.11  5153.3  100.26
  5203.9  100.17  5375.7  100.80  5395.9  100.74  5426.2  101.00  5476.8  101.01
  5567.7  101.78  5577.8  101.67  5628.6  101.86  5658.7  102.14  5870.0  102.43
#Mann=3,-1,0
  3981.0    0.05       0  5018.9   0.035       0  5024.9    0.05       0
Bank Sta=5018.9,5024.9
Exp/Cntr=0.3,0.1

Chan Stop Cuts=-1