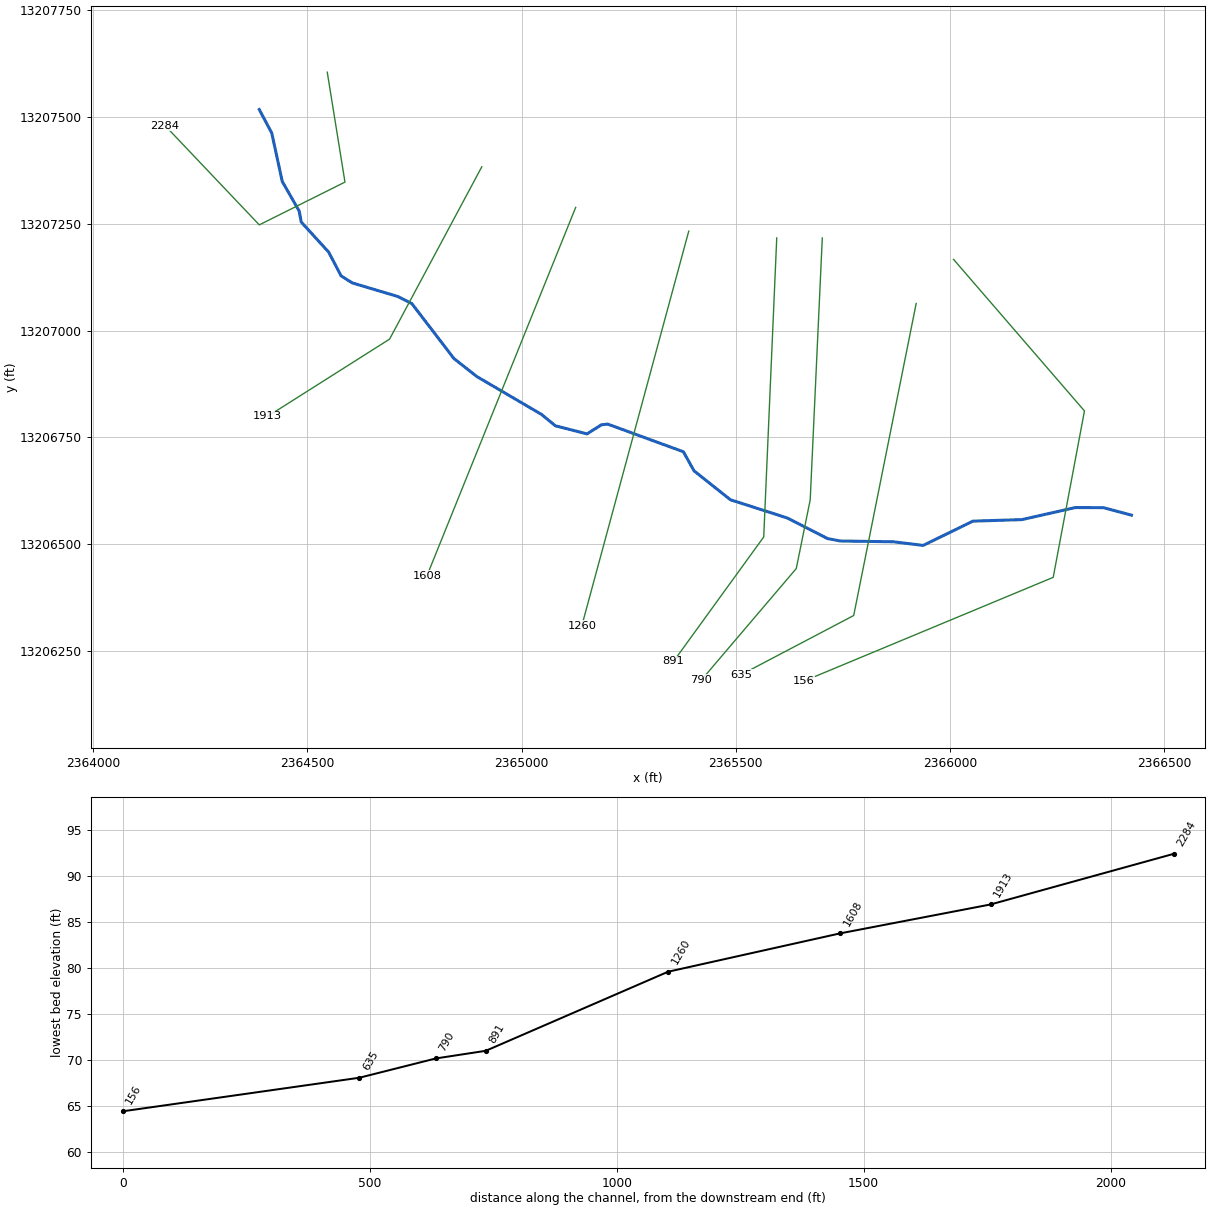
--- UNT111 IN BACR.prj (project) ---

Proj Title=UNT111 IN BACR Base Level Engineering
Current Plan=p01
Default Exp/Contr=0.3,0.1
English Units
Geom File=g01
Flow File=f01
Plan File=p01
Y Axis Title=Elevation
X Axis Title(PF)=Main Channel Distance
X Axis Title(XS)=Station
BEGIN DESCRIPTION:
UNT111 IN BACR
END DESCRIPTION:
DSS Export Rating Curves= 0
DSS Export Rating Curve Sorted= 0
DSS Export Volume Flow Curves= 0
DXF OffsetX= 0
DXF OffsetY= 0
DXF ScaleX= 1
DXF ScaleY= 10

--- UNT111 IN BACR.p01 (plan) ---

Plan Title=Multiple Run
Short Identifier=Multiple
Geom File=g01
Flow File=f01
Subcritical Flow
K Sum by GR= 0
Std Step Tol= 0.01
Critical Tol= 0.01
Num of Std Step Trials= 20
Max Error Tol= 0.3
Flow Tol Ratio= 0.001
Split Flow NTrial= 30
Split Flow Tol= 0.02
Split Flow Ratio= 0.02
Log Output Level= 0
Friction Slope Method= 1
Unsteady Friction Slope Method= 2
Unsteady Bridges Friction Slope Method= 1
Parabolic Critical Depth
Global Vel Dist=  1 , 1 , 1
Global Log Level= 0
CheckData=True
Encroach Param= -1, 0, 0, 0
BEGIN DESCRIPTION:
Multiple Run
END DESCRIPTION:

--- UNT111 IN BACR.f01 (steady flow) ---

Flow Title=Multiple
Number of Profiles=7
Profile Names=10-year,25-year,50-year,1pct_min,100-year,1pct_plu,500-year
River Rch & RM= UNT111 IN BACR,Reach-1,2284
     251     329     389     336     455     615     622
Boundary for River Rch & Prof#=UNT111 IN BACR,Reach-1,1
Up Type=0
Dn Type=3
Dn Slope=0.005
Boundary for River Rch & Prof#=UNT111 IN BACR,Reach-1,2
Up Type=0
Dn Type=3
Dn Slope=0.005
Boundary for River Rch & Prof#=UNT111 IN BACR,Reach-1,3
Up Type=0
Dn Type=3
Dn Slope=0.005
Boundary for River Rch & Prof#=UNT111 IN BACR,Reach-1,4
Up Type=0
Dn Type=3
Dn Slope=0.005
Boundary for River Rch & Prof#=UNT111 IN BACR,Reach-1,5
Up Type=0
Dn Type=3
Dn Slope=0.005
Boundary for River Rch & Prof#=UNT111 IN BACR,Reach-1,6
Up Type=0
Dn Type=3
Dn Slope=0.005
Boundary for River Rch & Prof#=UNT111 IN BACR,Reach-1,7
Up Type=0
Dn Type=3
Dn Slope=0.005

--- UNT111 IN BACR.g01 (geometry) ---

Geom Title=Existing Conditions
Program Version=4.10

River Reach=UNT111 IN BACR  ,Reach-1
Reach XY= 30
      2364387.72     13207516.33       2364416.8     13207461.56
      2364441.32     13207348.32      2364480.78     13207279.38
      2364485.62      13207253.5      2364549.62     13207183.28
      2364578.75     13207127.61      2364604.66     13207111.28
      2364711.19     13207079.46      2364743.96     13207062.72
      2364841.85     13206934.71      2364895.33     13206892.56
      2365046.43     13206803.93      2365078.89     13206777.31
      2365152.59     13206758.43      2365186.28     13206779.65
      2365200.92      13206781.3      2365377.64     13206716.65
      2365402.36     13206672.17      2365487.43     13206604.46
      2365620.36     13206561.81      2365714.15      13206513.8
      2365743.52     13206508.16       2365868.2     13206506.26
      2365937.25     13206497.79      2366053.49     13206554.56
      2366167.59     13206558.08       2366292.3     13206586.24
      2366358.01     13206586.05      2366423.51     13206568.47

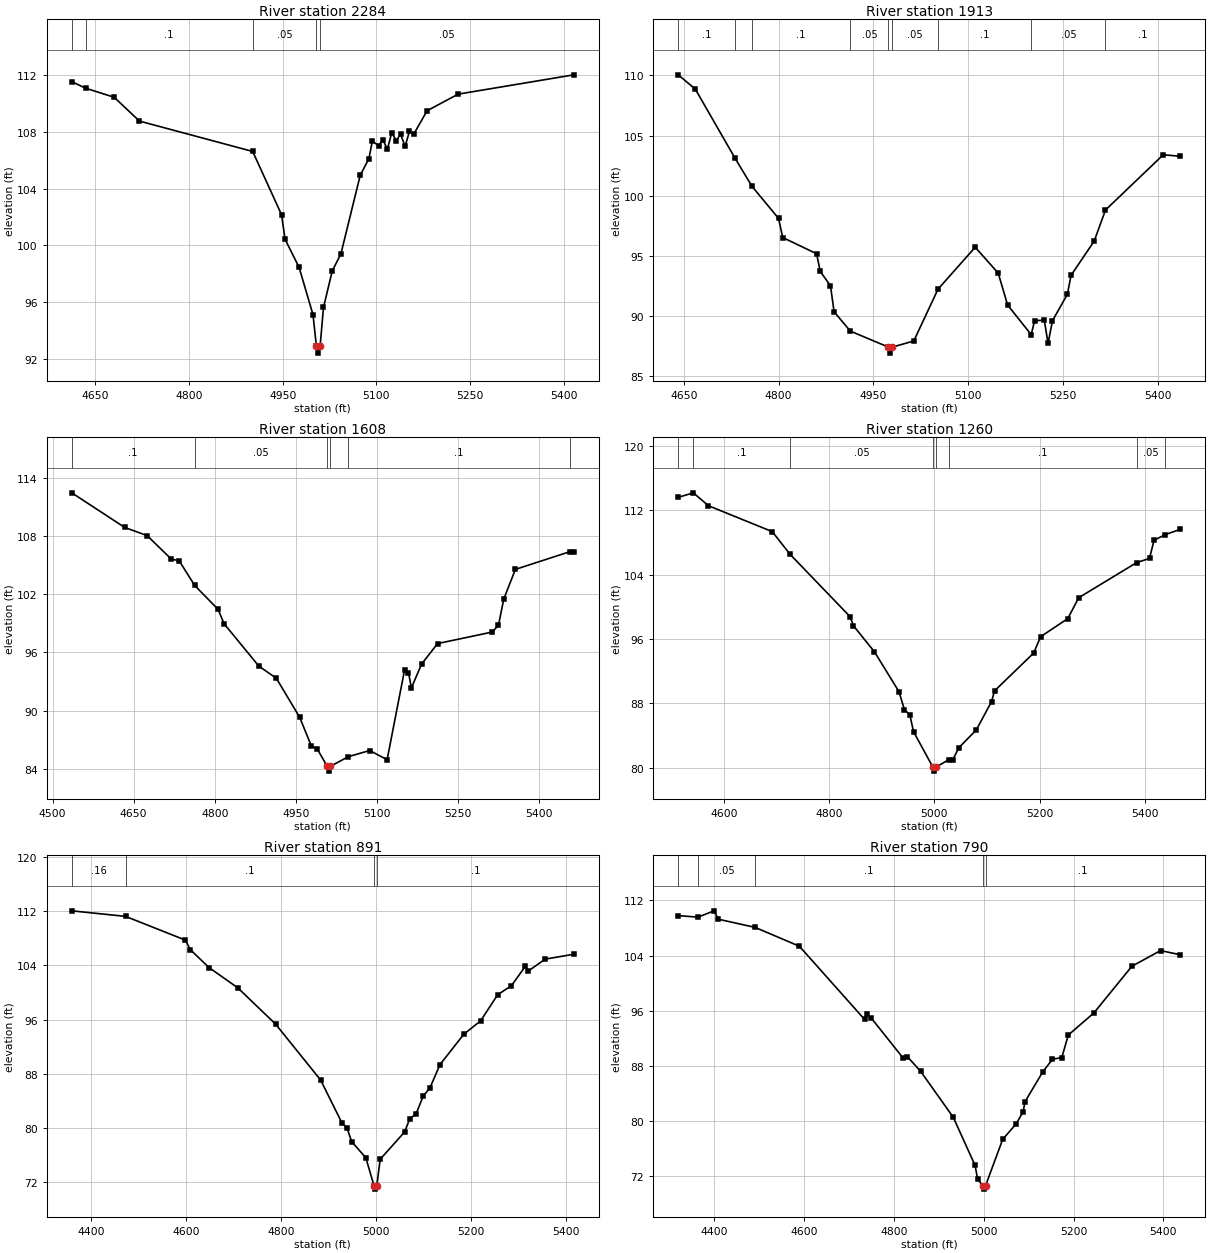
Type RM Length L Ch R = 1 ,2284    ,371,371,371
BEGIN DESCRIPTION:
UNT111 IN BACR 5.0
END DESCRIPTION:
XS GIS Cut Line= 4
      2364546.36     13207603.79      2364587.72     13207346.85
      2364387.72     13207246.85      2364167.87     13207478.77
#Sta/Elev= 30
  4612.5  111.53  4634.5  111.07  4680.3  110.43  4720.8  108.75    4902  106.61
  4948.2  102.15  4953.8  100.42  4976.2   98.45  4998.5   95.11  5003.9    92.9
  5006.7    92.4  5009.9    92.9  5015.3   95.62  5029.3   98.19  5043.2    99.4
    5074  104.92    5088  106.11  5093.5  107.36  5103.4     107  5110.3  107.42
  5117.6  106.78  5124.5  107.93  5131.7  107.37  5138.6  107.83  5145.9  106.97
  5152.8  108.02  5160.1  107.86  5181.1  109.48  5230.8  110.65  5415.9  112.01
#Mann= 5 ,-1 , 0
  4612.5     .05       0  4634.5      .1       0    4902     .05       0
  5003.9     .03       0  5009.9     .05       0
Bank Sta=5003.9,5009.9
XS Rating Curve= 0 ,0
Exp/Cntr=0.3,0.1

Type RM Length L Ch R = 1 ,1913    ,305,305,305
BEGIN DESCRIPTION:
Mapping XS 394f7b39
END DESCRIPTION:
XS GIS Cut Line= 3
      2364907.06     13207382.58       2364691.8     13206979.84
      2364407.08     13206799.28
#Sta/Elev= 30
  4641.3  110.05  4668.3  108.86    4731  103.12  4757.8  100.78  4799.9    98.1
  4806.5   96.51  4860.1   95.16  4865.8   93.69    4882    92.5  4887.7   90.33
  4913.5   88.72  4973.6   87.39  4976.4   86.89  4979.6   87.39  5013.7    87.9
  5052.1   92.22  5110.8    95.7  5147.2   93.55    5162    90.9  5199.3   88.43
  5204.8    89.6  5220.1   89.62    5226    87.7    5233   89.59  5256.5   91.78
  5262.4   93.37  5298.9   96.21  5316.8    98.8  5408.2   103.4  5435.1  103.27
#Mann= 9 ,-1 , 0
  4641.3      .1       0    4731     .05       0  4757.8      .1       0
  4913.5     .05       0  4973.6     .03       0  4979.6     .05       0
  5052.1      .1       0  5199.3     .05       0  5316.8      .1       0
Bank Sta=4973.6,4979.6
XS Rating Curve= 0 ,0
Exp/Cntr=0.3,0.1

Type RM Length L Ch R = 1 ,1608    ,348,348,348
BEGIN DESCRIPTION:
UNT111 IN BACR 4.0
END DESCRIPTION:
XS GIS Cut Line= 2
      2365126.22     13207287.75      2364778.99     13206426.62
#Sta/Elev= 30
  4535.6   112.5  4633.6  108.92    4675  108.08  4719.9  105.64  4734.1  105.49
  4762.9  102.93  4806.1  100.46  4817.3   98.97  4881.6   94.59  4913.9   93.34
  4957.1    89.3  4978.6   86.34  4989.4   86.04    5008   84.24  5010.7   83.74
    5014   84.24  5046.9   85.23  5086.5   85.87  5118.8   84.92  5151.2   94.24
  5158.3   93.93  5163.7   92.34  5182.4   94.79    5212   96.92  5312.9   98.11
  5324.7   98.81  5334.5  101.52    5356  104.59  5456.9  106.42  5464.1  106.39
#Mann= 6 ,-1 , 0
  4535.6      .1       0  4762.9     .05       0    5008     .03       0
    5014     .05       0  5046.9      .1       0  5456.9     .05       0
Bank Sta=5008,5014
XS Rating Curve= 0 ,0
Exp/Cntr=0.3,0.1

Type RM Length L Ch R = 1 ,1260    ,369,369,369
BEGIN DESCRIPTION:
UNT111 IN BACR 3.0
END DESCRIPTION:
XS GIS Cut Line= 2
      2365390.11     13207232.19      2365140.57     13206310.26
#Sta/Elev= 30
  4512.7  113.63  4541.5  114.19    4570  112.59  4691.6  109.36  4725.6  106.53
  4839.4    98.8  4845.9   97.66  4885.7   94.44  4932.6   89.46    4943   87.21
  4953.3   86.57  4960.3   84.48  4997.1   80.07  4999.9   79.57  5003.1   80.07
  5027.5      81  5034.8   80.97  5046.6   82.49  5079.8    84.7  5108.7   88.22
  5114.5   89.56    5189   94.27    5202   96.29  5253.8   98.55  5274.5  101.14
  5384.7  105.51  5409.2  106.03  5417.8  108.29  5439.4     109  5467.8  109.65
#Mann= 8 ,-1 , 0
  4512.7     .16       0  4541.5      .1       0  4725.6     .05       0
  4997.1     .03       0  5003.1     .05       0  5027.5      .1       0
  5384.7     .05       0  5439.4      .1       0
Bank Sta=4997.1,5003.1
XS Rating Curve= 0 ,0
Exp/Cntr=0.3,0.1

Type RM Length L Ch R = 1 ,891     ,101,101,101
BEGIN DESCRIPTION:
Mapping XS d06635f1
END DESCRIPTION:
XS GIS Cut Line= 3
       2365595.5     13207216.32      2365565.12     13206517.54
      2365354.63     13206226.77
#Sta/Elev= 30
  4358.8  112.07  4472.2  111.25  4598.5  107.74  4608.5  106.35  4648.3  103.68
  4708.6  100.71  4788.7   95.32  4883.5   87.07  4928.8   80.68  4938.8   80.04
  4948.8   77.99  4978.8   75.59  4995.9   71.47  4998.6   70.97  5001.9   71.47
  5008.9   75.38  5060.3    79.4  5071.4   81.37  5084.7   82.09  5099.4   84.68
  5114.1   85.96  5134.9   89.35  5185.2   93.84  5220.8   95.83  5256.6   99.68
  5285.7  101.02  5315.1  103.89  5321.3  103.19  5356.9  104.94  5417.2  105.66
#Mann= 4 ,-1 , 0
  4358.8     .16       0  4472.2      .1       0  4995.9     .07       0
  5001.9      .1       0
Bank Sta=4995.9,5001.9
XS Rating Curve= 0 ,0
Exp/Cntr=0.3,0.1

Type RM Length L Ch R = 1 ,790     ,155,155,155
BEGIN DESCRIPTION:
Mapping XS 12c23d15
END DESCRIPTION:
XS GIS Cut Line= 4
      2365701.84     13207216.33      2365673.62     13206604.35
      2365641.07     13206443.76       2365419.7     13206183.32
#Sta/Elev= 30
  4319.6  109.79  4363.6  109.56  4399.2  110.48  4409.2  109.26  4490.7  108.08
  4589.4  105.35  4734.6   94.74  4739.6   95.48  4749.5   94.94  4819.6   89.21
  4829.6   89.36  4859.6   87.21  4932.2   80.55  4980.7   73.59  4986.5   71.59
  4998.1   70.64  5000.8   70.14  5004.1   70.64  5042.2   77.34  5072.5   79.63
  5087.8   81.36    5092   82.82  5131.4   87.12  5153.2   88.97    5174   89.21
  5188.3   92.47  5245.4   95.68    5330  102.44  5393.9  104.72  5437.9  104.11
#Mann= 5 ,-1 , 0
  4319.6     .16       0  4363.6     .05       0  4490.7      .1       0
  4998.1     .07       0  5004.1      .1       0
Bank Sta=4998.1,5004.1
XS Rating Curve= 0 ,0
Exp/Cntr=0.3,0.1

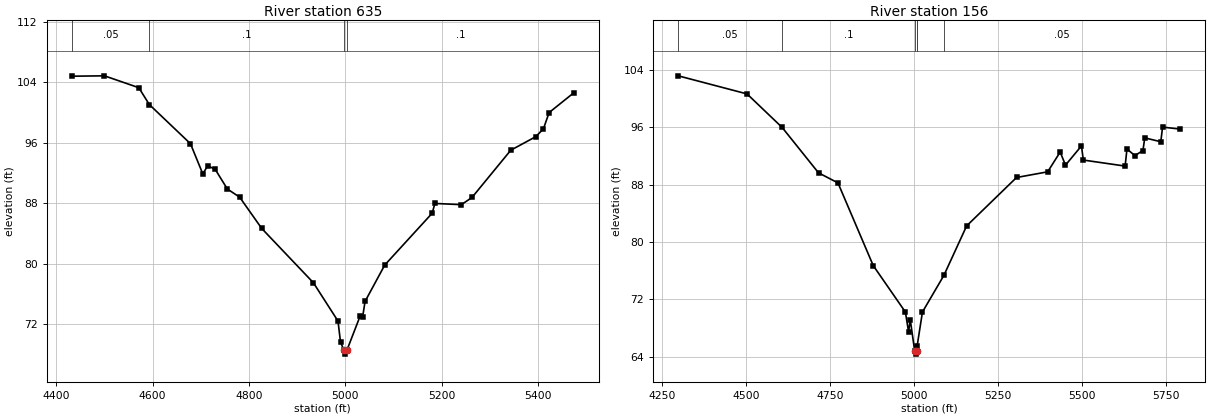
Type RM Length L Ch R = 1 ,635     ,479,479,479
BEGIN DESCRIPTION:
Mapping XS 3024ce63
END DESCRIPTION:
XS GIS Cut Line= 3
      2365920.97     13207063.19      2365775.13       13206334.
      2365511.98      13206195.5
#Sta/Elev= 30
  4432.6   104.8  4500.3  104.85  4571.6  103.28  4593.4  101.05  4678.7   95.87
  4704.2   91.89  4714.4   92.93  4729.7   92.51  4755.2   89.88  4780.7    88.8
  4826.5   84.66  4933.6   77.48  4984.6   72.41  4989.8   69.64    4997   68.54
  4999.7   68.04    5003   68.54  5030.5   73.08  5035.6   72.93  5040.7   75.01
  5081.5   79.82  5179.9   86.68  5185.5   87.97  5240.4   87.81  5262.4   88.76
  5342.8   95.01  5394.6    96.8  5410.6   97.85  5422.3   99.99  5473.6  102.61
#Mann= 4 ,-1 , 0
  4432.6     .05       0  4593.4      .1       0    4997     .07       0
    5003      .1       0
Bank Sta=4997,5003
XS Rating Curve= 0 ,0
Exp/Cntr=0.3,0.1

Type RM Length L Ch R = 1 ,156     ,0,0,0
BEGIN DESCRIPTION:
UNT111 IN BACR 1.0
END DESCRIPTION:
XS GIS Cut Line= 4
      2366008.17     13207166.25      2366313.73     13206812.08
      2366240.81     13206423.19      2365657.46     13206180.12
#Sta/Elev= 30
  4297.5  103.15  4502.4  100.63    4607   95.96  4715.3   89.64  4773.2   88.24
  4878.3   76.72  4974.1   70.25  4983.5   67.52  4988.6   69.17  5001.6   64.89
  5004.3   64.39  5007.6   64.89  5009.1   65.54  5024.9   70.26  5088.9   75.37
  5156.5   82.25  5305.1   88.99  5397.8   89.78  5435.1   92.54  5450.9   90.71
  5498.5   93.39    5504   91.42  5628.5   90.58    5634   92.95  5657.8   92.04
  5681.6   92.75    5687   94.51  5734.7   93.97  5740.1   96.01  5792.9   95.73
#Mann= 6 ,-1 , 0
  4297.5     .05       0    4607      .1       0  5001.6     .07       0
  5007.6      .1       0  5009.1     .12       0  5088.9     .05       0
Bank Sta=5001.6,5007.6
XS Rating Curve= 0 ,0
Exp/Cntr=0.3,0.1

Chan Stop Cuts=-1
Use User Specified Reach Order=0
Composite Channel Slope=5