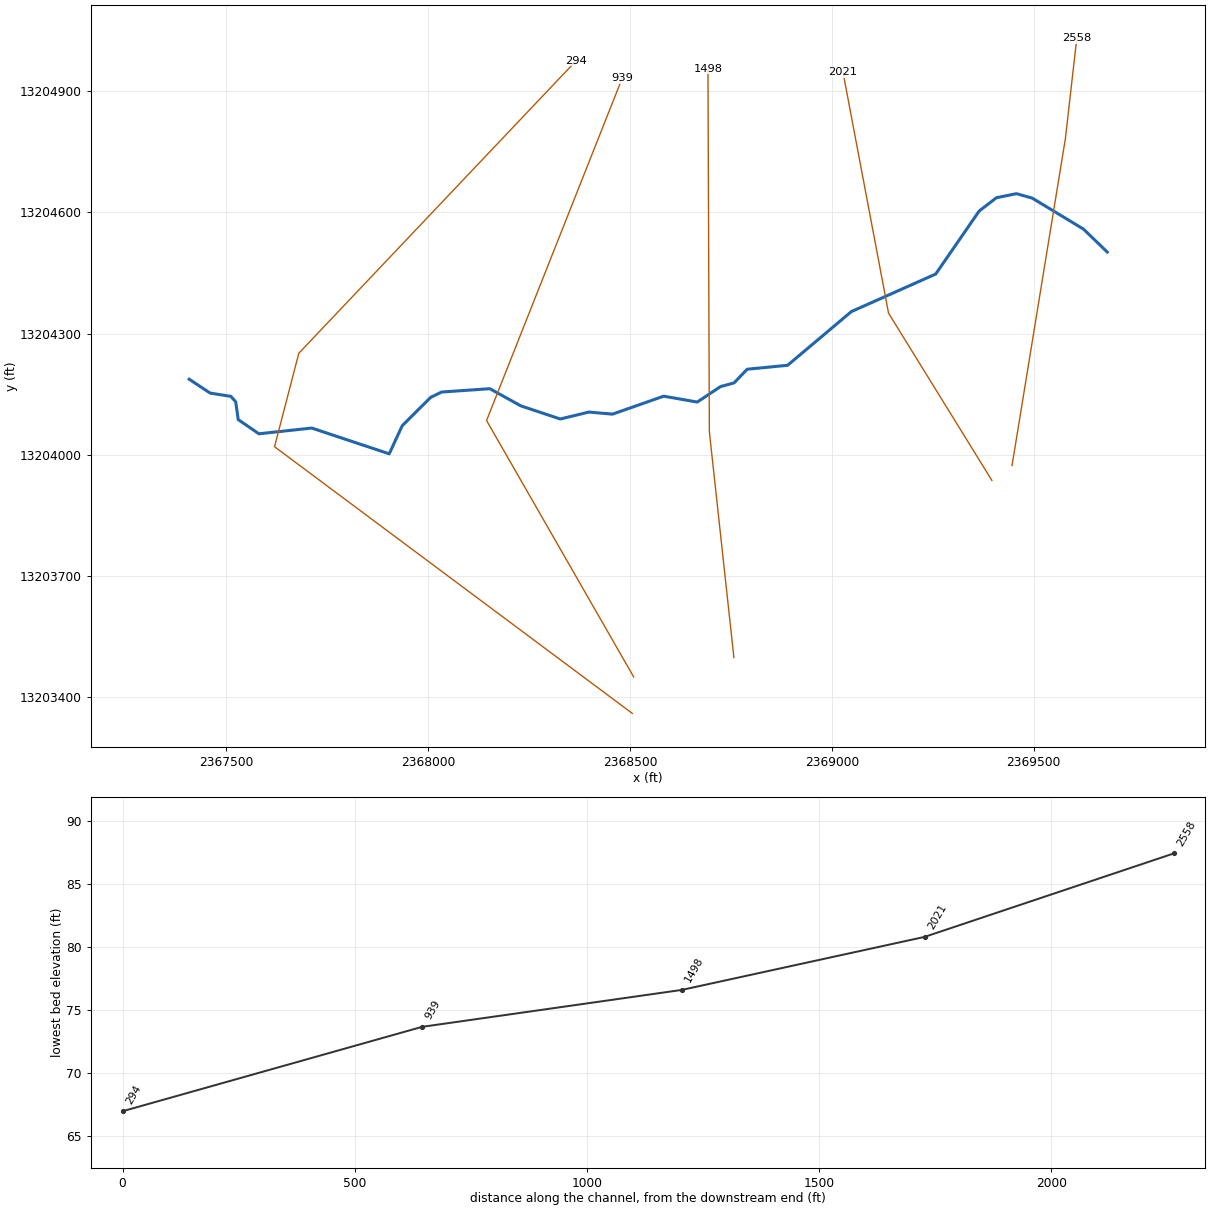
--- UNT112 IN BACR.prj (project) ---

Proj Title=UNT112 IN BACR Base Level Engineering
Current Plan=p01
Default Exp/Contr=0.3,0.1
English Units
Geom File=g01
Flow File=f01
Plan File=p01
BEGIN DESCRIPTION:
UNT112 IN BACR
END DESCRIPTION:

--- UNT112 IN BACR.p01 (plan) ---

Plan Title=Multiple Run
Short Identifier=Multiple
Geom File=g01
Flow File=f01
Subcritical Flow
K Sum by GR= 0
Std Step Tol= 0.01
Critical Tol= 0.01
Num of Std Step Trials= 20
Max Error Tol= 0.3
Flow Tol Ratio= 0.001
Split Flow NTrial= 30
Split Flow Tol= 0.02
Split Flow Ratio= 0.02
Log Output Level= 0
Friction Slope Method= 1
Unsteady Friction Slope Method= 2
Unsteady Bridges Friction Slope Method= 1
Parabolic Critical Depth
Global Vel Dist=  1 , 1 , 1
Global Log Level= 0
CheckData=True
Encroach Param= -1, 0, 0, 0
BEGIN DESCRIPTION:
Multiple Run
END DESCRIPTION:

--- UNT112 IN BACR.f01 (steady flow) ---

Flow Title=Multiple
Number of Profiles=7
Profile Names=10-year,25-year,50-year,1pct_min,100-year,1pct_plu,500-year
River Rch & RM= UNT112 IN BACR,Reach-1,2558
     265     349     414     360     487     659     674
Boundary for River Rch & Prof#=UNT112 IN BACR,Reach-1,1
Up Type=0
Dn Type=3
Dn Slope=0.005
Boundary for River Rch & Prof#=UNT112 IN BACR,Reach-1,2
Up Type=0
Dn Type=3
Dn Slope=0.005
Boundary for River Rch & Prof#=UNT112 IN BACR,Reach-1,3
Up Type=0
Dn Type=3
Dn Slope=0.005
Boundary for River Rch & Prof#=UNT112 IN BACR,Reach-1,4
Up Type=0
Dn Type=3
Dn Slope=0.005
Boundary for River Rch & Prof#=UNT112 IN BACR,Reach-1,5
Up Type=0
Dn Type=3
Dn Slope=0.005
Boundary for River Rch & Prof#=UNT112 IN BACR,Reach-1,6
Up Type=0
Dn Type=3
Dn Slope=0.005
Boundary for River Rch & Prof#=UNT112 IN BACR,Reach-1,7
Up Type=0
Dn Type=3
Dn Slope=0.005

--- UNT112 IN BACR.g01 (geometry) ---

Geom Title=Existing Conditions

River Reach=UNT112 IN BACR,Reach-1
Reach XY= 30
      2369682.72     13204501.85      2369623.82     13204558.74
      2369496.99     13204635.44      2369457.72     13204646.61
      2369407.92     13204636.45      2369365.23     13204603.50
      2369257.56     13204447.39      2369048.69     13204354.45
      2368890.54     13204221.28      2368790.52     13204211.59
      2368757.84     13204177.61      2368724.76     13204168.71
      2368666.65     13204130.21      2368583.53     13204144.75
      2368456.67     13204100.28      2368398.22     13204105.40
      2368327.23     13204088.20      2368229.42     13204120.84
      2368152.73     13204163.27      2368033.45     13204155.05
      2368006.09     13204141.79      2367935.62     13204071.61
      2367903.38     13204001.90      2367711.44     13204065.81
      2367580.56     13204051.56      2367529.21     13204086.70
      2367523.06     13204130.59      2367511.08     13204144.27
      2367459.64     13204152.39      2367407.72     13204186.85

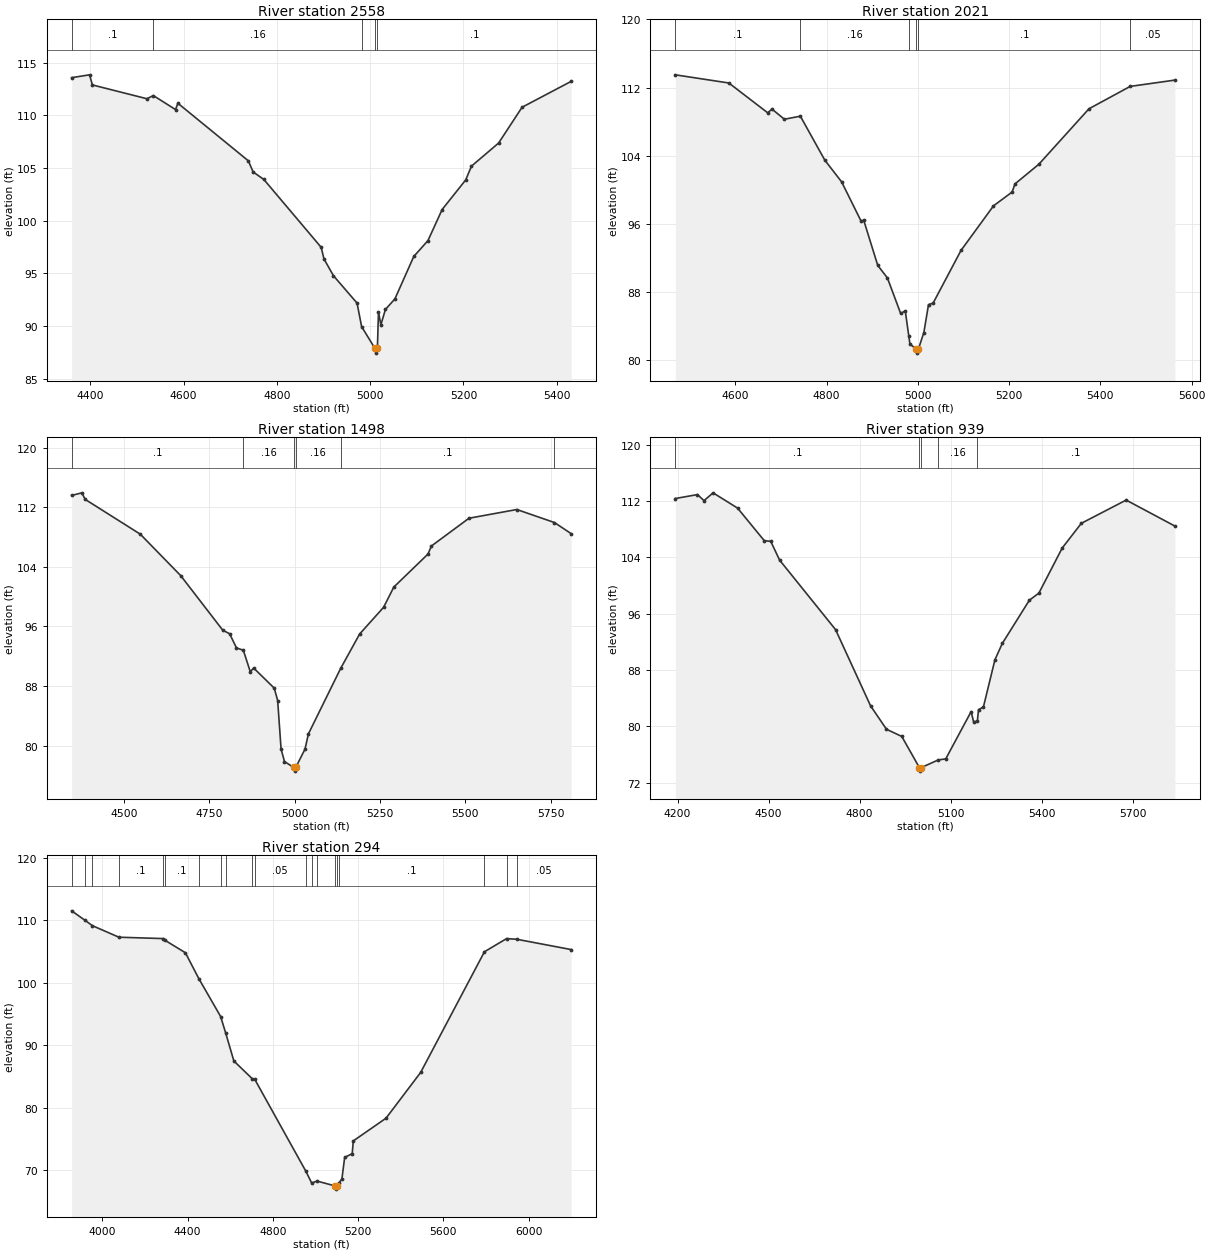
Type RM Length L Ch R = 1,2558,537,537,537
BEGIN DESCRIPTION:
UNT112 IN BACR 8.0
END DESCRIPTION:
XS GIS Cut Line= 3
      2369446.71     13203972.91      2369578.90     13204782.86
      2369607.16     13205031.49
#Sta/Elev= 30
  4360.1  113.57  4398.5  113.84  4404.6  112.88  4521.4  111.57  4535.3  111.87
  4582.8  110.54  4587.9  111.14  4739.0  105.67  4749.1  104.62  4772.2  103.90
  4895.0   97.46  4901.1   96.35  4921.4   94.76  4972.0   92.16  4981.7   89.93
  5009.6   87.91  5012.3   87.41  5015.6   87.91  5017.9   91.32  5023.0   90.10
  5032.8   91.56  5053.1   92.56  5093.6   96.59  5124.0   98.10  5154.4  101.05
  5204.9  103.86  5217.3  105.17  5275.4  107.36  5325.7  110.76  5431.0  113.22
#Mann=5,-1,0
  4360.1     0.1       0  4535.3    0.16       0  4981.7     0.1       0
  5009.6    0.07       0  5015.6     0.1       0
Bank Sta=5009.6,5015.6
Exp/Cntr=0.3,0.1

Type RM Length L Ch R = 1,2021,523,523,523
BEGIN DESCRIPTION:
UNT112 IN BACR 4.0
END DESCRIPTION:
XS GIS Cut Line= 3
      2369396.79     13203936.00      2369140.72     13204350.48
      2369027.86     13204947.30
#Sta/Elev= 30
  4468.6  113.49  4585.9  112.53  4671.0  109.03  4680.5  109.46  4707.6  108.27
  4742.6  108.63  4796.3  103.45  4833.0  100.91  4875.5   96.31  4881.4   96.40
  4912.2   91.09  4933.4   89.61  4962.3   85.45  4972.5   85.74  4980.1   82.83
  4982.6   81.87  4995.4   81.28  4998.1   80.78  5001.4   81.28  5013.2   83.20
  5023.4   86.48  5033.5   86.66  5094.6   92.85  5165.8   98.09  5206.5   99.71
  5212.9  100.67  5265.2  102.98  5375.0  109.50  5465.3  112.13  5563.2  112.87
#Mann=6,-1,0
  4468.6     0.1       0  4742.6    0.16       0  4980.1     0.1       0
  4995.4    0.07       0  5001.4     0.1       0  5465.3    0.05       0
Bank Sta=4995.4,5001.4
Exp/Cntr=0.3,0.1

Type RM Length L Ch R = 1,1498,559,559,559
BEGIN DESCRIPTION:
UNT112 IN BACR 3.0
END DESCRIPTION:
XS GIS Cut Line= 3
      2368757.51     13203497.14      2368696.71     13204056.65
      2368693.23     13204955.93
#Sta/Elev= 30
  4347.5  113.58  4377.4  113.93  4387.1  113.05  4548.4  108.38  4666.8  102.81
  4789.8   95.49  4809.9   95.01  4830.0   93.11  4850.0   92.80  4870.3   89.92
  4880.3   90.41  4940.5   87.71  4950.5   86.05  4960.5   79.53  4970.5   77.85
  4997.5   77.07  5000.3   76.57  5003.5   77.07  5030.5   79.52  5040.5   81.57
  5135.1   90.38  5190.5   94.98  5260.5   98.56  5290.5  101.28  5390.5  105.71
  5400.5  106.79  5510.5  110.52  5650.5  111.69  5760.7  109.94  5809.6  108.45
#Mann=6,-1,0
  4347.5     0.1       0  4850.0    0.16       0  4997.5    0.07       0
  5003.5    0.16       0  5135.1     0.1       0  5760.7    0.05       0
Bank Sta=4997.5,5003.5
Exp/Cntr=0.3,0.1

Type RM Length L Ch R = 1,939,645,645,645
BEGIN DESCRIPTION:
UNT112 IN BACR 2.0
END DESCRIPTION:
XS GIS Cut Line= 3
      2368509.22     13203448.99      2368144.62     13204084.42
      2368480.91     13204933.23
#Sta/Elev= 30
  4192.7  112.38  4265.6  112.94  4287.2  112.08  4317.1  113.19  4397.8  111.02
  4485.6  106.40  4507.2  106.29  4536.1  103.64  4720.6   93.75  4835.9   82.92
  4888.3   79.59  4938.7   78.57  4996.7   74.14  4999.5   73.64  5002.7   74.14
  5058.9   75.23  5083.5   75.38  5167.2   82.10  5175.3   80.65  5187.7   80.73
  5191.5   82.38  5207.6   82.75  5245.6   89.47  5269.9   91.79  5359.0   97.93
  5390.4   98.94  5467.1  105.34  5530.3  108.86  5677.9  112.16  5838.3  108.47
#Mann=5,-1,0
  4192.7     0.1       0  4996.7    0.07       0  5002.7     0.1       0
  5058.9    0.16       0  5187.7     0.1       0
Bank Sta=4996.7,5002.7
Exp/Cntr=0.3,0.1

Type RM Length L Ch R = 1,294,0,0,0
BEGIN DESCRIPTION:
UNT112 IN BACR 1.0
END DESCRIPTION:
XS GIS Cut Line= 4
      2368505.70     13203358.76      2367619.23     13204019.54
      2367679.35     13204251.09      2368366.88     13204976.31
#Sta/Elev= 30
  3855.5  111.55  3918.3  110.03  3952.9  109.17  4077.4  107.32  4286.1  107.10
  4291.6  106.87  4389.3  104.83  4453.3  100.62  4554.7   94.61  4578.4   91.96
  4616.8   87.48  4703.6   84.62  4713.8   84.60  4953.8   69.86  4981.8   67.93
  5007.0   68.23  5093.1   67.44  5095.9   66.94  5099.1   67.44  5109.9   67.96
  5123.7   68.55  5136.7   72.02  5172.1   72.63  5177.3   74.67  5330.8   78.31
  5493.4   85.65  5792.7  104.99  5896.6  107.10  5944.7  106.99  6199.7  105.34
#Mann=20,-1,0
  3855.5    0.05       0  3918.3     0.1       0  3952.9    0.05       0
  4077.4     0.1       0  4286.1    0.08       0  4291.6     0.1       0
  4453.3    0.05       0  4554.7     0.1       0  4578.4    0.05       0
  4703.6    0.08       0  4713.8    0.05       0  4953.8    0.08       0
  4981.8    0.05       0  5007.0    0.12       0  5093.1    0.04       0
  5099.1    0.12       0  5109.9     0.1       0  5792.7    0.05       0
  5896.6     0.1       0  5944.7    0.05       0
Bank Sta=5093.1,5099.1
Exp/Cntr=0.3,0.1

Chan Stop Cuts=-1