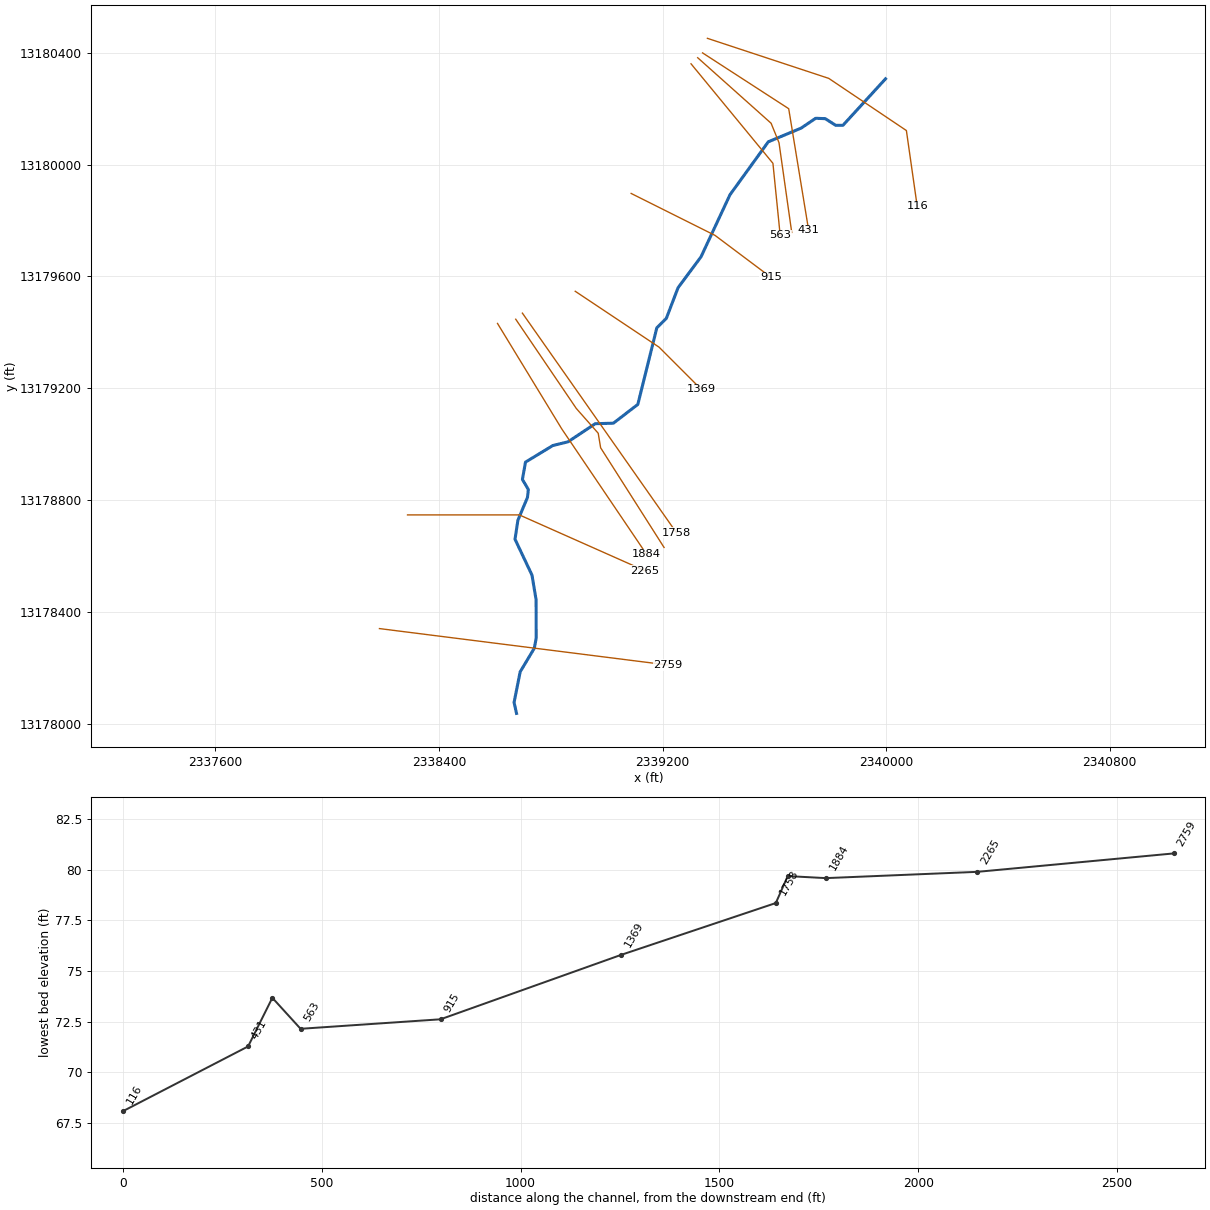
--- UNT316 IN BACR.prj (project) ---

Proj Title=UNT316 IN BACR Base Level Engineering
Current Plan=p01
Default Exp/Contr=0.3,0.1
English Units
Geom File=g01
Flow File=f01
Plan File=p01
Y Axis Title=Elevation
X Axis Title(PF)=Main Channel Distance
X Axis Title(XS)=Station
BEGIN DESCRIPTION:
UNT316 IN BACR
END DESCRIPTION:
DSS Export Rating Curves= 0
DSS Export Rating Curve Sorted= 0
DSS Export Volume Flow Curves= 0
DXF OffsetX= 0
DXF OffsetY= 0
DXF ScaleX= 1
DXF ScaleY= 10

--- UNT316 IN BACR.p01 (plan) ---

Plan Title=Multiple Run
Short Identifier=Multiple
Geom File=g01
Flow File=f01
Subcritical Flow
K Sum by GR= 0
Std Step Tol= 0.01
Critical Tol= 0.01
Num of Std Step Trials= 20
Max Error Tol= 0.3
Flow Tol Ratio= 0.001
Split Flow NTrial= 30
Split Flow Tol= 0.02
Split Flow Ratio= 0.02
Log Output Level= 0
Friction Slope Method= 1
Unsteady Friction Slope Method= 2
Unsteady Bridges Friction Slope Method= 1
Parabolic Critical Depth
Global Vel Dist=  1 , 1 , 1
Global Log Level= 0
CheckData=True
Encroach Param= -1, 0, 0, 0
BEGIN DESCRIPTION:
Multiple Run
END DESCRIPTION:

--- UNT316 IN BACR.f01 (steady flow) ---

Flow Title=Multiple
Number of Profiles=7
Profile Names=10-year,25-year,50-year,1pct_min,100-year,1pct_plu,500-year
River Rch & RM= UNT316 IN BACR,Reach-1,2759
     161     208     245     211     285     385     389
Boundary for River Rch & Prof#=UNT316 IN BACR,Reach-1,1
Up Type=0
Dn Type=3
Dn Slope=0.005
Boundary for River Rch & Prof#=UNT316 IN BACR,Reach-1,2
Up Type=0
Dn Type=3
Dn Slope=0.005
Boundary for River Rch & Prof#=UNT316 IN BACR,Reach-1,3
Up Type=0
Dn Type=3
Dn Slope=0.005
Boundary for River Rch & Prof#=UNT316 IN BACR,Reach-1,4
Up Type=0
Dn Type=3
Dn Slope=0.005
Boundary for River Rch & Prof#=UNT316 IN BACR,Reach-1,5
Up Type=0
Dn Type=3
Dn Slope=0.005
Boundary for River Rch & Prof#=UNT316 IN BACR,Reach-1,6
Up Type=0
Dn Type=3
Dn Slope=0.005
Boundary for River Rch & Prof#=UNT316 IN BACR,Reach-1,7
Up Type=0
Dn Type=3
Dn Slope=0.005

--- UNT316 IN BACR.g01 (geometry) ---

Geom Title=Existing Conditions
Program Version=4.10

River Reach=UNT316 IN BACR  ,Reach-1
Reach XY= 30
      2338677.72     13178036.86      2338668.93     13178075.88
       2338690.8     13178185.58      2338741.41     13178270.04
      2338748.01     13178306.21      2338747.77     13178442.67
      2338732.99     13178531.56      2338672.34      13178659.8
      2338682.52     13178727.39      2338716.78     13178809.33
      2338720.02     13178837.57      2338698.73     13178873.69
      2338709.84     13178935.72      2338807.52     13178994.98
      2338862.15     13179008.41      2338959.34     13179073.15
      2339024.27     13179074.92      2339111.69      13179142.2
      2339179.62     13179416.24      2339213.72     13179450.26
      2339255.67      13179559.8      2339337.62     13179669.98
      2339441.32      13179892.2      2339578.36     13180081.56
      2339695.85     13180130.55      2339747.77     13180165.68
      2339781.96     13180164.41       2339819.6     13180140.56
      2339845.47     13180140.58      2339997.72     13180306.86

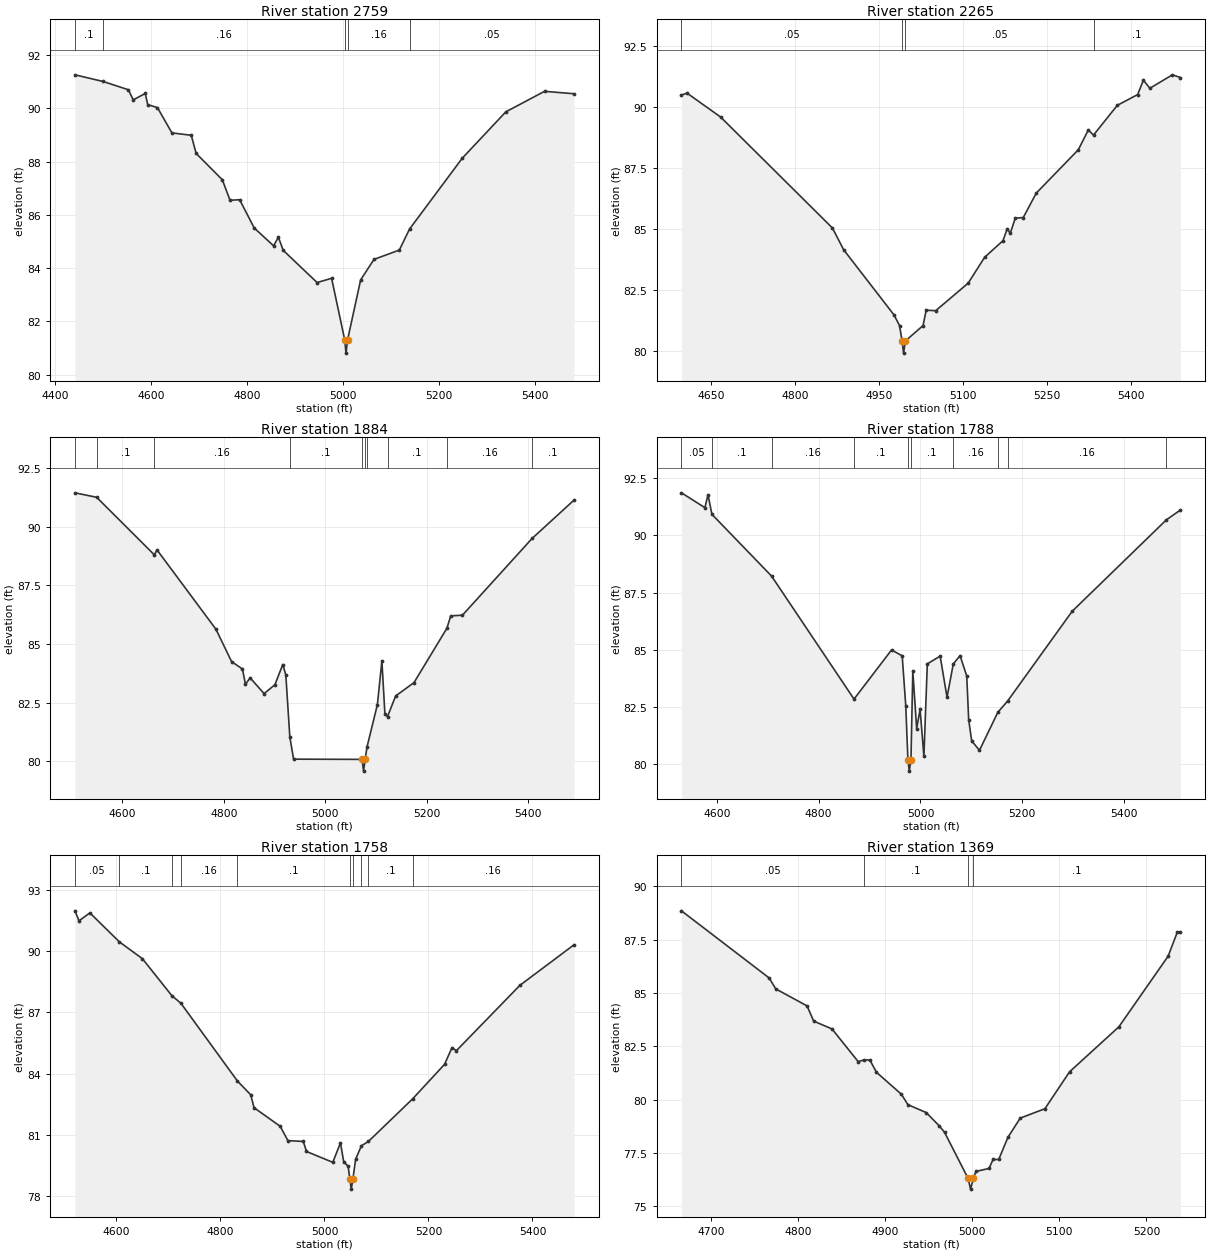
Type RM Length L Ch R = 1 ,2759    ,494,494,494
BEGIN DESCRIPTION:
UNT316 IN BACR 6.0
END DESCRIPTION:
XS GIS Cut Line= 2
       2338187.4     13178340.19      2339218.61     13178209.98
#Sta/Elev= 30
  4441.5   91.26    4500   91.01  4552.7    90.7  4562.8   90.32  4587.9   90.56
    4593   90.14  4613.2   90.03  4643.4   89.08  4683.7   88.99  4693.8   88.31
  4748.4   87.32  4764.4   86.55  4784.5   86.57  4814.8   85.51  4855.1   84.84
  4865.2   85.16  4875.2   84.67  4945.8   83.46    4976   83.62  5003.3   81.31
    5006   80.81  5009.3   81.31  5036.5   83.56  5064.3   84.33  5117.1   84.68
  5138.4   85.47  5248.2   88.13  5338.9   89.87  5419.5   90.64  5480.9   90.55
#Mann= 5 ,-1 , 0
  4441.5      .1       0    4500     .16       0  5003.3     .07       0
  5009.3     .16       0  5138.4     .05       0
Bank Sta=5003.3,5009.3
XS Rating Curve= 0 ,0
Exp/Cntr=0.3,0.1

Type RM Length L Ch R = 1 ,2265    ,381,381,381
BEGIN DESCRIPTION:
UNT316 IN BACR 5.0
END DESCRIPTION:
XS GIS Cut Line= 3
      2338287.77     13178746.85      2338687.72     13178746.85
      2339137.72     13178546.85
#Sta/Elev= 30
  4596.4   90.48  4606.4   90.56  4666.4   89.58  4866.4   85.03  4886.4   84.14
  4976.4   81.47  4986.4   81.03  4990.9    80.4  4993.6    79.9  4996.9    80.4
  5028.5   81.03    5034   81.66  5051.1   81.64  5109.2   82.77  5138.6   83.83
  5171.4   84.51    5179      85  5184.4   84.81  5193.3   85.43  5207.7   85.46
  5230.9   86.46  5306.2   88.24    5324   89.05  5333.3   88.84  5375.9   90.06
  5412.2    90.5  5422.5   91.09  5434.1   90.76  5474.4   91.31  5488.8    91.2
#Mann= 4 ,-1 , 0
  4596.4     .05       0  4990.9    .035       0  4996.9     .05       0
  5333.3      .1       0
Bank Sta=4990.9,4996.9
XS Rating Curve= 0 ,0
Exp/Cntr=0.3,0.1

Type RM Length L Ch R = 1 ,1884    ,96,96,96
BEGIN DESCRIPTION:
Mapping XS f4a298b6
END DESCRIPTION:
XS GIS Cut Line= 3
      2338609.72     13179431.76      2338839.75     13179054.16
      2339143.14     13178605.57
#Sta/Elev= 30
  4506.8   91.44  4549.5   91.25  4663.2    88.8  4668.5   89.01  4784.7   85.63
  4815.6   84.25  4836.9   83.94  4842.8   83.29  4852.1   83.56  4879.6   82.89
  4900.9   83.27  4916.4   84.13  4922.4   83.69  4930.3   81.05  4937.7    80.1
  5072.8   80.09  5075.6   79.59  5078.8   80.09  5082.5   80.62  5102.9   82.42
  5111.8   84.28  5117.8   82.01  5122.9   81.91  5138.9   82.79  5175.1   83.36
  5239.9   85.67  5247.5    86.2  5270.6   86.23    5408    89.5  5490.5   91.13
#Mann= 10 ,-1 , 0
  4506.8     .05       0  4549.5      .1       0  4663.2     .16       0
  4930.3      .1       0  5072.8     .07       0  5078.8      .1       0
  5082.5     .16       0  5122.9      .1       0  5239.9     .16       0
    5408      .1       0
Bank Sta=5072.8,5078.8
XS Rating Curve= 0 ,0
Exp/Cntr=0.3,0.1

Type RM Length L Ch R = 1 ,1788    ,30,30,30
BEGIN DESCRIPTION:
UNT316 IN BACR 4.0
END DESCRIPTION:
XS GIS Cut Line= 5
      2338674.81     13179446.97      2338891.63     13179127.52
      2338969.95     13179038.97      2338978.64     13178986.89
      2339205.52     13178630.36
#Sta/Elev= 30
  4530.8   91.86  4576.9   91.21  4582.9   91.78  4590.6   90.92  4707.7   88.22
  4869.6   82.84  4943.3   84.99  4964.2   84.73  4971.2   82.54  4975.4   80.19
  4978.1   79.69  4981.4   80.19    4985   84.07  4992.6   81.55  4999.3   82.39
  5006.8   80.33  5013.5   84.38  5038.7   84.72  5052.2   82.92  5064.5   84.38
  5077.8   84.74  5090.9   83.85  5094.7   81.94  5100.6   81.01  5115.9    80.6
  5151.9   82.26  5171.3   82.76  5297.9   86.68  5482.9   90.68  5510.5   91.11
#Mann= 10 ,-1 , 0
  4530.8     .05       0  4590.6      .1       0  4707.7     .16       0
  4869.6      .1       0  4975.4     .07       0  4981.4      .1       0
  5064.5     .16       0  5151.9      .1       0  5171.3     .16       0
  5482.9      .1       0
Bank Sta=4975.4,4981.4
XS Rating Curve= 0 ,0
Exp/Cntr=0.3,0.1

Type RM Length L Ch R = 1 ,1758    ,389,389,389
BEGIN DESCRIPTION:
Mapping XS 41c8ea13
END DESCRIPTION:
XS GIS Cut Line= 2
      2338698.67     13179468.69      2339249.89     13178683.08
#Sta/Elev= 30
  4520.2   91.96  4527.9   91.47  4548.8   91.86  4605.7   90.44  4649.9   89.62
  4706.3   87.82    4724   87.44  4832.7   83.64  4858.2   82.97  4864.5   82.34
  4914.9   81.43  4929.7   80.73  4959.3   80.69  4965.4    80.2    5016   79.67
  5030.8   80.62  5036.9   79.71  5045.6   79.47  5048.7   78.86  5051.5   78.36
  5054.7   78.86  5059.9   79.82  5071.1   80.48  5084.5   80.69  5169.5   82.77
    5231   84.46  5245.2   85.27  5253.9   85.13  5375.9   88.32  5479.9    90.3
#Mann= 10 ,-1 , 0
  4520.2     .05       0  4605.7      .1       0  4706.3     .05       0
    4724     .16       0  4832.7      .1       0  5048.7     .07       0
  5054.7      .1       0  5071.1     .16       0  5084.5      .1       0
  5169.5     .16       0
Bank Sta=5048.7,5054.7
XS Rating Curve= 0 ,0
Exp/Cntr=0.3,0.1

Type RM Length L Ch R = 1 ,1369    ,454,454,454
BEGIN DESCRIPTION:
UNT316 IN BACR 3.0
END DESCRIPTION:
XS GIS Cut Line= 3
      2338887.72     13179546.86      2339187.72     13179346.85
      2339337.73     13179196.85
#Sta/Elev= 30
  4666.4   88.85  4767.1    85.7  4774.6   85.19  4810.6   84.39  4818.1   83.68
  4839.2   83.31  4869.2   81.78  4876.2   81.86  4882.7   81.85  4890.2   81.28
  4918.8   80.25  4926.3   79.76  4947.3   79.39  4962.4   78.76  4968.4   78.46
  4995.4    76.3  4998.2    75.8  5001.4    76.3  5004.4   76.63  5019.4   76.77
    5024   77.19  5030.5   77.19  5041.1   78.23  5055.2   79.13  5083.5   79.57
  5111.8    81.3  5168.4   83.41  5224.9   86.72  5235.6   87.86  5239.1   87.86
#Mann= 4 ,-1 , 0
  4666.4     .05       0  4876.2      .1       0  4995.4     .07       0
  5001.4      .1       0
Bank Sta=4995.4,5001.4
XS Rating Curve= 0 ,0
Exp/Cntr=0.3,0.1

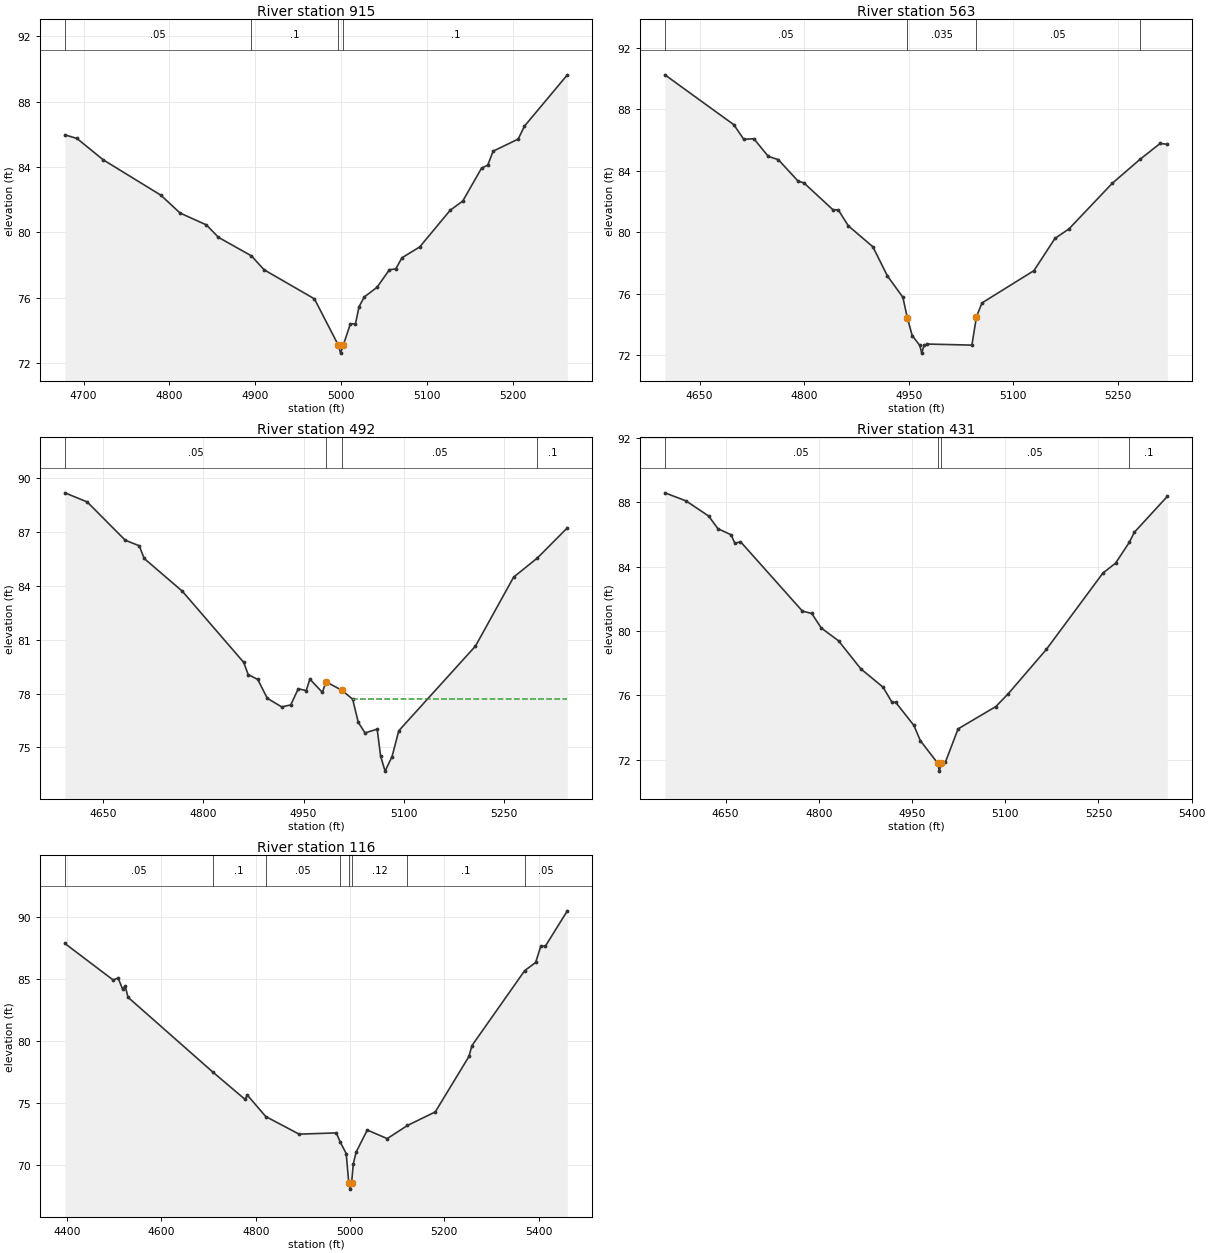
Type RM Length L Ch R = 1 ,915     ,352,352,352
BEGIN DESCRIPTION:
UNT316 IN BACR 2.0
END DESCRIPTION:
XS GIS Cut Line= 3
      2339087.74     13179896.85      2339387.72     13179746.85
      2339587.73     13179596.85
#Sta/Elev= 30
  4678.2   85.97  4692.2   85.75  4722.9   84.44    4790   82.28  4812.3   81.19
  4843.1   80.46  4857.1    79.7  4895.5   78.57  4910.2   77.72  4968.9   75.94
  4996.6   73.12  4999.4   72.62  5002.6   73.12  5010.8   74.41  5016.7   74.41
  5020.9   75.46  5027.1   76.06  5041.7   76.64  5056.3   77.72  5063.6   77.77
  5070.9   78.45  5091.7   79.12  5127.1   81.36  5141.7   81.92  5163.6   83.93
  5170.9   84.12  5177.1   84.97  5206.3   85.71  5213.6    86.5  5263.6   89.64
#Mann= 4 ,-1 , 0
  4678.2     .05       0  4895.5      .1       0  4996.6     .07       0
  5002.6      .1       0
Bank Sta=4996.6,5002.6
XS Rating Curve= 0 ,0
Exp/Cntr=0.3,0.1

Type RM Length L Ch R = 1 ,563     ,71,71,71
BEGIN DESCRIPTION:
Mapping XS 67d350ce
END DESCRIPTION:
XS GIS Cut Line= 3
      2339301.97      13180360.6      2339594.95     13180004.68
      2339620.99     13179746.49
#Sta/Elev= 30
  4600.4   90.23  4699.2   86.99  4713.5   86.04  4727.9   86.08  4748.7   84.93
    4763   84.72  4791.7   83.31  4799.5   83.22  4841.2   81.47  4849.1   81.45
  4863.4   80.42  4898.6   79.06  4919.4   77.17  4941.6   75.78  4948.1   74.43
    4955   73.29  4965.9   72.65  4968.7   72.15  4971.9   72.65  4976.8   72.74
  5040.6   72.67  5047.1    74.5    5055   75.41  5129.6   77.51  5159.7    79.6
  5179.8   80.22  5241.8   83.18  5281.7   84.74  5310.5   85.77  5320.9   85.72
#Mann= 4 ,-1 , 0
  4600.4     .05       0  4948.1    .035       0  5047.1     .05       0
  5281.7      .1       0
Bank Sta=4948.1,5047.1
XS Rating Curve= 0 ,0
Exp/Cntr=0.3,0.1

Type RM Length L Ch R = 1 ,492     ,61,61,61
BEGIN DESCRIPTION:
Mapping XS a34c1a14
END DESCRIPTION:
XS GIS Cut Line= 4
      2339325.84     13180382.31      2339588.44     13180147.91
      2339616.66     13180078.47      2339662.24     13179757.24
#Sta/Elev= 30
  4593.1   89.19  4626.5   88.68  4683.3   86.55  4704.2   86.24  4711.7   85.53
  4768.6   83.71  4860.5   79.74  4867.2   79.06  4881.5   78.79  4895.7   77.74
  4917.3   77.26  4930.8   77.37  4942.1   78.27    4954   78.17  4959.4   78.81
  4978.1   78.07  4983.5   78.66  5007.6   78.18  5023.4   77.69  5031.8    76.4
  5041.9   75.81  5060.1   76.02  5065.2   74.52  5071.9   73.68  5082.3   74.49
  5092.4   75.93  5207.1   80.65  5264.1   84.49  5299.7   85.56  5344.5   87.24
#Mann= 4 ,-1 , 0
  4593.1     .05       0  4983.5     .03       0  5007.6     .05       0
  5299.7      .1       0
#XS Ineff= 2 , 0
       0                 5023.86       0    77.7
Permanent Ineff=
       F       T
Bank Sta=4983.5,5007.6
XS Rating Curve= 0 ,0
Exp/Cntr=0.3,0.1

Type RM Length L Ch R = 1 ,431     ,315,315,315
BEGIN DESCRIPTION:
Mapping XS aef08ca5
END DESCRIPTION:
XS GIS Cut Line= 3
      2339343.24     13180399.63      2339651.38       13180200.
      2339722.86     13179764.58
#Sta/Elev= 30
  4552.5    88.6  4586.4    88.1  4622.7   87.16  4637.8   86.37  4658.9   85.99
  4665.1   85.46  4674.1   85.56  4773.7   81.24  4788.8   81.09    4804   80.19
  4831.9   79.39  4867.6   77.65  4903.6    76.5  4917.9   75.56  4923.8   75.56
  4953.2   74.12  4963.4   73.18  4991.3   71.78    4994   71.28  4997.3   71.78
  5003.9   71.85  5024.2   73.91    5085    75.3  5105.2   76.11  5166.1   78.85
  5257.3   83.61  5277.5   84.22  5299.5   85.51  5307.9   86.15  5360.9   88.38
#Mann= 4 ,-1 , 0
  4552.5     .05       0  4991.3     .03       0  4997.3     .05       0
  5299.5      .1       0
Bank Sta=4991.3,4997.3
XS Rating Curve= 0 ,0
Exp/Cntr=0.3,0.1

Type RM Length L Ch R = 1 ,116     ,0,0,0
BEGIN DESCRIPTION:
UNT316 IN BACR 1.0
END DESCRIPTION:
XS GIS Cut Line= 4
      2339360.62     13180451.72      2339794.61      13180308.5
      2340072.39     13180121.87       2340111.2     13179850.19
#Sta/Elev= 30
  4395.1   87.87  4497.4   84.93  4507.9   85.09  4517.7   84.18    4523   84.45
  4528.9   83.54  4708.7   77.52    4777   75.32  4782.3   75.65  4821.2   73.93
    4892   72.51    4971   72.61    4979   71.89    4992   70.94  4997.4   68.58
  5000.2   68.08  5003.4   68.58    5007   70.13    5013   71.06  5036.6   72.84
    5079   72.15  5121.9   73.21  5180.9    74.3  5252.4   78.77  5258.7   79.64
  5370.6   85.68  5393.9   86.34  5405.1   87.68  5414.1   87.63  5461.2    90.5
#Mann= 8 ,-1 , 0
  4395.1     .05       0  4708.7      .1       0  4821.2     .05       0
    4979     .12       0  4997.4     .07       0  5003.4     .12       0
  5121.9      .1       0  5370.6     .05       0
Bank Sta=4997.4,5003.4
XS Rating Curve= 0 ,0
Exp/Cntr=0.3,0.1

Chan Stop Cuts=-1
Use User Specified Reach Order=0
Composite Channel Slope=5