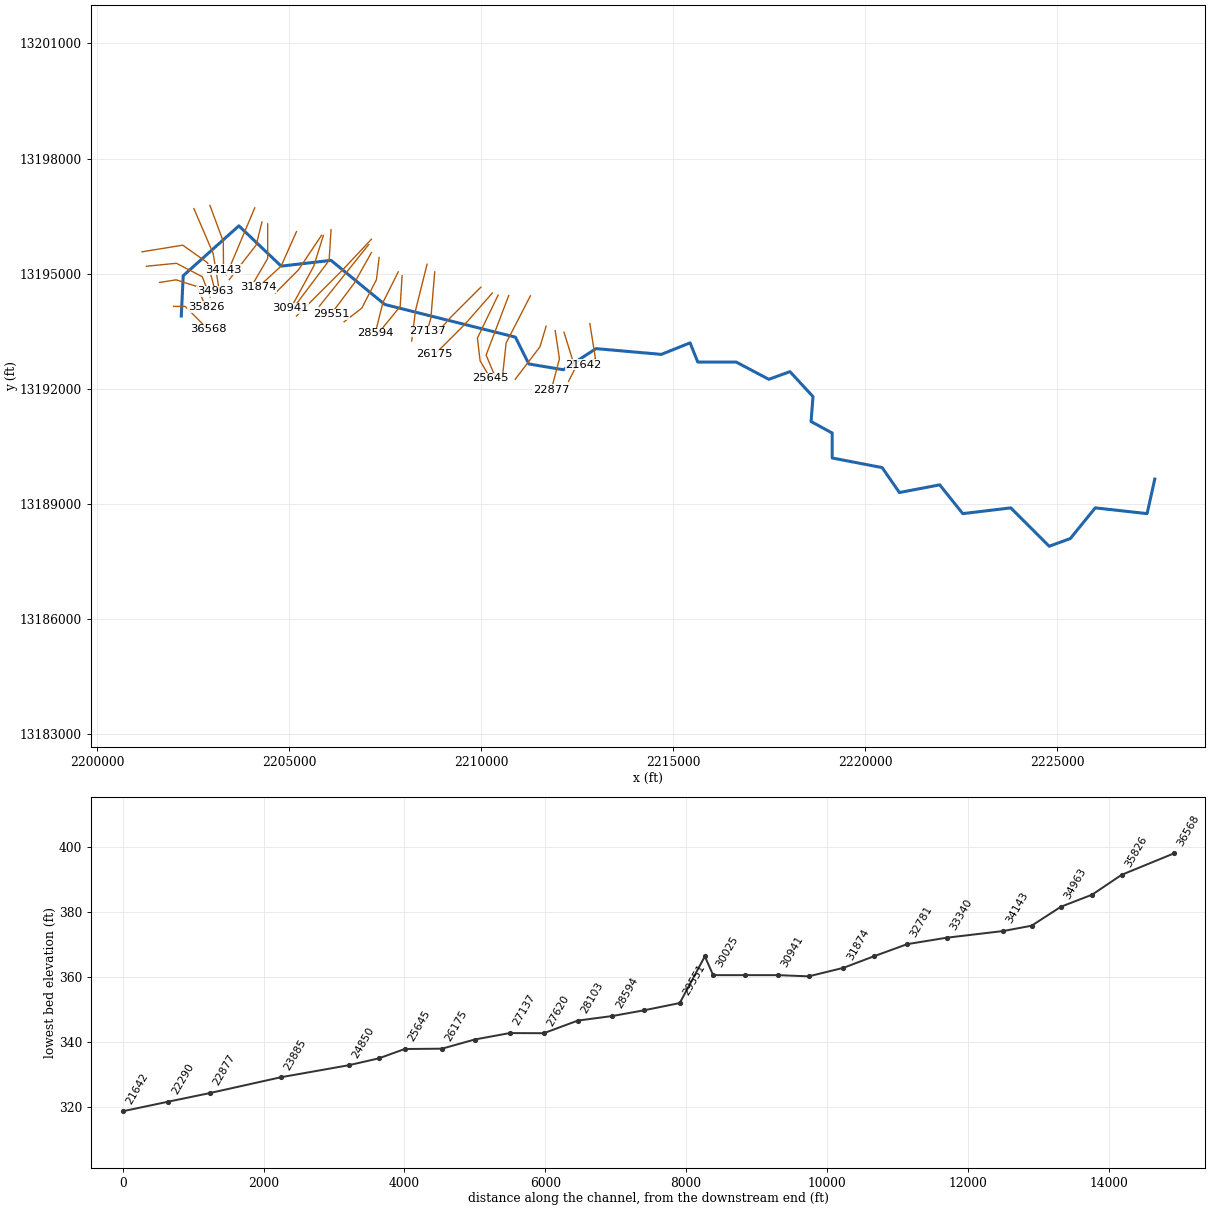
--- BOTELLO CREEK.prj (project) ---

Proj Title=BOTELLO CREEK Base Level Engineering
Current Plan=p01
Default Exp/Contr=0.3,0.1
English Units
Geom File=g01
Flow File=f01
Plan File=p01
Y Axis Title=Elevation
X Axis Title(PF)=Main Channel Distance
X Axis Title(XS)=Station
BEGIN DESCRIPTION:
BOTELLO CREEK
END DESCRIPTION:
DSS Export Rating Curves= 0
DSS Export Rating Curve Sorted= 0
DSS Export Volume Flow Curves= 0
DXF OffsetX= 0
DXF OffsetY= 0
DXF ScaleX= 1
DXF ScaleY= 10

--- BOTELLO CREEK.p01 (plan) ---

Plan Title=Multiple Run
Short Identifier=Multiple
Geom File=g01
Flow File=f01
Subcritical Flow
K Sum by GR= 0
Std Step Tol= 0.01
Critical Tol= 0.01
Num of Std Step Trials= 20
Max Error Tol= 0.3
Flow Tol Ratio= 0.001
Split Flow NTrial= 30
Split Flow Tol= 0.02
Split Flow Ratio= 0.02
Log Output Level= 0
Friction Slope Method= 1
Unsteady Friction Slope Method= 2
Unsteady Bridges Friction Slope Method= 1
Parabolic Critical Depth
Global Vel Dist=  1 , 1 , 1
Global Log Level= 0
CheckData=True
Encroach Param= -1, 0, 0, 0
BEGIN DESCRIPTION:
Multiple Run
END DESCRIPTION:

--- BOTELLO CREEK.f01 (steady flow) ---

Flow Title=Multiple
Program Version=4.10
Number of Profiles= 7
Profile Names=10-year,25-year,50-year,1pct_min,100-year,1pct_plu,500-year
River Rch & RM=BOTELLO CREEK,Reach-1         ,36568
     155     212     259     233     315     426     475
River Rch & RM=BOTELLO CREEK,Reach-1         ,34547
     208     288     355     323     436     590     668
River Rch & RM=BOTELLO CREEK,Reach-1         ,34143
     208     288     355     323     436     590     668
River Rch & RM=BOTELLO CREEK,Reach-1         ,30025
     294     415     517     474     641     867    1002
River Rch & RM=BOTELLO CREEK,Reach-1         ,26175
     385     551     692     639     864    1168    1369
River Rch & RM=BOTELLO CREEK,Reach-1         ,25645
     385     551     692     639     864    1168    1369
River Rch & RM=BOTELLO CREEK,Reach-1         ,21121
    1038    1530    1962    1841    2490    3368    4077
River Rch & RM=BOTELLO CREEK,Reach-1         ,20445
    1038    1530    1962    1841    2490    3368    4077
River Rch & RM=BOTELLO CREEK,Reach-1         ,17519
    1104    1630    2092    1965    2657    3593    4356
River Rch & RM=BOTELLO CREEK,Reach-1         ,10274
    1121    1655    2124    1995    2698    3648    4423
River Rch & RM=BOTELLO CREEK,Reach-1         ,5914
    1537    2290    2958    2793    3777    5108    6257
River Rch & RM=BOTELLO CREEK,Reach-1         ,2463
    1807    2668    3427    3221    4355    5890    7151
Boundary for River Rch & Prof#=BOTELLO CREEK,Reach-1         , 1
Up Type= 0
Dn Type= 3
Dn Slope=0.002
Boundary for River Rch & Prof#=BOTELLO CREEK,Reach-1         , 2
Up Type= 0
Dn Type= 3
Dn Slope=0.002
Boundary for River Rch & Prof#=BOTELLO CREEK,Reach-1         , 3
Up Type= 0
Dn Type= 3
Dn Slope=0.002
Boundary for River Rch & Prof#=BOTELLO CREEK,Reach-1         , 4
Up Type= 0
Dn Type= 3
Dn Slope=0.002
Boundary for River Rch & Prof#=BOTELLO CREEK,Reach-1         , 5
Up Type= 0
Dn Type= 3
Dn Slope=0.002
Boundary for River Rch & Prof#=BOTELLO CREEK,Reach-1         , 6
Up Type= 0
Dn Type= 3
Dn Slope=0.002
Boundary for River Rch & Prof#=BOTELLO CREEK,Reach-1         , 7
Up Type= 0
Dn Type= 3
Dn Slope=0.002
DSS Import GetInterval= 0
DSS Import GetPeak= 0
DSS Import FillOption= 0

--- BOTELLO CREEK.g01 (geometry) ---

Geom Title=Existing Conditions
Program Version=4.10

River Reach=BOTELLO CREEK   ,Reach-1
Reach XY= 30
      2202187.72     13193896.85      2202237.72     13194946.86
      2203687.72     13196246.86      2204787.72     13195196.85
      2206087.72     13195346.85      2207487.72     13194196.85
      2210887.72     13193346.85      2211237.72     13192646.86
      2212137.72     13192496.86      2212987.72     13193046.85
      2214687.72     13192896.85      2215437.72     13193196.85
      2215637.72     13192696.85      2216637.72     13192696.85
      2217487.72     13192246.85      2218037.72     13192446.85
      2218637.72     13191796.85      2218587.72     13191146.86
      2219137.72     13190846.86      2219137.72     13190196.86
      2220437.72     13189946.85      2220887.72     13189296.85
      2221937.72     13189496.85      2222537.72     13188746.85
      2223787.72     13188896.85      2224787.72     13187896.86
      2225337.72     13188096.85      2225987.72     13188896.85
      2227337.72     13188746.85      2227537.72     13189646.85

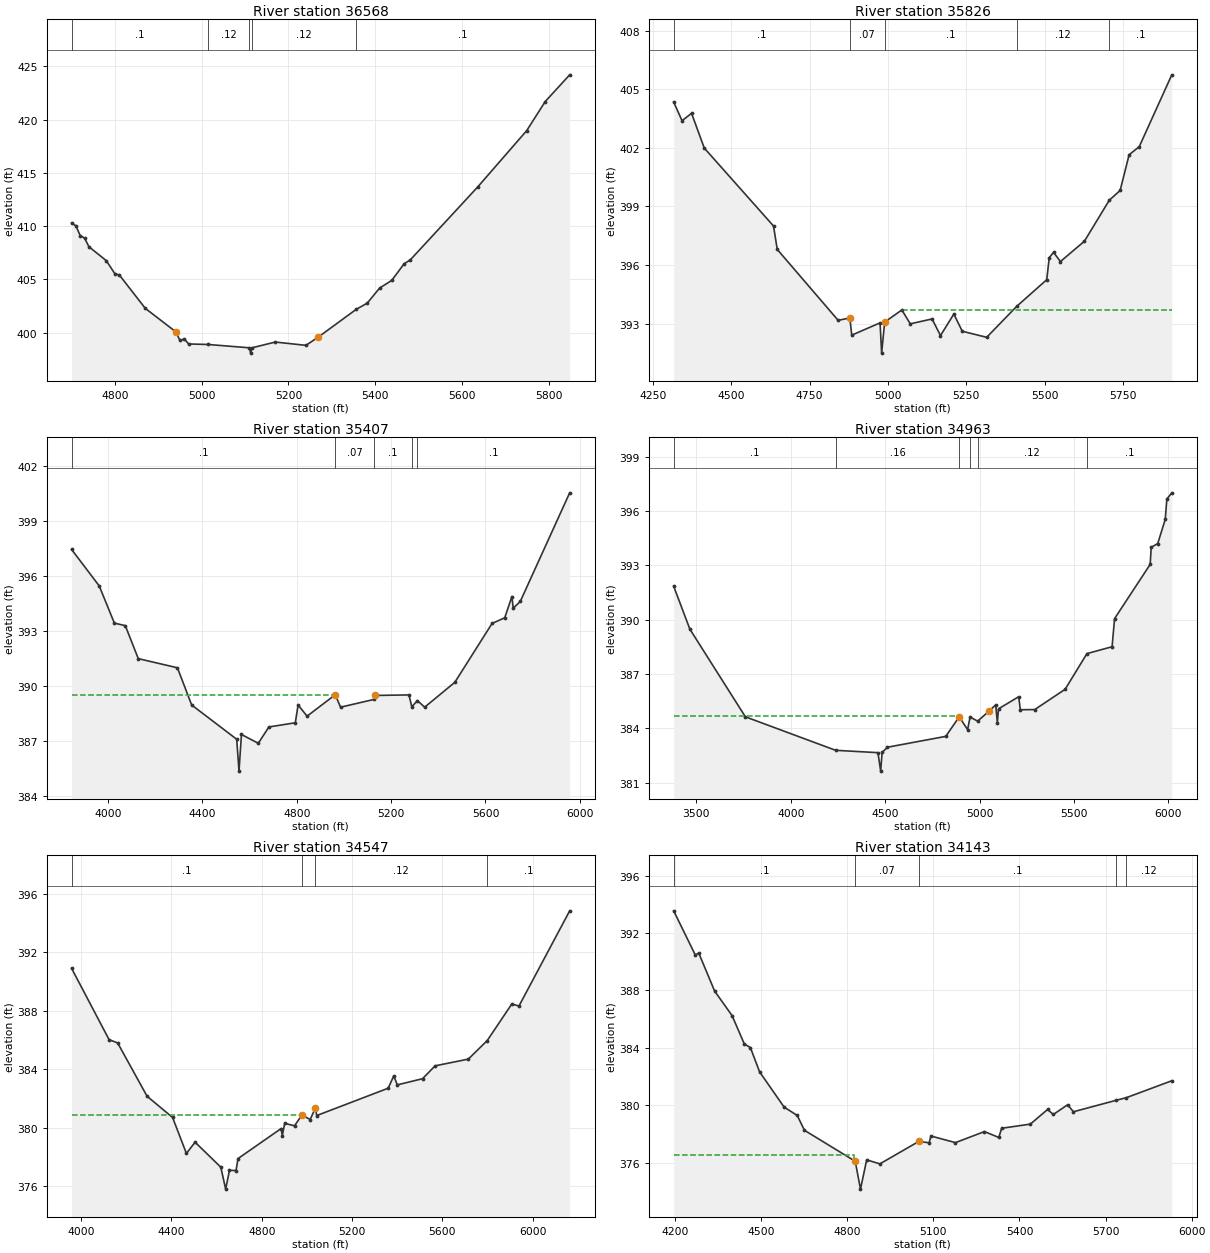
Type RM Length L Ch R = 1 ,36568   ,742,742,742
BEGIN DESCRIPTION:
BOTELLO CREEK 60.0
END DESCRIPTION:
XS GIS Cut Line= 3
      2201987.72     13194146.85      2202287.72     13194146.85
       2202887.7     13193546.87
#Sta/Elev= 30
    4700  410.31    4710  410.03    4720  409.11    4730  408.89    4740  408.07
    4780  406.77    4800  405.53    4810  405.43    4870  402.29    4940   400.1
    4950  399.28    4960  399.41    4970  398.95    5015   398.9  5110.1  398.59
  5112.9  398.09  5116.1  398.59  5169.7  399.13  5240.4  398.82  5268.7  399.59
  5356.4   402.2  5381.8  402.78  5410.1  404.19  5438.4  404.92  5466.7  406.47
  5480.8  406.83  5636.4  413.68  5749.5  418.97    5792  421.69  5848.5   424.2
#Mann= 5 ,-1 , 0
    4700      .1       0    5015     .12       0  5110.1     .07       0
  5116.1     .12       0  5356.4      .1       0
Bank Sta=4940,5268.7
XS Rating Curve= 0 ,0
Exp/Cntr=0.3,0.1

Type RM Length L Ch R = 1 ,35826   ,419,419,419
BEGIN DESCRIPTION:
BOTELLO CREEK 59.0
END DESCRIPTION:
XS GIS Cut Line= 4
       2201621.4     13194770.64      2202051.91     13194840.07
      2202593.57     13194666.46      2202829.64     13194131.84
#Sta/Elev= 30
  4316.3  404.35    4343  403.39  4373.3  403.77  4413.9  401.99  4634.8     398
  4646.8   396.8    4841  393.17  4878.4  393.29  4884.5  392.41  4974.8  393.04
  4979.8  391.49  4989.5  393.08  5044.3   393.7  5071.2  392.99  5140.7  393.24
  5167.6  392.39  5210.2  393.49  5237.1  392.61    5315   392.3  5410.4  393.88
  5506.6  395.25  5514.6  396.38  5528.4  396.65  5550.3  396.18  5626.8  397.22
  5706.2  399.32  5740.8  399.82  5769.5  401.65  5801.7  402.06  5905.6  405.74
#Mann= 5 ,-1 , 0
  4316.3      .1       0  4878.4     .07       0  4989.5      .1       0
  5410.4     .12       0  5706.2      .1       0
#XS Ineff= 2 , 0
       0                 5043.71       0   393.7
Permanent Ineff=
       F       T
Bank Sta=4878.4,4989.5
XS Rating Curve= 0 ,0
Exp/Cntr=0.3,0.1

Type RM Length L Ch R = 1 ,35407   ,444,444,444
BEGIN DESCRIPTION:
BOTELLO CREEK 58.0
END DESCRIPTION:
XS GIS Cut Line= 4
      2201281.04     13195194.24      2202058.85     13195270.63
      2202732.46     13194923.41      2202940.19     13194390.23
#Sta/Elev= 30
  3845.3  397.47  3962.5  395.48  4026.7  393.45  4073.1  393.31  4128.1  391.51
  4294.1  391.01  4354.4  388.98  4545.3  387.11  4555.1  385.37  4565.4  387.37
  4636.8  386.89  4681.8  387.78  4793.7  388.01  4805.6  388.98  4843.7  388.37
  4963.1  389.54  4985.6  388.86  5126.2  389.28  5131.8   389.5  5275.7  389.53
  5287.5  388.88  5311.3  389.22  5342.2  388.86  5470.1  390.22  5627.8  393.43
  5681.5  393.74  5712.1   394.9  5717.5  394.26  5747.4  394.63  5956.9  400.56
#Mann= 5 ,-1 , 0
  3845.3      .1       0  4963.1     .07       0  5126.2      .1       0
  5287.5     .12       0  5311.3      .1       0
#XS Ineff= 2 , 0
       0 4954.55  389.54               0
Permanent Ineff=
       T       F
Bank Sta=4963.1,5131.8
XS Rating Curve= 0 ,0
Exp/Cntr=0.3,0.1

Type RM Length L Ch R = 1 ,34963   ,416,416,416
BEGIN DESCRIPTION:
BOTELLO CREEK 57.0
END DESCRIPTION:
XS GIS Cut Line= 4
      2201163.01     13195569.24      2202225.52     13195742.85
      2202871.35     13195284.52      2203072.69     13194541.66
#Sta/Elev= 30
  3379.6  391.85  3465.4  389.48  3759.3  384.64  4237.4  382.79  4461.5  382.66
    4476  381.64  4483.4  382.67  4511.9  382.96  4820.7  383.56    4892  384.64
  4936.4  383.93  4949.4  384.63  4989.6   384.4  5049.5  384.95  5085.2   385.3
  5093.8  384.32    5100  385.08    5207  385.75  5215.6  385.03    5292  385.04
  5452.9  386.16  5568.4  388.13  5701.6  388.51  5714.6  390.06  5903.4  393.06
  5908.8     394  5943.3  394.21  5983.1  395.54  5991.7  396.67  6017.8  397.01
#Mann= 6 ,-1 , 0
  3379.6      .1       0  4237.4     .16       0    4892     .07       0
  4949.4      .1       0  4989.6     .12       0  5568.4      .1       0
#XS Ineff= 2 , 0
       0 4891.19  384.66               0
Permanent Ineff=
       T       F
Bank Sta=4892,5049.5
XS Rating Curve= 0 ,0
Exp/Cntr=0.3,0.1

Type RM Length L Ch R = 1 ,34547   ,404,404,404
BEGIN DESCRIPTION:
BOTELLO CREEK 56.0
END DESCRIPTION:
XS GIS Cut Line= 3
      2202517.18     13196694.26      2203017.19     13195527.57
      2203169.97     13194603.94
#Sta/Elev= 30
  3958.2   390.9  4124.3  386.02  4162.1   385.8  4292.6  382.15  4405.4   380.7
  4466.7  378.24  4505.1  379.01    4619   377.3  4640.5   375.8  4657.4  377.09
  4686.4  377.07  4695.2  377.89  4885.9  379.94  4891.3  379.46  4901.9   380.3
  4945.4  380.13  4978.1  380.87  5014.6  380.56  5038.2  381.36  5043.6  380.83
    5360   382.7  5384.7  383.54  5400.6  382.93  5512.1  383.35  5567.8  384.23
  5714.8  384.69  5798.7  385.96  5907.4  388.46  5939.1  388.32  6163.7  394.83
#Mann= 4 ,-1 , 0
  3958.2      .1       0  4978.1     .07       0  5038.2     .12       0
  5798.7      .1       0
#XS Ineff= 2 , 0
       0 4972.73  380.88               0
Permanent Ineff=
       T       F
Bank Sta=4978.1,5038.2
XS Rating Curve= 0 ,0
Exp/Cntr=0.3,0.1

Type RM Length L Ch R = 1 ,34143   ,803,803,803
BEGIN DESCRIPTION:
Mapping XS 9d94bf6c
END DESCRIPTION:
XS GIS Cut Line= 3
      2202933.85     13196777.59      2203281.07     13195840.07
      2203288.02     13195103.95
#Sta/Elev= 30
  4194.9  393.55  4270.3  390.47  4282.2  390.61  4337.6  387.96  4398.4  386.25
  4440.9  384.28  4462.3  384.02  4494.3  382.33  4579.6  379.88  4625.6  379.29
  4650.6  378.26  4827.6   376.1  4845.9  374.16  4867.5   376.2  4913.5  375.92
  5048.8  377.48  5085.2  377.39  5091.4  377.86  5176.8   377.4  5277.9  378.17
  5327.9  377.76  5337.9   378.4  5437.9  378.69  5497.9  379.71  5517.9  379.36
  5567.9  380.04  5587.9  379.55  5737.2  380.35  5772.1  380.53  5930.8  381.71
#Mann= 5 ,-1 , 0
  4194.9      .1       0  4827.6     .07       0  5048.8      .1       0
  5737.2      .1       0  5772.1     .12       0
#XS Ineff= 2 , 0
       0 4822.48  376.55               0
Permanent Ineff=
       T       F
Bank Sta=4827.6,5048.8
XS Rating Curve= 0 ,0
Exp/Cntr=0.3,0.1

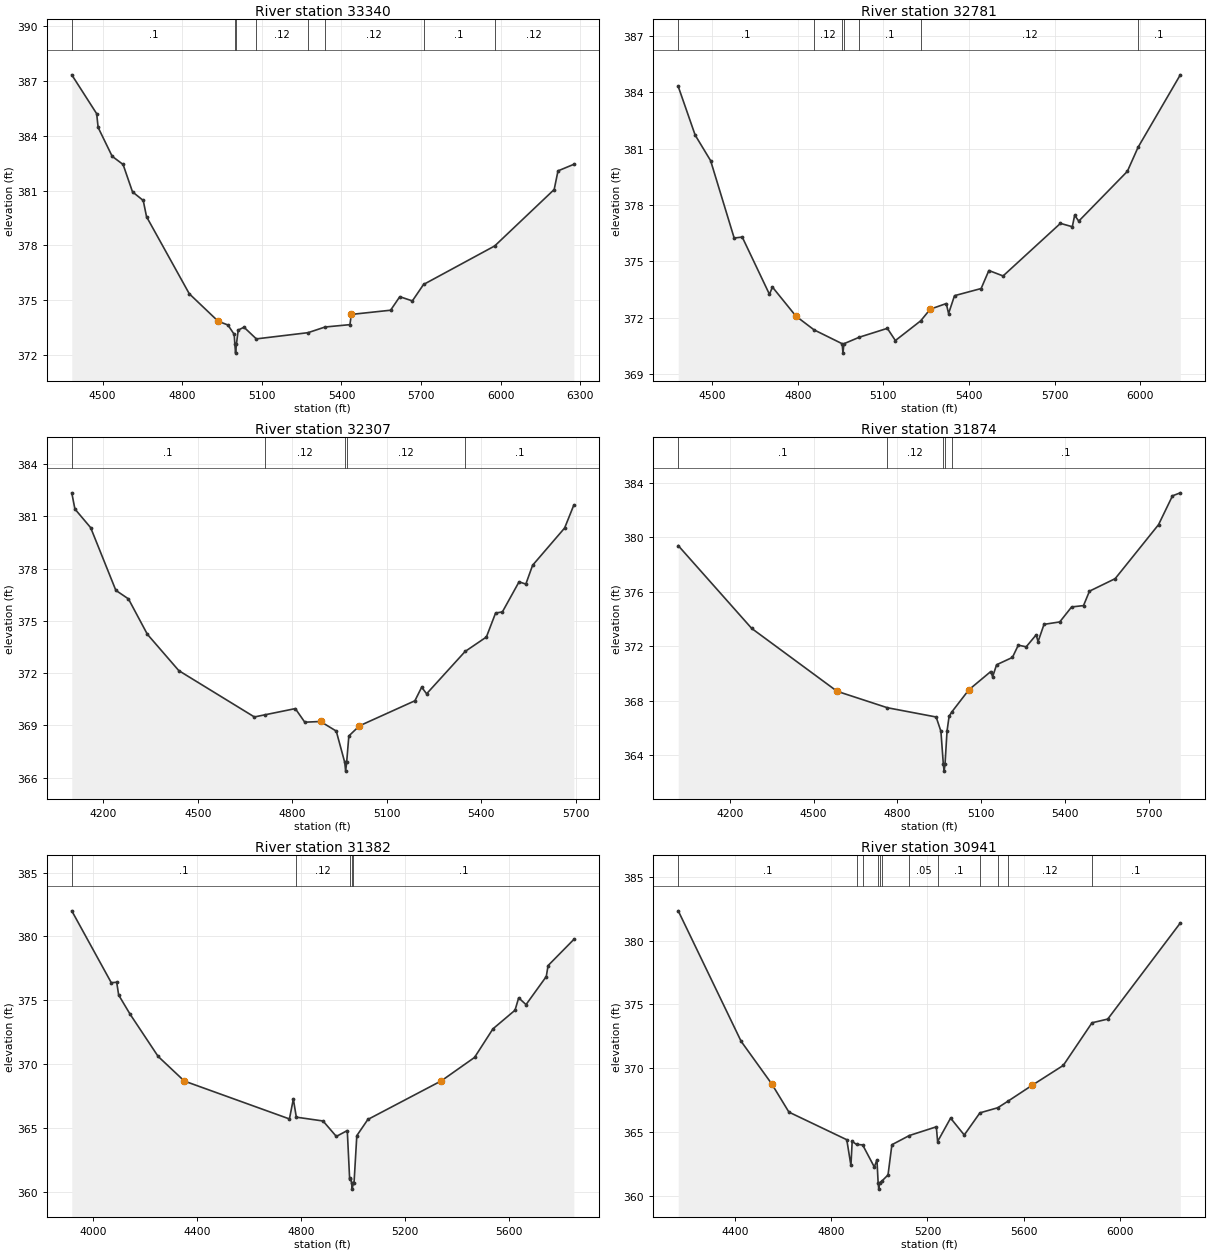
Type RM Length L Ch R = 1 ,33340   ,559,559,559
BEGIN DESCRIPTION:
BOTELLO CREEK 55.0
END DESCRIPTION:
XS GIS Cut Line= 3
      2204100.53      13196715.1       2203565.8     13195444.24
      2203364.39     13194971.97
#Sta/Elev= 30
  4383.5  387.34  4477.4  385.21  4482.8  384.46  4535.7  382.88  4576.9  382.43
  4612.4  380.93  4652.8  380.46  4665.3  379.57  4826.4  375.35  4934.9  373.85
  4971.9  373.64  4995.6  373.13  4998.1   372.6  5000.8   372.1  5004.1   372.6
  5010.8  373.36  5032.5  373.52  5079.1  372.88  5273.9  373.22    5338  373.53
  5431.8  373.66  5437.2  374.22  5585.1  374.45  5619.7  375.19  5667.1  374.96
  5709.3  375.86  5977.5  377.97  6201.6  381.06    6216  382.08  6275.7  382.44
#Mann= 8 ,-1 , 0
  4383.5      .1       0  4998.1     .07       0  5004.1      .1       0
  5079.1     .12       0  5273.9      .1       0    5338     .12       0
  5709.3      .1       0  5977.5     .12       0
Bank Sta=4934.9,5437.2
XS Rating Curve= 0 ,0
Exp/Cntr=0.3,0.1

Type RM Length L Ch R = 1 ,32781   ,474,474,474
BEGIN DESCRIPTION:
BOTELLO CREEK 54.0
END DESCRIPTION:
XS GIS Cut Line= 3
      2204287.73     13196346.89      2204137.72     13195746.86
      2203437.71     13194846.84
#Sta/Elev= 30
  4381.5  384.32  4440.8  381.73  4494.9  380.37  4577.4  376.25  4605.7   376.3
  4701.1  373.25  4711.4  373.64  4793.8  372.09  4857.2  371.36  4955.8  370.62
  4958.5  370.12  4961.8  370.62  5016.2  370.97    5114  371.44  5142.1  370.79
  5230.8  371.84  5264.2  372.46  5320.3  372.76  5328.5  372.23  5349.3  373.18
  5442.5  373.56  5469.6  374.52  5519.4  374.23  5720.3  377.03  5761.9  376.85
  5770.1  377.46  5784.5  377.15  5954.7   379.8  5992.2  381.08  6140.2  384.94
#Mann= 7 ,-1 , 0
  4381.5      .1       0  4857.2     .12       0  4955.8     .07       0
  4961.8     .12       0  5016.2      .1       0  5230.8     .12       0
  5992.2      .1       0
Bank Sta=4793.8,5264.2
XS Rating Curve= 0 ,0
Exp/Cntr=0.3,0.1

Type RM Length L Ch R = 1 ,32307   ,433,433,433
BEGIN DESCRIPTION:
BOTELLO CREEK 53.0
END DESCRIPTION:
XS GIS Cut Line= 3
      2204437.72     13196296.85      2204437.72     13195396.85
      2204087.73     13194796.87
#Sta/Elev= 30
    4100  382.35    4110  381.42    4160  380.35    4240  376.75    4280  376.26
    4340  374.23    4440  372.14    4680  369.48  4712.3   369.6    4810  369.96
    4840  369.18    4890  369.22    4940  368.67    4967  366.87  4969.8  366.37
    4973  366.87    4980  368.39  5013.6  368.97  5189.8  370.41  5211.3  371.19
    5227  370.81  5349.2  373.24  5416.8  374.07  5446.1  375.45  5467.6  375.51
  5520.6  377.24  5542.1  377.11  5563.6  378.19  5665.3  380.33  5694.6  381.65
#Mann= 5 ,-1 , 0
    4100      .1       0  4712.3     .12       0    4967     .07       0
    4973     .12       0  5349.2      .1       0
Bank Sta=4890,5013.6
XS Rating Curve= 0 ,0
Exp/Cntr=0.3,0.1

Type RM Length L Ch R = 1 ,31874   ,492,492,492
BEGIN DESCRIPTION:
BOTELLO CREEK 52.0
END DESCRIPTION:
XS GIS Cut Line= 3
      2205187.73     13196096.87      2204787.72     13195196.85
      2204187.75     13194646.88
#Sta/Elev= 30
  4015.1  379.39  4278.4   373.3  4584.2  368.68  4764.5  367.47  4939.1  366.79
  4956.2  365.74  4964.9  363.31  4967.6  362.81  4970.9  363.31  4978.1  365.75
  4985.6  366.85  4995.2  367.16  5056.4  368.79  5134.7  370.13  5141.5  369.75
  5155.7  370.63  5212.4  371.17  5233.4  372.07  5261.8  371.95  5297.5  372.83
  5304.3  372.33  5325.6   373.6    5382  373.78  5424.5  374.88  5467.1  374.98
  5488.4  376.04  5580.5  376.96  5735.9  380.93  5785.9  383.05  5813.9  383.27
#Mann= 5 ,-1 , 0
  4015.1      .1       0  4764.5     .12       0  4964.9     .07       0
  4970.9     .12       0  4995.2      .1       0
Bank Sta=4584.2,5056.4
XS Rating Curve= 0 ,0
Exp/Cntr=0.3,0.1

Type RM Length L Ch R = 1 ,31382   ,441,441,441
BEGIN DESCRIPTION:
BOTELLO CREEK 51.0
END DESCRIPTION:
XS GIS Cut Line= 3
      2205837.74     13195996.88      2205237.72     13195096.86
      2204637.74     13194496.87
#Sta/Elev= 30
  3918.3  382.01  4070.1  376.38  4091.1  376.41  4098.6  375.41  4142.2  373.92
  4250.3   370.6    4351  368.67  4755.1   365.7  4770.1  367.26  4781.6  365.84
  4884.3  365.54  4935.4  364.33  4977.5  364.79  4986.5  361.02  4989.5  361.07
    4994   360.7  4996.7   360.2    5000   360.7  5003.5   360.7  5014.1  364.39
  5056.6  365.66  5339.4  368.69  5466.7  370.52  5537.4  372.76  5622.3  374.22
  5636.4  375.19  5664.7  374.66  5742.5  376.86  5749.5  377.72  5848.5  379.77
#Mann= 5 ,-1 , 0
  3918.3      .1       0  4781.6     .12       0  4989.5      .1       0
    4994     .07       0    5000      .1       0
Bank Sta=4351,5339.4
XS Rating Curve= 0 ,0
Exp/Cntr=0.3,0.1

Type RM Length L Ch R = 1 ,30941   ,462,462,462
BEGIN DESCRIPTION:
BOTELLO CREEK 50.0
END DESCRIPTION:
XS GIS Cut Line= 3
      2205887.73      13195996.9      2205637.72     13195196.85
      2205037.72     13194096.85
#Sta/Elev= 30
  4161.8  382.32  4423.8  372.12  4551.1   368.8  4622.8  366.59  4863.8  364.43
  4881.1  362.42  4886.3   364.3  4904.6  364.06  4929.8  364.03  4978.5   362.3
  4989.5  362.86  4994.4  361.07  4997.1  360.57  5000.4  361.07    5010   361.2
  5035.6  361.68  5051.7  364.04  5124.5  364.76  5236.8  365.44  5242.1  364.29
  5296.2  366.12  5353.1   364.8  5418.3  366.53  5492.6  366.93  5534.1  367.43
  5634.6  368.67  5765.6  370.24  5885.2  373.57  5950.7  373.86    6253  381.37
#Mann= 12 ,-1 , 0
  4161.8      .1       0  4904.6     .12       0  4929.8     .05       0
  4994.4    .035       0  5000.4     .05       0    5010     .12       0
  5124.5     .05       0  5242.1      .1       0  5418.3     .12       0
  5492.6      .1       0  5534.1     .12       0  5885.2      .1       0
Bank Sta=4551.1,5634.6
XS Rating Curve= 0 ,0
Exp/Cntr=0.3,0.1

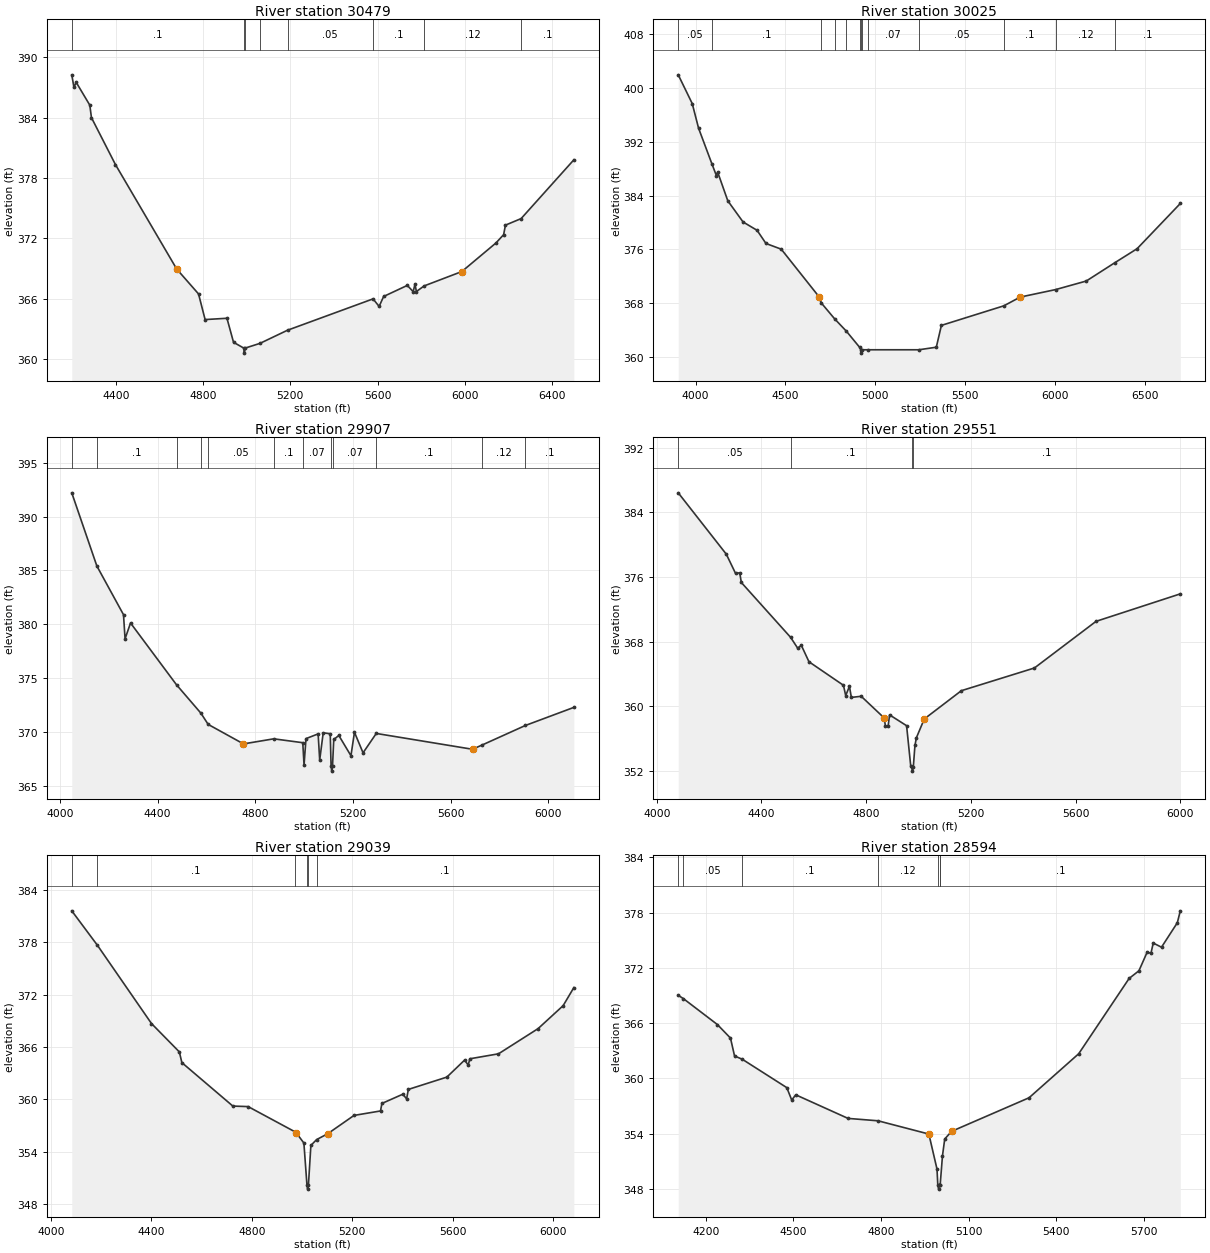
Type RM Length L Ch R = 1 ,30479   ,454,454,454
BEGIN DESCRIPTION:
BOTELLO CREEK 49.0
END DESCRIPTION:
XS GIS Cut Line= 3
      2206087.72     13196146.89      2206037.72     13195346.85
      2205137.72     13194146.86
#Sta/Elev= 30
  4198.4  388.27  4208.5  387.02  4218.5  387.53  4281.1  385.25  4288.6  384.01
  4398.8  379.33  4679.4  368.94  4779.6  366.46  4809.6  363.91  4909.8  364.04
  4939.9  361.65    4987  361.07  4989.7  360.57    4993  361.07    5061  361.54
  5187.4  362.85  5579.6  365.97  5607.3  365.22  5628.1  366.21  5736.5  367.31
  5763.5  366.69  5771.9  367.44  5778.1   366.7  5813.8  367.26  5986.5  368.69
  6142.7  371.53  6178.1  372.36  6186.5  373.31  6258.3  373.96    6500  379.81
#Mann= 8 ,-1 , 0
  4198.4      .1       0    4987     .07       0    4993      .1       0
    5061     .12       0  5187.4     .05       0  5579.6      .1       0
  5813.8     .12       0  6258.3      .1       0
Bank Sta=4679.4,5986.5
XS Rating Curve= 0 ,0
Exp/Cntr=0.3,0.1

Type RM Length L Ch R = 1 ,30025   ,118,118,118
BEGIN DESCRIPTION:
BOTELLO CREEK 48.0
END DESCRIPTION:
XS GIS Cut Line= 3
      2207137.73     13195896.87      2206387.72     13195096.86
      2205187.69     13193896.82
#Sta/Elev= 30
  3903.4  401.99  3981.3  397.71  4016.5  394.05  4090.2  388.78  4115.6     387
  4122.7  387.52  4179.2  383.24  4264.1  380.09    4342  378.85  4391.6  376.89
  4476.6  376.04  4688.6   368.9  4699.7  368.03  4774.4  365.65  4839.1  363.83
  4913.5  361.41  4919.1  361.07  4921.8  360.57  4925.1  361.07  4956.6  361.07
  5242.5  361.07  5339.4  361.45  5367.7   364.7  5715.2  367.61  5806.1  368.91
  6003.6  370.03  6173.8   371.3  6334.1  374.05  6456.6  376.11  6697.1  382.84
#Mann= 13 ,-1 , 0
  3903.4     .05       0  4090.2      .1       0  4699.7     .05       0
  4774.4      .1       0  4839.1     .05       0  4913.5      .1       0
  4919.1     .07       0  4925.1      .1       0  4956.6     .07       0
  5242.5     .05       0  5715.2      .1       0  6003.6     .12       0
  6334.1      .1       0
Bank Sta=4688.6,5806.1
XS Rating Curve= 0 ,0
Exp/Cntr=0.3,0.1

Type RM Length L Ch R = 1 ,29907   ,356,356,356
BEGIN DESCRIPTION:
Mapping XS f7dd37d1
END DESCRIPTION:
XS GIS Cut Line= 2
       2207066.1     13195756.01      2205781.41     13194150.16
#Sta/Elev= 30
  4048.4  392.21  4151.2  385.41  4260.3  380.89  4266.7  378.65  4289.1  380.12
  4477.4  374.38  4577.1  371.75  4607.1   370.7  4751.7  368.89  4875.8  369.36
  4994.6     369  4999.8  366.93  5007.8  369.38  5057.5  369.82  5063.9  367.39
  5078.3  369.92  5107.1  369.83  5110.5  366.86  5113.2  366.36  5116.5  366.86
  5121.5   369.3  5142.3  369.67  5191.9  367.79  5206.3  369.97  5241.5  368.06
  5295.6  369.86  5689.8  368.39  5729.6  368.79  5906.4   370.6  6104.9  372.28
#Mann= 12 ,-1 , 0
  4048.4     .05       0  4151.2      .1       0  4477.4     .05       0
  4577.1      .1       0  4607.1     .05       0  4875.8      .1       0
  4994.6     .07       0  5110.5     .07       0  5116.5     .07       0
  5295.6      .1       0  5729.6     .12       0  5906.4      .1       0
Bank Sta=4751.7,5689.8
XS Rating Curve= 0 ,0
Exp/Cntr=0.3,0.1

Type RM Length L Ch R = 1 ,29551   ,512,512,512
BEGIN DESCRIPTION:
BOTELLO CREEK 47.0
END DESCRIPTION:
XS GIS Cut Line= 3
      2207137.73     13195546.87      2206687.72     13194746.85
      2206087.72     13193946.85
#Sta/Elev= 30
  4082.1   386.4  4265.7  378.81  4301.1  376.43    4317  376.51  4323.1  375.31
  4511.4  368.52  4538.2  367.19  4552.5  367.52  4581.5   365.5  4713.2  362.59
  4721.8  361.32  4736.1  362.46  4743.4  361.09    4781  361.23  4867.7  358.58
  4873.8  357.57  4883.7   357.5  4889.4  358.93  4954.4  357.59  4970.4  352.55
  4974.1  352.47  4976.8  351.97  4980.1  352.47  4986.3  355.15    4992  356.11
  5021.9  358.42  5163.5  361.92  5442.7  364.73  5678.1   370.5    6000   373.9
#Mann= 4 ,-1 , 0
  4082.1     .05       0  4511.4      .1       0  4974.1     .07       0
  4980.1      .1       0
Bank Sta=4867.7,5021.9
XS Rating Curve= 0 ,0
Exp/Cntr=0.3,0.1

Type RM Length L Ch R = 1 ,29039   ,445,445,445
BEGIN DESCRIPTION:
BOTELLO CREEK 46.0
END DESCRIPTION:
XS GIS Cut Line= 4
      2207339.54     13195421.78       2207270.1     13194844.56
      2206888.16     13194102.38      2206428.12      13193746.5
#Sta/Elev= 30
  4083.8  381.61  4186.1  377.65    4401  368.69  4511.8  365.44  4521.9  364.21
  4724.7  359.23  4785.6  359.17  4971.9  356.28  4977.5  356.14  5007.4  354.99
  5019.5  350.21  5022.2  349.71  5025.5  350.21  5035.2  354.72  5058.1  355.39
  5101.7  356.05  5206.9  358.16  5312.2  358.67  5317.8  359.53  5400.9  360.59
  5416.1  360.06    5423  361.14  5576.2  362.55  5646.8   364.5  5661.3  363.93
  5667.6  364.65  5781.7  365.22  5939.3  368.11  6038.9  370.74  6081.5  372.81
#Mann= 6 ,-1 , 0
  4083.8     .05       0  4186.1      .1       0  4971.9     .12       0
  5019.5     .07       0  5025.5     .12       0  5058.1      .1       0
Bank Sta=4977.5,5101.7
XS Rating Curve= 0 ,0
Exp/Cntr=0.3,0.1

Type RM Length L Ch R = 1 ,28594   ,491,491,491
BEGIN DESCRIPTION:
BOTELLO CREEK 45.0
END DESCRIPTION:
XS GIS Cut Line= 3
      2207837.71     13195046.83      2207437.72     13194246.85
      2207237.73     13193446.88
#Sta/Elev= 30
  4105.6  369.02  4123.5  368.65  4239.7  365.84  4284.5  364.37  4298.4  362.43
    4325  362.07  4477.3  358.99  4494.1  357.65  4508.1  358.21    4687  355.65
  4789.6  355.39  4963.7  353.95  4991.6  350.14  4994.2  348.47    4997  347.97
  5000.2  348.47  5002.5  348.47  5010.3  351.59    5018  353.41  5041.2  354.24
  5306.7  357.89  5476.7  362.67  5649.4  370.85  5682.9  371.68  5711.2  373.71
  5724.1  373.58  5731.9  374.69  5760.2  374.24  5814.3  376.89  5824.6  378.19
#Mann= 7 ,-1 , 0
  4105.6      .1       0  4123.5     .05       0    4325      .1       0
  4789.6     .12       0  4994.2     .07       0  5000.2     .12       0
  5002.5      .1       0
Bank Sta=4963.7,5041.2
XS Rating Curve= 0 ,0
Exp/Cntr=0.3,0.1

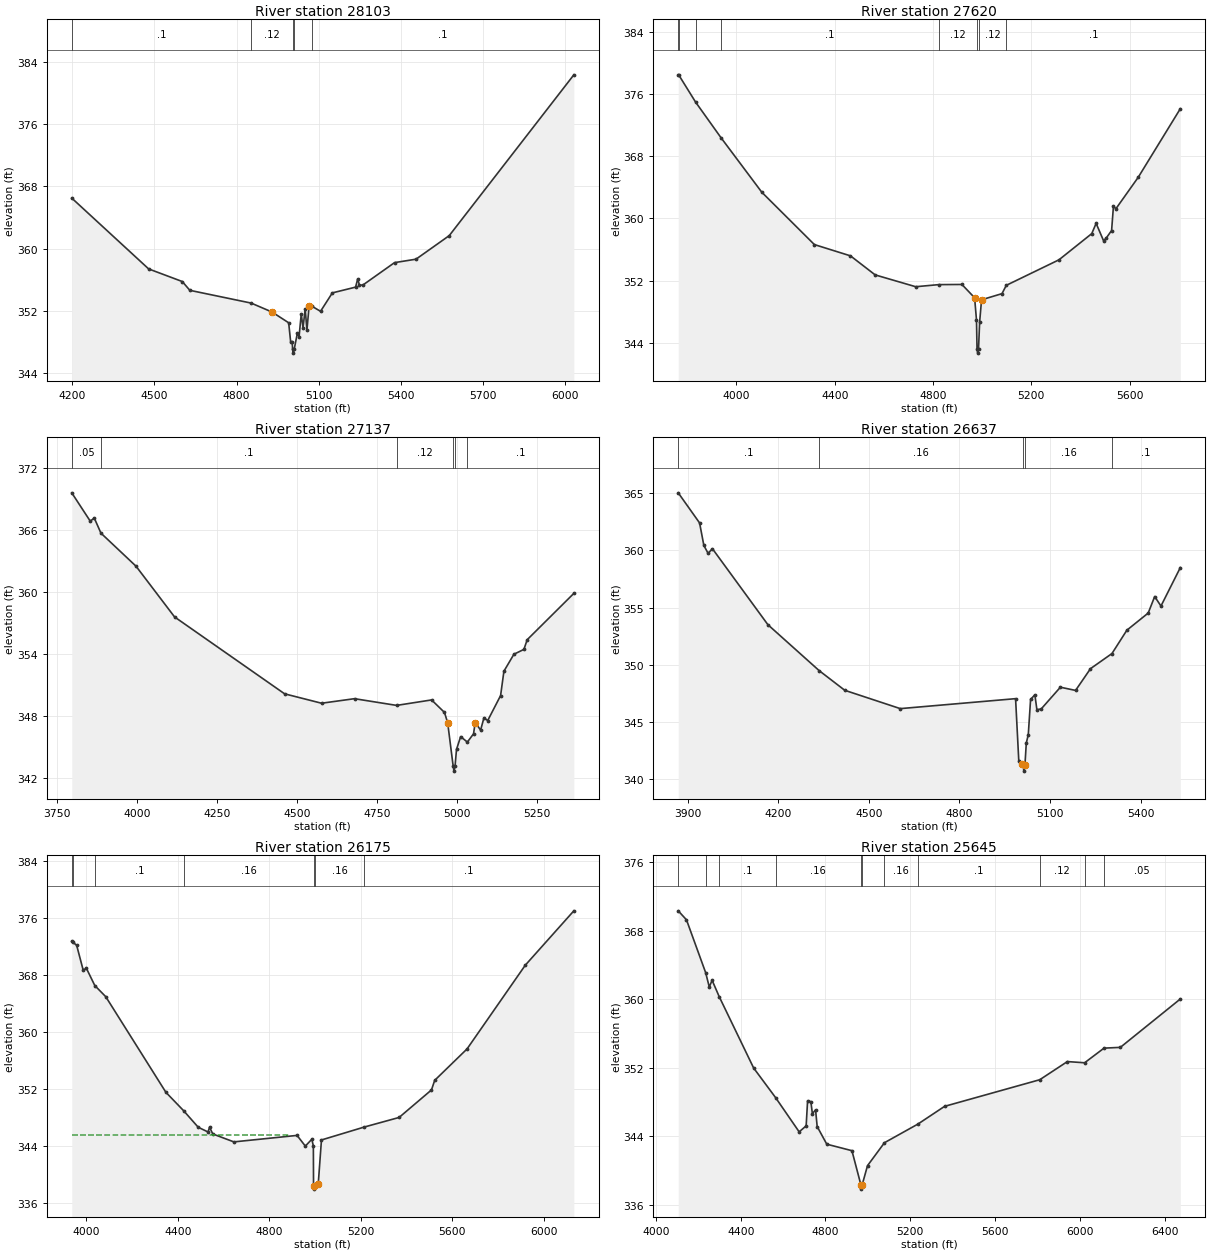
Type RM Length L Ch R = 1 ,28103   ,483,483,483
BEGIN DESCRIPTION:
BOTELLO CREEK 44.0
END DESCRIPTION:
XS GIS Cut Line= 3
      2207937.72     13194946.89      2207887.72     13194146.85
      2207237.71     13193346.84
#Sta/Elev= 30
  4198.4  366.48    4479  357.38  4601.7  355.76  4629.3  354.63  4853.2  352.99
  4929.9  351.83    4990  350.46  4997.5  347.93  5003.2  347.93  5004.2  347.06
  5006.9  346.56  5010.2  347.06  5021.6   349.1    5028  348.68  5035.9   351.6
  5042.4  349.83  5050.3  352.23  5056.7  349.52  5064.4  352.56  5075.8  352.57
  5106.3  351.93  5149.4   354.3  5234.2  355.04  5242.1  356.11  5248.5  355.25
  5262.9  355.36  5376.4  358.19  5454.7  358.63  5576.1  361.66  6030.8  382.32
#Mann= 5 ,-1 , 0
  4198.4      .1       0  4853.2     .12       0  5004.2     .07       0
  5010.2     .12       0  5075.8      .1       0
Bank Sta=4929.9,5064.4
XS Rating Curve= 0 ,0
Exp/Cntr=0.3,0.1

Type RM Length L Ch R = 1 ,27620   ,483,483,483
BEGIN DESCRIPTION:
BOTELLO CREEK 43.0
END DESCRIPTION:
XS GIS Cut Line= 3
      2208587.71     13195246.82      2208287.72     13194046.85
      2208187.72     13193246.88
#Sta/Elev= 30
  3763.1  378.46  3766.4  378.38  3833.8  374.95  3936.5   370.4  4103.2  363.36
  4317.1  356.63    4464  355.18  4564.5  352.73  4729.4  351.21  4823.5  351.48
  4917.5   351.5  4969.1  349.79  4976.8  346.93    4979  343.17  4981.7  342.67
    4985  343.17  4989.7   346.7  4997.4  349.53  5080.6  350.32  5098.1  351.39
  5312.4  354.67  5445.9  358.04  5463.6  359.36  5493.8  357.13  5503.9  357.43
  5526.6  358.44  5534.1  361.56  5544.2  361.24  5634.9  365.28  5806.2   374.1
#Mann= 8 ,-1 , 0
  3763.1     .05       0  3766.4      .1       0  3833.8     .05       0
  3936.5      .1       0  4823.5     .12       0    4979     .07       0
    4985     .12       0  5098.1      .1       0
Bank Sta=4969.1,4997.4
XS Rating Curve= 0 ,0
Exp/Cntr=0.3,0.1

Type RM Length L Ch R = 1 ,27137   ,500,500,500
BEGIN DESCRIPTION:
BOTELLO CREEK 42.0
END DESCRIPTION:
XS GIS Cut Line= 3
      2208787.72      13195046.9      2208687.72     13193846.85
      2208587.72     13193496.86
#Sta/Elev= 30
  3795.8  369.64  3853.5   366.9  3866.1   367.2  3886.9  365.74  3996.5  362.54
  4116.9  357.63  4460.6  350.19    4576  349.28  4678.9  349.72  4810.5  349.07
  4919.7   349.6  4959.9  348.39  4969.9  347.39    4987  343.21  4989.7  342.71
    4993  343.21  4997.5  344.81  5010.4  346.05  5031.4  345.52  5050.7  346.32
  5055.9  347.41  5072.8  346.68  5083.2  347.87  5094.9   347.6  5135.2  350.02
  5145.6  352.38  5176.8  354.02    5208  354.49  5218.4  355.43    5364  359.91
#Mann= 6 ,-1 , 0
  3795.8     .05       0  3886.9      .1       0  4810.5     .12       0
    4987     .07       0    4993     .12       0  5031.4      .1       0
Bank Sta=4969.9,5055.9
XS Rating Curve= 0 ,0
Exp/Cntr=0.3,0.1

Type RM Length L Ch R = 1 ,26637   ,462,462,462
BEGIN DESCRIPTION:
BOTELLO CREEK 41.0
END DESCRIPTION:
XS GIS Cut Line= 3
      2209987.74     13194646.88      2209187.72     13193846.85
      2208837.73     13193446.86
#Sta/Elev= 30
  3868.6  365.03  3939.3   362.4  3953.5  360.43  3967.6  359.74  3981.8  360.15
  4165.6  353.51  4335.3   349.5  4420.2  347.78    4604  346.18  4985.9  347.05
  4996.5  341.63  5007.1   341.3  5010.8  341.22  5013.5  340.72  5016.8  341.22
  5021.4  343.17    5028  343.91  5035.6  346.98  5049.8  347.39  5056.5  346.09
  5070.7  346.15  5134.3  348.05  5184.6  347.77    5234  349.67  5305.1  350.99
  5354.5  353.03  5425.2  354.53  5446.6  355.97  5467.4  355.14  5531.5   358.5
#Mann= 5 ,-1 , 0
  3868.6      .1       0  4335.3     .16       0  5010.8     .07       0
  5016.8     .16       0  5305.1      .1       0
Bank Sta=5007.1,5016.8
XS Rating Curve= 0 ,0
Exp/Cntr=0.3,0.1

Type RM Length L Ch R = 1 ,26175   ,530,530,530
BEGIN DESCRIPTION:
BOTELLO CREEK 40.0
END DESCRIPTION:
XS GIS Cut Line= 3
      2210287.71     13194496.84      2209587.72     13193696.85
       2208787.7     13192896.83
#Sta/Elev= 30
    3937  372.69  3941.8  372.55  3958.3  372.13  3986.8  368.65  4001.1  368.88
  4037.7  366.47  4085.5  364.91  4348.4  351.49  4426.3  348.89  4489.8  346.58
  4532.6  345.92  4539.2   346.6  4553.4  345.64  4645.5  344.53  4921.7  345.44
  4957.8  343.94  4986.2   344.9  4992.9  343.96  4993.7   338.4  4996.4   337.9
  4999.7   338.4  5014.1  338.56  5028.3   344.8    5215  346.61  5367.7  347.96
  5509.1  351.82  5523.3  353.17  5664.7  357.58  5919.2  369.33  6131.4  376.96
#Mann= 7 ,-1 , 0
    3937      .1       0  3941.8     .05       0  4037.7      .1       0
  4426.3     .16       0  4993.7     .07       0  4999.7     .16       0
    5215      .1       0
#XS Ineff= 2 , 0
       0 4886.73  345.48               0
Permanent Ineff=
       T       F
Bank Sta=4993.7,5014.1
XS Rating Curve= 0 ,0
Exp/Cntr=0.3,0.1

Type RM Length L Ch R = 1 ,25645   ,367,367,367
BEGIN DESCRIPTION:
BOTELLO CREEK 39.0
END DESCRIPTION:
XS GIS Cut Line= 4
      2210437.63     13194440.91      2209899.44     13193321.13
      2209968.88     13192730.85      2210237.66     13192271.33
#Sta/Elev= 30
  4105.3  370.31  4144.2  369.26  4234.8  363.08  4251.8  361.41  4265.1   362.2
  4298.3   360.3  4461.1  351.95  4564.7  348.49  4675.9  344.49  4708.9  345.19
  4715.7  348.13  4731.1  348.01  4738.3  346.62  4753.3  347.06  4760.9  345.11
  4806.2  343.05  4924.9  342.29  4967.2   338.3    4970   337.8  4973.2   338.3
  4998.4  340.54  5078.3  343.22  5236.3   345.4  5362.1  347.47  5811.2  350.58
  5941.5   352.7  6022.9  352.56  6114.4  354.27  6191.5  354.36  6474.4  360.01
#Mann= 11 ,-1 , 0
  4105.3      .1       0  4234.8     .05       0  4298.3      .1       0
  4564.7     .16       0  4967.2     .07       0  4973.2     .16       0
  5078.3     .16       0  5236.3      .1       0  5811.2     .12       0
  6022.9      .1       0  6114.4     .05       0
#XS Ineff= 1 ,-1
 4420.92 4720.66  347.98
Permanent Ineff=
       T
Bank Sta=4967.2,4973.2
XS Rating Curve= 0 ,0
Exp/Cntr=0.3,0.1

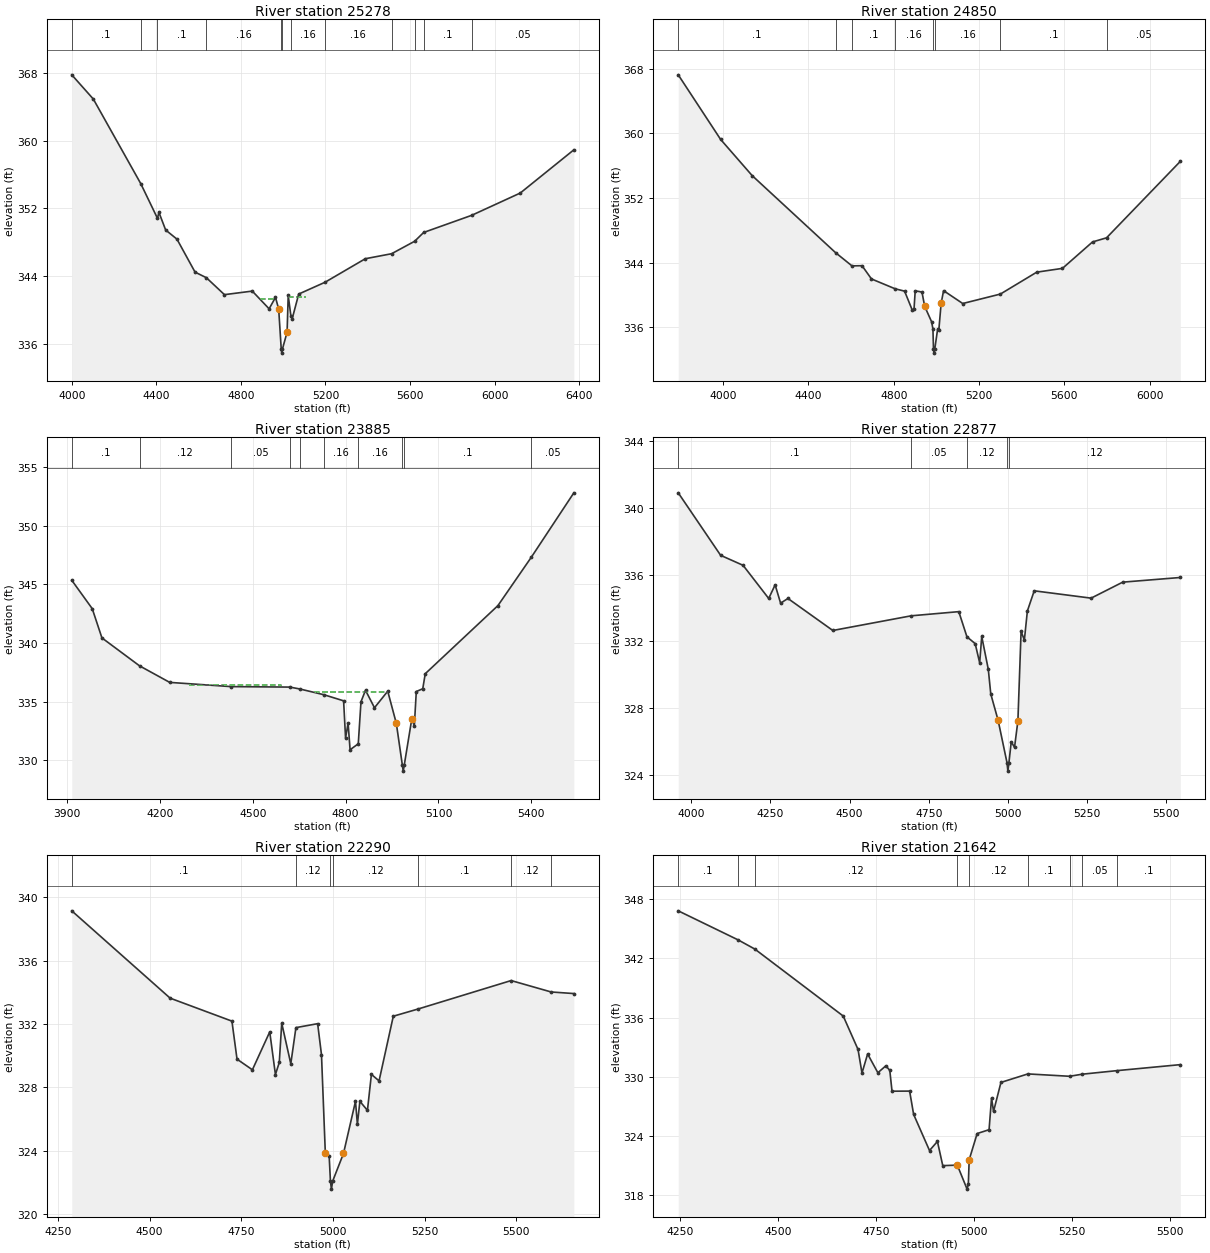
Type RM Length L Ch R = 1 ,25278   ,428,428,428
BEGIN DESCRIPTION:
BOTELLO CREEK 38.0
END DESCRIPTION:
XS GIS Cut Line= 3
      2210715.41     13194432.23      2210125.13     13192878.42
      2210402.15     13192220.52
#Sta/Elev= 30
  3999.4  367.76  4101.4   364.9  4325.7  354.93  4405.1  350.82  4411.7  351.54
  4443.7  349.45  4497.2  348.37  4582.8  344.48  4636.3  343.82  4721.9  341.82
  4853.7  342.24  4933.3  340.15  4963.5   341.5  4978.6  340.12  4990.6  335.42
  4993.3  334.92  4996.6  335.42  5018.4   337.4  5023.7  341.73  5036.5  339.29
  5042.8     339  5073.3  341.89  5197.7  343.28  5388.6  346.06    5513  346.65
    5622  348.12  5664.7  349.16  5891.8  351.18  6121.8  353.81  6375.4  358.91
#Mann= 12 ,-1 , 0
  3999.4      .1       0  4325.7     .05       0  4405.1      .1       0
  4636.3     .16       0  4990.6     .07       0  4996.6     .16       0
  5036.5     .16       0  5197.7     .16       0    5513      .1       0
    5622     .12       0  5664.7      .1       0  5891.8     .05       0
#XS Ineff= 3 ,-1
 4647.55 4852.31  342.23 4891.26 4956.91  341.34 5024.79 5109.37  341.53
Permanent Ineff=
       T       T       T
Bank Sta=4978.6,5018.4
XS Rating Curve= 0 ,0
Exp/Cntr=0.3,0.1

Type RM Length L Ch R = 1 ,24850   ,965,965,965
BEGIN DESCRIPTION:
BOTELLO CREEK 37.0
END DESCRIPTION:
XS GIS Cut Line= 3
      2211279.63     13194423.52       2210646.4     13193192.69
       2210541.8     13192227.41
#Sta/Elev= 30
  3789.2  367.24  3987.9  359.25  4135.9  354.77  4526.9  345.24    4604   343.6
  4651.3  343.62  4695.6  341.98  4806.8  340.76  4850.9  340.47  4887.5  338.09
  4895.2  338.24  4900.8  340.51  4932.5  340.36  4945.2  338.59  4977.5  336.69
  4983.9   335.8  4986.5   333.3  4989.3   332.8  4992.5   333.3  5006.1   335.8
  5011.7  335.69  5022.5  338.99  5033.9  340.53  5123.7  338.94  5300.4  340.11
  5470.9  342.82  5591.6  343.29  5732.5  346.56  5798.3  347.07  6144.3  356.53
#Mann= 8 ,-1 , 0
  3789.2      .1       0  4526.9     .05       0    4604      .1       0
  4806.8     .16       0  4986.5     .07       0  4992.5     .16       0
  5300.4      .1       0  5798.3     .05       0
#XS Ineff= 2 ,-1
 4781.89 4904.34  340.48 5034.44 5510.84  340.44
Permanent Ineff=
       T       T
Bank Sta=4945.2,5022.5
XS Rating Curve= 0 ,0
Exp/Cntr=0.3,0.1

Type RM Length L Ch R = 1 ,23885   ,1008,1008,1008
BEGIN DESCRIPTION:
BOTELLO CREEK 36.0
END DESCRIPTION:
XS GIS Cut Line= 3
       2211688.1     13193630.26      2211528.37     13193095.49
      2210882.61     13192248.37
#Sta/Elev= 30
  3914.4  345.35  3980.6  342.93  4011.9  340.44  4133.5  338.06  4231.1  336.65
  4429.5  336.29  4619.5  336.25  4651.5  336.09  4729.4   335.6  4793.3  335.08
  4799.6  331.92  4807.9  333.16  4814.2  330.91  4840.7  331.42  4849.5     335
  4864.1  335.98  4893.1  334.49    4936   335.9  4963.8  333.15  4983.3  329.59
  4986.1  329.09  4989.3  329.59  5013.7  333.53    5022  332.97  5028.3  335.87
  5049.2  336.11  5057.3  337.39  5292.2  343.19  5400.1  347.31  5537.7   352.8
#Mann= 10 ,-1 , 0
  3914.4      .1       0  4133.5     .12       0  4429.5     .05       0
  4619.5     .12       0  4651.5      .1       0  4729.4     .16       0
  4840.7     .16       0  4983.3     .07       0  4989.3      .1       0
  5400.1     .05       0
#XS Ineff= 2 ,-1
 4292.44 4591.05  336.47    4702 4932.13  335.85
Permanent Ineff=
       T       T
Bank Sta=4963.8,5013.7
XS Rating Curve= 0 ,0
Exp/Cntr=0.3,0.1

Type RM Length L Ch R = 1 ,22877   ,587,587,587
BEGIN DESCRIPTION:
BOTELLO CREEK 35.0
END DESCRIPTION:
XS GIS Cut Line= 3
      2211924.19     13193519.14      2212035.31     13192782.99
      2211820.22     13191971.19
#Sta/Elev= 30
  3959.5  340.92  4093.3  337.17  4164.1  336.57    4245  334.58  4265.2   335.4
  4282.5   334.3  4305.7  334.58  4447.3  332.66  4694.5  333.54  4844.8  333.79
  4870.5  332.28  4896.5  331.87  4910.7  330.72  4917.2   332.3  4937.9  330.33
  4945.7  328.85    4969  327.26    4997  324.72  4999.7  324.22    5003  324.72
  5010.3  325.98  5020.7  325.65  5031.3  327.23  5041.4  332.62  5051.7  332.08
  5061.2  333.83  5082.8  335.04  5262.3   334.6  5362.1  335.56  5543.8  335.84
#Mann= 5 ,-1 , 0
  3959.5      .1       0  4694.5     .05       0  4870.5     .12       0
    4997     .07       0    5003     .12       0
Bank Sta=4969,5031.3
XS Rating Curve= 0 ,0
Exp/Cntr=0.3,0.1

Type RM Length L Ch R = 1 ,22290   ,648,648,648
BEGIN DESCRIPTION:
BOTELLO CREEK 34.0
END DESCRIPTION:
XS GIS Cut Line= 3
      2212153.37     13193477.44      2212445.03     13192532.99
      2212272.09     13192194.02
#Sta/Elev= 30
  4287.7  339.14  4555.9  333.63  4724.4  332.18  4738.3  329.78  4780.2  329.11
  4827.5   331.5    4843  328.81  4853.5  329.57  4860.2  332.05  4884.9  329.49
  4898.9  331.77  4958.1  332.02  4968.6  330.06  4979.1  323.83  4989.5  323.69
    4993  322.08  4995.7  321.58    4999  322.08  5028.6  323.83  5061.3  327.12
  5066.5  325.67  5073.3  327.12  5093.9  326.55  5104.7  328.82  5125.6  328.41
  5164.4  332.49  5232.7  332.95  5485.7  334.74  5594.8  334.02  5656.7  333.92
#Mann= 7 ,-1 , 0
  4287.7      .1       0  4898.9     .12       0    4993     .07       0
    4999     .12       0  5232.7      .1       0  5485.7     .12       0
  5594.8      .1       0
Bank Sta=4979.1,5028.6
XS Rating Curve= 0 ,0
Exp/Cntr=0.3,0.1

Type RM Length L Ch R = 1 ,21642   ,521,521,521
BEGIN DESCRIPTION:
BOTELLO CREEK 33.0
END DESCRIPTION:
XS GIS Cut Line= 3
      2212826.98     13193699.67      2212972.81     13192782.99
      2212655.08     13192631.04
#Sta/Elev= 30
  4245.6  346.81  4398.6  343.86  4440.8  342.94  4666.4  336.15  4704.1  332.77
  4714.2  330.38  4728.6  332.31  4754.7  330.41    4775  331.11  4785.1  330.65
  4790.8  328.54  4835.7  328.55  4845.9  326.19  4886.4  322.53  4906.6  323.45
  4920.2     321  4957.3  321.05  4982.2  318.62  4985.4  319.12  4987.6   321.6
  5007.9  324.25  5038.3  324.64  5044.6  327.85  5049.7  326.49  5068.6  329.43
  5137.3  330.29  5243.8  330.05  5275.4  330.26  5363.9  330.62    5526  331.23
#Mann= 9 ,-1 , 0
  4245.6      .1       0  4398.6     .16       0  4440.8     .12       0
  4957.3     .07       0  4987.6     .12       0  5137.3      .1       0
  5243.8     .12       0  5275.4     .05       0  5363.9      .1       0
Bank Sta=4957.3,4987.6
XS Rating Curve= 0 ,0
Exp/Cntr=0.3,0.1