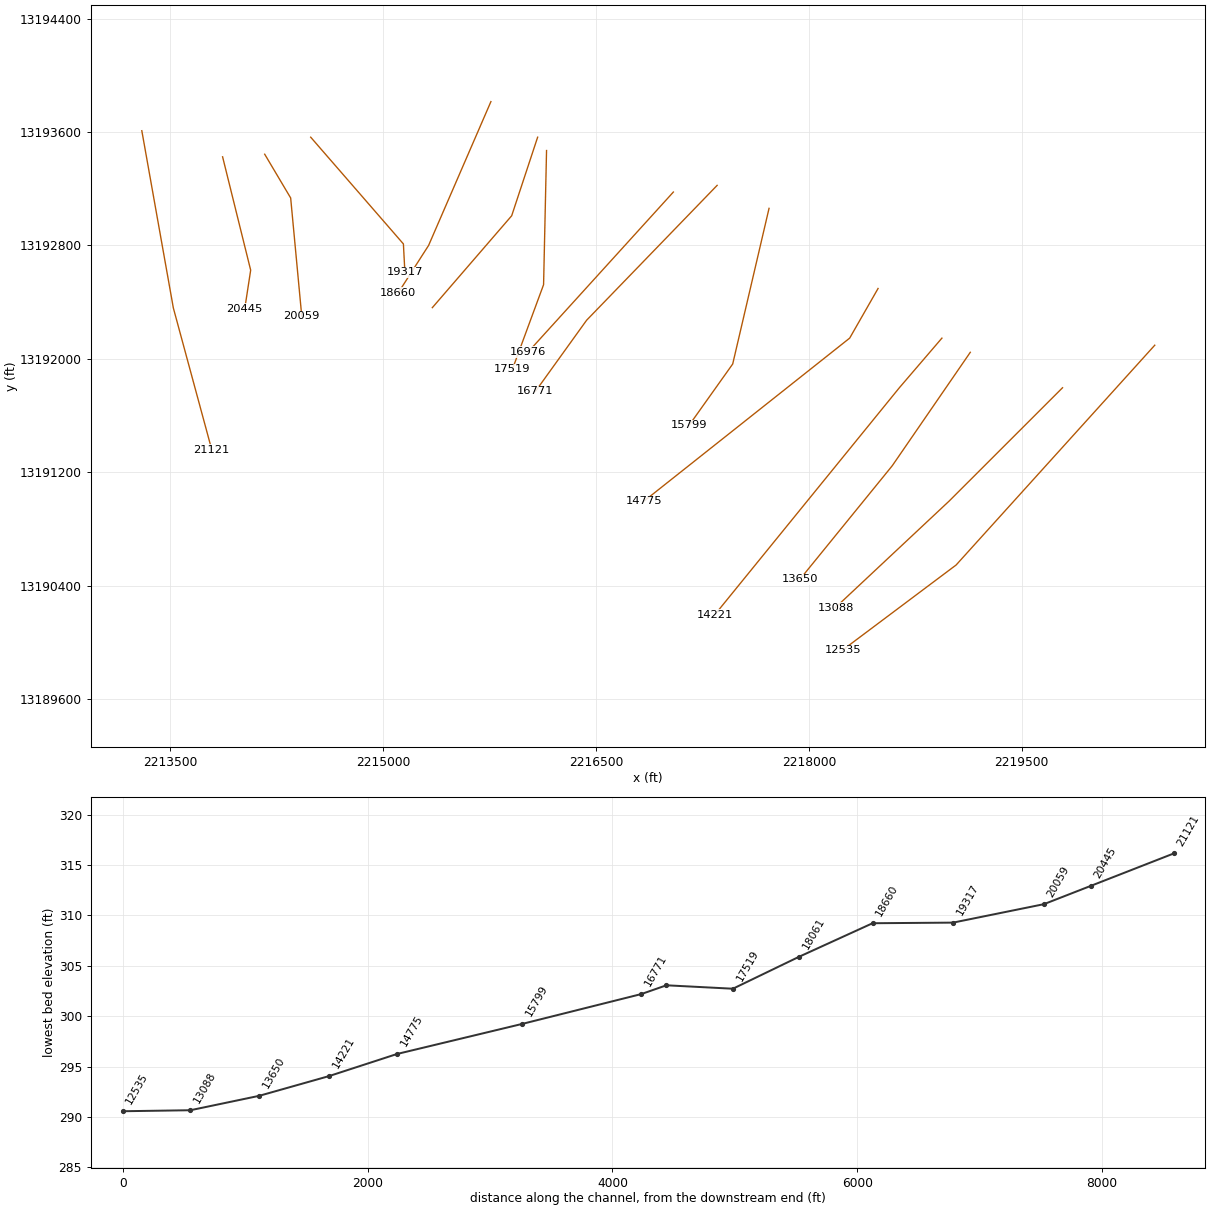
HEC-RAS study BOTELLO CREEK.prj: BOTELLO CREEK Base Level Engineering

--- BOTELLO CREEK.g01 (geometry) --- (continued)

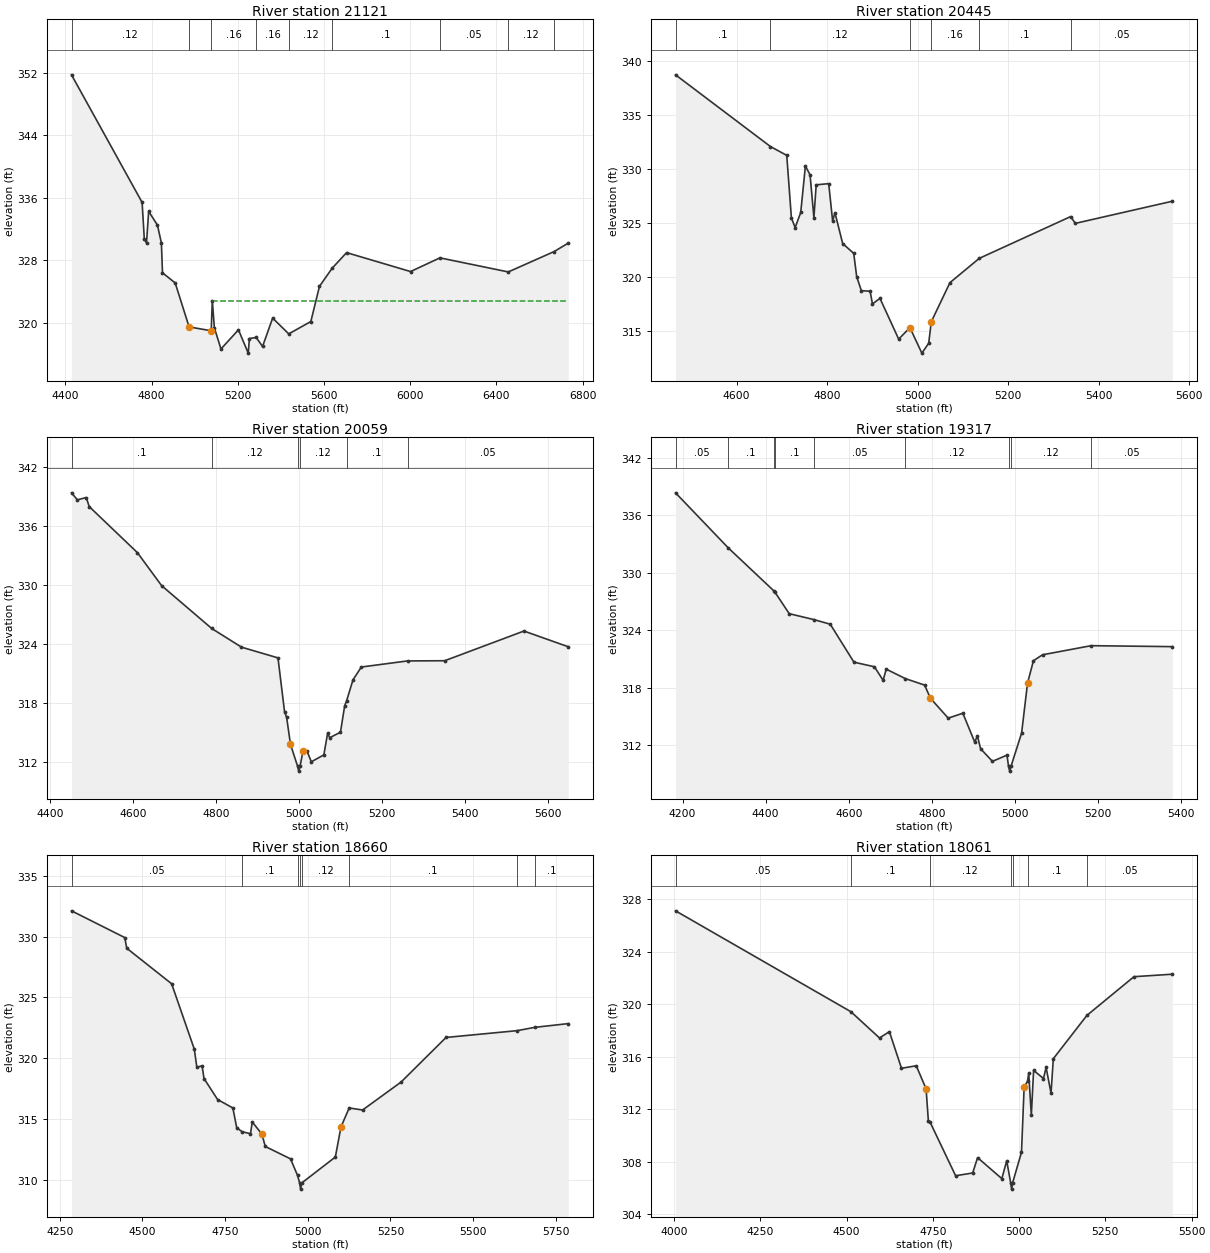
Type RM Length L Ch R = 1 ,21121   ,676,676,676
BEGIN DESCRIPTION:
BOTELLO CREEK 32.0
END DESCRIPTION:
XS GIS Cut Line= 3
      2213299.21     13193609.34      2213521.42     13192359.38
      2213791.92     13191360.62
#Sta/Elev= 30
  4428.7  351.73  4756.2  335.42  4766.4  330.73  4776.6  330.23  4786.6  334.27
  4827.3  332.52  4845.6  330.23  4850.7  326.42  4909.7  325.12  4974.1   319.5
  5076.7  319.01  5081.8  322.86  5091.4  319.38  5121.9  316.68  5203.1  319.13
  5248.5  316.15  5253.9  318.02  5285.4  318.15  5314.9     317  5361.7  320.63
  5436.4  318.61  5538.8  320.19  5578.9  324.69  5637.6     327  5704.6     329
  6001.3  326.58  6137.7  328.33  6454.7  326.53  6667.7  329.14    6733  330.22
#Mann= 9 ,-1 , 0
  4428.7     .12       0  4974.1     .07       0  5076.7     .16       0
  5285.4     .16       0  5436.4     .12       0  5637.6      .1       0
  6137.7     .05       0  6454.7     .12       0  6667.7      .1       0
#XS Ineff= 2 , 0
       0                 5081.87       0  322.86
Permanent Ineff=
       F       T
Bank Sta=4974.1,5076.7
XS Rating Curve= 0 ,0
Exp/Cntr=0.3,0.1

Type RM Length L Ch R = 1 ,20445   ,386,386,386
BEGIN DESCRIPTION:
BOTELLO CREEK 31.0
END DESCRIPTION:
XS GIS Cut Line= 3
      2213868.47     13193425.37      2214066.39     13192625.88
      2214024.73     13192355.09
#Sta/Elev= 30
  4465.1  338.72  4674.7  332.08  4710.8  331.26  4721.1  325.46  4729.4  324.57
  4741.7  325.97    4752  330.27  4762.3  329.46  4770.8  325.49  4775.9  328.53
  4803.5  328.64  4812.2  325.17  4817.3  325.95  4834.4  323.09  4858.8  322.18
  4865.3  320.03  4875.6  318.73    4895  318.67  4900.2   317.5  4916.8  318.01
  4958.1  314.24    4983   315.3  5009.3  312.94  5024.4  313.85  5030.2  315.85
  5071.4  319.47  5136.2  321.72  5338.1  325.59  5348.4  324.96  5562.7  327.01
#Mann= 6 ,-1 , 0
  4465.1      .1       0  4674.7     .12       0    4983     .07       0
  5030.2     .16       0  5136.2      .1       0  5338.1     .05       0
Bank Sta=4983,5030.2
XS Rating Curve= 0 ,0
Exp/Cntr=0.3,0.1

Type RM Length L Ch R = 1 ,20059   ,742,742,742
BEGIN DESCRIPTION:
BOTELLO CREEK 30.0
END DESCRIPTION:
XS GIS Cut Line= 3
      2214165.26     13193443.55       2214348.2     13193135.17
      2214426.46     13192300.39
#Sta/Elev= 30
  4452.3  339.42  4466.4  338.71  4487.8  338.94    4495  338.02  4611.2  333.33
  4669.4  329.98  4790.2  325.62  4861.9  323.72  4949.8  322.63  4965.6  317.16
  4970.7  316.57  4979.9  313.84    4997  311.61  4999.7  311.11    5003  311.61
    5010  313.13  5020.1  313.11  5030.1  312.06  5060.3  312.76  5069.4  314.96
  5074.5  314.51  5100.4  315.07  5110.5  317.76  5114.9  318.23  5130.6   320.4
  5150.7   321.7    5262  322.32  5351.5  322.34  5542.4  325.36  5649.3  323.76
#Mann= 6 ,-1 , 0
  4452.3      .1       0  4790.2     .12       0    4997     .07       0
    5003     .12       0  5114.9      .1       0    5262     .05       0
Bank Sta=4979.9,5010
XS Rating Curve= 0 ,0
Exp/Cntr=0.3,0.1

Type RM Length L Ch R = 1 ,19317   ,657,657,657
BEGIN DESCRIPTION:
BOTELLO CREEK 29.0
END DESCRIPTION:
XS GIS Cut Line= 3
      2214489.34     13193563.75      2215142.67     13192811.11
      2215153.12     13192612.54
#Sta/Elev= 30
  4183.1  338.32  4310.1  332.57  4419.7  328.09  4421.3  328.02  4456.7  325.71
  4516.3  325.09  4555.4  324.61  4612.4  320.65  4661.7  320.17  4682.6  318.76
  4690.2  319.92  4736.4  318.93  4782.4  318.26  4796.6  316.88  4839.3  314.81
  4874.5  315.32    4903  312.32  4909.6  312.95  4917.2  311.62  4945.7   310.3
  4980.8  310.95  4984.4  309.78  4987.2  309.28  4990.4  309.78  5015.9  313.25
  5030.2  318.47  5044.4   320.8  5066.2  321.42  5183.3  322.37  5378.6  322.27
#Mann= 9 ,-1 , 0
  4183.1     .05       0  4310.1      .1       0  4419.7     .05       0
  4421.3      .1       0  4516.3     .05       0  4736.4     .12       0
  4984.4     .07       0  4990.4     .12       0  5183.3     .05       0
Bank Sta=4796.6,5030.2
XS Rating Curve= 0 ,0
Exp/Cntr=0.3,0.1

Type RM Length L Ch R = 1 ,18660   ,599,599,599
BEGIN DESCRIPTION:
BOTELLO CREEK 28.0
END DESCRIPTION:
XS GIS Cut Line= 3
      2215759.41     13193814.61      2215320.38     13192800.66
      2215106.07     13192466.14
#Sta/Elev= 30
  4285.6  332.12  4446.6  329.92  4452.7  329.04  4588.3  326.12  4656.9  320.74
  4664.6  319.25  4680.4  319.37  4686.3  318.32  4727.4  316.59  4773.5   315.9
  4785.2  314.27  4801.7  313.94  4826.8  313.78  4832.2  314.74  4861.1  313.76
  4871.6  312.73  4947.9  311.71  4969.1  310.35  4975.5  309.72  4978.3  309.22
  4981.5  309.72  5083.4  311.86  5100.4  314.33  5125.3   315.9  5165.8  315.73
  5282.1  318.03  5418.1   321.7  5633.1  322.26  5685.8  322.53  5787.8  322.84
#Mann= 8 ,-1 , 0
  4285.6     .05       0  4801.7      .1       0  4969.1     .12       0
  4975.5     .07       0  4981.5     .12       0  5125.3      .1       0
  5633.1     .05       0  5685.8      .1       0
Bank Sta=4861.1,5100.4
XS Rating Curve= 0 ,0
Exp/Cntr=0.3,0.1

Type RM Length L Ch R = 1 ,18061   ,542,542,542
BEGIN DESCRIPTION:
BOTELLO CREEK 27.0
END DESCRIPTION:
XS GIS Cut Line= 3
      2216088.73     13193563.81      2215905.78     13193009.73
      2215346.62     13192361.74
#Sta/Elev= 30
  4004.6  327.11  4512.8  319.42  4595.6  317.42  4624.2   317.9  4659.3  315.11
  4702.1   315.3  4730.6  313.54  4737.2  311.08  4742.2     311  4816.1  306.92
  4865.5  307.13  4879.8   308.3    4950   306.7  4964.2  308.06  4975.5   306.4
  4978.3   305.9  4981.5   306.4    5007  308.71  5014.6  313.67  5024.5  314.12
  5027.9  314.74  5035.5  311.53  5042.1  314.95  5070.7  314.33  5078.3  315.17
  5092.6  313.21  5099.2  315.84  5196.5  319.14  5332.8  322.09    5444  322.28
#Mann= 7 ,-1 , 0
  4004.6     .05       0  4512.8      .1       0  4742.2     .12       0
  4975.5     .07       0  4981.5     .12       0  5024.5      .1       0
  5196.5     .05       0
Bank Sta=4730.6,5014.6
XS Rating Curve= 0 ,0
Exp/Cntr=0.3,0.1

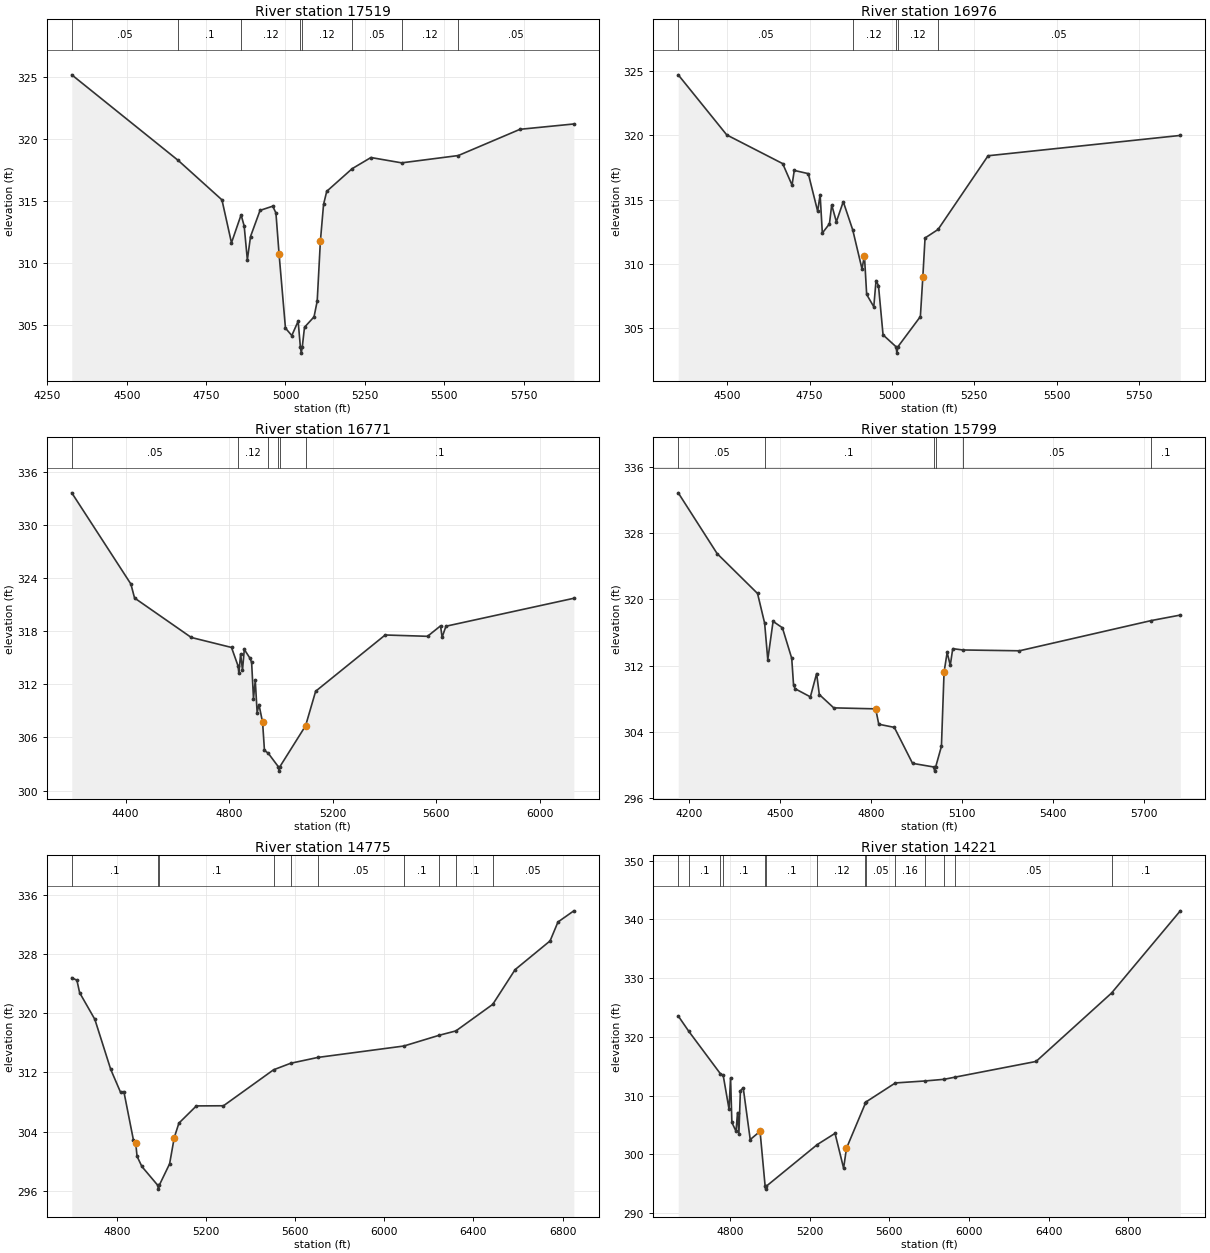
Type RM Length L Ch R = 1 ,17519   ,543,543,543
BEGIN DESCRIPTION:
BOTELLO CREEK 26.0
END DESCRIPTION:
XS GIS Cut Line= 3
      2216151.44     13193469.69      2216130.53     13192523.64
        2215911.     13191927.78
#Sta/Elev= 30
    4327   325.2  4662.5  318.28    4800   315.1    4830  311.63  4860.3  313.89
    4870  312.99    4880  310.26    4890  312.14    4920  314.25    4960  314.59
    4970  314.04    4980  310.69    5000  304.74    5020  304.14    5040   305.3
    5047  303.22  5049.8  302.72    5053  303.22    5060  304.81    5090  305.65
    5100  306.92    5110  311.76    5120  314.73    5130  315.79  5210.1  317.62
  5269.2  318.52  5365.9  318.09  5544.4  318.68  5738.8   320.8  5908.3  321.23
#Mann= 8 ,-1 , 0
    4327     .05       0  4662.5      .1       0  4860.3     .12       0
    5047     .07       0    5053     .12       0  5210.1     .05       0
  5365.9     .12       0  5544.4     .05       0
Bank Sta=4980,5110
XS Rating Curve= 0 ,0
Exp/Cntr=0.3,0.1

Type RM Length L Ch R = 1 ,16976   ,205,205,205
BEGIN DESCRIPTION:
BOTELLO CREEK 25.0
END DESCRIPTION:
XS GIS Cut Line= 2
      2217045.19     13193176.96      2216021.75     13192049.09
#Sta/Elev= 30
  4351.7  324.69  4498.9  320.02  4668.5  317.79  4696.9  316.12  4703.7  317.26
  4746.2  317.01  4774.6  314.09  4782.1  315.38  4788.8  312.39  4810.4  313.11
  4817.2  314.58  4831.4  313.27  4852.3  314.83  4881.1  312.63  4909.1  309.61
  4916.5  310.63  4923.3  307.62  4944.9  306.66  4951.7   308.7  4959.1  308.31
    4973  304.48  5012.2  303.56    5015  303.06  5018.2  303.56  5086.2   305.9
  5093.6  308.95  5100.4  312.01  5139.8  312.67  5291.6   318.4  5874.7  319.98
#Mann= 5 ,-1 , 0
  4351.7     .05       0  4881.1     .12       0  5012.2     .07       0
  5018.2     .12       0  5139.8     .05       0
Bank Sta=4916.5,5093.6
XS Rating Curve= 0 ,0
Exp/Cntr=0.3,0.1

Type RM Length L Ch R = 1 ,16771   ,972,972,972
BEGIN DESCRIPTION:
BOTELLO CREEK 24.0
END DESCRIPTION:
XS GIS Cut Line= 3
      2217353.62     13193224.05      2216433.68     13192272.76
      2216073.37     13191771.45
#Sta/Elev= 30
  4191.6  333.65  4420.1  323.34  4434.3  321.76  4653.5   317.3  4809.1  316.17
  4834.3  314.08  4837.4  313.26  4844.3  315.43  4851.5   313.6  4858.5  315.95
  4879.8  314.98  4886.8  314.49    4894   310.4  4900.9  312.44  4908.1  308.81
  4915.1  309.72  4929.2  307.71  4936.4  304.54  4951.1  304.21    4990  302.69
  4992.8  302.19    4996  302.69  5095.4  307.32  5134.3  311.22  5403.1  317.58
  5566.7  317.43    5617  318.61  5623.1  317.32  5637.9  318.57  6132.3  321.73
#Mann= 6 ,-1 , 0
  4191.6     .05       0  4834.3     .12       0  4951.1     .05       0
    4990     .04       0    4996     .05       0  5095.4      .1       0
Bank Sta=4929.2,5095.4
XS Rating Curve= 0 ,0
Exp/Cntr=0.3,0.1

Type RM Length L Ch R = 1 ,15799   ,1024,1024,1024
BEGIN DESCRIPTION:
BOTELLO CREEK 23.0
END DESCRIPTION:
XS GIS Cut Line= 3
      2217719.46     13193061.96      2217463.36     13191964.38
      2217155.46     13191531.23
#Sta/Elev= 30
    4163  332.88  4291.5  325.53    4425  320.71  4448.4  317.12  4458.8  312.71
  4476.3  317.34  4507.1  316.56  4537.9  312.87  4543.9  309.66    4549  309.19
  4599.5  308.21  4620.1  311.03    4629  308.49  4676.7  306.88  4815.2  306.76
  4825.4   304.9  4876.8  304.52    4937  300.17  5007.3  299.73    5010  299.23
  5013.3  299.73  5032.4  302.23  5041.1   311.2  5051.3  313.58  5061.6  312.02
  5069.8  314.04  5102.9  313.88  5290.1  313.78  5726.2  317.44  5821.5   318.1
#Mann= 6 ,-1 , 0
    4163     .05       0  4448.4      .1       0  5007.3     .07       0
  5013.3      .1       0  5102.9     .05       0  5726.2      .1       0
Bank Sta=4815.2,5041.1
XS Rating Curve= 0 ,0
Exp/Cntr=0.3,0.1

Type RM Length L Ch R = 1 ,14775   ,554,554,554
BEGIN DESCRIPTION:
BOTELLO CREEK 22.0
END DESCRIPTION:
XS GIS Cut Line= 3
      2218487.71     13192496.84      2218287.72     13192146.86
       2216837.7     13190996.84
#Sta/Elev= 30
  4596.9  324.79  4619.9  324.46  4632.2  322.77  4700.5  319.17  4771.8  312.41
  4815.7  309.33  4830.8  309.41    4874  302.82  4884.1  302.44  4889.9  300.68
  4911.5   299.3  4983.3  296.74  4986.1  296.24  4989.3  296.74  5036.1  299.66
  5056.9  303.19  5077.7  305.15  5156.2  307.48    5278   307.5  5502.8  312.36
  5579.5  313.24  5701.9  314.03  6087.7  315.57  6247.3  317.03  6321.3  317.61
  6486.7   321.2  6587.1  325.89  6744.1  329.77  6779.4  332.32  6850.7  333.83
#Mann= 10 ,-1 , 0
  4596.9      .1       0  4983.3     .07       0  4989.3      .1       0
  5502.8     .05       0  5579.5      .1       0  5701.9     .05       0
  6087.7      .1       0  6247.3     .16       0  6321.3      .1       0
  6486.7     .05       0
Bank Sta=4884.1,5056.9
XS Rating Curve= 0 ,0
Exp/Cntr=0.3,0.1

Type RM Length L Ch R = 1 ,14221   ,571,571,571
BEGIN DESCRIPTION:
BOTELLO CREEK 21.0
END DESCRIPTION:
XS GIS Cut Line= 3
      2218937.74     13192146.87      2218637.72     13191796.85
      2217337.69     13190196.82
#Sta/Elev= 30
    4539  323.55  4591.5  320.96    4750  313.74  4764.8  313.45  4794.2  307.68
  4801.9  313.02  4808.5  305.41  4829.3  303.91    4837   307.1  4843.6  303.37
  4851.3   310.8  4865.5  311.31  4900.7  302.49  4950.1   303.9  4975.6  294.55
  4978.3  294.05  4981.6  294.55  5237.9  301.65  5326.8  303.55  5369.9  297.62
  5384.3  301.01  5479.8  308.72  5483.6  308.93  5629.9  312.14    5780  312.48
  5875.2  312.76  5930.1  313.13  6336.8   315.8    6716  327.45  7061.6  341.46
#Mann= 14 ,-1 , 0
    4539     .05       0  4591.5      .1       0    4750     .12       0
  4764.8      .1       0  4975.6     .07       0  4981.6      .1       0
  5237.9     .12       0  5479.8      .1       0  5483.6     .05       0
  5629.9     .16       0    5780     .05       0  5875.2      .1       0
  5930.1     .05       0    6716      .1       0
Bank Sta=4950.1,5384.3
XS Rating Curve= 0 ,0
Exp/Cntr=0.3,0.1

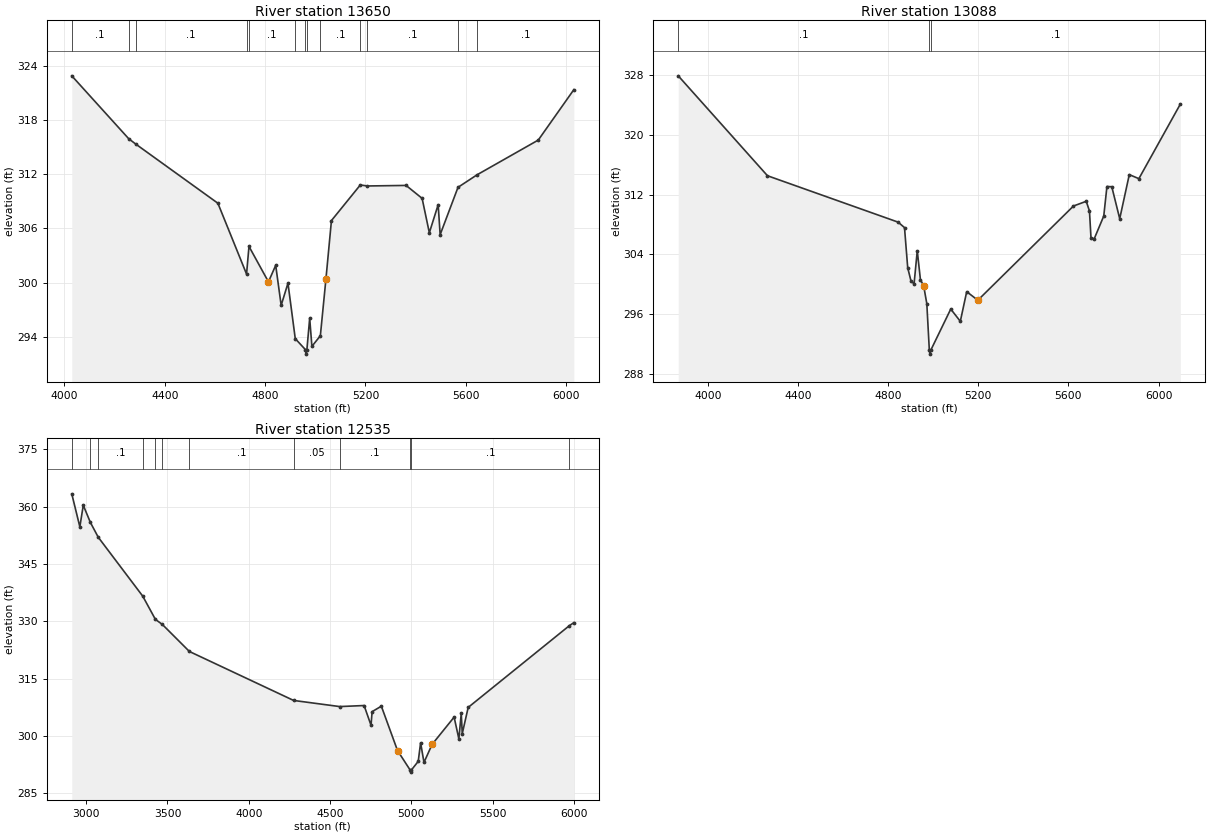
Type RM Length L Ch R = 1 ,13650   ,562,562,562
BEGIN DESCRIPTION:
BOTELLO CREEK 20.0
END DESCRIPTION:
XS GIS Cut Line= 3
      2219137.71     13192046.83      2218587.72     13191246.85
      2217937.71     13190446.84
#Sta/Elev= 30
  4029.2  322.89  4256.2  315.93  4284.1  315.34  4611.7  308.79    4726  300.95
  4735.7  304.01  4813.3  300.09  4842.2  301.92    4864  297.49  4891.1  299.94
  4920.2   293.8  4960.6  292.59  4963.3  292.09  4966.6  292.59  4977.7  296.06
  4986.5  292.95  5020.2  294.12  5042.4  300.38  5064.4  306.87  5179.5  310.81
  5207.7   310.7    5362  310.76  5425.9  309.33  5454.7  305.52  5489.9  308.63
  5497.8  305.31    5569  310.55  5645.2  311.94    5889  315.78  6030.8  321.36
#Mann= 13 ,-1 , 0
  4029.2      .1       0  4256.2     .12       0  4284.1      .1       0
    4726     .12       0  4735.7      .1       0  4920.2     .12       0
  4960.6     .07       0  4966.6     .12       0  5020.2      .1       0
  5179.5     .05       0  5207.7      .1       0    5569     .16       0
  5645.2      .1       0
Bank Sta=4813.3,5042.4
XS Rating Curve= 0 ,0
Exp/Cntr=0.3,0.1

Type RM Length L Ch R = 1 ,13088   ,553,553,553
BEGIN DESCRIPTION:
BOTELLO CREEK 19.0
END DESCRIPTION:
XS GIS Cut Line= 3
      2219787.74     13191796.88      2218987.72     13190996.86
      2218187.71     13190246.85
#Sta/Elev= 30
  3868.6   327.9  4264.6  314.53  4844.4  308.32  4872.7  307.59  4886.9  302.22
    4901   300.5  4915.1  300.05  4929.3  304.49  4943.4  300.61  4957.6  299.82
  4971.7  297.41  4982.9  291.16  4985.6  290.66  4988.9  291.16  5077.9  296.69
  5120.4  295.05  5148.7  299.02  5198.1  297.87  5622.5  310.48  5679.2  311.11
  5693.4  309.82  5700.2  306.25  5714.4  306.08  5756.9  309.14    5771  313.09
  5792.5  313.06  5827.7  308.78  5870.2  314.68  5912.7  314.14  6096.6  324.11
#Mann= 3 ,-1 , 0
  3868.6      .1       0  4982.9     .07       0  4988.9      .1       0
Bank Sta=4957.6,5198.1
XS Rating Curve= 0 ,0
Exp/Cntr=0.3,0.1

Type RM Length L Ch R = 1 ,12535   ,592,592,592
BEGIN DESCRIPTION:
BOTELLO CREEK 18.0
END DESCRIPTION:
XS GIS Cut Line= 3
      2220437.75     13192096.88      2219037.72     13190546.85
      2218237.72     13189946.86
#Sta/Elev= 30
  2911.3  363.32    2961  354.68    2982  360.34  3025.7  355.85  3074.2  351.97
    3348  336.56  3425.7   330.5  3468.7  329.16    3635   322.1  4276.1   309.3
  4559.5   307.7  4709.7  307.97  4752.3  302.81    4759  306.37  4815.8   307.8
  4915.2  296.21  4993.6  291.06  4996.4  290.56  4999.6  291.06  5042.7  293.38
  5057.3  298.23  5078.1   293.1  5128.1  297.82  5263.5  304.94  5292.7  299.25
  5307.3  305.94  5313.5  300.61    5350  307.48  5972.7  328.86    6000  329.64
#Mann= 12 ,-1 , 0
  2911.3      .1       0  3025.7     .08       0  3074.2      .1       0
    3348     .05       0  3425.7      .1       0  3468.7     .05       0
    3635      .1       0  4276.1     .05       0  4559.5      .1       0
  4993.6     .07       0  4999.6      .1       0  5972.7     .05       0
Bank Sta=4915.2,5128.1
XS Rating Curve= 0 ,0
Exp/Cntr=0.3,0.1