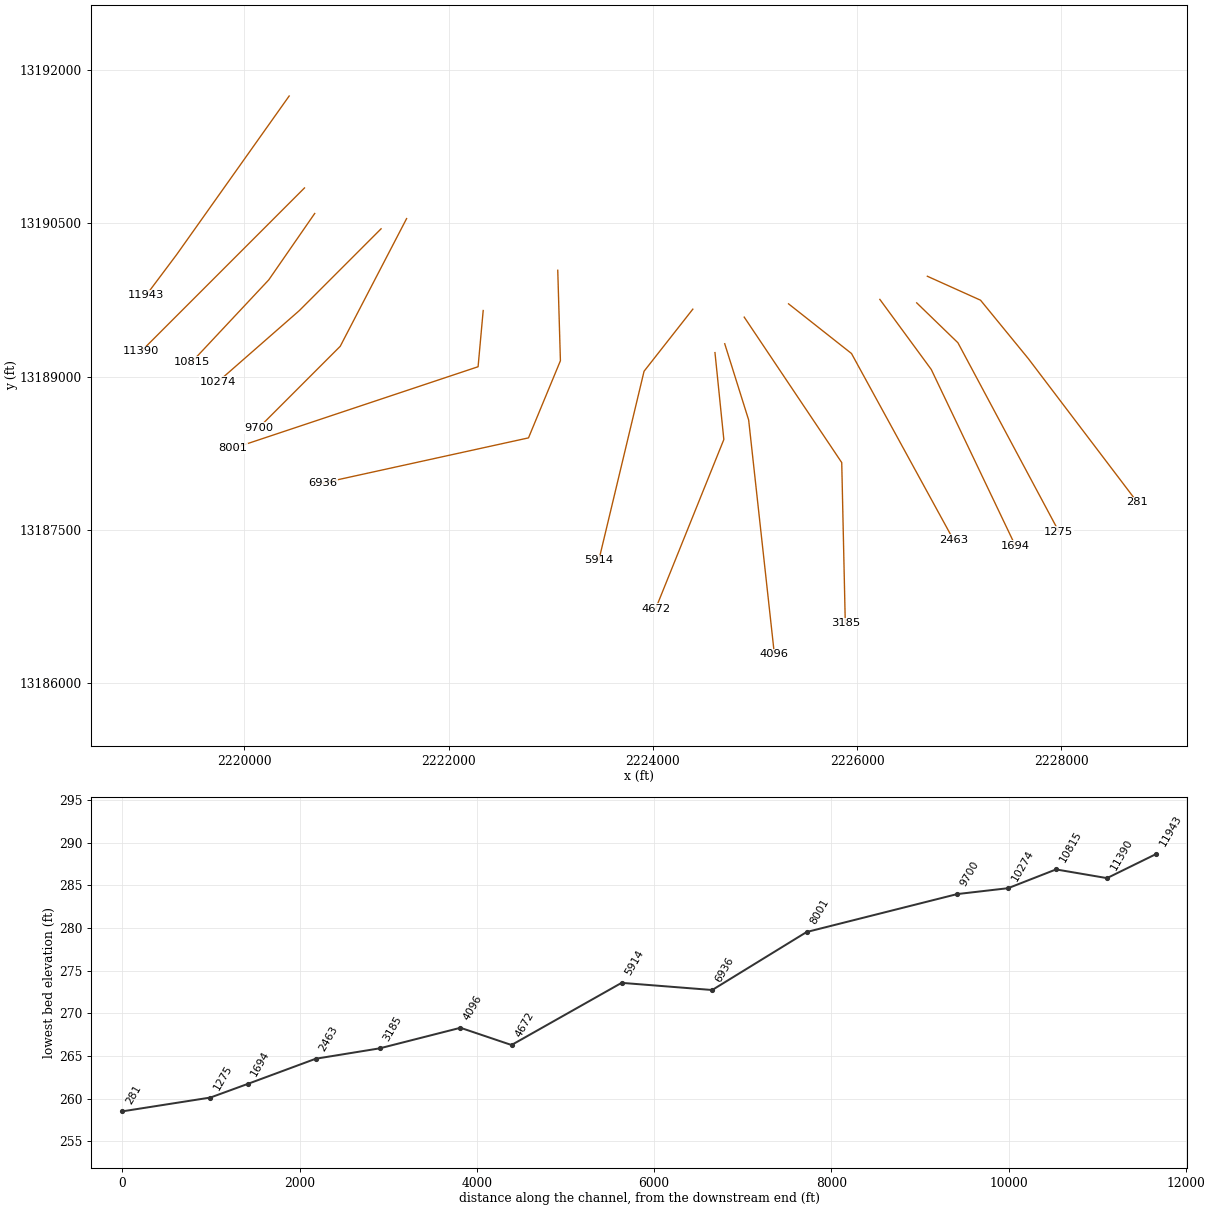
HEC-RAS study BOTELLO CREEK.prj: BOTELLO CREEK Base Level Engineering

--- BOTELLO CREEK.g01 (geometry) --- (continued)

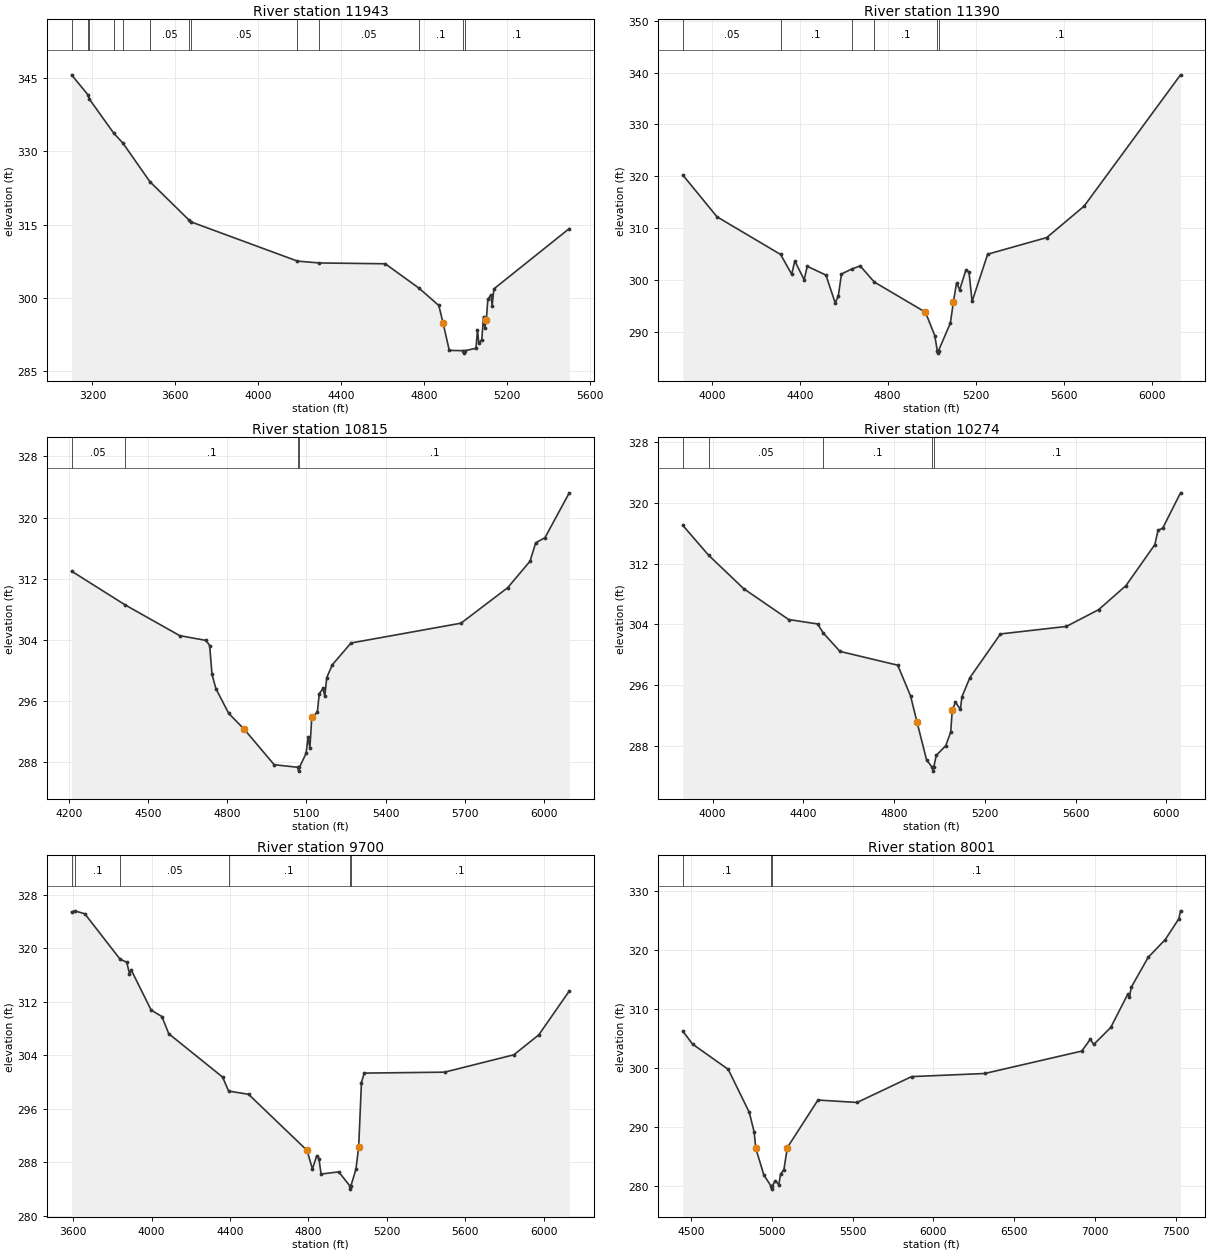
Type RM Length L Ch R = 1 ,11943   ,553,553,553
BEGIN DESCRIPTION:
BOTELLO CREEK 17.0
END DESCRIPTION:
XS GIS Cut Line= 3
      2220437.74     13191746.89      2219337.72     13190196.86
      2219037.72     13189796.86
#Sta/Elev= 30
  3099.3  345.67  3179.6  341.52  3184.5  340.74  3303.5  333.68  3347.2  331.68
  3477.5  323.77  3667.9  315.84    3675  315.56  4188.7  307.52  4294.2  307.14
  4612.5  306.97  4774.5     302  4870.8  298.43  4891.7  294.78  4921.3  289.23
  4989.6  289.17  4992.4  288.67  4995.6  289.17    5050  289.66  5057.3  293.44
  5063.5  290.76  5078.1  291.44  5086.5  296.15  5092.7   293.9    5100  295.47
  5107.3   299.7  5121.9  300.59  5128.1  298.39  5136.5  301.83    5500  314.18
#Mann= 13 ,-1 , 0
  3099.3     .08       0  3179.6     .05       0  3184.5      .1       0
  3303.5     .05       0  3347.2      .1       0  3477.5     .05       0
  3667.9      .1       0    3675     .05       0  4188.7      .1       0
  4294.2     .05       0  4774.5      .1       0  4989.6     .07       0
  4995.6      .1       0
Bank Sta=4891.7,5100
XS Rating Curve= 0 ,0
Exp/Cntr=0.3,0.1

Type RM Length L Ch R = 1 ,11390   ,575,575,575
BEGIN DESCRIPTION:
BOTELLO CREEK 16.0
END DESCRIPTION:
XS GIS Cut Line= 3
      2220587.74     13190846.88      2219787.72     13190046.85
       2218987.7     13189246.83
#Sta/Elev= 30
  3868.6  320.23  4024.2  312.16  4313.4  304.89  4363.6  301.07  4377.7  303.65
  4420.2  300.01  4434.3  302.61  4519.2  300.92  4561.6  295.52  4575.7  296.94
  4589.9  301.13  4636.6  302.08  4674.7  302.69  4739.3  299.57  4971.7  293.75
  5014.1  289.24  5025.3  286.35    5028  285.85  5031.3  286.35  5084.9  291.64
    5099  295.78  5113.1   299.4  5127.3  298.08  5155.6   301.9  5169.7  301.49
  5183.8  295.83  5254.6  304.95  5523.3  308.16    5693  314.22  6131.4  339.57
#Mann= 6 ,-1 , 0
  3868.6     .05       0  4313.4      .1       0  4636.6     .05       0
  4739.3      .1       0  5025.3     .07       0  5031.3      .1       0
Bank Sta=4971.7,5099
XS Rating Curve= 0 ,0
Exp/Cntr=0.3,0.1

Type RM Length L Ch R = 1 ,10815   ,541,541,541
BEGIN DESCRIPTION:
BOTELLO CREEK 15.0
END DESCRIPTION:
XS GIS Cut Line= 3
      2220687.74     13190596.88      2220237.72     13189946.85
      2219487.71     13189146.84
#Sta/Elev= 30
  4209.4     313    4412   308.6  4619.6  304.57  4720.3  303.94  4733.1  303.25
  4741.9  299.54  4756.7  297.64  4805.4  294.41  4864.2  292.34  4977.7  287.71
  5067.6  287.37  5070.3  286.87  5073.6  287.37  5098.9  289.21  5106.2  291.34
  5113.1  289.88  5120.4  293.95  5141.4  294.55  5148.7     297  5162.9  297.67
  5169.7  296.68  5177.1   299.1  5198.1  300.76  5268.9  303.61  5686.1   306.2
  5863.3  310.84  5947.9   314.3  5969.3   316.7  6004.5  317.37  6096.6  323.23
#Mann= 4 ,-1 , 0
  4209.4     .05       0    4412      .1       0  5067.6     .07       0
  5073.6      .1       0
Bank Sta=4864.2,5120.4
XS Rating Curve= 0 ,0
Exp/Cntr=0.3,0.1

Type RM Length L Ch R = 1 ,10274   ,574,574,574
BEGIN DESCRIPTION:
BOTELLO CREEK 14.0
END DESCRIPTION:
XS GIS Cut Line= 3
      2221337.74     13190446.88      2220537.72     13189646.85
      2219737.73     13188946.86
#Sta/Elev= 30
  3868.6  317.06  3982.2  313.13  4137.3  308.71  4335.3  304.65  4462.6  304.07
  4488.4  302.86  4561.6  300.45  4816.2  298.63  4872.7  294.58    4901  291.15
  4943.4  286.14  4968.7  285.17  4971.5  284.67  4974.7  285.17  4985.9  286.74
    5028  288.03  5049.8  289.84  5056.5  292.71  5070.7  293.76  5092.5  292.81
  5099.2  294.47  5134.3  296.99  5269.1  302.75  5559.5  303.74  5701.9  305.95
  5822.4  309.12  5949.6  314.52  5963.8   316.4  5984.7  316.71    6063  321.35
#Mann= 5 ,-1 , 0
  3868.6      .1       0  3982.2     .05       0  4488.4      .1       0
  4968.7     .07       0  4974.7      .1       0
Bank Sta=4901,5056.5
XS Rating Curve= 0 ,0
Exp/Cntr=0.3,0.1

Type RM Length L Ch R = 1 ,9700    ,1699,1699,1699
BEGIN DESCRIPTION:
BOTELLO CREEK 13.0
END DESCRIPTION:
XS GIS Cut Line= 3
      2221587.72     13190546.85      2220937.72     13189296.85
       2220137.7     13188496.83
#Sta/Elev= 30
  3591.1  325.43  3606.4  325.62  3658.7  325.18  3838.4   318.4  3872.9  317.92
  3886.8  316.21  3895.4  316.78  3997.3  310.77  4052.4   309.8    4087  307.24
  4361.9  300.75  4392.8  298.65  4494.5  298.17  4792.8  289.78  4820.5     287
  4842.6  288.99  4853.5  288.56  4864.7  286.24  4954.9  286.56  5011.1  284.48
  5013.9  283.98  5017.1  284.48  5042.4  286.93  5056.6  290.26  5070.7  299.93
  5084.9  301.34    5495  301.48  5848.5  304.08  5975.8  307.06  6131.4  313.62
#Mann= 6 ,-1 , 0
  3591.1     .05       0  3606.4      .1       0  3838.4     .05       0
  4392.8      .1       0  5011.1     .07       0  5017.1      .1       0
Bank Sta=4792.8,5056.6
XS Rating Curve= 0 ,0
Exp/Cntr=0.3,0.1

Type RM Length L Ch R = 1 ,8001    ,1065,1065,1065
BEGIN DESCRIPTION:
BOTELLO CREEK 12.0
END DESCRIPTION:
XS GIS Cut Line= 3
      2222337.72     13189646.89      2222287.72     13189096.85
      2219887.74     13188296.86
#Sta/Elev= 30
  4447.7  306.31    4508  304.11  4728.9  299.83  4859.4  292.53  4889.5  289.21
  4899.6  286.44  4949.8  281.91  4994.5  280.03  4997.2  279.53  5000.5  280.03
  5021.1  280.97  5042.2  280.26  5052.7  282.05  5073.8  282.85  5094.9  286.58
  5284.6  294.63    5527  294.22  5864.4   298.6  6317.6  299.13  6918.4  302.93
  6971.2  304.93  6992.2  304.05  7097.6  306.93  7203.1  312.58  7213.6  312.06
  7224.1  313.72  7329.5  318.82    7435  321.82  7519.3  325.35  7529.8   326.7
#Mann= 3 ,-1 , 0
  4447.7      .1       0  4994.5     .07       0  5000.5      .1       0
Bank Sta=4899.6,5094.9
XS Rating Curve= 0 ,0
Exp/Cntr=0.3,0.1

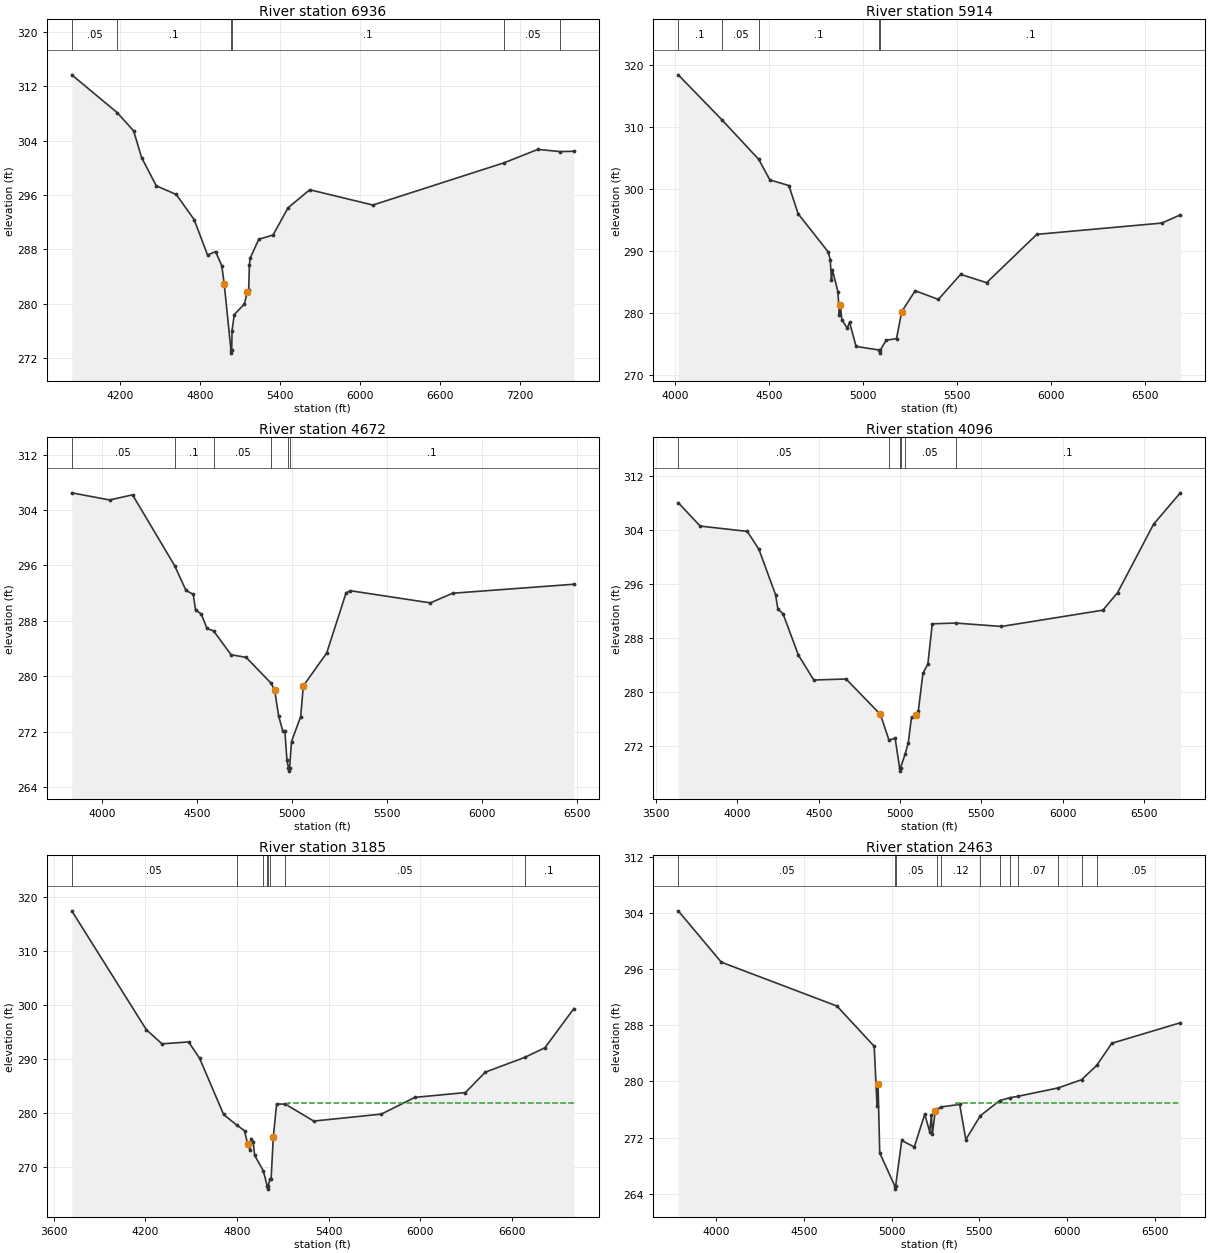
Type RM Length L Ch R = 1 ,6936    ,1022,1022,1022
BEGIN DESCRIPTION:
BOTELLO CREEK 11.0
END DESCRIPTION:
XS GIS Cut Line= 4
       2223067.9       13190041.      2223093.94     13189155.59
      2222781.44     13188400.38      2220763.22     13187957.68
#Sta/Elev= 30
  3834.2  313.66  4175.2   308.1  4298.5  305.42  4358.6  301.49  4468.6  297.34
  4618.7  296.06  4752.9  292.37  4853.9  287.15  4913.4  287.67  4960.3   285.6
  4978.4  282.97    5029  273.23  5031.8  272.73    5035  273.23  5037.5  276.02
  5054.1   278.4  5129.9  279.94  5151.5  281.71  5162.3  281.97  5167.8  285.75
  5173.2  286.68  5238.1  289.47  5345.9  290.11  5457.7   294.1  5620.8  296.76
  6094.8  294.51  7082.3  300.74  7332.7  302.69  7502.9  302.37  7603.5  302.42
#Mann= 6 ,-1 , 0
  3834.2     .05       0  4175.2      .1       0    5029     .07       0
    5035      .1       0  7082.3     .05       0  7502.9      .1       0
Bank Sta=4978.4,5151.5
XS Rating Curve= 0 ,0
Exp/Cntr=0.3,0.1

Type RM Length L Ch R = 1 ,5914    ,1242,1242,1242
BEGIN DESCRIPTION:
BOTELLO CREEK 9.0
END DESCRIPTION:
XS GIS Cut Line= 3
      2224390.52     13189660.31      2223913.07     13189052.65
      2223470.37      13187203.7
#Sta/Elev= 30
  4015.6  318.44  4248.8  311.17    4444  304.82  4503.6   301.5  4604.8  300.59
  4654.5  296.02  4814.9  289.87  4825.2   288.6  4831.6  285.43  4836.7     287
  4866.3  283.45  4873.6  279.65  4878.8  281.37  4886.9  278.95  4915.7   277.6
    4928  278.54  4962.8  274.65    5086  274.07  5088.7  273.57    5092  274.07
  5123.4  275.66  5178.2  275.91  5205.7  280.24  5277.6  283.63    5401  282.23
  5519.6  286.27  5658.1  284.93  5925.4  292.72  6591.1  294.54  6689.6  295.86
#Mann= 5 ,-1 , 0
  4015.6      .1       0  4248.8     .05       0    4444      .1       0
    5086     .07       0    5092      .1       0
Bank Sta=4878.8,5205.7
XS Rating Curve= 0 ,0
Exp/Cntr=0.3,0.1

Type RM Length L Ch R = 1 ,4672    ,576,576,576
BEGIN DESCRIPTION:
BOTELLO CREEK 8.0
END DESCRIPTION:
XS GIS Cut Line= 3
      2224607.51     13189234.98      2224694.32     13188384.25
      2224025.92     13186726.26
#Sta/Elev= 30
  3842.1  306.47  4041.2  305.44  4161.9  306.18  4383.8  295.94  4443.3  292.37
  4481.5  291.82  4493.6  289.55  4523.7  288.96  4553.9  286.89    4589  286.52
  4680.5  283.09  4759.8  282.71    4892  278.96  4910.1  277.94  4931.6  274.17
  4953.2  272.03  4963.8  272.12  4974.8  267.86  4982.6  266.78  4985.3  266.28
  4988.6  266.78  4998.7  270.55    5047  274.16    5061  278.59    5184  283.34
    5286  292.03    5309  292.33  5729.5  290.58  5847.1  291.97  6484.9  293.27
#Mann= 6 ,-1 , 0
  3842.1     .05       0  4383.8      .1       0    4589     .05       0
    4892      .1       0  4982.6     .07       0  4988.6      .1       0
Bank Sta=4910.1,5061
XS Rating Curve= 0 ,0
Exp/Cntr=0.3,0.1

Type RM Length L Ch R = 1 ,4096    ,911,911,911
BEGIN DESCRIPTION:
BOTELLO CREEK 7.0
END DESCRIPTION:
XS GIS Cut Line= 3
        2224703.     13189321.75      2224937.38     13188575.22
      2225189.11     13186283.56
#Sta/Elev= 30
  3635.7  308.05  3770.1  304.58  4060.1  303.79  4131.9  301.14  4234.3  294.41
  4248.7  292.28  4280.2   291.6  4374.5  285.49  4469.5  281.79    4668  281.94
  4879.3  276.69  4931.6   272.9  4969.8  273.15    4997   268.8  4999.7   268.3
    5003   268.8  5030.7  270.79  5050.3  272.47  5070.4  276.28  5100.6  276.54
  5111.9  277.13  5140.8  282.79    5171  284.15    5198  290.11  5341.2  290.22
  5623.7  289.72  6247.5  292.13    6338  294.73  6559.3  304.86  6723.6   309.5
#Mann= 6 ,-1 , 0
  3635.7     .05       0  4931.6      .1       0    4997     .07       0
    5003      .1       0  5030.7     .05       0  5341.2      .1       0
Bank Sta=4879.3,5100.6
XS Rating Curve= 0 ,0
Exp/Cntr=0.3,0.1

Type RM Length L Ch R = 1 ,3185    ,722,722,722
BEGIN DESCRIPTION:
BOTELLO CREEK 5.0
END DESCRIPTION:
XS GIS Cut Line= 3
      2224893.97     13189582.18      2225848.84     13188158.56
      2225883.56     13186587.34
#Sta/Elev= 30
  3717.8  317.45  4206.1  295.42  4308.1  292.81  4482.1  293.16  4554.2  290.14
  4711.6  279.72  4796.8  277.77  4848.3  276.71  4869.3  274.18  4884.3  273.18
  4892.2  275.25  4905.3  274.66  4914.3  272.17  4971.3  269.29  4997.6  266.39
  5000.3  265.89  5003.6  266.39  5013.9  267.77  5022.4  267.78  5036.7  275.55
  5058.4  281.66  5114.5  281.65  5301.6   278.5  5743.8  279.79  5963.8  282.89
  6293.9  283.78  6423.9  287.56    6681  290.28    6814  292.08  7003.6  299.34
#Mann= 8 ,-1 , 0
  3717.8     .05       0  4796.8      .1       0  4971.3     .12       0
  4997.6     .07       0  5003.6     .12       0  5013.9      .1       0
  5114.5     .05       0    6681      .1       0
#XS Ineff= 2 , 0
                         5136.02          281.76
Permanent Ineff=
       F       F
Bank Sta=4869.3,5036.7
XS Rating Curve= 0 ,0
Exp/Cntr=0.3,0.1

Type RM Length L Ch R = 1 ,2463    ,769,769,769
BEGIN DESCRIPTION:
BOTELLO CREEK 4.0
END DESCRIPTION:
XS GIS Cut Line= 3
      2225328.03     13189712.36      2225944.32     13189226.26
       2226942.6     13187403.33
#Sta/Elev= 30
  3782.5   304.3    4028  296.99  4687.7  290.74  4900.1  285.01  4916.3   276.5
    4922  279.59  4931.6  269.82  5016.6  265.17  5019.4  264.67  5022.6  265.17
    5057   271.6  5128.7  270.67  5188.4  275.35  5216.6  272.82  5226.3  275.22
    5232  272.47  5248.1  275.81  5257.6  276.03  5283.7  276.38  5387.6  276.73
  5422.6  271.73  5505.4  275.12  5616.2  277.29  5676.3   277.7  5718.6  277.88
  5948.8  279.08  6082.6  280.25  6168.6  282.28  6255.2  285.44  6645.8  288.36
#Mann= 12 ,-1 , 0
  3782.5     .05       0  5016.6     .03       0  5022.6     .05       0
  5257.6      .1       0  5283.7     .12       0  5505.4      .1       0
  5616.2     .07       0  5676.3      .1       0  5718.6     .07       0
  5948.8     .05       0  6082.6     .07       0  6168.6     .05       0
#XS Ineff= 2 , 0
                         5365.06          276.95
Permanent Ineff=
       F       F
Bank Sta=4922,5248.1
XS Rating Curve= 0 ,0
Exp/Cntr=0.3,0.1

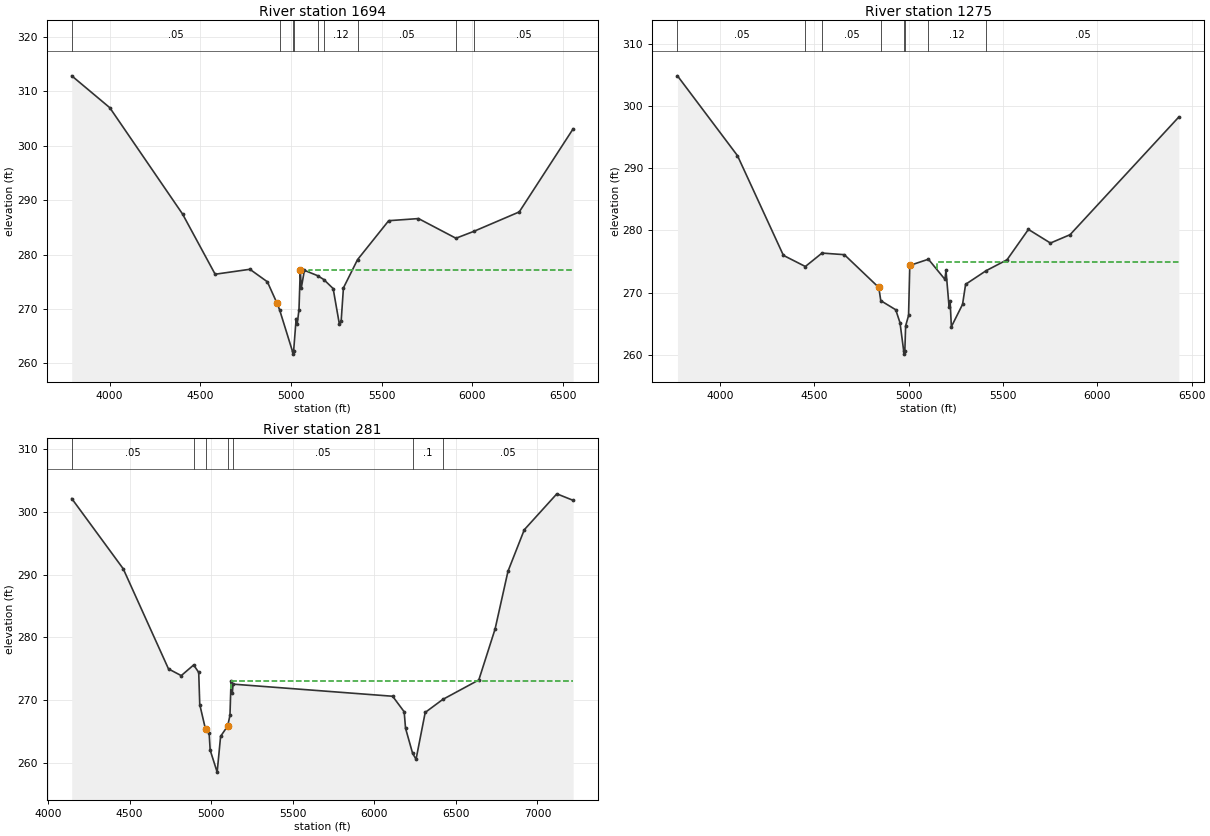
Type RM Length L Ch R = 1 ,1694    ,419,419,419
BEGIN DESCRIPTION:
BOTELLO CREEK 3.0
END DESCRIPTION:
XS GIS Cut Line= 3
      2226222.12     13189755.75      2226725.57     13189070.01
      2227550.23     13187342.57
#Sta/Elev= 30
  3791.2  312.81    4001  306.96  4402.2  287.44    4582  276.38  4773.7  277.29
    4870  274.99  4922.4  271.11  4937.1  269.88  5008.6  262.21  5011.4  261.71
  5014.6  262.21  5028.8  268.24  5034.3   267.2  5044.3  269.86  5051.5  277.21
    5057  273.84  5074.2   277.1  5146.7  276.12  5180.9  275.41  5232.7  273.75
  5266.7  267.28    5277  267.82  5289.4  273.87  5367.2  279.06    5539  286.21
  5703.3   286.6  5909.8  282.99  6006.8  284.23  6258.9  287.82  6556.1  303.08
#Mann= 9 ,-1 , 0
  3791.2     .05       0  4937.1      .1       0  5008.6     .07       0
  5014.6      .1       0  5146.7     .05       0  5180.9     .12       0
  5367.2     .05       0  5909.8      .1       0  6006.8     .05       0
#XS Ineff= 2 , 0
                         5100.85           277.2
Permanent Ineff=
       F       F
Bank Sta=4922.4,5051.5
XS Rating Curve= 0 ,0
Exp/Cntr=0.3,0.1

Type RM Length L Ch R = 1 ,1275    ,994,994,994
BEGIN DESCRIPTION:
BOTELLO CREEK 2.0
END DESCRIPTION:
XS GIS Cut Line= 3
      2226582.99     13189722.01      2226986.65     13189331.37
      2227974.78     13187483.85
#Sta/Elev= 30
  3775.4  304.84  4093.5  292.01  4336.8  275.99  4453.1   274.2  4541.5  276.36
  4659.8   276.1  4842.3  270.83  4852.8  268.71    4932  267.25  4954.6  265.17
  4974.3  260.62  4977.1  260.12  4980.3  260.62  4984.5  264.66    5000  266.33
  5006.5  274.37  5105.2  275.37  5192.6  272.14  5198.3  273.56  5214.6  267.77
  5220.2  268.63  5226.8  264.52  5286.1  268.12  5302.3  271.34  5411.2  273.53
  5521.8  275.28  5635.1  280.16  5751.8  277.97  5855.8  279.31  6432.3  298.23
#Mann= 8 ,-1 , 0
  3775.4     .05       0  4453.1      .1       0  4541.5     .05       0
  4852.8      .1       0  4974.3     .07       0  4980.3      .1       0
  5105.2     .12       0  5411.2     .05       0
#XS Ineff= 2 , 0
                          5148.3          274.96
Permanent Ineff=
       F       F
Bank Sta=4842.3,5006.5
XS Rating Curve= 0 ,0
Exp/Cntr=0.3,0.1

Type RM Length L Ch R = 1 ,281     ,0,0,0
BEGIN DESCRIPTION:
BOTELLO CREEK 1.0
END DESCRIPTION:
XS GIS Cut Line= 4
      2226687.21      13189982.4        2227208.     13189748.04
      2227676.75     13189175.12      2228742.47      13187771.5
#Sta/Elev= 30
  4145.1  302.13  4460.7  290.93  4738.3  274.96  4816.5  273.89  4892.5  275.59
  4923.5   274.4  4929.9  269.28  4965.1  265.34  4987.4  264.75  4993.8     262
  5036.6   258.5  5057.7  264.21  5100.8  265.84  5115.1  267.55  5121.6  272.99
  5129.5  271.14  5134.4  272.53  6112.3   270.6  6183.1  268.12  6191.4   265.5
  6234.7   261.5  6255.8  260.55    6312  268.02  6419.5  270.09  6640.6   273.2
  6740.4  281.33  6819.4  290.53  6919.3  297.15  7118.9  302.88  7218.8  301.84
#Mann= 7 ,-1 , 0
  4145.1     .05       0  4892.5      .1       0  4965.1     .07       0
  5100.8      .1       0  5134.4     .05       0  6234.7      .1       0
  6419.5     .05       0
#XS Ineff= 2 , 0
       0                 5120.14       0  273.08
Permanent Ineff=
       F       T
Bank Sta=4965.1,5100.8
XS Rating Curve= 0 ,0
Exp/Cntr=0.3,0.1

Chan Stop Cuts=-1
Use User Specified Reach Order=0
Composite Channel Slope=5