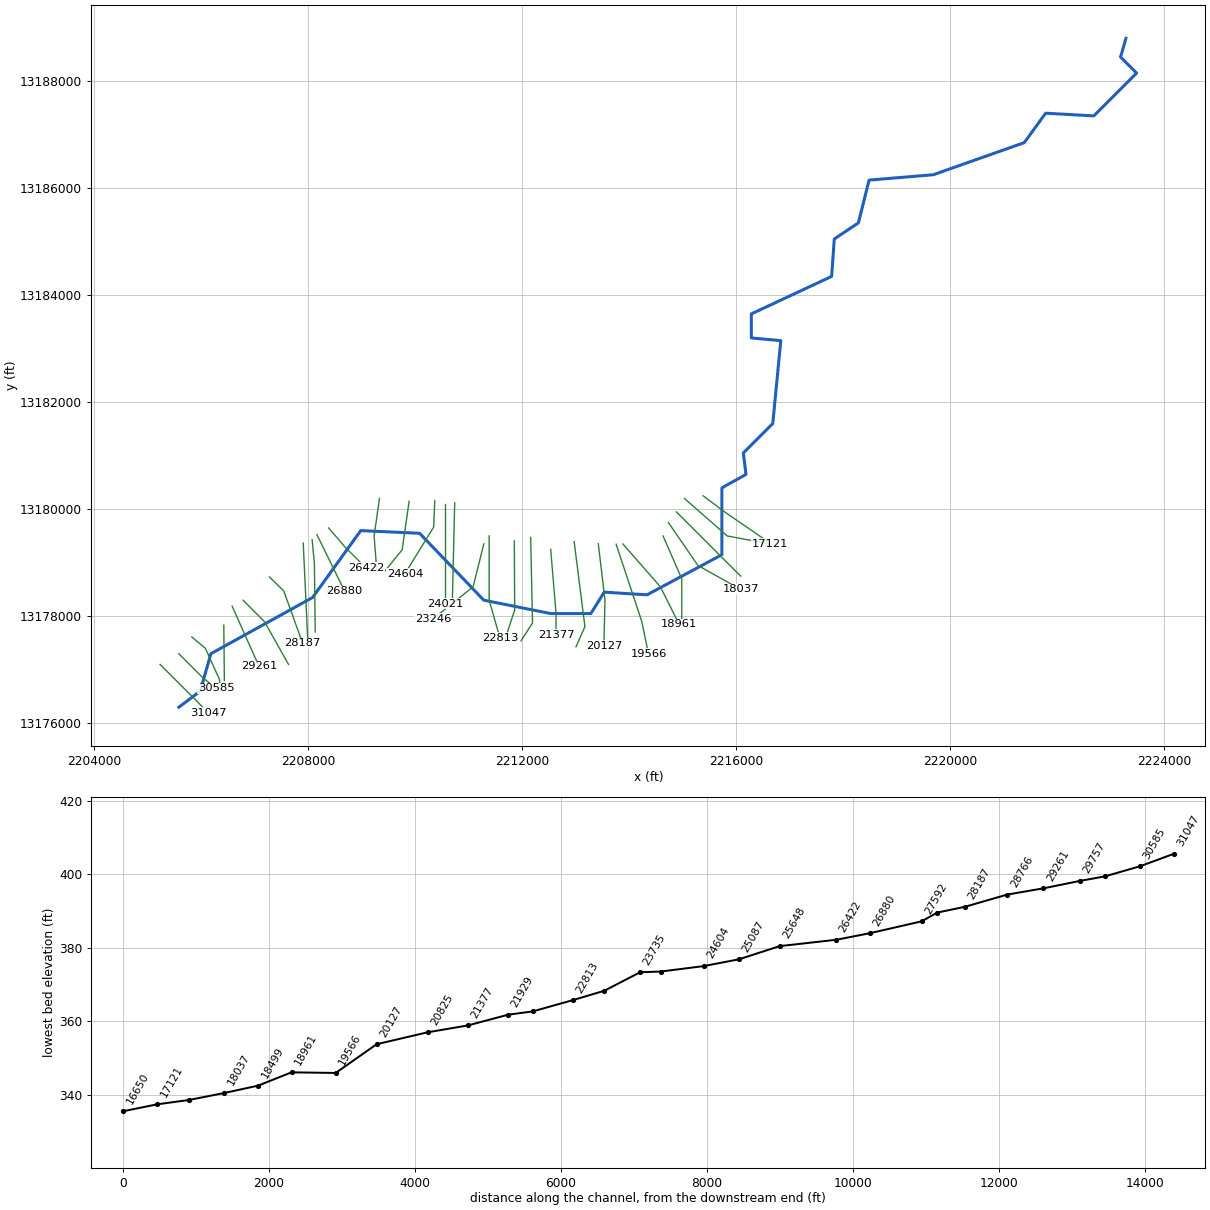
--- GATO CREEK.prj (project) ---

Proj Title=GATO CREEK Base Level Engineering
Current Plan=p01
Default Exp/Contr=0.3,0.1
English Units
Geom File=g01
Flow File=f01
Plan File=p01
Y Axis Title=Elevation
X Axis Title(PF)=Main Channel Distance
X Axis Title(XS)=Station
BEGIN DESCRIPTION:
GATO CREEK
END DESCRIPTION:
DSS Export Rating Curves= 0
DSS Export Rating Curve Sorted= 0
DSS Export Volume Flow Curves= 0
DXF OffsetX= 0
DXF OffsetY= 0
DXF ScaleX= 1
DXF ScaleY= 10

--- GATO CREEK.p01 (plan) ---

Plan Title=Multiple Run
Short Identifier=Multiple
Geom File=g01
Flow File=f01
Subcritical Flow
K Sum by GR= 0
Std Step Tol= 0.01
Critical Tol= 0.01
Num of Std Step Trials= 20
Max Error Tol= 0.3
Flow Tol Ratio= 0.001
Split Flow NTrial= 30
Split Flow Tol= 0.02
Split Flow Ratio= 0.02
Log Output Level= 0
Friction Slope Method= 1
Unsteady Friction Slope Method= 2
Unsteady Bridges Friction Slope Method= 1
Parabolic Critical Depth
Global Vel Dist=  1 , 1 , 1
Global Log Level= 0
CheckData=True
Encroach Param= -1, 0, 0, 0
BEGIN DESCRIPTION:
Multiple Run
END DESCRIPTION:

--- GATO CREEK.f01 (steady flow) ---

Flow Title=Multiple
Program Version=4.10
Number of Profiles= 7
Profile Names=10-year,25-year,50-year,1pct_min,100-year,1pct_plu,500-year
River Rch & RM=GATO CREEK,Reach-1         ,31047
     201     277     339     306     414     560     626
River Rch & RM=GATO CREEK,Reach-1         ,29261
     240     333     411     373     504     682     769
River Rch & RM=GATO CREEK,Reach-1         ,25648
     306     430     534     488     660     892    1021
River Rch & RM=GATO CREEK,Reach-1         ,23735
     312     440     547     500     676     914    1048
River Rch & RM=GATO CREEK,Reach-1         ,22813
     440     631     793     732     990    1339    1567
River Rch & RM=GATO CREEK,Reach-1         ,18037
     515     743     938     870    1177    1591    1879
River Rch & RM=GATO CREEK,Reach-1         ,17554
     515     743     938     870    1177    1591    1879
River Rch & RM=GATO CREEK,Reach-1         ,17121
     559     809    1024     950    1285    1738    2057
River Rch & RM=GATO CREEK,Reach-1         ,13476
     609     883    1120    1041    1408    1904    2260
River Rch & RM=GATO CREEK,Reach-1         ,11404
     609     883    1120    1041    1408    1904    2260
River Rch & RM=GATO CREEK,Reach-1         ,7623
     744    1088    1387    1296    1752    2370    2842
River Rch & RM=GATO CREEK,Reach-1         ,7132
     744    1088    1387    1296    1752    2370    2842
River Rch & RM=GATO CREEK,Reach-1         ,1731
     830    1218    1556    1457    1971    2665    3210
Boundary for River Rch & Prof#=GATO CREEK,Reach-1         , 1
Up Type= 0
Dn Type= 3
Dn Slope=0.0052
Boundary for River Rch & Prof#=GATO CREEK,Reach-1         , 2
Up Type= 0
Dn Type= 3
Dn Slope=0.0052
Boundary for River Rch & Prof#=GATO CREEK,Reach-1         , 3
Up Type= 0
Dn Type= 3
Dn Slope=0.0052
Boundary for River Rch & Prof#=GATO CREEK,Reach-1         , 4
Up Type= 0
Dn Type= 3
Dn Slope=0.0052
Boundary for River Rch & Prof#=GATO CREEK,Reach-1         , 5
Up Type= 0
Dn Type= 3
Dn Slope=0.0052
Boundary for River Rch & Prof#=GATO CREEK,Reach-1         , 6
Up Type= 0
Dn Type= 3
Dn Slope=0.0052
Boundary for River Rch & Prof#=GATO CREEK,Reach-1         , 7
Up Type= 0
Dn Type= 3
Dn Slope=0.0052
DSS Import GetInterval= 0
DSS Import GetPeak= 0
DSS Import FillOption= 0

--- GATO CREEK.g01 (geometry) ---

Geom Title=Existing Conditions
Program Version=4.10

River Reach=GATO CREEK      ,Reach-1
Reach XY= 30
      2205587.72     13176296.85      2205987.72     13176596.85
      2206187.72     13177296.85      2208087.72     13178346.85
      2208987.72     13179596.85      2210087.72     13179546.85
      2211287.72     13178296.85      2212537.72     13178046.86
      2213287.72     13178046.86      2213537.72     13178446.85
      2214337.72     13178396.85      2215737.72     13179146.85
      2215737.72     13180396.85      2216187.72     13180646.85
      2216137.72     13181046.85      2216687.72     13181596.85
      2216837.72     13183146.86      2216287.72     13183196.85
      2216287.72     13183646.85      2217787.72     13184346.85
      2217837.72     13185046.85      2218287.72     13185346.85
      2218487.72     13186146.85      2219687.72     13186246.86
      2221387.72     13186846.85      2221787.72     13187396.86
      2222687.72     13187346.85      2223487.72     13188146.85
      2223187.72     13188446.85      2223287.72     13188796.85

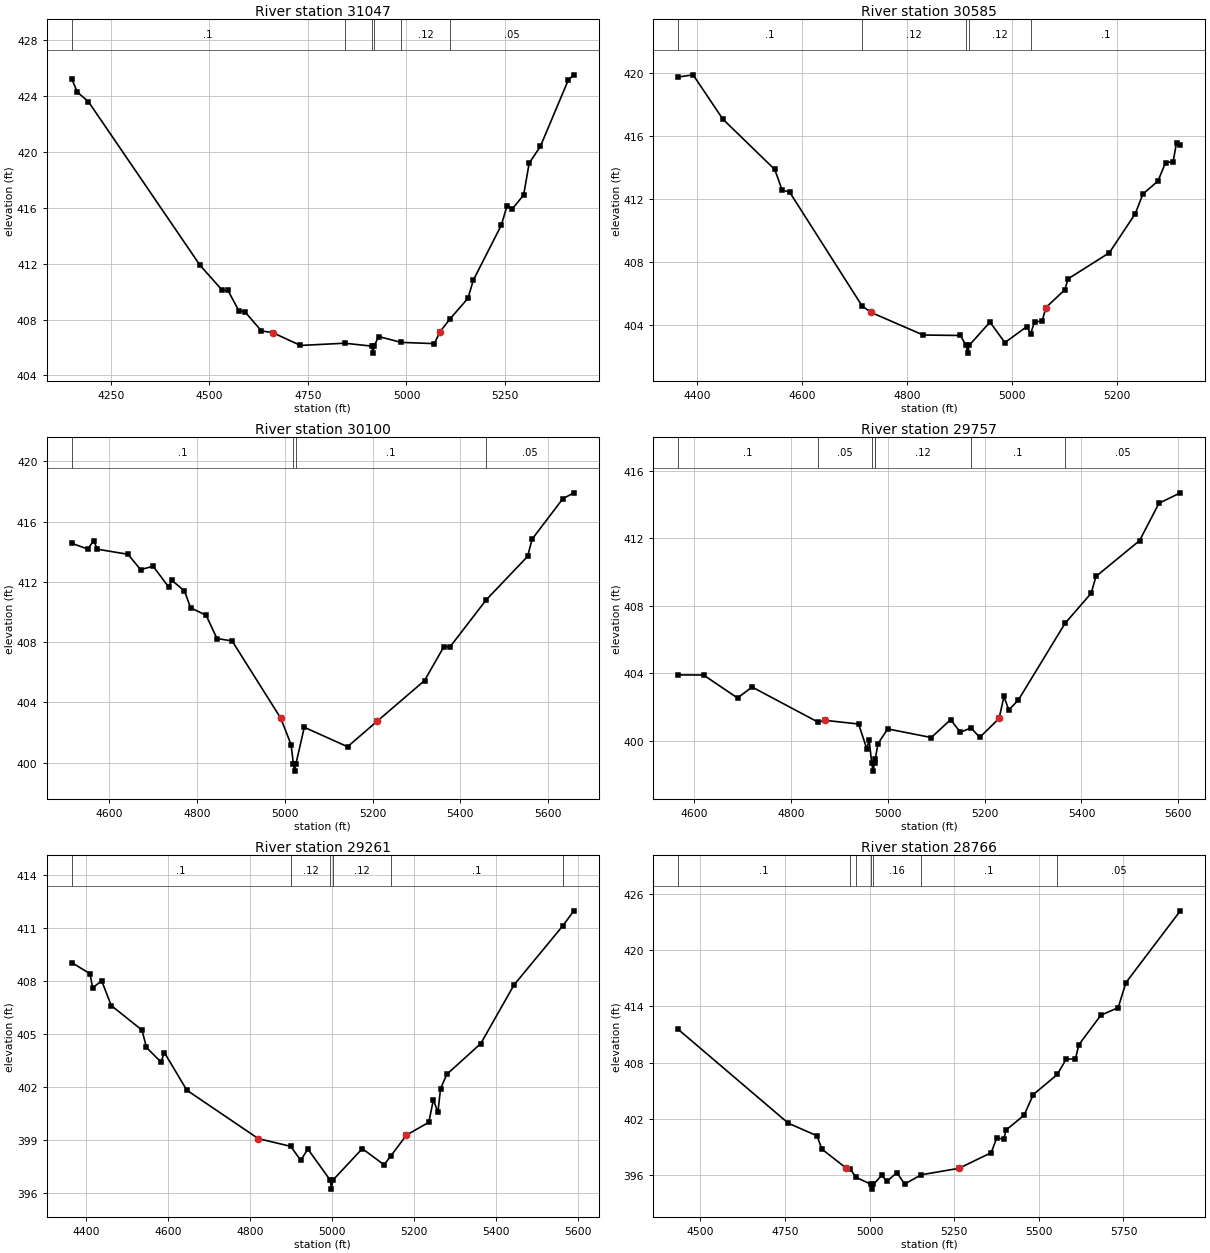
Type RM Length L Ch R = 1 ,31047   ,462,462,462
BEGIN DESCRIPTION:
UNT 041 IN LACR 11.0
END DESCRIPTION:
XS GIS Cut Line= 3
      2205237.74     13177096.83      2205837.72     13176496.85
      2206137.75     13176196.83
#Sta/Elev= 30
  4151.5  425.24  4165.6  424.29  4193.9   423.6  4476.7  411.89  4533.3  410.09
  4547.5  410.09  4575.7   408.6  4589.9  408.58  4632.3  407.19  4660.6  407.07
  4731.3  406.15  4843.3  406.31  4912.1   406.1  4914.9   405.6  4918.1   406.1
  4929.3  406.79  4986.4  406.37  5070.7  406.28  5084.9  407.13    5111  408.07
  5155.6  409.52  5169.7  410.84  5240.4  414.76  5254.6  416.12  5268.7  415.95
    5297  416.92  5311.1  419.21  5339.4   420.4  5410.1  425.15  5424.3  425.53
#Mann= 6 ,-1 , 0
  4151.5      .1       0  4843.3     .05       0  4912.1     .07       0
  4918.1     .05       0  4986.4     .12       0    5111     .05       0
Bank Sta=4660.6,5084.9
XS Rating Curve= 0 ,0
Exp/Cntr=0.3,0.1

Type RM Length L Ch R = 1 ,30585   ,485,485,485
BEGIN DESCRIPTION:
UNT 041 IN LACR 10.0
END DESCRIPTION:
XS GIS Cut Line= 3
      2205587.72     13177296.86      2206037.72     13176846.85
      2206287.75     13176646.83
#Sta/Elev= 30
  4363.6  419.74  4391.9  419.88  4448.5  417.07  4547.5  413.87  4561.6  412.56
  4575.7  412.44    4714   405.2  4731.3  404.79  4830.3  403.36    4901  403.33
  4912.1  402.71  4914.9  402.21  4918.1  402.71  4957.6  404.18  4985.9  402.88
    5028   403.9    5035  403.42  5042.4  404.21  5056.8  404.23    5064   405.1
    5100  406.23  5106.5  406.93  5184.9  408.58  5234.5  411.07  5248.9  412.31
  5277.7  413.14  5292.1  414.31  5306.5  414.36    5313  415.57  5320.2  415.43
#Mann= 5 ,-1 , 0
  4363.6      .1       0    4714     .12       0  4912.1     .07       0
  4918.1     .12       0    5035      .1       0
Bank Sta=4731.3,5064
XS Rating Curve= 0 ,0
Exp/Cntr=0.3,0.1

Type RM Length L Ch R = 1 ,30100   ,343,343,343
BEGIN DESCRIPTION:
UNT 041 IN LACR 9.0
END DESCRIPTION:
XS GIS Cut Line= 4
      2205829.86     13177610.45      2206085.04     13177396.93
      2206350.67     13176808.39      2206355.87     13176641.81
#Sta/Elev= 30
    4514  414.56  4550.3  414.18  4564.2  414.74    4572  414.17  4642.3  413.83
  4670.9  412.81  4699.5  413.04  4734.7  411.67  4742.5   412.1  4771.1  411.39
    4785  410.28  4820.5  409.78  4845.2  408.24  4879.7  408.08  4990.9  402.94
  5014.1   401.2  5019.4  399.94  5022.1  399.44  5025.4  399.94  5044.3  402.35
    5143  401.06    5210  402.74  5318.6  405.45  5362.5  407.69  5377.4  407.71
  5459.3  410.81  5553.6  413.69    5564  414.84    5634  417.52  5659.1  417.91
#Mann= 4 ,-1 , 0
    4514      .1       0  5019.4     .07       0  5025.4      .1       0
  5459.3     .05       0
Bank Sta=4990.9,5210
XS Rating Curve= 0 ,0
Exp/Cntr=0.3,0.1

Type RM Length L Ch R = 1 ,29757   ,496,496,496
BEGIN DESCRIPTION:
UNT 041 IN LACR 8.0
END DESCRIPTION:
XS GIS Cut Line= 2
      2206428.79     13177829.23      2206439.21     13176792.79
#Sta/Elev= 30
  4567.6  403.91    4620   403.9    4690  402.54    4720  403.19  4856.3  401.11
    4870  401.22    4940     401  4956.8  399.53  4961.8  400.04    4967  398.71
  4969.7  398.21    4973  398.71  4974.4  398.94    4980  399.84    5000  400.71
    5090   400.2    5130  401.26    5150  400.51  5172.1  400.77    5190  400.21
    5230  401.33    5240  402.63    5250  401.83    5270  402.43  5366.1  406.96
    5420  408.74    5430  409.74    5520  411.86    5560  414.07  5604.1  414.69
#Mann= 7 ,-1 , 0
  4567.6      .1       0  4856.3     .05       0    4967     .07       0
    4973     .05       0  4974.4     .12       0  5172.1      .1       0
  5366.1     .05       0
Bank Sta=4870,5230
XS Rating Curve= 0 ,0
Exp/Cntr=0.3,0.1

Type RM Length L Ch R = 1 ,29261   ,495,495,495
BEGIN DESCRIPTION:
UNT 041 IN LACR 7.0
END DESCRIPTION:
XS GIS Cut Line= 2
      2206585.03     13178183.42      2207085.05     13177063.58
#Sta/Elev= 30
  4364.6  409.02  4409.1  408.39  4415.6  407.59  4437.7  407.99    4461  406.59
  4536.1   405.2    4547  404.22  4582.5  403.39  4590.8  403.93  4645.6   401.8
  4820.1  399.06  4899.4  398.62  4923.9  397.83  4941.3  398.47  4996.1   396.7
  4998.8   396.2  5002.1   396.7  5074.2  398.49  5127.4  397.58    5144  398.08
  5182.2  399.26  5236.7  399.98  5247.9  401.26  5258.9  400.54  5265.4  401.89
  5280.8   402.7  5363.7  404.44    5445  407.76  5563.3  411.08    5591  411.95
#Mann= 6 ,-1 , 0
  4364.6      .1       0  4899.4     .12       0  4996.1     .07       0
  5002.1     .12       0    5144      .1       0  5563.3     .05       0
Bank Sta=4820.1,5182.2
XS Rating Curve= 0 ,0
Exp/Cntr=0.3,0.1

Type RM Length L Ch R = 1 ,28766   ,579,579,579
BEGIN DESCRIPTION:
UNT 041 IN LACR 6.0
END DESCRIPTION:
XS GIS Cut Line= 3
      2206787.71     13178296.87      2207187.72     13177896.86
      2207637.73     13177096.84
#Sta/Elev= 30
  4434.3  411.55  4759.6  401.54  4844.4   400.2  4858.6  398.78  4929.3  396.79
  4941.5  396.69  4959.9  395.76    5005  395.01  5007.7  394.51    5011  395.01
  5035.4  395.98  5051.3  395.35  5080.3  396.27  5103.3  395.05  5152.2  396.04
  5263.9  396.73  5359.2   398.4  5375.1  399.95  5396.8  399.85  5402.5   400.8
  5456.1  402.39  5483.5   404.6  5554.4  406.74  5580.4  408.37  5608.1  408.41
    5618  409.91    5683  413.06  5734.3  413.87  5757.2  416.54  5917.9   424.2
#Mann= 7 ,-1 , 0
  4434.3      .1       0  4941.5     .12       0  4959.9     .16       0
    5005     .07       0    5011     .16       0  5152.2      .1       0
  5554.4     .05       0
Bank Sta=4929.3,5263.9
XS Rating Curve= 0 ,0
Exp/Cntr=0.3,0.1

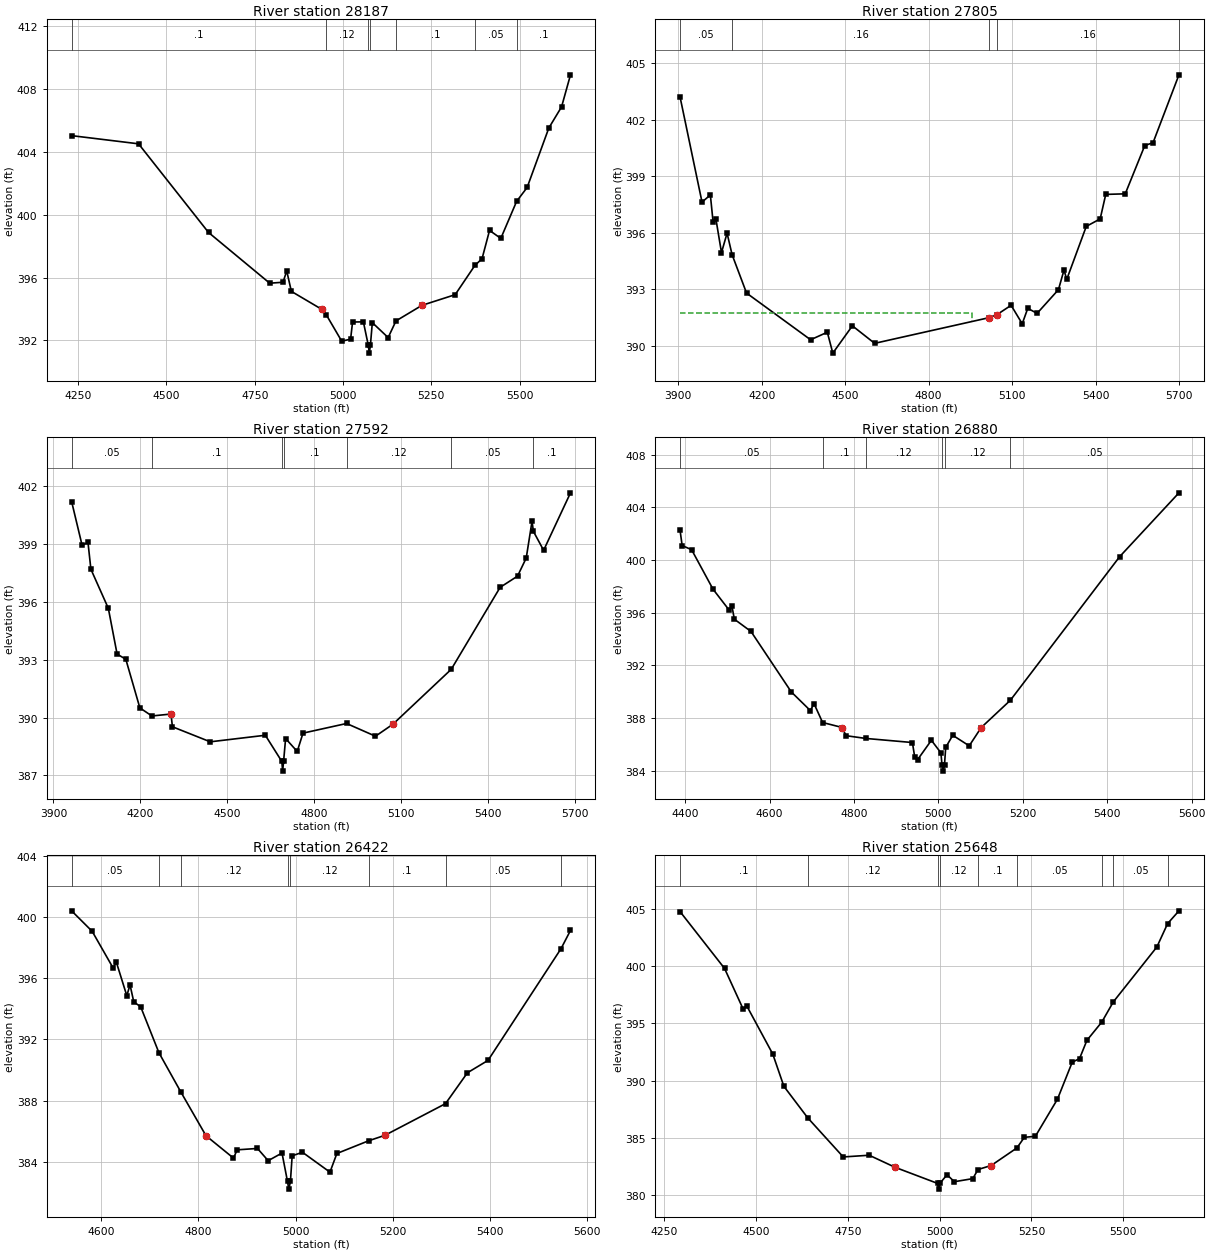
Type RM Length L Ch R = 1 ,28187   ,382,382,382
BEGIN DESCRIPTION:
UNT 041 IN LACR 5.0
END DESCRIPTION:
XS GIS Cut Line= 3
      2207282.98     13178730.25      2207548.58     13178469.85
      2207902.51     13177491.35
#Sta/Elev= 30
  4231.4  405.03  4420.9  404.51    4619  398.87  4792.3  395.64  4829.9   395.7
  4840.5  396.42  4853.6  395.12  4940.2  393.97  4952.7  393.62  4996.2  391.95
  5021.3  392.08  5026.9  393.17  5057.5  393.18  5071.4  391.69  5074.2  391.19
  5077.4  391.69  5082.8  393.13  5127.6  392.18  5149.8  393.24  5223.3  394.23
  5317.4  394.91  5373.2  396.77  5393.5   397.2  5414.7     399  5446.6  398.49
  5491.4  400.85  5521.1  401.73  5582.6  405.52  5618.6  406.86  5643.9   408.9
#Mann= 7 ,-1 , 0
  4231.4      .1       0  4952.7     .12       0  5071.4     .07       0
  5077.4     .12       0  5149.8      .1       0  5373.2     .05       0
  5491.4      .1       0
Bank Sta=4940.2,5223.3
XS Rating Curve= 0 ,0
Exp/Cntr=0.3,0.1

Type RM Length L Ch R = 1 ,27805   ,213,213,213
BEGIN DESCRIPTION:
UNT 041 IN LACR 4.0
END DESCRIPTION:
XS GIS Cut Line= 2
      2207913.17     13179365.64       2207996.5     13177573.97
#Sta/Elev= 30
  3906.3   403.2  3985.2  397.62  4015.2     398  4025.2  396.54  4035.2  396.72
  4055.2  394.94  4075.3  395.97  4093.3  394.83  4145.3  392.79  4375.6  390.31
  4435.7  390.71  4455.4   389.6  4525.8  391.05  4605.8  390.12  5016.3  391.48
  5046.3  391.65  5096.4  392.14  5136.4  391.16  5156.4  391.98  5189.8  391.71
  5266.6  392.97  5286.6  394.01  5296.6  393.52  5366.7  396.33  5416.7  396.73
  5436.7  398.03  5506.8  398.06  5576.9  400.62  5606.9  400.78  5699.9  404.38
#Mann= 5 ,-1 , 0
  3906.3     .05       0  4093.3     .16       0  5016.3     .07       0
  5046.3     .16       0  5699.9      .1       0
#XS Ineff= 2 , 0
       0 4956.86  391.72               0
Permanent Ineff=
       T       F
Bank Sta=5016.3,5046.3
XS Rating Curve= 0 ,0
Exp/Cntr=0.3,0.1

Type RM Length L Ch R = 1 ,27592   ,712,712,712
BEGIN DESCRIPTION:
UNT 041 IN LACR 3.0
END DESCRIPTION:
XS GIS Cut Line= 3
      2208079.83     13179423.01       2208121.5     13178990.68
      2208137.12      13177704.2
#Sta/Elev= 30
  3962.9   401.2  3999.2  398.92  4019.3  399.09  4029.4  397.69  4089.6  395.66
  4119.8  393.29  4149.9  393.02  4198.3   390.5  4239.8  390.08  4305.7  390.18
  4310.7  389.52  4441.1  388.74  4631.1  389.08  4688.1  387.72  4690.8  387.22
  4694.1  387.72  4701.1  388.91  4741.1  388.24  4761.1  389.19  4911.4  389.69
  5011.1  389.03  5071.1  389.65  5272.5   392.5  5441.1  396.75  5501.1  397.33
  5531.1  398.27  5551.1  400.17  5555.9  399.65  5591.1  398.67  5683.8  401.65
#Mann= 7 ,-1 , 0
  3962.9     .05       0  4239.8      .1       0  4688.1     .07       0
  4694.1      .1       0  4911.4     .12       0  5272.5     .05       0
  5555.9      .1       0
Bank Sta=4305.7,5071.1
XS Rating Curve= 0 ,0
Exp/Cntr=0.3,0.1

Type RM Length L Ch R = 1 ,26880   ,458,458,458
BEGIN DESCRIPTION:
UNT 041 IN LACR 2.0
END DESCRIPTION:
XS GIS Cut Line= 2
      2208168.39      13179521.9      2208688.61     13178460.65
#Sta/Elev= 30
  4388.1  402.25    4393   401.1  4415.5  400.78  4466.1  397.79  4505.1  396.17
  4511.1  396.48  4516.7  395.51  4556.1  394.58  4651.6  389.99  4696.6  388.58
  4705.6  389.09  4725.8  387.67  4772.4  387.29  4781.1  386.67  4828.4  386.46
  4938.5  386.15  4944.1  385.03  4950.6  384.84  4983.5  386.32    5006  385.37
  5008.6  384.48  5011.3  383.98  5014.6  384.48  5017.4  385.78  5034.1   386.7
  5073.1   385.9  5101.6  387.29  5170.7  389.36  5429.4  400.25    5570   405.1
#Mann= 6 ,-1 , 0
  4388.1     .05       0  4725.8      .1       0  4828.4     .12       0
  5008.6     .07       0  5014.6     .12       0  5170.7     .05       0
Bank Sta=4772.4,5101.6
XS Rating Curve= 0 ,0
Exp/Cntr=0.3,0.1

Type RM Length L Ch R = 1 ,26422   ,774,774,774
BEGIN DESCRIPTION:
UNT 041 IN LACR 1.0
END DESCRIPTION:
XS GIS Cut Line= 3
      2208387.71     13179646.87      2208687.72     13179296.85
      2209087.73     13178896.84
#Sta/Elev= 30
    4539  400.41  4581.3  399.07  4624.1  396.69  4631.2  397.04  4652.6  394.86
  4659.2  395.57  4666.9  394.46  4681.2  394.13  4718.7  391.13  4763.5  388.58
  4815.6   385.7  4872.1  384.24  4879.8  384.78  4921.5  384.87  4943.5  384.07
    4972  384.57  4983.3  382.71    4986  382.21  4989.3  382.71  4992.9  384.39
  5014.1  384.62  5070.7  383.32  5084.9  384.54  5150.1  385.37  5183.8  385.73
  5308.5   387.8  5353.6  389.82    5396  390.63  5546.3  397.94  5565.7  399.13
#Mann= 8 ,-1 , 0
    4539     .05       0  4718.7      .1       0  4763.5     .12       0
  4983.3     .07       0  4989.3     .12       0  5150.1      .1       0
  5308.5     .05       0  5546.3      .1       0
Bank Sta=4815.6,5183.8
XS Rating Curve= 0 ,0
Exp/Cntr=0.3,0.1

Type RM Length L Ch R = 1 ,25648   ,561,561,561
BEGIN DESCRIPTION:
GATO CREEK 45.0
END DESCRIPTION:
XS GIS Cut Line= 3
      2209337.72     13180196.85      2209237.72     13179496.85
      2209287.72     13178846.87
#Sta/Elev= 30
  4292.9   404.8  4414.1  399.82  4464.6  396.27  4474.7  396.53  4545.4  392.32
  4575.7  389.49  4640.6  386.73  4737.4   383.3  4808.1  383.45  4878.8  382.39
  4994.5  380.98  4997.2  380.48  5000.5  380.98  5020.1  381.74  5040.1  381.13
  5090.3   381.4  5104.6   382.2  5140.4  382.55  5210.5  384.09  5230.7  385.02
  5260.8  385.11  5320.9  388.36  5361.1   391.6  5381.1  391.92  5401.2  393.52
  5441.9  395.13  5473.1  396.89  5591.7   401.7    5621  403.75  5651.9  404.87
#Mann= 9 ,-1 , 0
  4292.9      .1       0  4640.6     .12       0  4994.5     .07       0
  5000.5     .12       0  5104.6      .1       0  5210.5     .05       0
  5441.9      .1       0  5473.1     .05       0    5621      .1       0
Bank Sta=4878.8,5140.4
XS Rating Curve= 0 ,0
Exp/Cntr=0.3,0.1

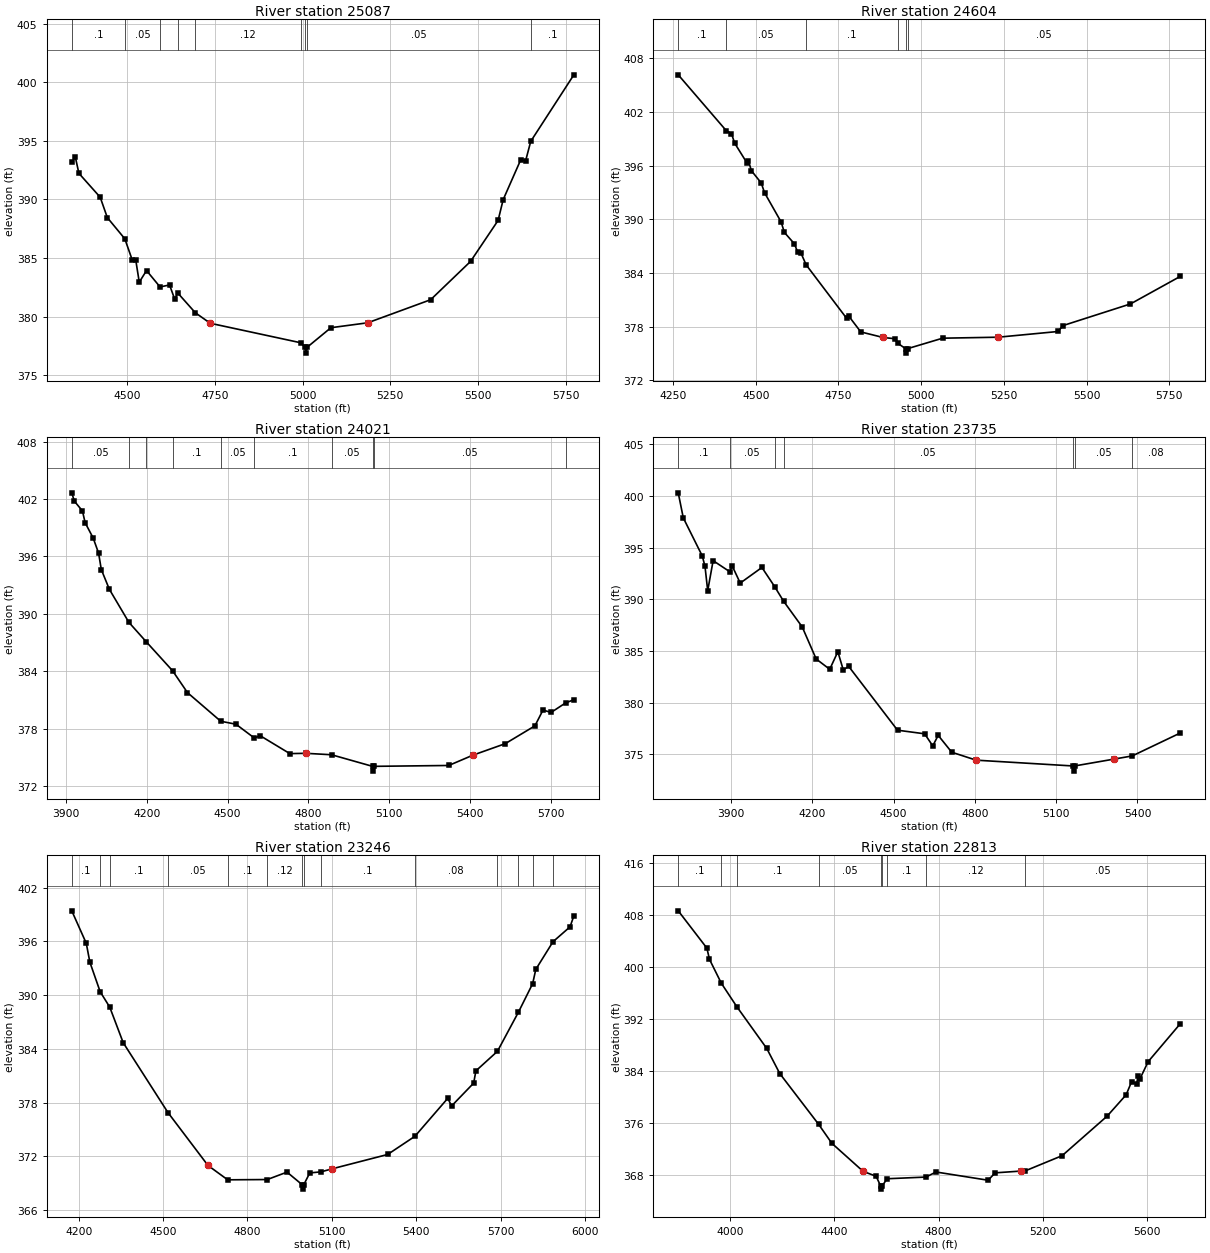
Type RM Length L Ch R = 1 ,25087   ,483,483,483
BEGIN DESCRIPTION:
GATO CREEK 44.0
END DESCRIPTION:
XS GIS Cut Line= 3
      2209892.34     13180146.98      2209762.12     13179240.68
      2209440.08     13178840.72
#Sta/Elev= 30
  4343.2   393.2  4353.4  393.61  4363.5  392.23  4424.1  390.19  4444.4  388.45
  4494.2  386.64  4515.1  384.85  4525.2  384.85  4535.3  382.94    4556  383.93
  4594.5  382.53  4621.5   382.7  4636.3  381.48    4645  382.01  4694.8  380.33
  4737.3  379.43  4995.7  377.76  5007.1  377.38  5009.9  376.88  5013.1  377.38
  5080.8  379.05  5185.6  379.47  5364.7  381.44  5478.3  384.71  5556.7  388.21
  5571.1  389.98  5620.7  393.36  5635.1  393.31  5649.6  394.96  5772.3  400.64
#Mann= 9 ,-1 , 0
  4343.2      .1       0  4494.2     .05       0  4594.5     .12       0
    4645     .05       0  4694.8     .12       0  4995.7     .05       0
  5007.1     .03       0  5013.1     .05       0  5649.6      .1       0
Bank Sta=4737.3,5185.6
XS Rating Curve= 0 ,0
Exp/Cntr=0.3,0.1

Type RM Length L Ch R = 1 ,24604   ,583,583,583
BEGIN DESCRIPTION:
GATO CREEK 43.0
END DESCRIPTION:
XS GIS Cut Line= 3
       2210371.5     13180157.39      2210350.67     13179662.56
       2209814.2     13178792.76
#Sta/Elev= 30
  4265.9  406.15    4411  399.91  4426.6  399.59  4436.6   398.5  4473.1  396.33
  4478.1  396.57  4486.6  395.45  4516.7  394.06  4526.7  392.97  4576.7  389.71
  4586.7  388.53  4616.7  387.27  4626.8  386.34  4636.8  386.22  4652.4  384.91
    4775  378.92  4780.9  379.19  4817.6  377.41    4885  376.79  4920.6  376.65
    4929  376.15  4952.9  375.54  4955.6  375.04  4958.9  375.54  5064.8  376.71
  5232.7  376.82  5414.1  377.46  5427.8  378.11  5632.5  380.54  5783.1  383.62
#Mann= 6 ,-1 , 0
  4265.9      .1       0    4411     .05       0  4652.4      .1       0
    4929     .05       0  4952.9     .03       0  4958.9     .05       0
Bank Sta=4885,5232.7
XS Rating Curve= 0 ,0
Exp/Cntr=0.3,0.1

Type RM Length L Ch R = 1 ,24021   ,286,286,286
BEGIN DESCRIPTION:
GATO CREEK 42.0
END DESCRIPTION:
XS GIS Cut Line= 2
      2210566.79     13180096.48      2210566.79     13178232.38
#Sta/Elev= 30
  3921.3  402.64  3930.9  401.77  3960.9  400.75  3970.9  399.52  4000.9  397.91
  4020.9  396.34  4030.9  394.63  4060.9  392.56  4133.4  389.11  4196.9  387.11
  4295.7  384.05  4350.9  381.77  4474.4  378.78  4530.9  378.47  4599.1  377.03
  4620.9  377.27  4730.9   375.4  4790.9  375.43  4885.8  375.28  5037.9  374.07
  5040.7  373.57  5043.9  374.07  5320.9  374.16  5410.9  375.24  5530.9  376.44
  5640.9   378.3  5670.9  379.95  5700.9   379.7  5754.5  380.69  5785.4  381.03
#Mann= 10 ,-1 , 0
  3921.3     .05       0  4133.4      .1       0  4196.9     .05       0
  4295.7      .1       0  4474.4     .05       0  4599.1      .1       0
  4885.8     .05       0  5037.9     .03       0  5043.9     .05       0
  5754.5     .08       0
Bank Sta=4790.9,5410.9
XS Rating Curve= 0 ,0
Exp/Cntr=0.3,0.1

Type RM Length L Ch R = 1 ,23735   ,489,489,489
BEGIN DESCRIPTION:
GATO CREEK 41.0
END DESCRIPTION:
XS GIS Cut Line= 2
      2210743.73     13180115.49      2210699.49     13178263.91
#Sta/Elev= 30
  3705.9  400.29  3724.5  397.87  3794.6  394.18  3804.6  393.18  3814.6  390.82
  3834.6  393.73  3896.5  392.65  3904.6  393.24  3934.6  391.56  4014.6  393.07
  4061.5  391.22  4094.4  389.81  4163.2  387.32  4214.7  384.22  4264.7  383.22
  4294.7  384.92  4314.7  383.16  4334.7   383.5  4514.8  377.33  4614.8  376.98
  4644.8  375.81  4664.8  376.83  4714.8   375.2  4804.8  374.43  5161.9  373.87
  5164.7  373.37  5167.9  373.87    5315  374.54  5380.6  374.84    5558  377.06
#Mann= 7 ,-1 , 0
  3705.9      .1       0  3896.5     .05       0  4061.5      .1       0
  4094.4     .05       0  5161.9     .04       0  5167.9     .05       0
  5380.6     .08       0
Bank Sta=4804.8,5315
XS Rating Curve= 0 ,0
Exp/Cntr=0.3,0.1

Type RM Length L Ch R = 1 ,23246   ,433,433,433
BEGIN DESCRIPTION:
GATO CREEK 40.0
END DESCRIPTION:
XS GIS Cut Line= 3
      2211287.72     13179346.83      2211087.72     13178546.86
       2210337.7     13177946.84
#Sta/Elev= 30
  4175.4  399.42  4226.9   395.8  4239.8  393.68  4276.3  390.39  4310.5  388.66
  4358.3  384.69  4517.4  376.89  4659.8  370.98  4729.8  369.38  4870.5  369.41
  4940.7  370.24  4994.4  368.84  4997.2  368.34  5000.4  368.84  5021.6  370.15
  5061.9  370.27    5100   370.6  5298.5  372.21  5395.4  374.24  5512.2  378.48
  5525.9  377.63  5604.3  380.18  5612.3  381.55  5688.8  383.73  5763.6  388.11
  5814.1  391.29  5825.2  392.88  5886.4  395.97  5946.9  397.63  5960.5  398.85
#Mann= 14 ,-1 , 0
  4175.4      .1       0  4276.3     .05       0  4310.5      .1       0
  4517.4     .05       0  4729.8      .1       0  4870.5     .12       0
  4994.4     .07       0  5000.4     .12       0  5061.9      .1       0
  5395.4     .08       0  5688.8     .05       0  5763.6     .08       0
  5814.1     .05       0  5886.4     .08       0
Bank Sta=4659.8,5100
XS Rating Curve= 0 ,0
Exp/Cntr=0.3,0.1

Type RM Length L Ch R = 1 ,22813   ,549,549,549
BEGIN DESCRIPTION:
GATO CREEK 39.0
END DESCRIPTION:
XS GIS Cut Line= 3
      2211387.72     13179496.85      2211387.72     13178296.85
      2211587.72     13177596.87
#Sta/Elev= 30
    3800  408.68    3910  402.93    3920   401.2  3965.3  397.53  4024.8  393.91
    4140  387.46    4190  383.59  4338.9  375.78    4390  372.84    4510  368.52
    4560  367.76    4577  366.28  4579.8  365.78    4583  366.28  4602.3  367.38
  4751.1  367.64    4790  368.42    4990  367.15  5016.9  368.29  5114.4  368.56
  5132.2  368.59  5274.3  370.94  5447.2  377.04    5520  380.32  5540.8  382.33
  5560.3  382.05  5565.5  383.16    5572  382.69  5604.5  385.43    5728  391.28
#Mann= 9 ,-1 , 0
    3800      .1       0  3965.3     .05       0  4024.8      .1       0
  4338.9     .05       0    4577     .07       0    4583     .05       0
  4602.3      .1       0  4751.1     .12       0  5132.2     .05       0
Bank Sta=4510,5114.4
XS Rating Curve= 0 ,0
Exp/Cntr=0.3,0.1

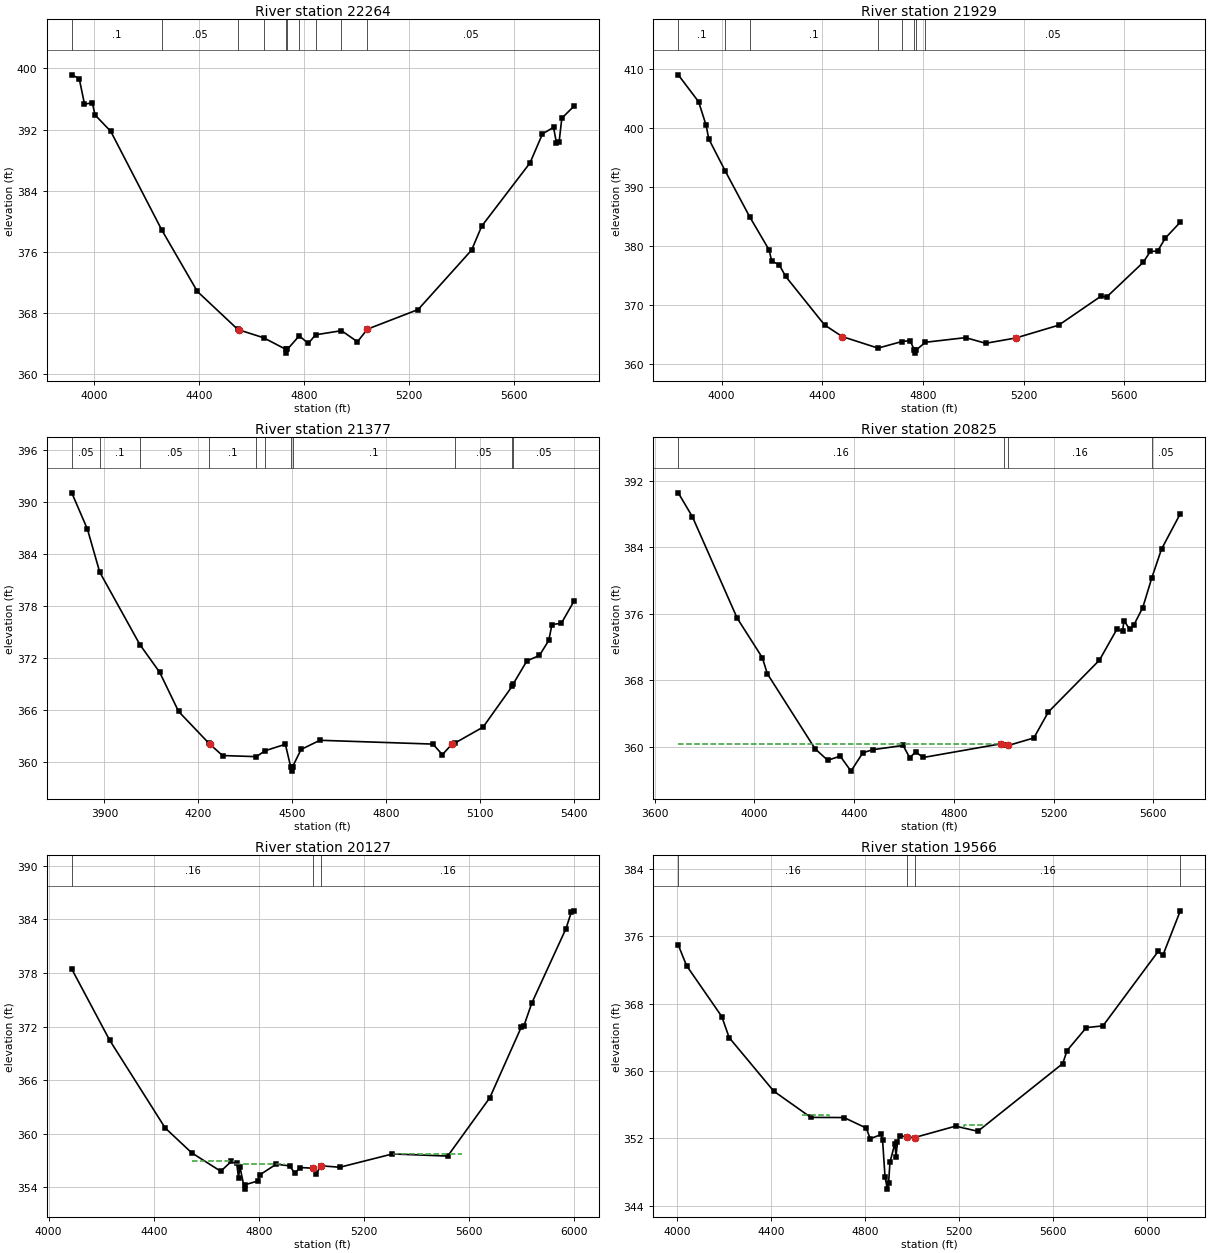
Type RM Length L Ch R = 1 ,22264   ,335,335,335
BEGIN DESCRIPTION:
GATO CREEK 38.0
END DESCRIPTION:
XS GIS Cut Line= 3
      2211857.89     13179405.34      2211864.83     13178113.66
      2211670.38     13177523.36
#Sta/Elev= 30
  3915.5  399.17    3944  398.66    3964  395.34    3994  395.49    4004  393.92
    4064  391.77  4258.6  378.84    4394   370.8    4548  365.83    4554  365.75
  4646.8  364.73    4731  363.22  4733.7  362.72    4737  363.22  4782.3  364.98
  4816.8  363.99  4844.5  365.12  4943.3  365.66    5004  364.21  5042.1  365.86
  5235.4  368.43  5439.2  376.22  5477.6  379.35  5661.6  387.63  5709.2  391.44
  5751.3  392.29  5762.2  390.29  5772.4  390.33  5782.9  393.49  5828.7  395.05
#Mann= 10 ,-1 , 0
  3915.5      .1       0  4258.6     .05       0    4548      .1       0
  4646.8     .12       0    4731     .07       0    4737     .12       0
  4782.3      .1       0  4844.5     .05       0  4943.3      .1       0
  5042.1     .05       0
Bank Sta=4554,5042.1
XS Rating Curve= 0 ,0
Exp/Cntr=0.3,0.1

Type RM Length L Ch R = 1 ,21929   ,552,552,552
BEGIN DESCRIPTION:
GATO CREEK 37.0
END DESCRIPTION:
XS GIS Cut Line= 3
      2212163.44     13179467.87      2212198.16      13177870.6
      2211982.86     13177537.23
#Sta/Elev= 30
  3827.5  409.03  3908.5  404.46  3938.5  400.44  3948.5  398.18  4014.7  392.68
  4110.7     385  4188.6  379.32  4198.6  377.45  4228.6  376.82    4254  374.85
  4408.7  366.61  4478.7  364.64  4621.1  362.68  4716.4   363.8  4748.7  363.95
  4765.7  362.33  4768.5  361.83  4771.7  362.33  4809.5  363.67  4968.8  364.46
  5048.8   363.5  5168.8   364.4  5338.9  366.57  5507.9  371.52  5529.1  371.33
  5674.2  377.21  5703.4   379.1  5731.6  379.11    5762  381.32    5822  384.04
#Mann= 8 ,-1 , 0
  3827.5      .1       0  4014.7     .05       0  4110.7      .1       0
  4621.1     .12       0  4716.4      .1       0  4765.7     .03       0
  4771.7      .1       0  4809.5     .05       0
Bank Sta=4478.7,5168.8
XS Rating Curve= 0 ,0
Exp/Cntr=0.3,0.1

Type RM Length L Ch R = 1 ,21377   ,552,552,552
BEGIN DESCRIPTION:
GATO CREEK 36.0
END DESCRIPTION:
XS GIS Cut Line= 3
      2212537.72      13179246.9      2212637.72     13178046.86
      2212637.72     13177646.86
#Sta/Elev= 30
  3795.8  391.03    3846  386.82  3885.1  381.88  4013.3  373.52  4076.8  370.31
    4137   365.8  4233.8  362.13  4237.4     362  4277.5  360.71  4385.1  360.58
  4414.2  361.27  4478.2  362.01  4495.3  359.41    4498  358.91  4501.3  359.41
  4528.4  361.41  4588.6  362.47  4949.8  362.03  4979.9  360.81    5010     362
  5021.8  362.19    5110  363.99  5202.8   368.7  5205.7  368.94    5250  371.63
    5290  372.26    5320     374    5330  375.83    5360  375.97    5400   378.5
#Mann= 11 ,-1 , 0
  3795.8     .05       0  3885.1      .1       0  4013.3     .05       0
  4233.8      .1       0  4385.1     .12       0  4414.2      .1       0
  4495.3     .07       0  4501.3      .1       0  5021.8     .05       0
  5202.8      .1       0  5205.7     .05       0
Bank Sta=4237.4,5010
XS Rating Curve= 0 ,0
Exp/Cntr=0.3,0.1

Type RM Length L Ch R = 1 ,20825   ,698,698,698
BEGIN DESCRIPTION:
GATO CREEK 35.0
END DESCRIPTION:
XS GIS Cut Line= 3
      2212975.95     13179391.42      2213177.33     13177801.16
      2213010.67     13177426.18
#Sta/Elev= 30
  3695.1  390.52  3752.1  387.63  3931.5  375.44  4032.3  370.69  4052.5  368.75
    4244  359.72  4294.4  358.35  4344.8  358.84  4387.7  357.04  4435.5  359.25
  4475.8  359.62  4596.8  360.13  4623.3  358.65  4647.2  359.35  4677.4  358.68
  4989.9  360.33    5000  360.21  5018.8  360.13    5121  361.03  5179.1  364.15
  5384.1  370.39  5453.8   374.1  5477.1  373.88  5482.5  375.16  5505.8  374.08
  5521.6  374.59  5557.8  376.71  5594.1  380.29    5633  383.75  5708.4  388.01
#Mann= 4 ,-1 , 0
  3695.1     .16       0    5000     .07       0  5018.8     .16       0
  5594.1     .05       0
#XS Ineff= 2 , 0
       0 4989.82  360.33               0
Permanent Ineff=
       T       F
Bank Sta=4989.9,5018.8
XS Rating Curve= 0 ,0
Exp/Cntr=0.3,0.1

Type RM Length L Ch R = 1 ,20127   ,561,561,561
BEGIN DESCRIPTION:
GATO CREEK 33.0
END DESCRIPTION:
XS GIS Cut Line= 3
      2213427.33     13179349.78      2213552.33     13178301.16
       2213531.5     13177446.96
#Sta/Elev= 30
  4088.2  378.44  4232.1  370.49  4443.6  360.65  4544.3  357.87  4655.1   355.8
  4695.4  356.91  4715.5  356.76  4722.8  355.09  4727.9  356.32  4745.5   353.8
  4748.7   354.3  4796.1  354.71  4805.4  355.43  4866.6   356.6    4917   356.4
  4937.1  355.59  4957.2  356.22  5007.6  356.14  5017.7  355.53  5037.8  356.41
  5108.3  356.25  5308.6  357.74  5518.7   357.5  5678.7  364.02  5798.7  371.94
  5808.7  372.09  5838.8  374.64  5968.8  382.97  5988.8  384.79  5998.7  384.96
#Mann= 3 , 0 , 0
  4088.2     .16       0  5007.6     .07       0  5037.8     .16       0
#XS Ineff= 3 ,-1
 4545.45 4705.68  356.96 4707.95 4894.32  356.66 5309.09 5573.86  357.75
Permanent Ineff=
       F       F       F
Bank Sta=5007.6,5037.8
XS Rating Curve= 0 ,0
Exp/Cntr=0.3,0.1

Type RM Length L Ch R = 1 ,19566   ,605,605,605
BEGIN DESCRIPTION:
GATO CREEK 32.0
END DESCRIPTION:
XS GIS Cut Line= 3
      2213760.65     13179342.86      2214239.83     13177898.38
      2214364.82     13177294.26
#Sta/Elev= 30
  4003.3  374.98  4038.8  372.52  4188.7  366.48  4220.3  363.97    4410  357.62
    4568   354.5  4709.4  354.48  4804.5  353.23  4820.9  351.96  4867.8  352.47
  4873.6  351.87  4884.1  347.47    4894  345.98  4899.5  346.76  4905.2  349.17
  4925.9  351.38  4931.2  349.84  4936.8  351.54  4947.3  352.34  4978.9  352.16
  5010.5  352.11  5184.7  353.46  5279.7  352.85  5641.2  360.89  5659.5  362.43
  5741.6  365.16  5812.7  365.37  6047.5   374.2    6068  373.76  6142.1  379.03
#Mann= 4 ,-1 , 0
  4003.3     .16       0  4978.9     .07       0  5010.5     .16       0
  6142.1      .1       0
#XS Ineff= 2 ,-1
 4530.23 4644.71  354.74 5221.72 5308.73   353.6
Permanent Ineff=
       F       F
Bank Sta=4978.9,5010.5
XS Rating Curve= 0 ,0
Exp/Cntr=0.3,0.1

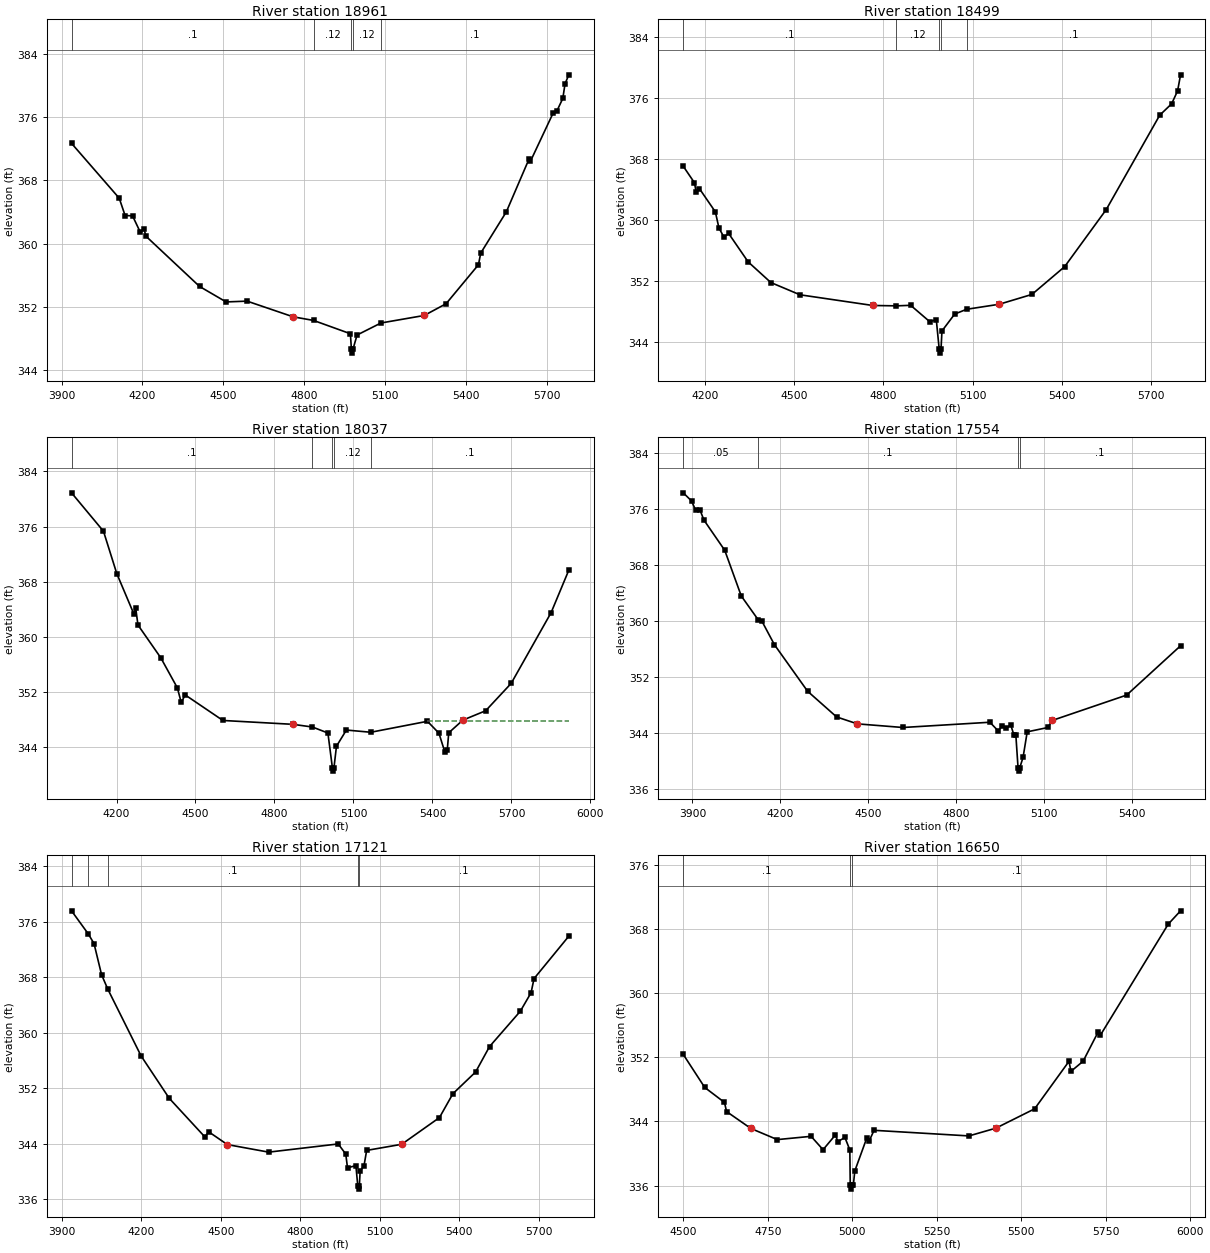
Type RM Length L Ch R = 1 ,18961   ,462,462,462
BEGIN DESCRIPTION:
GATO CREEK 31.0
END DESCRIPTION:
XS GIS Cut Line= 3
      2213887.73     13179346.84      2214587.72     13178546.86
      2214937.71     13177846.88
#Sta/Elev= 30
    3937  372.66    4114  365.73  4135.8  363.54  4163.4   363.5  4191.8  361.46
  4206.1  361.78  4213.7  360.91    4412  354.58  4510.7  352.62  4588.6  352.72
  4759.4  350.74  4835.3  350.28    4972   348.6  4975.6  346.65  4978.4  346.15
  4981.6  346.65  4996.7  348.44  5085.5  349.96    5246  350.91    5327  352.39
  5447.2  357.32  5455.6  358.79  5550.6     364  5634.5  370.65  5640.1  370.39
  5723.9  376.46  5737.9  376.73  5760.3  378.34  5768.6   380.2  5782.6  381.32
#Mann= 5 ,-1 , 0
    3937      .1       0  4835.3     .12       0  4975.6     .07       0
  4981.6     .12       0  5085.5      .1       0
Bank Sta=4759.4,5246
XS Rating Curve= 0 ,0
Exp/Cntr=0.3,0.1

Type RM Length L Ch R = 1 ,18499   ,462,462,462
BEGIN DESCRIPTION:
GATO CREEK 30.0
END DESCRIPTION:
XS GIS Cut Line= 3
      2214637.73     13179496.84      2214987.72     13178696.86
      2214987.72     13177896.86
#Sta/Elev= 30
  4126.8  367.02  4164.6  364.85  4170.4  363.58  4181.4  364.07  4234.8  361.04
  4246.9  358.92  4263.6  357.73  4279.6   358.2  4345.1  354.48  4421.5  351.77
  4519.7  350.16  4764.2  348.76  4844.1  348.71    4892  348.78  4956.3  346.63
  4978.2  346.89    4988  343.01  4990.8  342.51    4994  343.01  4997.3  345.42
    5040  347.63  5080.1  348.26    5190  348.92    5300  350.21    5410  353.85
    5550  361.34    5730  373.72    5770  375.21    5790   376.9    5800  379.01
#Mann= 5 ,-1 , 0
  4126.8      .1       0  4844.1     .12       0    4988     .07       0
    4994     .12       0  5080.1      .1       0
Bank Sta=4764.2,5190
XS Rating Curve= 0 ,0
Exp/Cntr=0.3,0.1

Type RM Length L Ch R = 1 ,18037   ,483,483,483
BEGIN DESCRIPTION:
GATO CREEK 29.0
END DESCRIPTION:
XS GIS Cut Line= 3
      2214737.73     13179746.83      2215287.72     13178946.85
      2216087.74     13178496.84
#Sta/Elev= 30
  4029.2   380.9  4150.5  375.33    4201  369.19  4266.6  363.26  4272.7  364.23
  4281.5  361.72  4368.1  356.97    4431  352.61  4445.9  350.48  4460.8  351.58
  4604.2  347.87  4870.1  347.31  4944.1  346.92  5002.9  346.05  5019.9  341.02
  5022.7  340.52  5025.9  341.02  5035.4  344.13    5073  346.48  5165.8  346.16
  5380.9  347.75  5424.5  346.03  5447.5  343.23  5456.1  343.54  5461.8  346.08
  5515.4  347.92    5602  349.28  5698.9  353.25  5850.6  363.52  5917.9  369.69
#Mann= 5 ,-1 , 0
  4029.2      .1       0  4944.1     .12       0  5019.9     .07       0
  5025.9     .12       0  5165.8      .1       0
#XS Ineff= 2 , 0
                         5381.04          347.75
Permanent Ineff=
       F       F
Bank Sta=4870.1,5515.4
XS Rating Curve= 0 ,0
Exp/Cntr=0.3,0.1

Type RM Length L Ch R = 1 ,17554   ,433,433,433
BEGIN DESCRIPTION:
GATO CREEK 28.0
END DESCRIPTION:
XS GIS Cut Line= 3
       2214887.7     13179946.88      2215687.72     13179146.85
      2216087.73     13178746.84
#Sta/Elev= 30
  3868.6  378.36  3896.9   377.2  3911.1  375.85  3925.2  375.96  3939.3  374.46
  4010.1  370.16  4066.6  363.63  4124.4  360.23  4137.3  360.01  4179.8  356.67
  4292.9  350.03  4391.9  346.36  4462.6  345.37  4618.2  344.85  4915.1   345.6
  4943.4  344.36  4957.6  345.11  4971.7  344.72  4985.9  345.25  4996.5  343.85
  5003.5  343.85  5011.1  339.12  5013.9  338.62  5017.1  339.12  5028.3  340.59
  5042.4  344.23  5113.1  344.85  5127.3  345.85  5381.8  349.48  5565.7  356.52
#Mann= 4 ,-1 , 0
  3868.6     .05       0  4124.4      .1       0  5011.1     .07       0
  5017.1      .1       0
Bank Sta=4462.6,5127.3
XS Rating Curve= 0 ,0
Exp/Cntr=0.3,0.1

Type RM Length L Ch R = 1 ,17121   ,471,471,471
BEGIN DESCRIPTION:
GATO CREEK 27.0
END DESCRIPTION:
XS GIS Cut Line= 3
      2215037.73     13180196.85      2215837.72     13179496.85
      2216637.68     13179346.86
#Sta/Elev= 30
    3937  377.55  4000.1  374.23  4021.9  372.83  4050.4  368.34  4073.8  366.27
  4199.4  356.65  4305.7  350.54  4440.5  344.96  4454.7  345.71    4525  343.87
  4681.1  342.78  4943.5  343.96    4972   342.5  4978.6  340.52  5010.2  340.84
  5017.3  337.95  5020.1  337.45  5023.3  337.95  5026.3  340.07  5040.7   340.8
  5050.9  343.03  5183.1  343.91  5325.6  347.76  5376.4   351.2  5462.1  354.33
  5514.6  357.99  5630.8  363.08  5671.5  365.76  5682.5  367.78  5813.9   373.9
#Mann= 5 ,-1 , 0
    3937      .1       0  4000.1     .08       0  4073.8      .1       0
  5017.3     .07       0  5023.3      .1       0
Bank Sta=4525,5183.1
XS Rating Curve= 0 ,0
Exp/Cntr=0.3,0.1

Type RM Length L Ch R = 1 ,16650   ,470,470,470
BEGIN DESCRIPTION:
GATO CREEK 26.0
END DESCRIPTION:
XS GIS Cut Line= 3
      2215387.72     13180246.85      2215787.72     13179946.85
       2216587.7     13179396.87
#Sta/Elev= 30
    4500  352.36  4563.5  348.24  4621.9  346.37  4628.1  345.23    4700  343.12
  4778.1  341.73  4878.1  342.14  4913.5  340.47    4950  342.31  4957.3  341.48
  4978.1     342  4992.7  340.44  4993.9  336.05  4996.6  335.55  4999.9  336.05
    5003  336.05  5007.4  337.82  5043.3  341.99  5049.4  341.52  5064.3  342.89
    5345  342.19  5424.7  343.16  5539.2  345.57  5640.7  351.49  5646.8  350.25
  5682.6  351.51  5727.3  355.18  5733.4  354.74  5934.4  368.62  5970.8  370.28
#Mann= 3 ,-1 , 0
    4500      .1       0  4993.9     .07       0  4999.9      .1       0
Bank Sta=4700,5424.7
XS Rating Curve= 0 ,0
Exp/Cntr=0.3,0.1