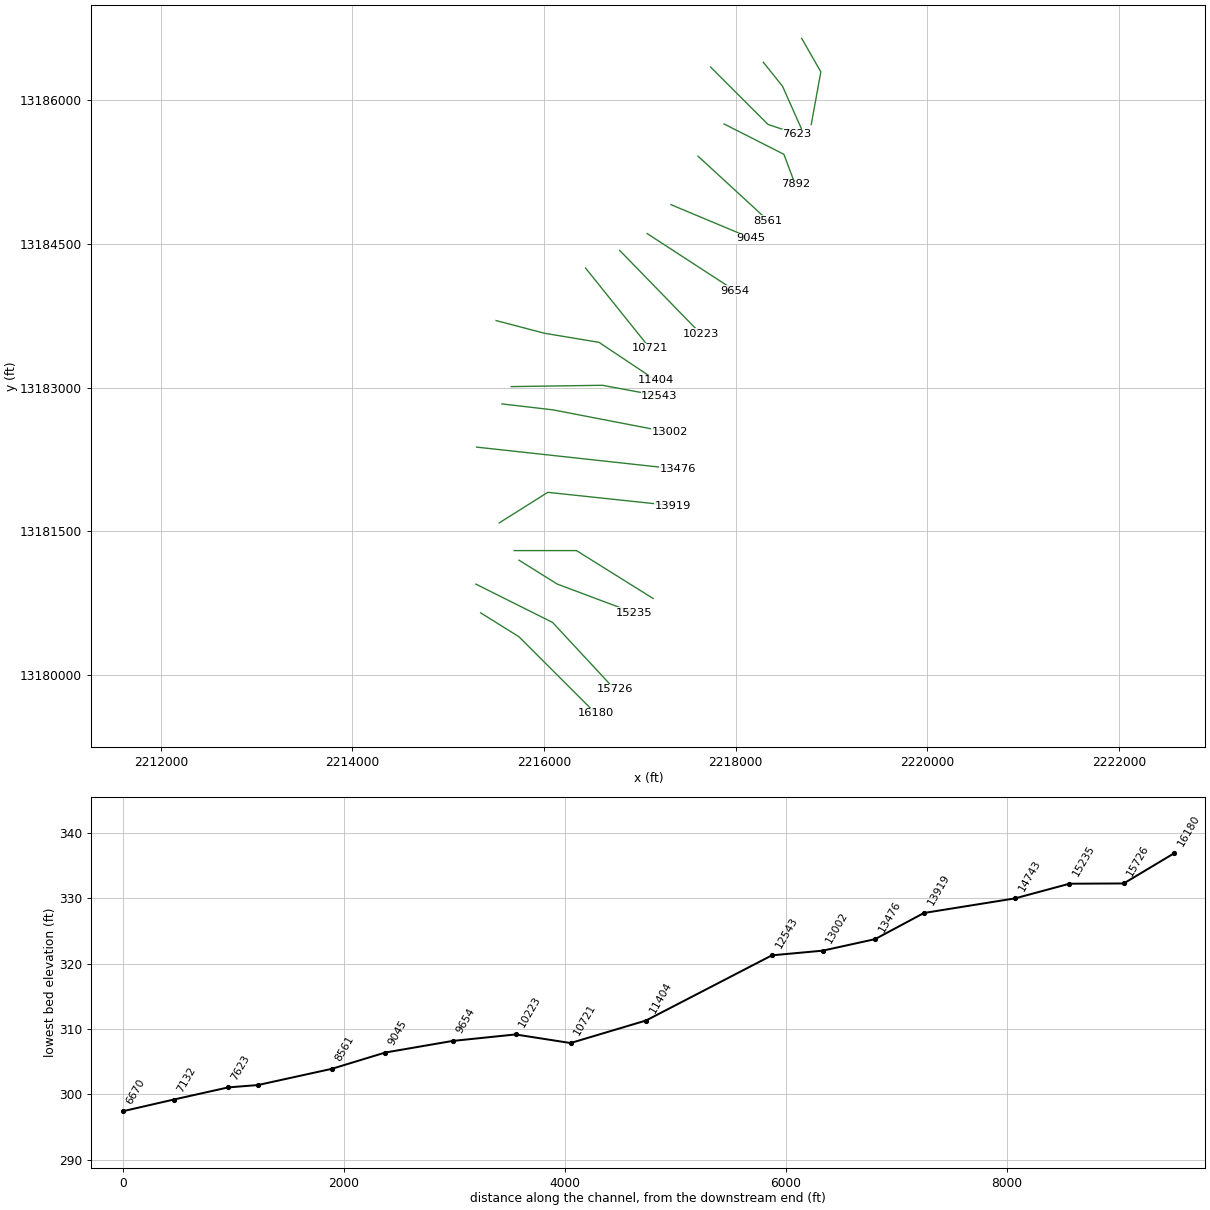
HEC-RAS study GATO CREEK.prj: GATO CREEK Base Level Engineering

--- GATO CREEK.g01 (geometry) --- (continued)

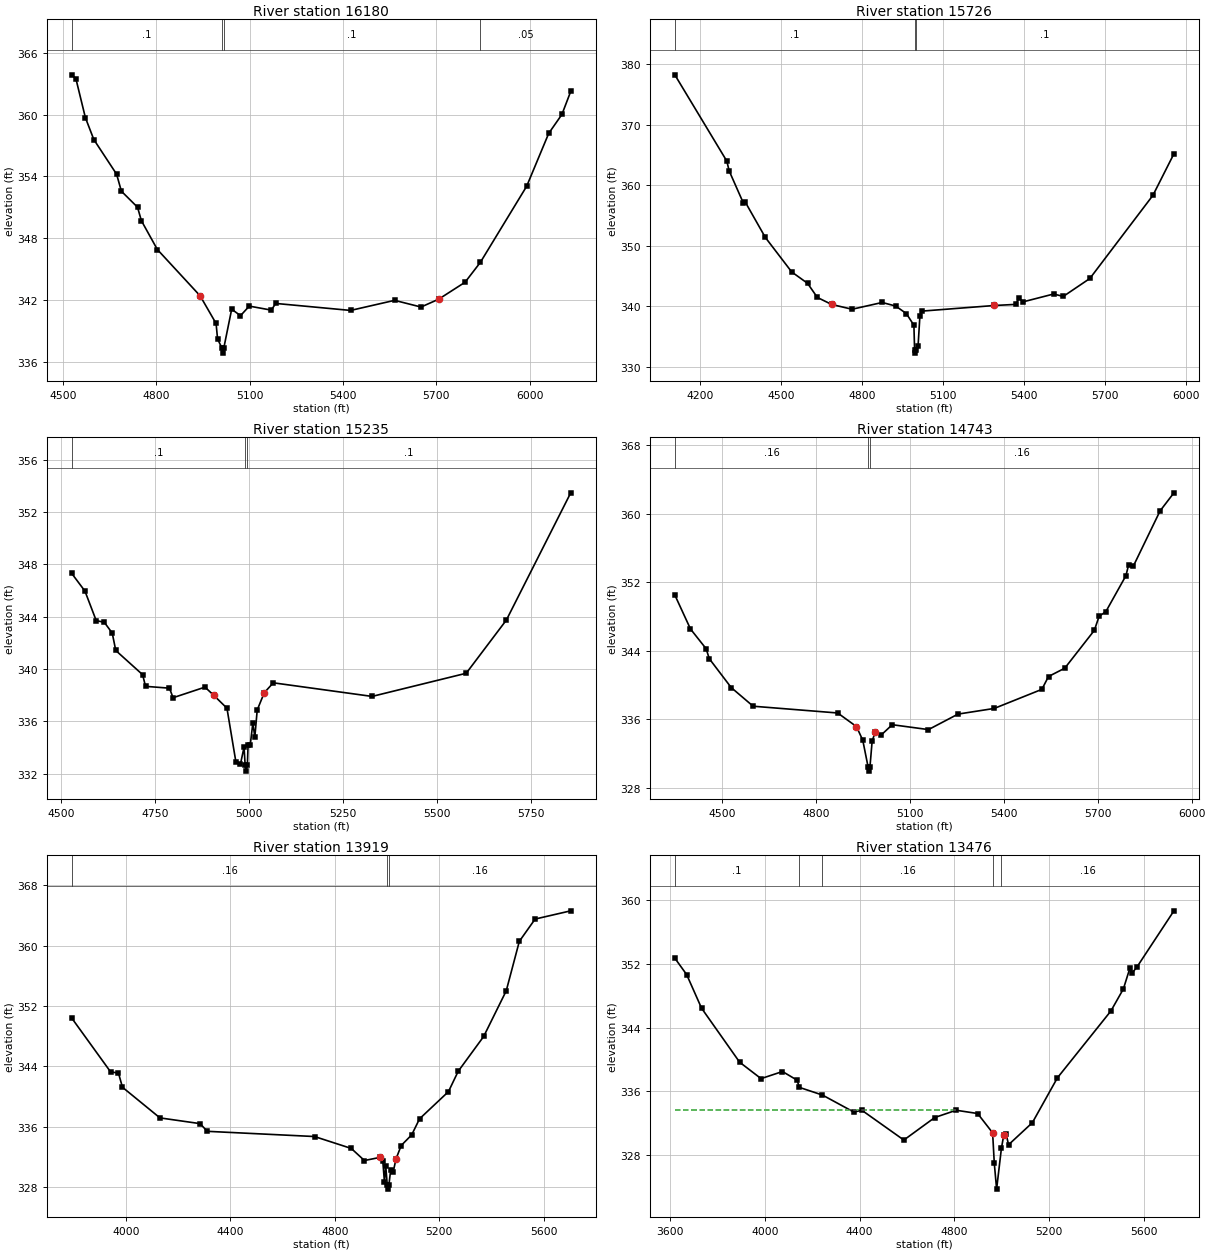
Type RM Length L Ch R = 1 ,16180   ,454,454,454
BEGIN DESCRIPTION:
GATO CREEK 25.0
END DESCRIPTION:
XS GIS Cut Line= 3
      2215337.72     13180646.86      2215737.72     13180396.85
      2216537.74     13179596.83
#Sta/Elev= 30
  4528.3  363.88  4541.9  363.52  4572.5  359.72  4599.6  357.59  4672.8  354.22
  4688.1  352.57    4740  351.01  4752.4   349.7  4803.7   346.9    4941   342.4
  4992.3  339.71  4997.1   338.2  5011.1  337.33  5013.9  336.83  5017.1  337.33
  5042.4   341.1  5070.7  340.47    5099   341.4  5169.7  341.01  5183.8  341.66
  5424.3  340.98  5565.7  341.96  5650.5  341.31  5707.1  342.07    5792  343.72
  5841.1  345.65  5989.9  353.05  6060.7  358.19  6103.1  360.03  6131.4  362.27
#Mann= 4 ,-1 , 0
  4528.3      .1       0  5011.1     .07       0  5017.1      .1       0
  5841.1     .05       0
Bank Sta=4941,5707.1
XS Rating Curve= 0 ,0
Exp/Cntr=0.3,0.1

Type RM Length L Ch R = 1 ,15726   ,491,491,491
BEGIN DESCRIPTION:
GATO CREEK 24.0
END DESCRIPTION:
XS GIS Cut Line= 3
      2215287.74     13180946.84      2216087.72     13180546.85
      2216737.69     13179846.89
#Sta/Elev= 30
  4105.6  378.28  4298.4     364  4306.8  362.41  4359.9  357.04  4365.5  357.32
    4441  351.38  4538.8  345.67  4597.5  343.79  4633.8  341.45    4687  340.29
  4762.4   339.5  4874.2  340.62  4924.5  340.02  4963.7  338.78  4991.6  336.85
  4994.2  332.74    4997  332.24  5000.2  332.74  5007.1  333.47  5013.9  338.43
  5021.3  339.19    5290  340.12  5368.2   340.3  5382.1  341.35    5396  340.72
  5509.4  342.02  5545.1  341.62  5643.7  344.59  5877.3  358.34  5955.2  365.22
#Mann= 3 ,-1 , 0
  4105.6      .1       0  4994.2     .07       0  5000.2      .1       0
Bank Sta=4687,5290
XS Rating Curve= 0 ,0
Exp/Cntr=0.3,0.1

Type RM Length L Ch R = 1 ,15235   ,492,492,492
BEGIN DESCRIPTION:
GATO CREEK 23.0
END DESCRIPTION:
XS GIS Cut Line= 3
      2215737.72     13181196.86      2216137.72     13180946.85
      2216937.72     13180646.86
#Sta/Elev= 30
  4528.3  347.32  4563.7  345.96  4593.7   343.7    4615  343.58  4636.2  342.75
  4645.6  341.42    4717  339.57  4724.6  338.68  4788.3  338.54  4797.8  337.81
  4882.7  338.62  4905.7     338    4941  337.01  4964.6  332.93    4977  332.75
  4986.4  334.03  4989.3   332.7  4992.1   332.2  4995.3   332.7  4997.1  334.16
  5002.7  334.16  5009.8  335.86  5015.1  334.81  5021.4  336.87  5040.1  338.19
  5064.1  338.95  5326.6  337.91  5576.7  339.68  5683.5  343.75  5854.4  353.47
#Mann= 3 ,-1 , 0
  4528.3      .1       0  4989.3     .07       0  4995.3      .1       0
Bank Sta=4905.7,5040.1
XS Rating Curve= 0 ,0
Exp/Cntr=0.3,0.1

Type RM Length L Ch R = 1 ,14743   ,824,824,824
BEGIN DESCRIPTION:
GATO CREEK 22.0
END DESCRIPTION:
XS GIS Cut Line= 3
      2215687.72     13181296.85      2216337.72     13181296.85
      2217137.72     13180796.85
#Sta/Elev= 30
    4350  350.53    4400  346.56    4450  344.25    4460  343.09    4530  339.72
    4600  337.54    4870  336.75    4930  335.16    4950  333.57    4967  330.46
  4969.8  329.96    4973  330.46    4980  333.49    4990  334.51  5007.7  334.14
  5044.2  335.38  5159.8  334.81  5254.1  336.62  5369.7  337.28  5521.8  339.51
    5543  341.01  5594.9  341.98  5689.3   346.4  5704.6  348.05  5725.8  348.57
  5790.1  352.78  5798.9  354.07  5813.7  353.89  5899.2  360.35  5943.4  362.46
#Mann= 3 ,-1 , 0
    4350     .16       0    4967     .07       0    4973     .16       0
Bank Sta=4930,4990
XS Rating Curve= 0 ,0
Exp/Cntr=0.3,0.1

Type RM Length L Ch R = 1 ,13919   ,443,443,443
BEGIN DESCRIPTION:
GATO CREEK 21.0
END DESCRIPTION:
XS GIS Cut Line= 3
       2215531.5     13181585.88      2216038.44     13181905.33
      2217343.38      13181766.5
#Sta/Elev= 30
  3792.2  350.42  3941.4  343.27  3971.6  343.11  3986.9  341.23  4130.5  337.17
  4284.2  336.41  4311.8  335.39  4722.5   334.7  4863.3  333.12  4913.6  331.52
  4973.9  331.94    4984  331.43  4990.2  328.72  4995.2  330.83  5001.1  328.23
  5003.9  327.73  5007.1  328.23  5014.2  330.28  5024.2  330.06  5034.3   331.7
  5054.4  333.51  5094.6  334.92  5124.8  337.05  5235.4  340.65  5272.8  343.35
  5370.3  347.96  5456.7  354.01  5506.9  360.57  5567.3  363.52  5703.7  364.61
#Mann= 3 ,-1 , 0
  3792.2     .16       0  5001.1     .07       0  5007.1     .16       0
Bank Sta=4973.9,5034.3
XS Rating Curve= 0 ,0
Exp/Cntr=0.3,0.1

Type RM Length L Ch R = 1 ,13476   ,474,474,474
BEGIN DESCRIPTION:
GATO CREEK 20.0
END DESCRIPTION:
XS GIS Cut Line= 2
      2215295.36     13182377.55      2217392.57     13182148.39
#Sta/Elev= 30
  3618.8  352.72  3668.8  350.66  3731.8  346.44  3892.8  339.66  3983.3   337.6
  4073.9  338.49  4135.4  337.41  4145.3   336.5  4242.7  335.54  4375.6   333.4
  4409.3  333.63  4586.9  329.89  4717.7  332.72  4808.2  333.63  4898.7  333.22
  4962.1   330.8  4969.2  326.96    4979  323.73  4999.3  328.85  5009.4  330.54
  5019.5   330.6  5029.5   329.3  5130.1  332.07    5236   337.7  5462.1  346.09
  5514.9  348.86  5542.5  351.48  5552.6  350.88  5572.7  351.63  5728.5  358.66
#Mann= 5 ,-1 , 0
  3618.8      .1       0  4145.3     .16       0  4242.7     .16       0
  4962.1     .07       0  4999.3     .16       0
#XS Ineff= 2 , 0
       0 4808.24  333.67               0
Permanent Ineff=
       T       F
Bank Sta=4962.1,5009.4
XS Rating Curve= 0 ,0
Exp/Cntr=0.3,0.1

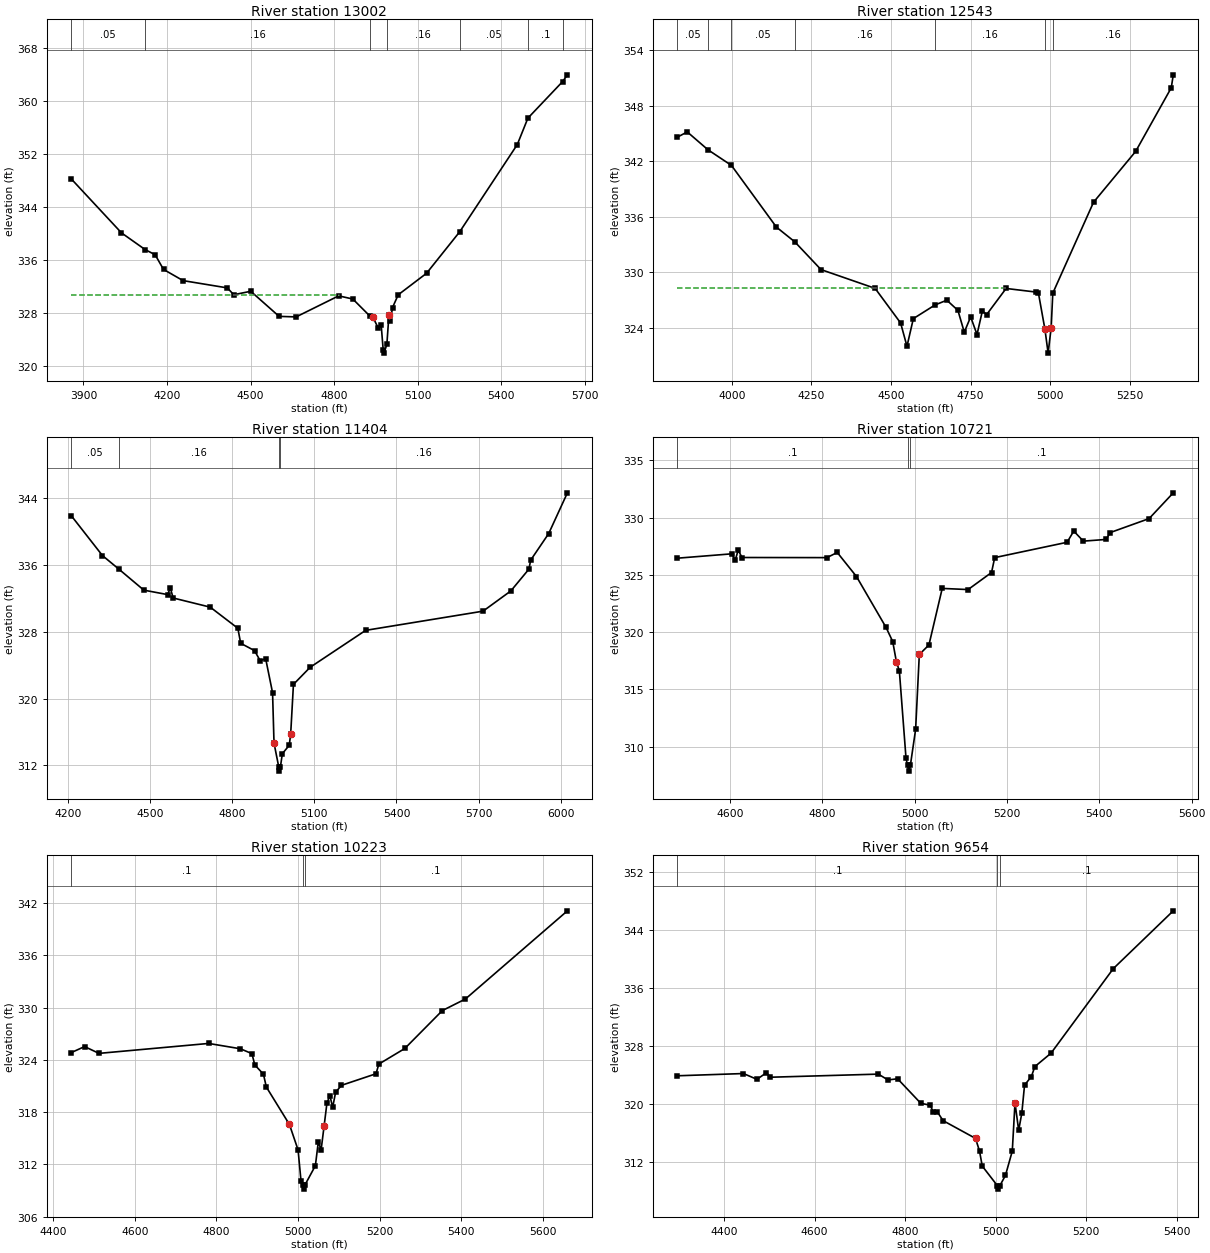
Type RM Length L Ch R = 1 ,13002   ,459,459,459
BEGIN DESCRIPTION:
Mapping XS 9468cad7
END DESCRIPTION:
XS GIS Cut Line= 3
      2215559.24     13182828.94        2216094.     13182766.44
      2217314.43     13182530.67
#Sta/Elev= 30
  3856.9  348.25  4036.6  340.13  4121.4  337.61  4157.4  336.83  4187.6  334.61
  4257.8  332.92  4416.9  331.82  4439.8  330.79  4500.9  331.31  4602.8  327.52
  4663.9  327.44  4816.7  330.62  4867.6  330.14  4928.7  327.57  4938.9  327.48
  4959.3  325.71  4969.4  326.21  4976.6  322.47  4979.4  321.97  4989.8  323.28
  4997.2   327.7  5002.2  326.82  5010.2  328.86  5030.6  330.78  5132.4  334.03
  5251.7  340.31  5458.3  353.47  5496.4  357.46  5621.3  362.99  5638.3     364
#Mann= 7 ,-1 , 0
  3856.9     .05       0  4121.4     .16       0  4928.7     .07       0
  4989.8     .16       0  5251.7     .05       0  5496.4      .1       0
  5621.3     .05       0
#XS Ineff= 2 , 0
       0 4816.76   330.7               0
Permanent Ineff=
       T       F
Bank Sta=4938.9,4997.2
XS Rating Curve= 0 ,0
Exp/Cntr=0.3,0.1

Type RM Length L Ch R = 1 ,12543   ,1139,1139,1139
BEGIN DESCRIPTION:
GATO CREEK 19.0
END DESCRIPTION:
XS GIS Cut Line= 3
      2215656.54     13183009.49      2216607.89     13183023.38
      2217203.92     13182912.49
#Sta/Elev= 30
  3828.7   344.6  3859.9  345.17  3924.9  343.24  3998.7  341.55  4139.9  334.88
  4197.6  333.29  4279.9  330.29  4449.9  328.26    4530  324.52    4550     322
    4570  324.99  4638.3  326.47  4675.2  326.98    4710  325.88    4730  323.52
    4750  325.18    4770  323.27  4786.8  325.82  4800.3  325.43  4861.3  328.25
  4955.2  327.86  4963.1  327.71  4983.4  323.82  4993.3  321.26  5002.9  324.01
    5008  327.74    5136  337.57  5268.2  343.06  5380.1  349.94  5386.4  351.34
#Mann= 7 ,-1 , 0
  3828.7     .05       0  3924.9      .1       0  3998.7     .05       0
  4197.6     .16       0  4638.3     .16       0  4983.4     .07       0
    5008     .16       0
#XS Ineff= 2 , 0
       0  4861.4  328.25               0
Permanent Ineff=
       T       F
Bank Sta=4983.4,5002.9
XS Rating Curve= 0 ,0
Exp/Cntr=0.3,0.1

Type RM Length L Ch R = 1 ,11404   ,683,683,683
BEGIN DESCRIPTION:
GATO CREEK 18.0
END DESCRIPTION:
XS GIS Cut Line= 4
       2215498.6     13183699.23      2216006.06     13183566.25
      2216573.06     13183471.75      2217163.68     13183076.83
#Sta/Elev= 30
  4213.8   341.9  4326.8  337.15  4385.7  335.55    4478     333  4564.4  332.47
  4574.7  333.25    4585  332.06  4720.4  330.96    4821  328.43  4831.3  326.63
  4881.9  325.75  4902.3  324.55  4922.6  324.77  4947.7   320.7    4953  314.66
  4970.3   311.8    4973   311.3  4976.3   311.8  4983.4  313.39  5008.6   314.4
  5013.8  315.74  5023.9   321.7  5084.8  323.75  5287.5  328.18  5715.8  330.48
  5817.4  332.91  5883.5  335.53  5889.5  336.59  5955.5  339.79  6023.7  344.67
#Mann= 4 ,-1 , 0
  4213.8     .05       0  4385.7     .16       0  4970.3     .07       0
  4976.3     .16       0
Bank Sta=4953,5013.8
XS Rating Curve= 0 ,0
Exp/Cntr=0.3,0.1

Type RM Length L Ch R = 1 ,10721   ,498,498,498
BEGIN DESCRIPTION:
GATO CREEK 17.0
END DESCRIPTION:
XS GIS Cut Line= 2
      2216432.42     13184247.53      2217104.47     13183409.91
#Sta/Elev= 30
  4486.3  326.46  4603.8  326.84  4611.8  326.31  4618.2  327.17  4626.2  326.52
  4810.2  326.51  4832.6  326.96  4874.2  324.86  4938.3  320.41  4952.7  319.18
  4960.6  317.43  4967.1   316.6  4981.5  308.98  4984.9  308.36  4987.6  307.86
  4990.9  308.36  5002.3  311.51  5010.3  318.05  5031.1  318.88  5059.9  323.82
  5115.9  323.72  5166.7  325.21  5173.5  326.51  5330.3  327.85  5344.7  328.83
  5365.5  327.95  5415.1   328.1  5423.1  328.69  5507.9  329.92  5560.2  332.17
#Mann= 3 ,-1 , 0
  4486.3      .1       0  4984.9     .07       0  4990.9      .1       0
Bank Sta=4960.6,5010.3
XS Rating Curve= 0 ,0
Exp/Cntr=0.3,0.1

Type RM Length L Ch R = 1 ,10223   ,569,569,569
BEGIN DESCRIPTION:
GATO CREEK 15.0
END DESCRIPTION:
XS GIS Cut Line= 2
      2216787.92     13184432.57      2217635.29     13183560.86
#Sta/Elev= 30
  4444.5  324.85  4476.7  325.53    4512  324.75  4780.8  325.89  4858.5  325.28
  4886.8  324.72    4894  323.42  4915.1  322.36  4922.2  320.89  4978.8  316.59
    5000  313.67  5007.1  310.15  5011.1  309.67  5013.8  309.17  5017.1  309.67
  5042.4  311.86  5049.6  314.59  5056.5  313.69  5063.7  316.38  5070.7  319.03
  5077.9  319.91  5084.8  318.56    5092  320.28  5106.2  321.08    5191  322.41
    5198  323.52  5261.6  325.31  5353.6  329.66  5410.2  330.99  5660.2  341.11
#Mann= 3 ,-1 , 0
  4444.5      .1       0  5011.1     .07       0  5017.1      .1       0
Bank Sta=4978.8,5063.7
XS Rating Curve= 0 ,0
Exp/Cntr=0.3,0.1

Type RM Length L Ch R = 1 ,9654    ,609,609,609
BEGIN DESCRIPTION:
GATO CREEK 14.0
END DESCRIPTION:
XS GIS Cut Line= 2
      2217075.25     13184607.88      2217994.18     13184009.84
#Sta/Elev= 30
  4296.4  323.86  4442.5  324.17  4472.4  323.37  4493.5  324.29  4502.2  323.66
  4740.8  324.09  4762.2  323.28  4783.3  323.45  4834.7  320.05  4855.8  319.79
  4861.8  318.86  4870.9  318.89    4884  317.65  4955.6   315.2  4964.5  313.44
  4970.5  311.37  5003.7  308.68  5006.4  308.18  5009.7  308.68  5021.8  310.08
  5036.9  313.44  5042.9  320.12    5051  316.32    5058   318.7    5064  322.57
  5079.1  323.75  5086.8  325.13  5122.6  326.99  5260.3  338.69  5392.8  346.68
#Mann= 3 ,-1 , 0
  4296.4      .1       0  5003.7     .07       0  5009.7      .1       0
Bank Sta=4955.6,5042.9
XS Rating Curve= 0 ,0
Exp/Cntr=0.3,0.1

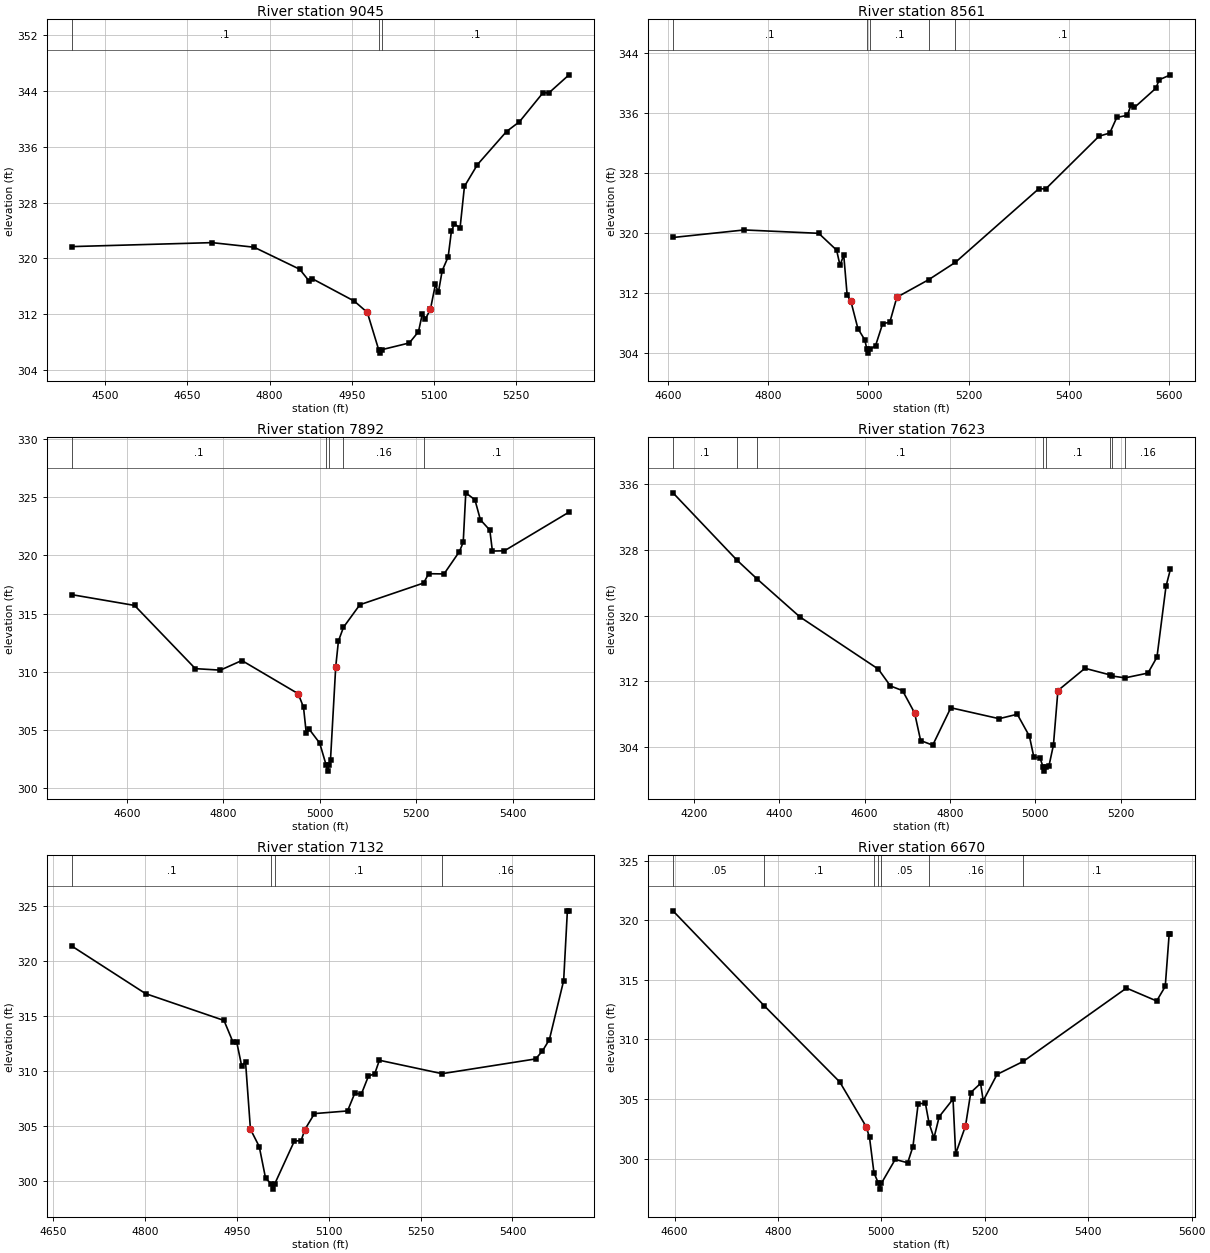
Type RM Length L Ch R = 1 ,9045    ,484,484,484
BEGIN DESCRIPTION:
GATO CREEK 13.0
END DESCRIPTION:
XS GIS Cut Line= 2
      2217323.57     13184909.82      2218161.24     13184559.17
#Sta/Elev= 30
  4438.4  321.69  4694.9  322.26  4771.7   321.6  4854.9  318.44  4872.3  316.73
  4877.7  317.09  4954.5  313.87  4978.3  312.25    4999  306.91  5001.8  306.41
    5005  306.91    5055  307.87  5071.7  309.49  5078.8  312.08  5084.3  311.31
  5093.4  312.68  5102.6  316.26    5108  315.12    5115  318.24  5125.9  320.23
  5131.8  323.91  5137.3  324.94  5147.6  324.38  5155.6  330.33  5179.4  333.46
  5232.4   338.2    5256   339.6  5299.3  343.79  5309.2   343.7  5346.5  346.33
#Mann= 3 ,-1 , 0
  4438.4      .1       0    4999     .07       0    5005      .1       0
Bank Sta=4978.3,5093.4
XS Rating Curve= 0 ,0
Exp/Cntr=0.3,0.1

Type RM Length L Ch R = 1 ,8561    ,669,669,669
BEGIN DESCRIPTION:
GATO CREEK 12.0
END DESCRIPTION:
XS GIS Cut Line= 2
      2217606.05     13185416.25      2218336.54     13184744.21
#Sta/Elev= 30
    4610  319.38  4752.2  320.39  4900.8  319.94  4936.5  317.69  4943.3  315.65
  4950.7  317.05  4957.5   311.7  4964.9  310.87    4979   307.2  4992.7   305.7
    4997  304.42  4999.8  303.92    5003  304.42  5014.2  304.92  5028.4  307.87
  5042.6  308.04  5056.7  311.39  5120.2  313.74  5173.7  316.07  5339.7  325.89
  5353.9  325.89    5460  332.92  5481.5  333.35  5495.5  335.43  5516.7  335.72
  5523.5  337.03  5530.8  336.77  5573.4  339.33  5580.2  340.47  5602.6  341.13
#Mann= 5 ,-1 , 0
    4610      .1       0    4997     .07       0    5003      .1       0
  5120.2     .16       0  5173.7      .1       0
Bank Sta=4964.9,5056.7
XS Rating Curve= 0 ,0
Exp/Cntr=0.3,0.1

Type RM Length L Ch R = 1 ,7892    ,269,269,269
BEGIN DESCRIPTION:
GATO CREEK 11.0
END DESCRIPTION:
XS GIS Cut Line= 3
      2217878.71     13185752.29      2218502.07     13185435.74
      2218618.95     13185124.06
#Sta/Elev= 30
  4485.2  316.63  4615.9   315.7    4742  310.26  4793.9  310.13  4838.5  310.96
  4955.4   308.1  4966.4  306.94    4972  304.75  4977.6  305.08    5000  303.85
  5013.5  301.94  5016.3  301.44  5019.5  301.94  5022.4  302.43  5033.2  310.41
  5038.8  312.63  5049.3  313.82  5083.3  315.76  5215.7  317.63  5225.9  318.43
  5257.9  318.41  5289.9  320.34  5297.7  321.14    5303  325.39    5322  324.79
  5333.3  323.07  5352.9  322.18  5358.2  320.38  5383.1   320.4  5517.2  323.73
#Mann= 5 ,-1 , 0
  4485.2      .1       0  5013.5     .07       0  5019.5      .1       0
  5049.3     .16       0  5215.7      .1       0
Bank Sta=4955.4,5033.2
XS Rating Curve= 0 ,0
Exp/Cntr=0.3,0.1

Type RM Length L Ch R = 1 ,7623    ,491,491,491
BEGIN DESCRIPTION:
GATO CREEK 10.0
END DESCRIPTION:
XS GIS Cut Line= 3
      2217737.74     13186346.83      2218337.72     13185746.86
      2218637.69     13185646.86
#Sta/Elev= 30
  4151.5  334.94  4300.9  326.77  4349.1  324.43  4448.5  319.85  4632.3  313.49
  4660.6  311.44  4688.9  310.88  4717.2  308.16  4731.3   304.8  4759.6  304.24
    4802  308.79  4915.1  307.46  4957.6     308  4985.9  305.34  4996.5  302.76
  5010.5  302.72  5018.1  301.58  5020.8  301.08  5024.1  301.58  5031.6  301.68
  5042.2  304.25  5052.7  310.88    5116  313.59  5173.9   312.8  5179.1  312.65
  5210.1  312.43  5263.5  313.01  5284.6  314.95  5305.7  323.55  5316.2  325.66
#Mann= 8 ,-1 , 0
  4151.5      .1       0  4300.9     .05       0  4349.1      .1       0
  5018.1     .07       0  5024.1      .1       0  5173.9     .16       0
  5179.1      .1       0  5210.1     .16       0
Bank Sta=4717.2,5052.7
XS Rating Curve= 0 ,0
Exp/Cntr=0.3,0.1

Type RM Length L Ch R = 1 ,7132    ,462,462,462
BEGIN DESCRIPTION:
GATO CREEK 9.0
END DESCRIPTION:
XS GIS Cut Line= 3
      2218287.69     13186396.89      2218487.72     13186146.85
       2218687.7     13185696.89
#Sta/Elev= 30
  4679.8  321.35  4800.7  317.01  4928.8  314.57  4943.2  312.64  4949.6   312.6
  4957.6  310.46    4964   310.8    4972  304.68  4986.4   303.1  4996.8   300.2
  5005.9  299.73  5008.6  299.23  5011.9  299.73  5043.8  303.61  5054.7  303.63
  5060.9  304.65  5076.6   306.1  5130.6  306.34  5142.3  307.93  5153.2  307.88
  5164.8  309.51  5175.1  309.73  5182.6  310.95    5285  309.73  5437.7  311.07
  5448.7  311.77  5460.3  312.83  5483.6  318.19  5489.7  324.54  5492.4  324.54
#Mann= 4 ,-1 , 0
  4679.8      .1       0  5005.9     .07       0  5011.9      .1       0
    5285     .16       0
Bank Sta=4972,5060.9
XS Rating Curve= 0 ,0
Exp/Cntr=0.3,0.1

Type RM Length L Ch R = 1 ,6670    ,471,471,471
BEGIN DESCRIPTION:
GATO CREEK 8.0
END DESCRIPTION:
XS GIS Cut Line= 3
      2218687.73     13186646.84      2218887.72     13186296.85
      2218787.72     13185746.87
#Sta/Elev= 30
  4596.9  320.78  4773.6  312.81  4919.4  306.43  4970.5  302.68    4977  301.78
  4985.6  298.81  4994.1  297.94  4996.9  297.44  5000.1  297.94  5026.7  299.93
  5050.8  299.65    5061  301.01  5071.1  304.61  5085.1  304.63  5092.2  302.96
  5101.6  301.73  5111.8  303.52  5138.5  304.99  5143.6   300.4  5162.6  302.73
  5172.8  305.54  5191.8  306.31  5196.9  304.85  5223.6  307.06  5274.3  308.15
  5473.9   314.3  5532.3  313.22  5548.9  314.44  5556.5  318.83    5559  318.83
#Mann= 7 ,-1 , 0
  4596.9     .05       0  4773.6      .1       0  4985.6     .05       0
  4994.1     .07       0  5000.1     .05       0  5092.2     .16       0
  5274.3      .1       0
Bank Sta=4970.5,5162.6
XS Rating Curve= 0 ,0
Exp/Cntr=0.3,0.1