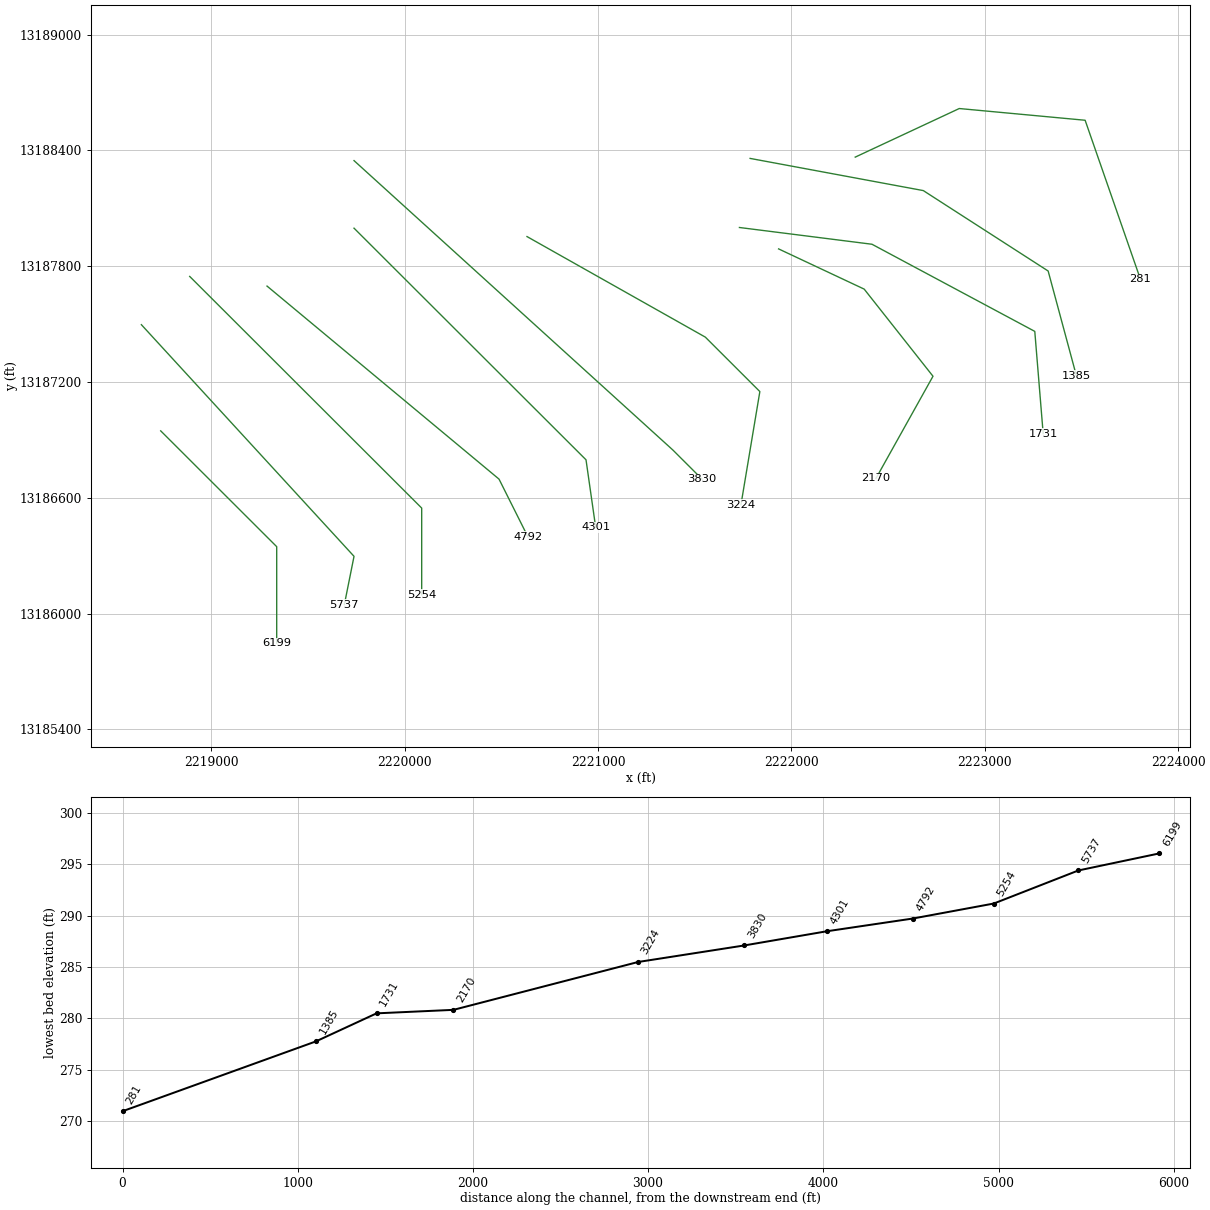
HEC-RAS study GATO CREEK.prj: GATO CREEK Base Level Engineering

--- GATO CREEK.g01 (geometry) --- (continued)

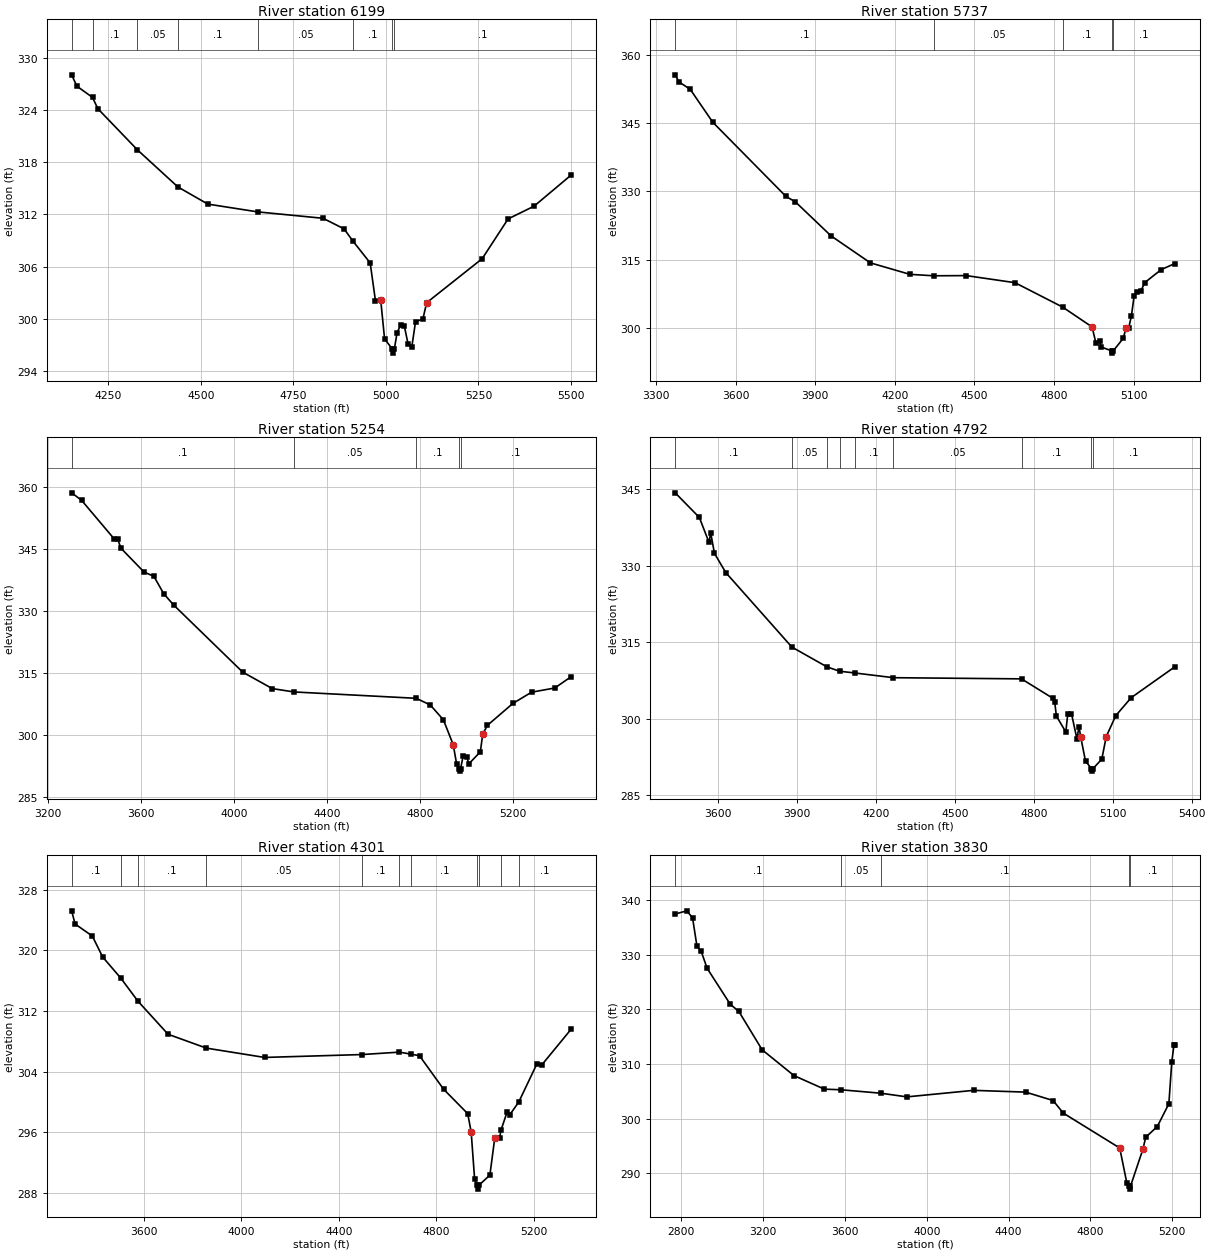
Type RM Length L Ch R = 1 ,6199    ,462,462,462
BEGIN DESCRIPTION:
GATO CREEK 7.0
END DESCRIPTION:
XS GIS Cut Line= 3
      2218737.74     13186946.83      2219337.72     13186346.85
      2219337.72     13185846.85
#Sta/Elev= 30
  4151.5  328.03  4165.6  326.73    4208  325.43  4222.2  324.14  4328.9  319.42
  4438.4  315.15  4519.2  313.18  4654.8  312.28  4830.3  311.55  4886.9  310.34
  4911.2  308.92  4957.6  306.42  4971.7   302.1  4985.9  302.19  4996.5  297.68
    5017  296.56  5019.8  296.06    5023  296.56    5030  298.38    5040  299.32
    5050  299.13    5060  297.08    5070  296.79    5080  299.65    5100     300
    5110  301.85    5260  306.91    5330  311.48    5400  312.94    5500  316.51
#Mann= 8 ,-1 , 0
  4151.5     .05       0    4208      .1       0  4328.9     .05       0
  4438.4      .1       0  4654.8     .05       0  4911.2      .1       0
    5017     .07       0    5023      .1       0
Bank Sta=4985.9,5110
XS Rating Curve= 0 ,0
Exp/Cntr=0.3,0.1

Type RM Length L Ch R = 1 ,5737    ,483,483,483
BEGIN DESCRIPTION:
GATO CREEK 6.0
END DESCRIPTION:
XS GIS Cut Line= 3
      2218637.71     13187496.87      2219737.72     13186296.85
      2219687.71     13186046.81
#Sta/Elev= 30
  3372.1  355.68    3386  354.12  3428.5  352.51  3513.6  345.25  3789.9  328.89
    3825  327.72  3959.5  320.22  4108.1  314.27  4256.7  311.75  4346.5  311.43
  4469.4  311.47  4653.2  309.91  4832.6  304.54  4943.6  300.17  4957.8  296.73
  4971.9  297.02  4978.7  295.74  5017.4   294.9  5020.1   294.4  5023.4   294.9
  5061.2  297.65  5071.4  299.85  5081.6  299.92  5091.8  302.54    5102  306.88
  5112.2  307.95  5127.5   308.1  5142.8  309.95    5204  312.78    5255  314.11
#Mann= 5 ,-1 , 0
  3372.1      .1       0  4346.5     .05       0  4832.6      .1       0
  5017.4     .07       0  5023.4      .1       0
Bank Sta=4943.6,5071.4
XS Rating Curve= 0 ,0
Exp/Cntr=0.3,0.1

Type RM Length L Ch R = 1 ,5254    ,462,462,462
BEGIN DESCRIPTION:
GATO CREEK 5.0
END DESCRIPTION:
XS GIS Cut Line= 3
      2218887.69     13187746.89      2220087.72     13186546.85
      2220087.72     13186096.85
#Sta/Elev= 30
  3302.9  358.67  3345.4  356.87  3486.8  347.43  3500.9  347.43  3515.1  345.22
  3614.1  339.46  3656.5  338.42  3698.9  334.19  3741.4  331.47  4038.3  315.19
  4165.6  311.19  4259.1  310.38  4784.1  308.84  4844.4  307.24    4901  303.63
  4943.4  297.59  4957.6  293.01  4968.7  291.68  4971.5  291.18  4974.7  291.68
  4985.9  294.82  5002.5  294.66    5010  292.92    5060  295.86    5070  300.13
    5090  302.27    5200   307.6    5280  310.32    5380  311.34    5450  314.07
#Mann= 5 ,-1 , 0
  3302.9      .1       0  4259.1     .05       0  4784.1      .1       0
  4968.7     .07       0  4974.7      .1       0
Bank Sta=4943.4,5070
XS Rating Curve= 0 ,0
Exp/Cntr=0.3,0.1

Type RM Length L Ch R = 1 ,4792    ,491,491,491
BEGIN DESCRIPTION:
GATO CREEK 4.0
END DESCRIPTION:
XS GIS Cut Line= 3
      2219287.68     13187696.89      2220487.72     13186696.85
      2220637.72     13186396.86
#Sta/Elev= 30
  3437.9  344.32  3529.7  339.48  3566.2   334.6  3572.7  336.47    3587  332.44
    3630  328.68  3881.3  314.05  4014.6  310.17  4062.3  309.32  4119.7  308.98
  4267.2  308.05  4753.6  307.82  4871.8  304.04  4879.6  303.33  4886.1  300.53
  4921.9   297.4  4929.1  300.84  4943.4     301  4964.2  296.03    4972  298.45
  4978.5  296.41  4996.7  291.69  5019.4  290.22  5022.1  289.72  5025.4  290.22
  5058.7  292.08  5075.5  296.49  5111.8  300.61  5170.5  304.14  5335.4  310.16
#Mann= 9 ,-1 , 0
  3437.9      .1       0  3881.3     .05       0  4014.6      .1       0
  4062.3     .05       0  4119.7      .1       0  4267.2     .05       0
  4753.6      .1       0  5019.4     .07       0  5025.4      .1       0
Bank Sta=4978.5,5075.5
XS Rating Curve= 0 ,0
Exp/Cntr=0.3,0.1

Type RM Length L Ch R = 1 ,4301    ,471,471,471
BEGIN DESCRIPTION:
GATO CREEK 3.0
END DESCRIPTION:
XS GIS Cut Line= 3
      2219737.69     13187996.89      2220937.72     13186796.85
      2220987.73     13186446.81
#Sta/Elev= 30
  3302.9  325.23  3317.1  323.49  3387.8   321.9  3430.2  319.14  3504.8  316.34
  3575.4  313.29  3698.9  308.93  3856.2   307.1  4094.9  305.87  4494.4  306.25
  4648.5  306.57    4698   306.3  4731.3  306.09  4830.3  301.67  4929.3  298.44
  4943.4  296.01  4957.6  289.77  4968.7  288.98  4971.5  288.48  4974.7  288.98
  5020.2  290.33  5040.4  295.27  5060.6  295.25  5065.4  296.23  5090.9  298.65
    5101  298.26  5138.7  299.98  5212.1  304.94  5232.3  304.84  5353.6  309.59
#Mann= 11 ,-1 , 0
  3302.9      .1       0  3504.8     .05       0  3575.4      .1       0
  3856.2     .05       0  4494.4      .1       0  4648.5     .05       0
    4698      .1       0  4968.7     .07       0  4974.7      .1       0
  5065.4     .16       0  5138.7      .1       0
Bank Sta=4943.4,5040.4
XS Rating Curve= 0 ,0
Exp/Cntr=0.3,0.1

Type RM Length L Ch R = 1 ,3830    ,606,606,606
BEGIN DESCRIPTION:
GATO CREEK 2.0
END DESCRIPTION:
XS GIS Cut Line= 3
      2219737.73     13188346.85      2221387.72     13186846.85
       2221537.7     13186696.88
#Sta/Elev= 30
  2770.1  337.41  2826.5  337.99  2854.9  336.71  2876.5   331.5  2897.5  330.56
  2925.8   327.5  3039.4   320.9  3081.3  319.59  3194.8  312.59  3350.9  307.86
  3499.5  305.38  3580.1  305.27  3775.1  304.64    3903  303.97  4228.7  305.16
  4483.4  304.84  4617.9   303.3  4667.2  301.01  4943.6  294.62  4978.7  288.15
  4989.9   287.6  4992.7   287.1  4995.9   287.6  5056.6  294.37  5070.7  296.59
  5127.3  298.55  5183.8  302.71    5198  310.29  5208.6  313.44  5212.1  313.44
#Mann= 5 ,-1 , 0
  2770.1      .1       0  3580.1     .05       0  3775.1      .1       0
  4989.9     .07       0  4995.9      .1       0
Bank Sta=4943.6,5056.6
XS Rating Curve= 0 ,0
Exp/Cntr=0.3,0.1

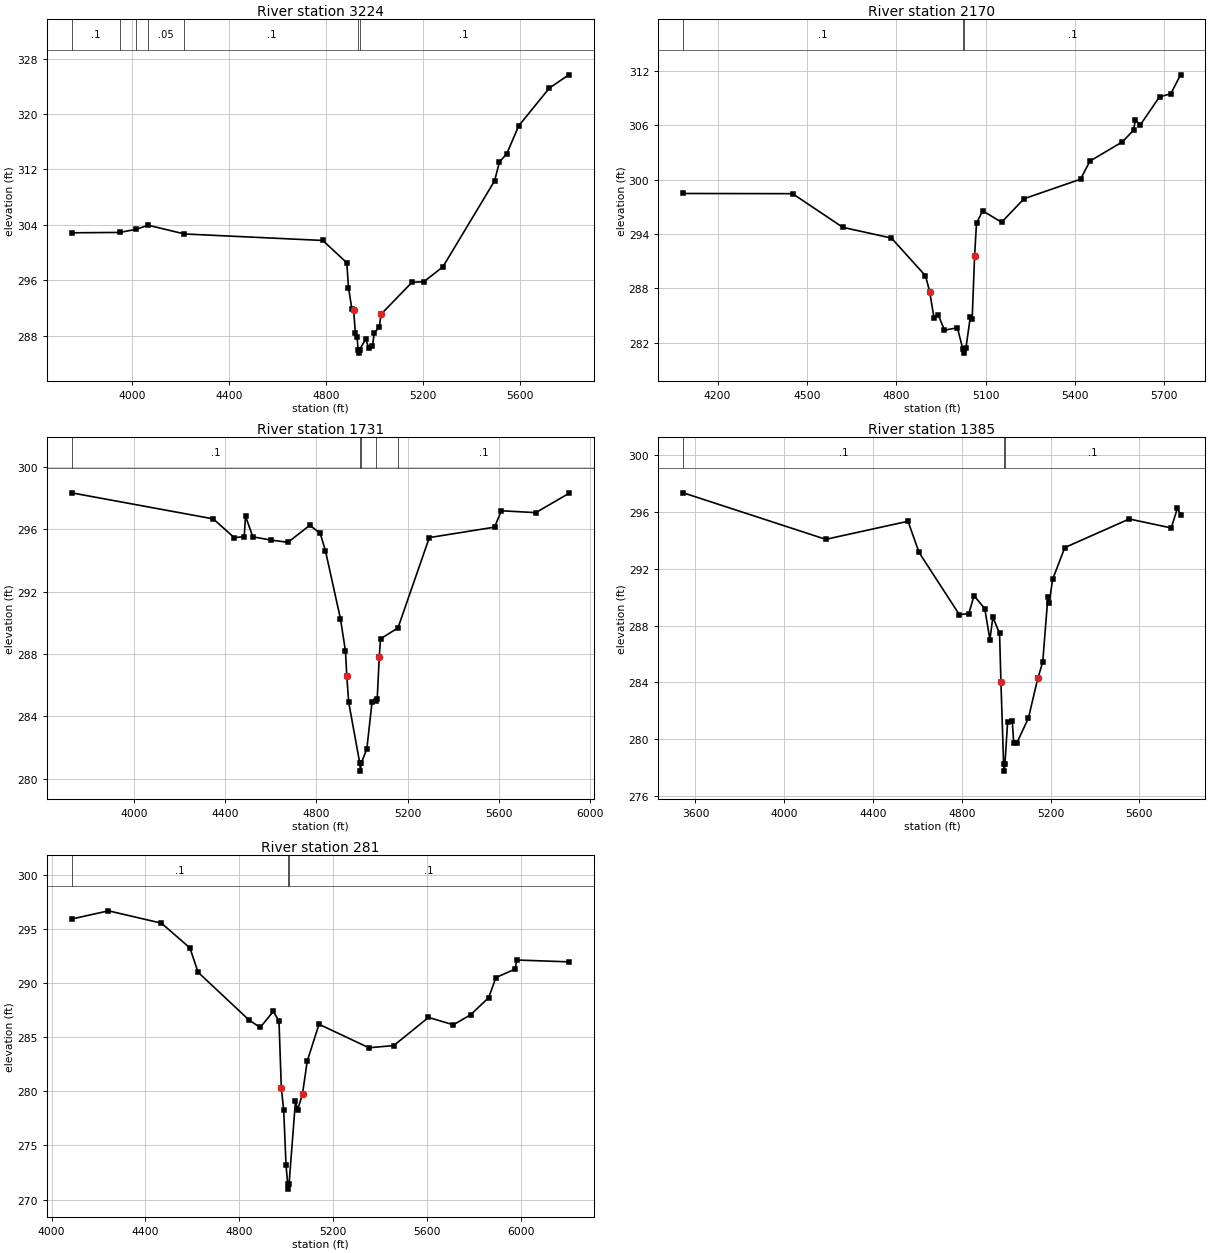
Type RM Length L Ch R = 1 ,3224    ,1054,1054,1054
BEGIN DESCRIPTION:
Mapping XS 983acd6e
END DESCRIPTION:
XS GIS Cut Line= 4
       2220632.5     13187953.32      2221554.79      13187432.5
      2221836.91     13187150.38      2221739.25     13186564.43
#Sta/Elev= 30
  3750.9  302.86  3949.1  302.91  4016.5  303.35  4066.9  303.95  4217.1  302.69
  4787.9  301.75  4886.9  298.53  4893.9  294.95  4908.1  291.81  4915.1  291.74
  4922.2  288.38  4929.3  287.88  4933.4  285.99  4936.1  285.49  4939.4  285.99
  4964.6  287.48  4978.8  286.16  4992.9   286.5    5000  288.36  5021.2   289.3
  5028.3  291.11  5155.6   295.7  5205.1   295.8  5283.6  297.95  5496.5  310.34
  5516.8  313.07  5547.2  314.28  5596.2  318.29  5722.9  323.75  5803.1  325.66
#Mann= 7 ,-1 , 0
  3750.9      .1       0  3949.1     .05       0  4016.5      .1       0
  4066.9     .05       0  4217.1      .1       0  4933.4     .07       0
  4939.4      .1       0
Bank Sta=4915.1,5028.3
XS Rating Curve= 0 ,0
Exp/Cntr=0.3,0.1

Type RM Length L Ch R = 1 ,2170    ,439,439,439
BEGIN DESCRIPTION:
Mapping XS baab93a3
END DESCRIPTION:
XS GIS Cut Line= 4
      2221933.87     13187889.48      2222376.62     13187681.13
      2222732.52     13187229.74      2222437.84     13186701.06
#Sta/Elev= 30
    4085  298.48  4451.8  298.46  4620.4  294.74  4783.9  293.55  4898.1  289.38
  4912.2  287.63  4926.7  284.72  4941.1  285.05  4961.9  283.37  5005.2  283.63
    5023  281.33  5025.8  280.83    5029  281.33  5034.1  281.43  5048.6  284.83
  5054.9  284.64    5063  291.58  5069.4   295.2  5090.2  296.56  5153.7   295.3
  5228.9   297.9  5418.6  300.06  5450.1  302.06  5559.2  304.19  5596.9  305.49
  5602.6  306.64  5618.6  306.03  5683.8  309.17  5721.5   309.5  5754.4   311.6
#Mann= 3 ,-1 , 0
    4085      .1       0    5023     .07       0    5029      .1       0
Bank Sta=4912.2,5063
XS Rating Curve= 0 ,0
Exp/Cntr=0.3,0.1

Type RM Length L Ch R = 1 ,1731    ,346,346,346
BEGIN DESCRIPTION:
Mapping XS 93c32bf7
END DESCRIPTION:
XS GIS Cut Line= 4
      2221731.32     13188000.37      2222417.05     13187913.57
      2223259.06     13187462.18      2223302.47     13186932.62
#Sta/Elev= 30
  3727.2  298.33  4347.9  296.66  4439.7  295.46  4483.5  295.52  4489.2  296.83
  4521.3  295.51  4600.7   295.3  4675.2  295.16  4770.9  296.25  4816.3  295.73
    4839  294.63  4905.1  290.25    4927  288.18  4932.7  286.59  4941.1   284.9
  4989.8  280.99  4992.6  280.49  4995.8  280.99  5020.5  281.91  5043.2   284.9
    5061  284.96  5065.9  285.09  5074.9  287.81  5080.5  288.97  5156.9  289.67
  5294.1  295.46  5579.8  296.13  5609.9  297.18  5760.4  297.06  5905.1  298.29
#Mann= 5 ,-1 , 0
  3727.2      .1       0  4989.8     .07       0  4995.8      .1       0
    5061     .16       0  5156.9      .1       0
Bank Sta=4932.7,5074.9
XS Rating Curve= 0 ,0
Exp/Cntr=0.3,0.1

Type RM Length L Ch R = 1 ,1385    ,1104,1104,1104
BEGIN DESCRIPTION:
Mapping XS 651be3f4
END DESCRIPTION:
XS GIS Cut Line= 4
      2221786.51     13188358.26      2222682.39     13188191.58
      2223328.22     13187774.91      2223474.06     13187233.23
#Sta/Elev= 30
  3545.1  297.33  4187.1  294.06  4557.9  295.33  4607.4  293.14  4788.9  288.77
  4831.6  288.83  4855.4   290.1  4903.8  289.18  4926.8     287  4940.1  288.59
  4970.4  287.44  4976.4  284.06  4988.5  278.26  4991.3  277.76  4994.5  278.26
  5006.7  281.23  5027.8  281.25  5033.9  279.77  5048.9  279.77  5100.4  281.49
  5142.7  284.29  5164.8  285.42  5188.2  290.02  5194.1  289.59  5209.3  291.24
  5264.3  293.48  5554.7  295.49  5744.1  294.86  5771.8  296.25  5785.9  295.79
#Mann= 3 ,-1 , 0
  3545.1      .1       0  4988.5     .07       0  4994.5      .1       0
Bank Sta=4976.4,5142.7
XS Rating Curve= 0 ,0
Exp/Cntr=0.3,0.1

Type RM Length L Ch R = 1 ,281     ,0,0,0
BEGIN DESCRIPTION:
GATO CREEK 1.0
END DESCRIPTION:
XS GIS Cut Line= 4
      2222330.27     13188364.97      2222868.44     13188616.69
      2223519.48     13188555.93      2223805.84     13187731.55
#Sta/Elev= 30
  4085.2  295.89  4242.8  296.65  4468.8  295.51  4590.2  293.22  4624.8  290.98
  4841.7  286.58  4889.5  285.88  4945.7  287.36  4969.9  286.48  4979.9   280.3
    4990  278.26    5000  273.16    5007  271.46  5009.8  270.96    5013  271.46
  5040.2  279.09  5049.7  278.29  5070.3  279.77  5090.4  282.78  5140.6  286.18
  5353.4  284.01  5459.3  284.21  5607.5  286.81  5713.7  286.13  5787.4  287.06
    5864  288.63  5895.1  290.49  5977.9  291.28  5983.2  292.11  6205.9  291.94
#Mann= 3 ,-1 , 0
  4085.2      .1       0    5007     .07       0    5013      .1       0
Bank Sta=4979.9,5070.3
XS Rating Curve= 0 ,0
Exp/Cntr=0.3,0.1

Chan Stop Cuts=-1
Use User Specified Reach Order=0
Composite Channel Slope=5