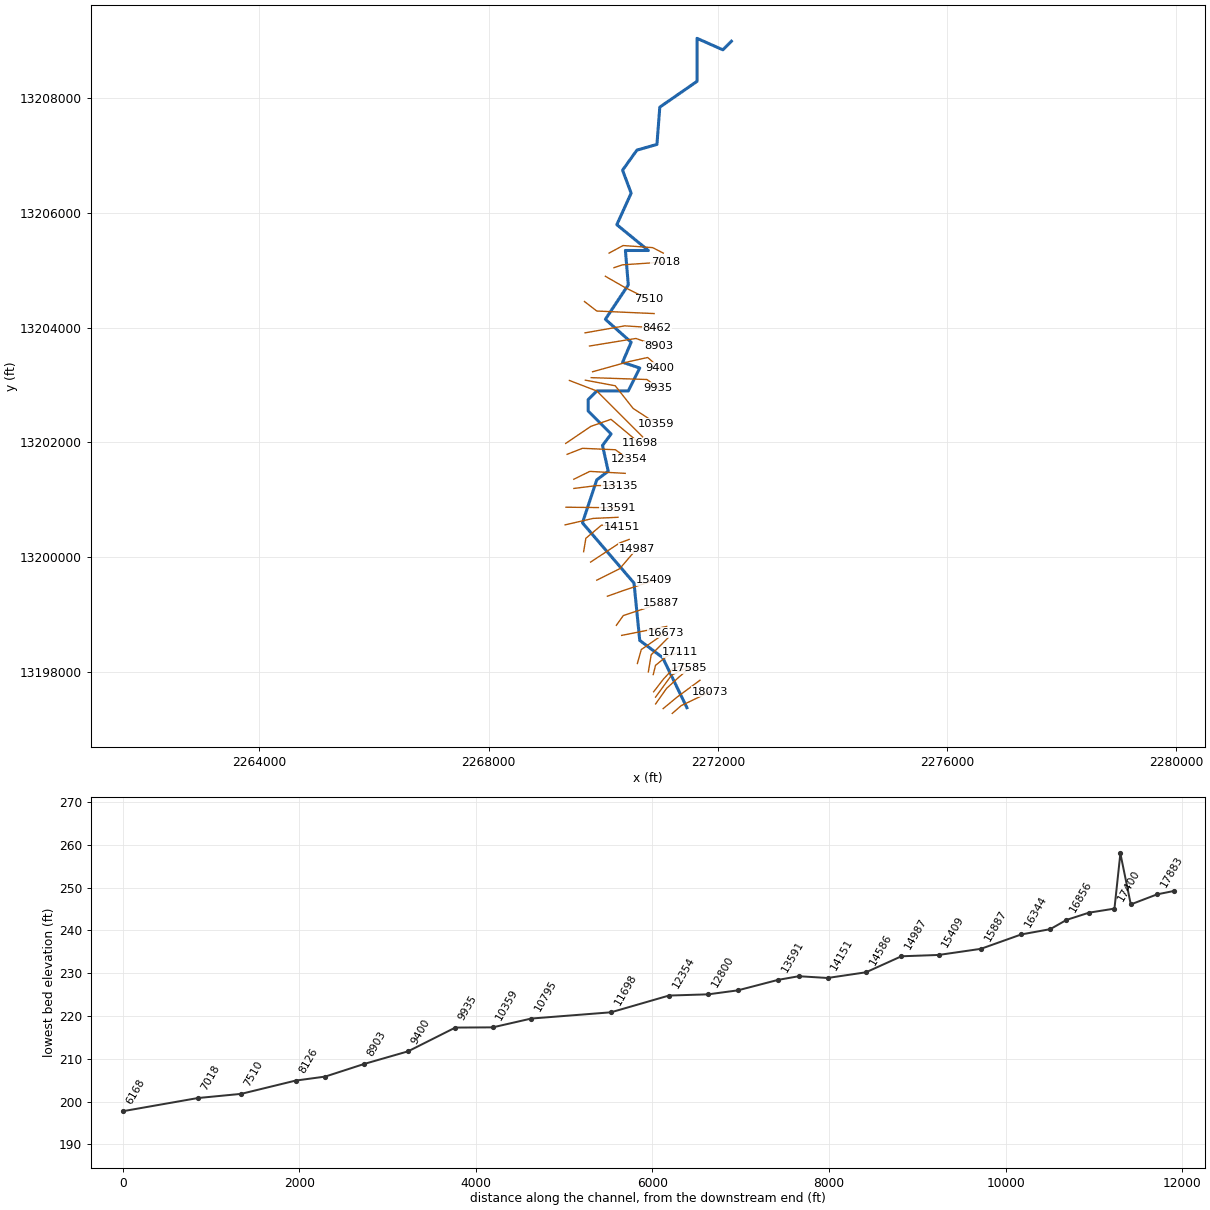
--- JULIAN CREEK.prj (project) ---

Proj Title=JULIAN CREEK Base Level Engineering
Current Plan=p01
Default Exp/Contr=0.3,0.1
English Units
Geom File=g01
Flow File=f01
Plan File=p01
Y Axis Title=Elevation
X Axis Title(PF)=Main Channel Distance
X Axis Title(XS)=Station
BEGIN DESCRIPTION:
JULIAN CREEK
END DESCRIPTION:
DSS Export Rating Curves= 0
DSS Export Rating Curve Sorted= 0
DSS Export Volume Flow Curves= 0
DXF OffsetX= 0
DXF OffsetY= 0
DXF ScaleX= 1
DXF ScaleY= 10

--- JULIAN CREEK.p01 (plan) ---

Plan Title=Multiple Run
Short Identifier=Multiple
Geom File=g01
Flow File=f01
Subcritical Flow
K Sum by GR= 0
Std Step Tol= 0.01
Critical Tol= 0.01
Num of Std Step Trials= 20
Max Error Tol= 0.3
Flow Tol Ratio= 0.001
Split Flow NTrial= 30
Split Flow Tol= 0.02
Split Flow Ratio= 0.02
Log Output Level= 0
Friction Slope Method= 1
Unsteady Friction Slope Method= 2
Unsteady Bridges Friction Slope Method= 1
Parabolic Critical Depth
Global Vel Dist=  1 , 1 , 1
Global Log Level= 0
CheckData=True
Encroach Param= -1, 0, 0, 0
BEGIN DESCRIPTION:
Multiple Run
END DESCRIPTION:

--- JULIAN CREEK.f01 (steady flow) ---

Flow Title=Multiple
Program Version=4.10
Number of Profiles= 7
Profile Names=10-year,25-year,50-year,1pct_min,100-year,1pct_plu,500-year
River Rch & RM=JULIAN CREEK,Reach-1         ,18073
     135     179     214     189     256     346     370
River Rch & RM=JULIAN CREEK,Reach-1         ,16344
     279     387     476     431     583     788     885
River Rch & RM=JULIAN CREEK,Reach-1         ,10795
     371     520     645     588     795    1075    1226
River Rch & RM=JULIAN CREEK,Reach-1         ,4212
     394     554     688     628     850    1149    1314
Boundary for River Rch & Prof#=JULIAN CREEK,Reach-1         , 1
Up Type= 0
Dn Type= 3
Dn Slope=0.003
Boundary for River Rch & Prof#=JULIAN CREEK,Reach-1         , 2
Up Type= 0
Dn Type= 3
Dn Slope=0.003
Boundary for River Rch & Prof#=JULIAN CREEK,Reach-1         , 3
Up Type= 0
Dn Type= 3
Dn Slope=0.003
Boundary for River Rch & Prof#=JULIAN CREEK,Reach-1         , 4
Up Type= 0
Dn Type= 3
Dn Slope=0.003
Boundary for River Rch & Prof#=JULIAN CREEK,Reach-1         , 5
Up Type= 0
Dn Type= 3
Dn Slope=0.003
Boundary for River Rch & Prof#=JULIAN CREEK,Reach-1         , 6
Up Type= 0
Dn Type= 3
Dn Slope=0.003
Boundary for River Rch & Prof#=JULIAN CREEK,Reach-1         , 7
Up Type= 0
Dn Type= 3
Dn Slope=0.003
DSS Import GetInterval= 0
DSS Import GetPeak= 0
DSS Import FillOption= 0

--- JULIAN CREEK.g01 (geometry) ---

Geom Title=Existing Conditions
Program Version=4.10

River Reach=JULIAN CREEK    ,Reach-1
Reach XY= 30
      2271460.99     13197373.59      2271037.72     13198246.85
      2270637.72     13198546.86      2270537.72     13199546.86
      2269637.72     13200596.85      2269887.72     13201346.86
      2270087.72     13201496.86      2269987.72     13201946.85
      2270137.72     13202146.86      2269737.72     13202546.85
      2269737.72     13202746.85      2269887.72     13202896.85
      2270437.72     13202896.85      2270637.72     13203296.86
      2270337.72     13203396.85      2270487.72     13203746.85
      2270037.72     13204146.86      2270437.72     13204746.85
      2270387.72     13205346.85      2270787.72     13205346.85
      2270237.72     13205796.85      2270487.72     13206346.85
      2270337.72     13206746.86      2270587.72     13207096.86
      2270937.72     13207196.85      2270987.72     13207846.85
      2271637.72     13208296.85      2271637.72     13209046.86
      2272087.72     13208846.85      2272237.72     13208996.85

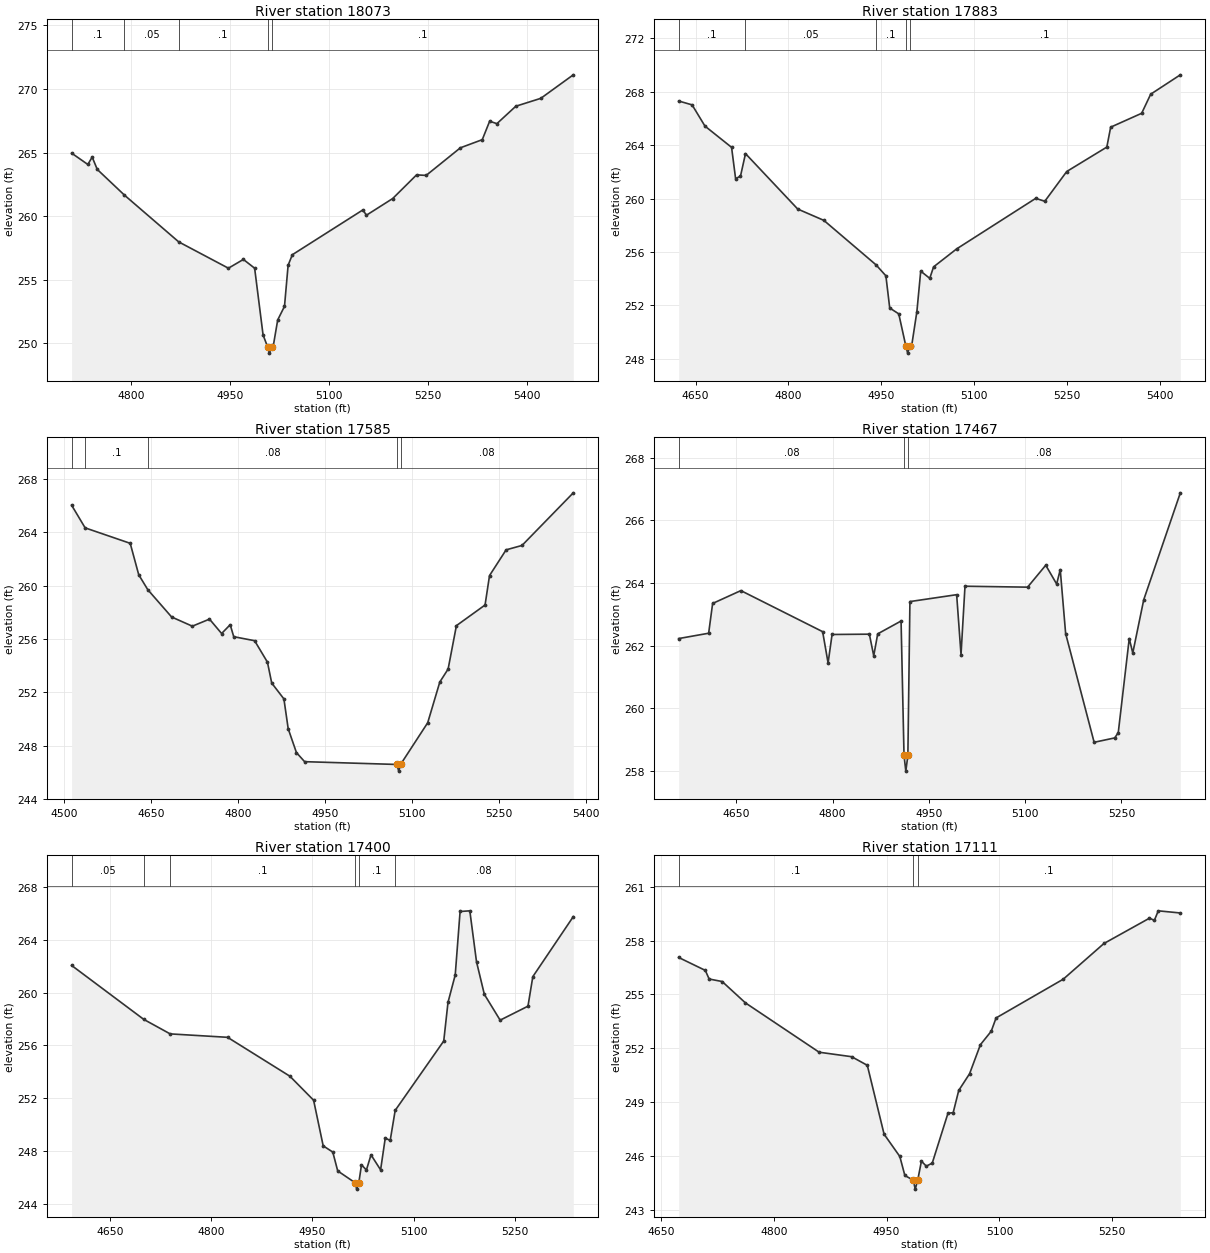
Type RM Length L Ch R = 1 ,18073   ,190,190,190
BEGIN DESCRIPTION:
JULIAN CREEK 33.0
END DESCRIPTION:
XS GIS Cut Line= 3
      2271205.96     13197274.14      2271362.22     13197409.57
      2271862.21     13197649.14
#Sta/Elev= 30
  4709.5  264.95  4734.1  264.06  4740.7  264.64  4748.4  263.67  4789.6  261.65
    4872  257.97  4947.4   255.9  4970.1  256.59  4987.2   255.9    5000  250.65
  5006.8  249.72  5009.6  249.22  5012.8  249.72  5015.4  249.76  5022.2  251.83
  5032.5   252.9    5038  256.13  5044.4  256.96  5151.3  260.48  5156.9  260.07
  5196.7  261.38  5232.9  263.24  5247.5   263.2  5299.4  265.37  5332.6  266.01
  5343.8  267.46  5354.8  267.27  5383.5  268.64  5421.4  269.26  5470.7  271.11
#Mann= 5 ,-1 , 0
  4709.5      .1       0  4789.6     .05       0    4872      .1       0
  5006.8     .07       0  5012.8      .1       0
Bank Sta=5006.8,5012.8
XS Rating Curve= 0 ,0
Exp/Cntr=0.3,0.1

Type RM Length L Ch R = 1 ,17883   ,298,298,298
BEGIN DESCRIPTION:
Mapping XS 22044f2f
END DESCRIPTION:
XS GIS Cut Line= 3
      2271046.76     13197357.41      2271286.33     13197555.31
      2271688.86     13197852.01
#Sta/Elev= 30
  4622.8  267.31  4644.5  267.02  4665.3  265.43  4708.3  263.84  4714.8   261.5
  4722.7  261.68  4730.8  263.37  4815.2  259.22  4857.5  258.37  4941.8  255.04
  4957.7  254.22  4963.9  251.81  4978.5  251.37  4990.1  248.93  4992.9  248.43
  4996.1  248.93  4999.4  248.99  5007.8  251.54    5014  254.57  5028.6  254.03
  5034.8  254.89  5071.9  256.23  5199.9  260.02  5214.5   259.8    5250  262.03
  5314.8  263.86    5321  265.35  5371.1  266.39  5385.7  267.82  5433.6  269.27
#Mann= 5 ,-1 , 0
  4622.8      .1       0  4730.8     .05       0  4941.8      .1       0
  4990.1     .07       0  4996.1      .1       0
Bank Sta=4990.1,4996.1
XS Rating Curve= 0 ,0
Exp/Cntr=0.3,0.1

Type RM Length L Ch R = 1 ,17585   ,118,118,118
BEGIN DESCRIPTION:
Mapping XS 395440fe
END DESCRIPTION:
XS GIS Cut Line= 4
       2270914.8     13197438.99      2271105.77     13197709.83
      2271322.79     13197907.74      2271505.58     13198062.94
#Sta/Elev= 30
  4513.6  266.04  4536.9  264.34  4614.6  263.18  4629.3  260.82  4644.9   259.7
    4686  257.65  4721.7  256.96  4751.3  257.49  4772.2  256.41    4787  257.07
  4793.1  256.17  4829.1  255.87  4851.2  254.26  4858.6  252.69  4879.6   251.5
    4887  249.26  4901.2  247.47  4915.3  246.79  5074.7  246.58  5077.5  246.08
  5080.7  246.58  5127.5  249.71  5148.4  252.77  5162.7  253.74    5177     257
  5226.4  258.55  5234.1  260.76  5262.7  262.69  5290.1  263.02  5378.5  266.97
#Mann= 5 ,-1 , 0
  4513.6     .08       0  4536.9      .1       0  4644.9     .08       0
  5074.7     .07       0  5080.7     .08       0
Bank Sta=5074.7,5080.7
XS Rating Curve= 0 ,0
Exp/Cntr=0.3,0.1

Type RM Length L Ch R = 1 ,17467   ,67,67,67
BEGIN DESCRIPTION:
Mapping XS cf8e13a4
END DESCRIPTION:
XS GIS Cut Line= 5
      2270913.04     13197557.01      2271036.33     13197725.45
      2271194.31     13197942.46       2271270.7     13197978.92
      2271468.66     13198074.43
#Sta/Elev= 30
  4560.2  262.23  4606.9   262.4  4613.1  263.35  4657.1  263.76  4784.5  262.45
    4793  261.45  4799.2  262.36  4857.3  262.37  4864.1  261.68  4870.3  262.38
  4906.7  262.79  4911.3   258.5  4914.1     258  4917.3   258.5  4920.5  263.41
  4993.3  263.63  5000.1  261.72  5006.3   263.9  5103.8  263.87  5132.1  264.57
  5149.1  263.97  5154.7  264.43  5163.1  262.39  5207.5  258.92  5239.6  259.06
  5245.1  259.23  5262.2  262.23  5267.7  261.77  5284.8  263.47  5341.8  266.88
#Mann= 3 ,-1 , 0
  4560.2     .08       0  4911.3     .07       0  4917.3     .08       0
Bank Sta=4911.3,4917.3
XS Rating Curve= 0 ,0
Exp/Cntr=0.3,0.1

Type RM Length L Ch R = 1 ,17400   ,289,289,289
BEGIN DESCRIPTION:
JULIAN CREEK 32.0
END DESCRIPTION:
XS GIS Cut Line= 4
      2270880.09     13197650.81      2271053.69     13197874.76
      2271220.36     13198053.58      2271419.98     13198133.42
#Sta/Elev= 30
  4593.4  262.06  4700.2  257.97  4739.3  256.87  4824.3  256.61  4916.6  253.66
  4951.7  251.84  4965.9  248.38  4980.1  247.91  4987.4  246.48  5012.7   245.6
  5015.5   245.1  5018.7   245.6  5022.6  246.94  5029.9  246.55  5036.7   247.7
  5050.9  246.56  5057.8  248.97  5065.1  248.79  5072.5  251.07  5144.4  256.33
  5150.7  259.26  5161.4  261.34  5168.6  266.15    5183   266.2  5192.9  262.34
  5204.5  259.87  5227.9  257.91  5269.1  258.97  5276.3  261.21  5336.2  265.76
#Mann= 6 ,-1 , 0
  4593.4     .05       0  4700.2     .08       0  4739.3      .1       0
  5012.7     .07       0  5018.7      .1       0  5072.5     .08       0
Bank Sta=5012.7,5018.7
XS Rating Curve= 0 ,0
Exp/Cntr=0.3,0.1

Type RM Length L Ch R = 1 ,17111   ,255,255,255
BEGIN DESCRIPTION:
Mapping XS 70a68011
END DESCRIPTION:
XS GIS Cut Line= 4
      2270873.61     13197950.66      2270912.66     13198111.75
      2271112.78     13198272.82      2271347.07     13198341.16
#Sta/Elev= 30
  4673.7  257.06  4709.1  256.34  4714.2  255.86  4731.5  255.72  4762.4  254.53
  4860.4  251.78  4903.6  251.53  4924.4  251.05  4946.7  247.21  4967.6  245.97
  4974.3  244.91  4985.4  244.65  4988.1  244.15  4991.4  244.65  4996.3  245.71
  5002.8  245.43  5010.7   245.6  5031.6  248.38  5038.5  248.41  5045.9  249.65
  5060.3  250.58  5074.7   252.2  5089.1  252.95  5095.5  253.69  5184.8  255.85
  5238.9  257.84  5299.4  259.25  5305.9  259.13  5311.1  259.66  5340.4  259.54
#Mann= 3 ,-1 , 0
  4673.7      .1       0  4985.4     .07       0  4991.4      .1       0
Bank Sta=4985.4,4991.4
XS Rating Curve= 0 ,0
Exp/Cntr=0.3,0.1

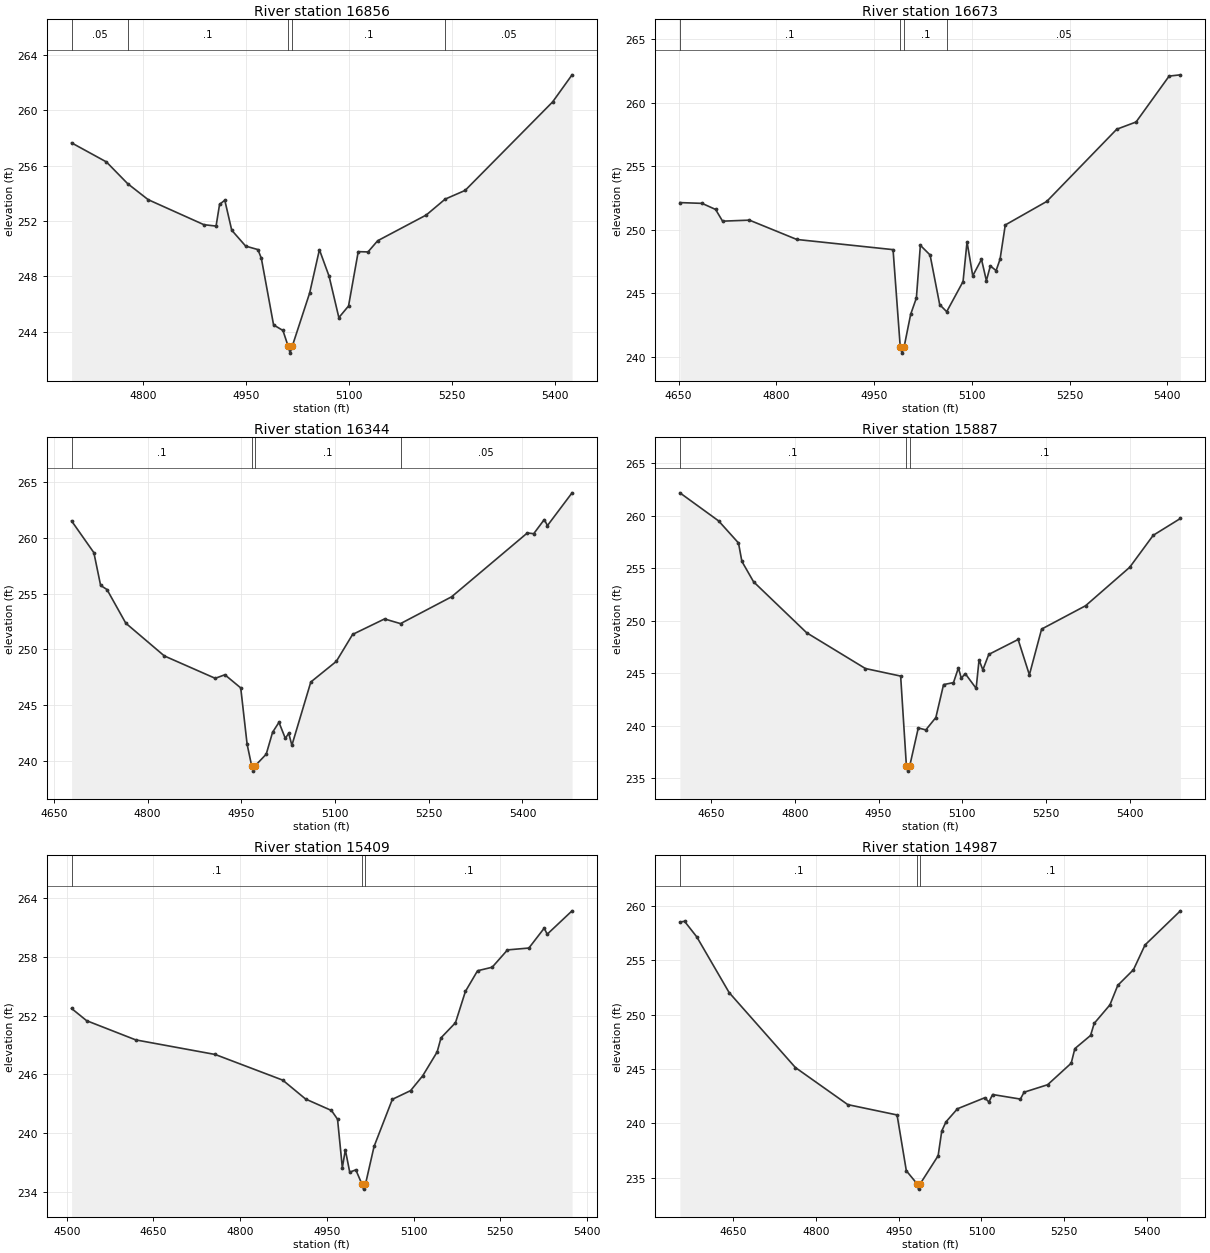
Type RM Length L Ch R = 1 ,16856   ,183,183,183
BEGIN DESCRIPTION:
JULIAN CREEK 31.0
END DESCRIPTION:
XS GIS Cut Line= 3
      2270787.73     13197996.89      2270837.72     13198296.85
      2271137.75     13198596.88
#Sta/Elev= 30
  4695.9  257.66  4746.6  256.28  4777.5  254.71  4807.4  253.55  4888.5  251.74
  4906.2  251.64  4911.3  253.21  4918.9  253.51    4929  251.34  4949.3  250.19
  4967.1  249.94  4972.1  249.31  4989.9  244.49  5003.5  244.09  5011.1  242.95
  5013.9  242.45  5017.1  242.95  5042.4   246.8  5056.6  249.93  5070.7  248.01
  5084.9  245.02    5099  245.86  5113.1  249.79  5127.3  249.77  5141.4  250.58
  5212.1  252.44  5239.6  253.59  5268.7  254.22    5396  260.62  5424.3  262.58
#Mann= 5 ,-1 , 0
  4695.9     .05       0  4777.5      .1       0  5011.1     .07       0
  5017.1      .1       0  5239.6     .05       0
Bank Sta=5011.1,5017.1
XS Rating Curve= 0 ,0
Exp/Cntr=0.3,0.1

Type RM Length L Ch R = 1 ,16673   ,329,329,329
BEGIN DESCRIPTION:
JULIAN CREEK 30.0
END DESCRIPTION:
XS GIS Cut Line= 3
      2270596.38     13198144.12      2270664.08     13198386.31
      2271088.58     13198680.59
#Sta/Elev= 30
  4652.1  252.14  4686.1  252.08  4706.9   251.6  4717.6  250.68  4758.8  250.76
  4831.5  249.24  4979.2  248.44  4990.2   240.8  4992.9   240.3  4996.2   240.8
  5006.2  243.35    5015  244.64  5021.1  248.78    5036  248.02  5050.8  244.11
  5061.5  243.56  5086.6  245.93  5092.7  249.05  5101.5  246.38  5114.9  247.68
  5122.4     246  5128.5  247.16  5137.3  246.79  5143.4  247.69  5151.4  250.38
    5215  252.23  5322.4  257.91  5352.1  258.48  5402.8  262.09  5420.1  262.19
#Mann= 4 ,-1 , 0
  4652.1      .1       0  4990.2     .07       0  4996.2      .1       0
  5061.5     .05       0
Bank Sta=4990.2,4996.2
XS Rating Curve= 0 ,0
Exp/Cntr=0.3,0.1

Type RM Length L Ch R = 1 ,16344   ,457,457,457
BEGIN DESCRIPTION:
Mapping XS d8d84c38
END DESCRIPTION:
XS GIS Cut Line= 2
      2270322.09     13198634.02      2271107.92     13198790.21
#Sta/Elev= 30
  4678.2  261.52  4713.9  258.67  4724.7  255.73  4734.9  255.36    4765  252.34
  4826.7   249.4  4908.2  247.39  4923.6  247.71    4949  246.53  4959.2  241.48
  4966.4  239.56  4969.2  239.06  4972.4  239.56  4989.8  240.58    5000  242.55
  5010.2  243.44  5020.4     242  5025.8  242.46  5030.9  241.38  5061.2  247.06
    5102  248.91  5128.1  251.33  5179.2  252.72  5204.8   252.3  5286.6  254.71
  5407.8  260.44    5418  260.37  5434.9  261.64    5440   261.1  5479.4  264.04
#Mann= 4 ,-1 , 0
  4678.2      .1       0  4966.4     .07       0  4972.4      .1       0
  5204.8     .05       0
Bank Sta=4966.4,4972.4
XS Rating Curve= 0 ,0
Exp/Cntr=0.3,0.1

Type RM Length L Ch R = 1 ,15887   ,478,478,478
BEGIN DESCRIPTION:
JULIAN CREEK 29.0
END DESCRIPTION:
XS GIS Cut Line= 3
      2270229.32     13198809.73      2270351.35     13198980.56
      2271004.03     13199194.87
#Sta/Elev= 30
  4593.9  262.17  4663.3   259.5  4698.9   257.4    4705  255.65  4725.9  253.71
  4821.1  248.86  4926.3  245.46  4989.5  244.74  4999.8   236.2  5002.5   235.7
  5005.8   236.2  5021.1  239.81  5034.6  239.62  5052.6   240.8  5066.4  243.93
  5084.2  244.12    5093  245.52  5098.2  244.54  5105.3  244.97  5124.8  243.57
    5130  246.28  5136.8  245.33  5147.4   246.8    5200  248.22  5220.2  244.86
  5242.1  249.21  5320.9  251.43    5400  255.09  5442.1  258.13  5490.8  259.73
#Mann= 3 ,-1 , 0
  4593.9      .1       0  4999.8     .07       0  5005.8      .1       0
Bank Sta=4999.8,5005.8
XS Rating Curve= 0 ,0
Exp/Cntr=0.3,0.1

Type RM Length L Ch R = 1 ,15409   ,422,422,422
BEGIN DESCRIPTION:
JULIAN CREEK 28.0
END DESCRIPTION:
XS GIS Cut Line= 3
      2270073.12     13199317.34       2270390.4     13199429.61
      2270892.97     13199595.51
#Sta/Elev= 30
  4508.3  252.72  4534.4  251.47  4619.3  249.51  4756.8  248.02  4873.6   245.4
  4913.2  243.47  4957.9   242.3  4968.4  241.41  4976.7  236.46  4981.9  238.28
  4989.5     236    5000  236.24  5010.7  234.77  5013.4  234.27  5016.7  234.77
  5031.6  238.63  5063.2  243.44  5094.8  244.33  5115.8  245.85  5140.7  248.28
  5147.4  249.72  5172.4  251.26  5189.6  254.46  5210.6  256.57  5235.9  256.93
  5262.4   258.7  5299.4  258.89  5325.9  260.92  5331.1   260.3  5374.1  262.69
#Mann= 3 ,-1 , 0
  4508.3      .1       0  5010.7     .07       0  5016.7      .1       0
Bank Sta=5010.7,5016.7
XS Rating Curve= 0 ,0
Exp/Cntr=0.3,0.1

Type RM Length L Ch R = 1 ,14987   ,401,401,401
BEGIN DESCRIPTION:
JULIAN CREEK 27.0
END DESCRIPTION:
XS GIS Cut Line= 3
      2269887.73     13199596.86      2270287.72     13199796.85
      2270587.74     13200146.87
#Sta/Elev= 30
  4552.8  258.51  4561.2  258.59  4583.5  257.15  4642.2  252.03  4762.4  245.14
  4857.5  241.73  4946.9  240.78  4963.7  235.65    4983  234.46  4985.8  233.96
    4989  234.46  5021.4  237.03    5028  239.31  5035.7  240.15  5056.5  241.35
  5105.9  242.36  5113.6  241.97  5120.2  242.66  5170.7  242.24  5177.3  242.87
  5220.1  243.56  5262.9  245.54  5269.5  246.88    5298  248.09  5304.6   249.2
  5333.1   250.9  5347.4   252.7  5375.9  254.14  5396.8  256.41    5461  259.55
#Mann= 3 ,-1 , 0
  4552.8      .1       0    4983     .07       0    4989      .1       0
Bank Sta=4983,4989
XS Rating Curve= 0 ,0
Exp/Cntr=0.3,0.1

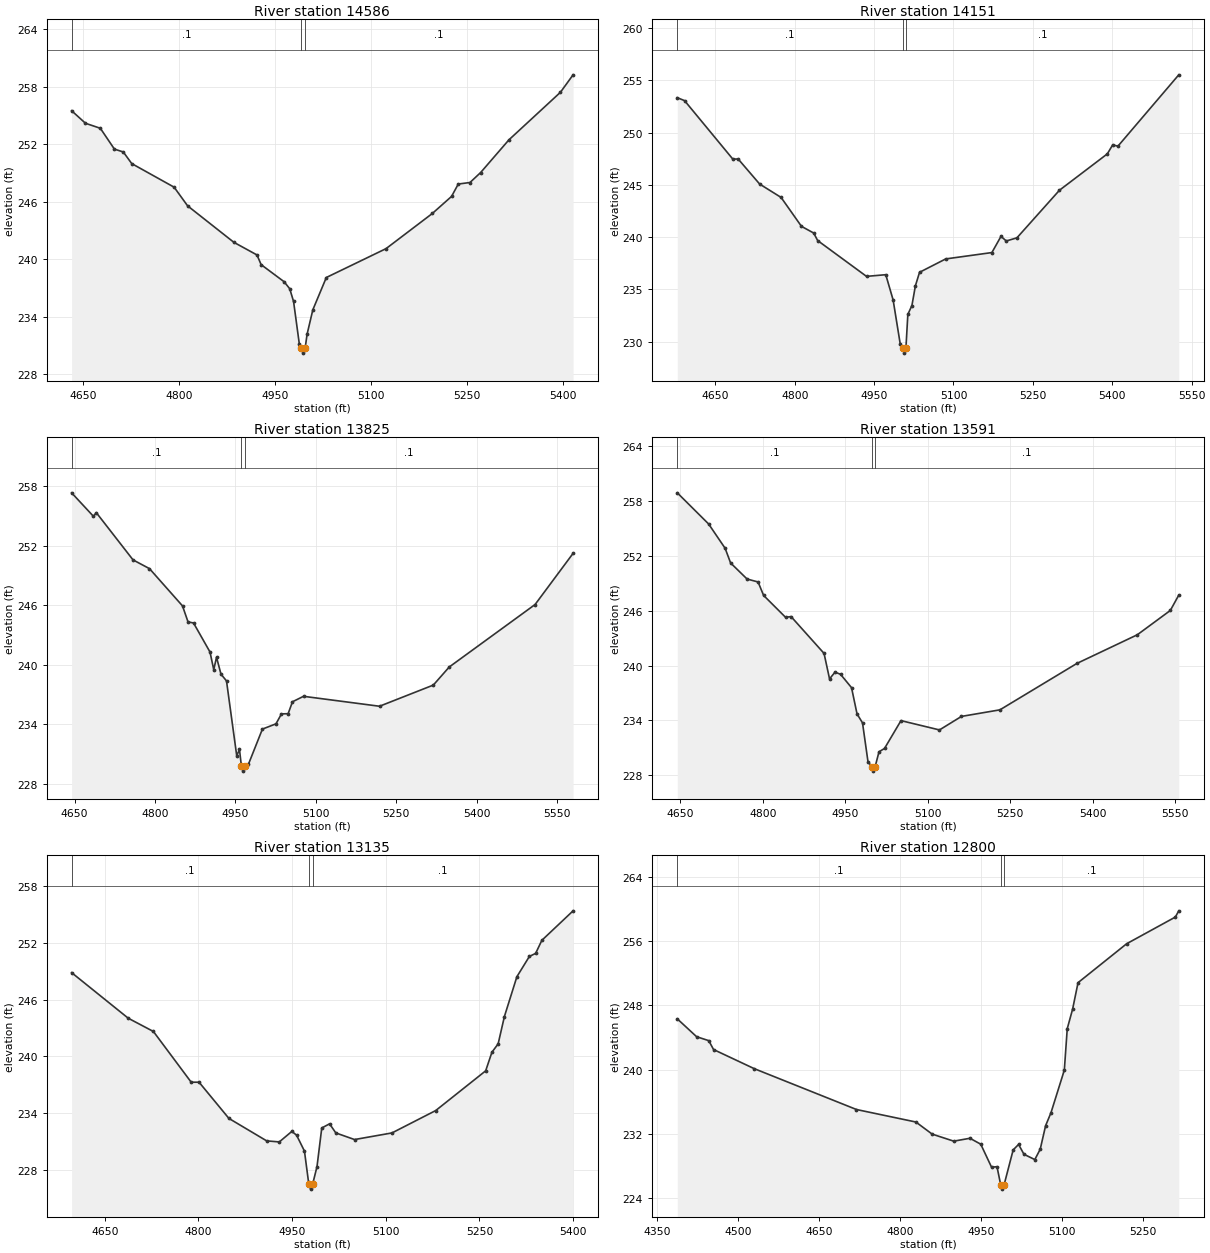
Type RM Length L Ch R = 1 ,14586   ,435,435,435
BEGIN DESCRIPTION:
JULIAN CREEK 26.0
END DESCRIPTION:
XS GIS Cut Line= 3
      2269780.26     13199912.81      2270287.72     13200246.85
      2270453.26     13200307.96
#Sta/Elev= 30
  4631.9  255.48  4653.6  254.17  4676.8  253.65  4698.8  251.48  4712.7  251.18
  4725.9  249.97  4792.2  247.51  4813.2  245.57  4885.5  241.77  4921.7  240.45
  4928.2  239.44  4964.1  237.66  4972.9  236.93  4978.9   235.6    4988  231.12
    4991  230.72  4993.7  230.22    4997  230.72    5000  232.18    5009  234.73
  5030.1   238.1  5123.5  241.11  5195.8  244.77  5225.9  246.55  5236.4  247.84
  5254.7     248  5271.4  249.04  5315.5  252.44  5396.1   257.4  5415.9  259.22
#Mann= 3 ,-1 , 0
  4631.9      .1       0    4991     .07       0    4997      .1       0
Bank Sta=4991,4997
XS Rating Curve= 0 ,0
Exp/Cntr=0.3,0.1

Type RM Length L Ch R = 1 ,14151   ,326,326,326
BEGIN DESCRIPTION:
JULIAN CREEK 25.0
END DESCRIPTION:
XS GIS Cut Line= 4
      2269658.25     13200093.38       2269697.3      13200327.7
      2269970.63     13200557.11      2270322.08     13200522.94
#Sta/Elev= 30
  4578.2  253.35  4591.9  253.07  4683.1  247.47  4693.2  247.48  4733.8  245.08
  4774.3   243.8  4812.8  241.03  4835.9  240.39  4843.4  239.67  4935.7  236.24
  4972.1   236.4    4986  233.98  4999.5  229.74  5004.2  229.39    5007  228.89
  5010.2  229.39  5013.8   232.6  5021.5  233.45  5028.1  235.34  5035.9  236.63
  5085.3  237.91  5172.6  238.52  5189.8  240.07  5199.8  239.63  5219.9  239.93
  5300.3  244.49  5390.7  247.97  5400.8  248.83  5410.8  248.71  5525.7  255.54
#Mann= 3 ,-1 , 0
  4578.2      .1       0  5004.2     .07       0  5010.2      .1       0
Bank Sta=5004.2,5010.2
XS Rating Curve= 0 ,0
Exp/Cntr=0.3,0.1

Type RM Length L Ch R = 1 ,13825   ,234,234,234
BEGIN DESCRIPTION:
Mapping XS be752b77
END DESCRIPTION:
XS GIS Cut Line= 3
      2269336.08     13200561.98      2269824.21     13200674.25
       2270258.6     13200693.78
#Sta/Elev= 30
  4644.5  257.31  4685.3  254.94  4690.5  255.32  4759.1  250.56  4789.8  249.68
  4851.4  245.93  4861.7  244.32    4872  244.21  4902.7  241.29  4909.7  239.51
  4914.9  240.76  4923.2  239.06  4933.5  238.38  4952.6  230.84  4957.7  231.48
  4961.3   229.8    4964   229.3  4967.3   229.8  4974.5     230  5000.5  233.53
  5025.8  234.06  5036.1  235.06  5048.5  235.08  5056.6  236.28  5077.2  236.83
    5219  235.83  5319.4  237.96  5349.1  239.78  5509.3  246.07  5580.2  251.22
#Mann= 3 ,-1 , 0
  4644.5      .1       0  4961.3     .07       0  4967.3      .1       0
Bank Sta=4961.3,4967.3
XS Rating Curve= 0 ,0
Exp/Cntr=0.3,0.1

Type RM Length L Ch R = 1 ,13591   ,456,456,456
BEGIN DESCRIPTION:
JULIAN CREEK 24.0
END DESCRIPTION:
XS GIS Cut Line= 2
      2269350.77     13200869.49      2270263.12     13200859.73
#Sta/Elev= 30
  4644.2  258.92  4701.2  255.51  4731.2  252.85  4741.2  251.24  4771.2  249.48
  4791.2  249.16  4801.2  247.69  4841.2  245.29  4851.2  245.37  4911.2  241.34
  4921.2  238.55  4931.2  239.29  4941.2  239.05  4961.2  237.59  4971.2  234.72
  4981.2  233.73  4991.2  229.46  4998.2  228.95  5000.9  228.45  5004.2  228.95
  5011.2  230.57  5021.2  230.93  5051.2  233.98  5121.2  232.96  5161.2  234.44
  5231.2  235.16  5371.2  240.24  5481.2  243.38  5541.2  246.04  5556.6  247.72
#Mann= 3 ,-1 , 0
  4644.2      .1       0  4998.2     .07       0  5004.2      .1       0
Bank Sta=4998.2,5004.2
XS Rating Curve= 0 ,0
Exp/Cntr=0.3,0.1

Type RM Length L Ch R = 1 ,13135   ,335,335,335
BEGIN DESCRIPTION:
JULIAN CREEK 23.0
END DESCRIPTION:
XS GIS Cut Line= 3
      2269487.73     13201196.86      2269887.72     13201246.85
      2270287.72     13201246.85
#Sta/Elev= 30
  4596.9  248.84  4687.6  244.03  4727.9  242.63  4788.4  237.28    4801  237.28
  4848.8  233.46  4909.3  231.09  4929.5  230.98  4949.6  232.09  4957.2  231.69
  4969.8  230.01  4976.8   226.5  4979.6     226  4982.8   226.5  4989.9  228.38
  4997.5  232.45    5010  232.89    5020  231.93    5050  231.23    5110  231.93
    5180  234.29    5260  238.48    5270  240.44    5280  241.33    5290  244.21
    5310  248.41    5330  250.55    5340  250.87    5350  252.25    5400  255.36
#Mann= 3 ,-1 , 0
  4596.9      .1       0  4976.8     .07       0  4982.8      .1       0
Bank Sta=4976.8,4982.8
XS Rating Curve= 0 ,0
Exp/Cntr=0.3,0.1

Type RM Length L Ch R = 1 ,12800   ,446,446,446
BEGIN DESCRIPTION:
JULIAN CREEK 22.0
END DESCRIPTION:
XS GIS Cut Line= 3
      2269487.44      13201357.6      2269765.63     13201494.25
      2270384.15     13201460.16
#Sta/Elev= 30
  4386.8  246.33  4422.6   244.1  4445.1  243.61    4454   242.5  4529.5  240.11
  4718.9  235.01    4829  233.45  4859.1  231.94  4899.1  231.06  4929.2  231.42
  4949.2  230.68  4969.2  227.81  4979.3  227.87  4986.3  225.57    4989  225.07
  4992.3  225.57  5009.3  229.97  5019.3  230.65  5029.3  229.42  5049.4  228.76
  5059.4  230.05  5069.4  232.99  5079.4  234.62  5104.1  239.93  5109.5   245.1
  5119.5  247.56  5129.5  250.85  5219.6  255.71  5309.8  259.04  5316.2  259.82
#Mann= 3 ,-1 , 0
  4386.8      .1       0  4986.3     .07       0  4992.3      .1       0
Bank Sta=4986.3,4992.3
XS Rating Curve= 0 ,0
Exp/Cntr=0.3,0.1

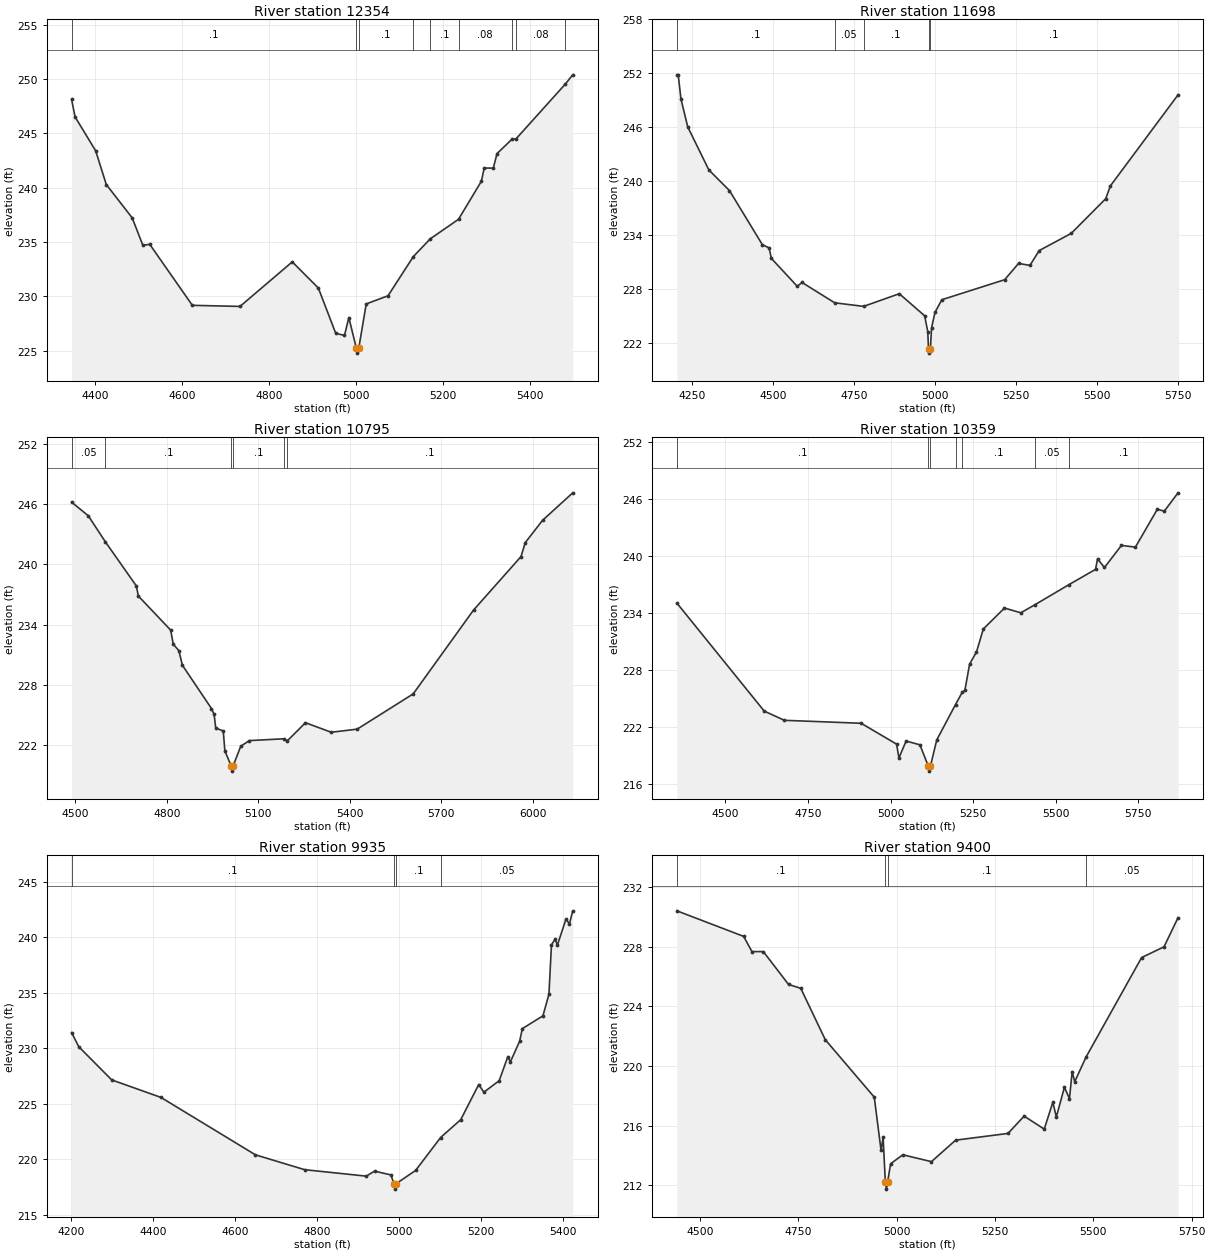
Type RM Length L Ch R = 1 ,12354   ,656,656,656
BEGIN DESCRIPTION:
JULIAN CREEK 21.0
END DESCRIPTION:
XS GIS Cut Line= 4
       2269370.3       13201792.      2269637.72     13201896.85
      2270212.72     13201871.85      2270448.95     13201704.14
#Sta/Elev= 30
  4346.5  248.13  4354.5  246.53  4401.9   243.4  4426.3   240.3  4485.9  237.23
  4510.3  234.71  4526.3  234.79  4624.2  229.18  4733.8  229.08    4854  233.18
    4914  230.77    4954   226.6  4974.1  226.41  4984.1  228.05  5001.1  225.28
  5003.8  224.78  5007.1  225.28  5024.1  229.31  5074.2  230.06  5132.5  233.67
  5171.3   235.3  5236.3   237.1    5289  240.61  5295.4  241.82  5316.3  241.81
  5324.9  243.15  5359.2  244.47  5368.5   244.5  5482.2  249.56    5499   250.4
#Mann= 9 ,-1 , 0
  4346.5      .1       0  5001.1     .07       0  5007.1      .1       0
  5132.5     .08       0  5171.3      .1       0  5236.3     .08       0
  5359.2      .1       0  5368.5     .08       0  5482.2      .1       0
Bank Sta=5001.1,5007.1
XS Rating Curve= 0 ,0
Exp/Cntr=0.3,0.1

Type RM Length L Ch R = 1 ,11698   ,903,903,903
BEGIN DESCRIPTION:
JULIAN CREEK 20.0
END DESCRIPTION:
XS GIS Cut Line= 4
       2269345.9     13201982.37      2269785.16     13202280.09
      2270136.59     13202402.11      2270633.58     13201987.95
#Sta/Elev= 30
    4202  251.83  4206.1  251.83  4214.6  249.13  4235.6  246.03  4300.8  241.25
  4364.4  238.96  4466.2  232.94  4487.2  232.57  4494.1  231.41    4574  228.31
    4589  228.73  4689.9  226.47  4779.3  226.07  4889.7  227.48  4968.2  225.02
  4977.7  223.26    4980  221.37  4982.8  220.87    4986  221.37  4989.4  223.68
    5000  225.39  5021.2  226.81  5215.6  229.04  5258.5  230.85  5293.7  230.63
  5322.3  232.28  5421.3  234.19    5528  238.05  5542.3  239.47  5751.6   249.6
#Mann= 5 ,-1 , 0
    4202      .1       0  4689.9     .05       0  4779.3      .1       0
    4980     .07       0    4986      .1       0
Bank Sta=4980,4986
XS Rating Curve= 0 ,0
Exp/Cntr=0.3,0.1

Type RM Length L Ch R = 1 ,10795   ,436,436,436
BEGIN DESCRIPTION:
JULIAN CREEK 19.0
END DESCRIPTION:
XS GIS Cut Line= 3
      2269409.28     13203080.58      2269887.72     13202896.85
      2270687.74     13202096.83
#Sta/Elev= 30
  4487.5  246.19  4542.2  244.84  4598.3  242.24  4700.1  237.84  4706.3  236.85
  4812.5  233.45    4821  232.05  4839.3  231.41    4851  229.95  4946.4  225.64
    4955  225.07  4960.3   223.7    4985  223.41  4990.3  221.43  5011.1  219.91
  5013.9  219.41  5017.1  219.91  5042.4  221.89  5070.7  222.45  5183.3  222.63
  5195.7  222.44  5254.6  224.23  5339.4  223.28  5424.3  223.59  5608.1   227.1
  5806.1  235.45  5961.7  240.77  5975.8  242.17  6032.4  244.38  6131.4  247.12
#Mann= 6 ,-1 , 0
  4487.5     .05       0  4598.3      .1       0  5011.1     .07       0
  5017.1      .1       0  5183.3     .16       0  5195.7      .1       0
Bank Sta=5011.1,5017.1
XS Rating Curve= 0 ,0
Exp/Cntr=0.3,0.1

Type RM Length L Ch R = 1 ,10359   ,424,424,424
BEGIN DESCRIPTION:
Mapping XS 88a0472d
END DESCRIPTION:
XS GIS Cut Line= 4
      2269687.58     13203085.43       2270209.8     13202987.82
      2270522.18     13202592.47      2270927.26     13202328.92
#Sta/Elev= 30
  4352.8  235.04  4617.4  223.67  4678.5   222.7    4911  222.39  5018.5  220.19
  5025.5  218.74  5047.3  220.52  5089.2  220.12  5114.8  217.85  5117.6  217.35
  5120.8  217.85  5140.2  220.64    5197  224.36  5217.7  225.67  5225.3  225.84
  5239.7  228.62  5260.5  229.89  5281.3  232.32  5345.4  234.52  5394.8  234.02
  5437.2  234.86    5541  236.99  5621.2  238.59  5627.3  239.69  5648.4  238.79
  5699.8  241.12    5742  240.93  5808.5  244.92  5829.6  244.72  5871.2  246.65
#Mann= 7 ,-1 , 0
  4352.8      .1       0  5114.8     .07       0  5120.8      .1       0
    5197     .16       0  5217.7      .1       0  5437.2     .05       0
    5541      .1       0
Bank Sta=5114.8,5120.8
XS Rating Curve= 0 ,0
Exp/Cntr=0.3,0.1

Type RM Length L Ch R = 1 ,9935    ,535,535,535
BEGIN DESCRIPTION:
JULIAN CREEK 18.0
END DESCRIPTION:
XS GIS Cut Line= 3
      2269790.07     13203129.37      2270762.72     13203096.85
      2270961.43      13202948.8
#Sta/Elev= 30
  4201.9   231.4  4219.6  230.12  4299.6  227.14  4419.7  225.56  4649.8  220.39
  4769.9  219.05    4920  218.47    4940  218.92    4980  218.58    4987   217.8
  4989.7   217.3    4993   217.8    5040  218.98    5101  221.95  5150.1  223.56
  5193.8  226.72  5206.4  226.03  5243.7  227.07  5264.8  229.23    5271  228.76
  5293.6  230.63  5300.2  231.76  5350.3  232.91  5364.9  234.85  5371.1   239.3
  5379.5   239.8  5385.7   239.3  5406.5  241.63  5414.9  241.19  5422.9  242.37
#Mann= 4 ,-1 , 0
  4201.9      .1       0    4987     .07       0    4993      .1       0
    5101     .05       0
Bank Sta=4987,4993
XS Rating Curve= 0 ,0
Exp/Cntr=0.3,0.1

Type RM Length L Ch R = 1 ,9400    ,497,497,497
BEGIN DESCRIPTION:
JULIAN CREEK 17.0
END DESCRIPTION:
XS GIS Cut Line= 4
       2269814.4     13203231.86      2270444.09     13203407.59
      2270775.99      13203480.8      2270987.72     13203296.86
#Sta/Elev= 30
  4441.3  230.39  4610.9  228.68  4632.1  227.66    4661  227.66  4725.1  225.46
  4756.2   225.2  4818.5  221.76  4943.1  217.91  4960.4  214.34  4965.6  215.24
  4971.2  212.25    4974  211.75  4977.2  212.25  4984.6  213.45  5015.8  214.05
  5088.4  213.59    5150  215.03  5283.1  215.48  5324.1  216.64  5375.3  215.77
  5397.1  217.57    5406  216.58  5426.5  218.57  5439.4  217.81  5446.2  219.61
  5452.8  218.95  5481.8  220.61  5622.8  227.26  5679.8  227.98  5715.4  229.93
#Mann= 4 ,-1 , 0
  4441.3      .1       0  4971.2     .07       0  4977.2      .1       0
  5481.8     .05       0
Bank Sta=4971.2,4977.2
XS Rating Curve= 0 ,0
Exp/Cntr=0.3,0.1

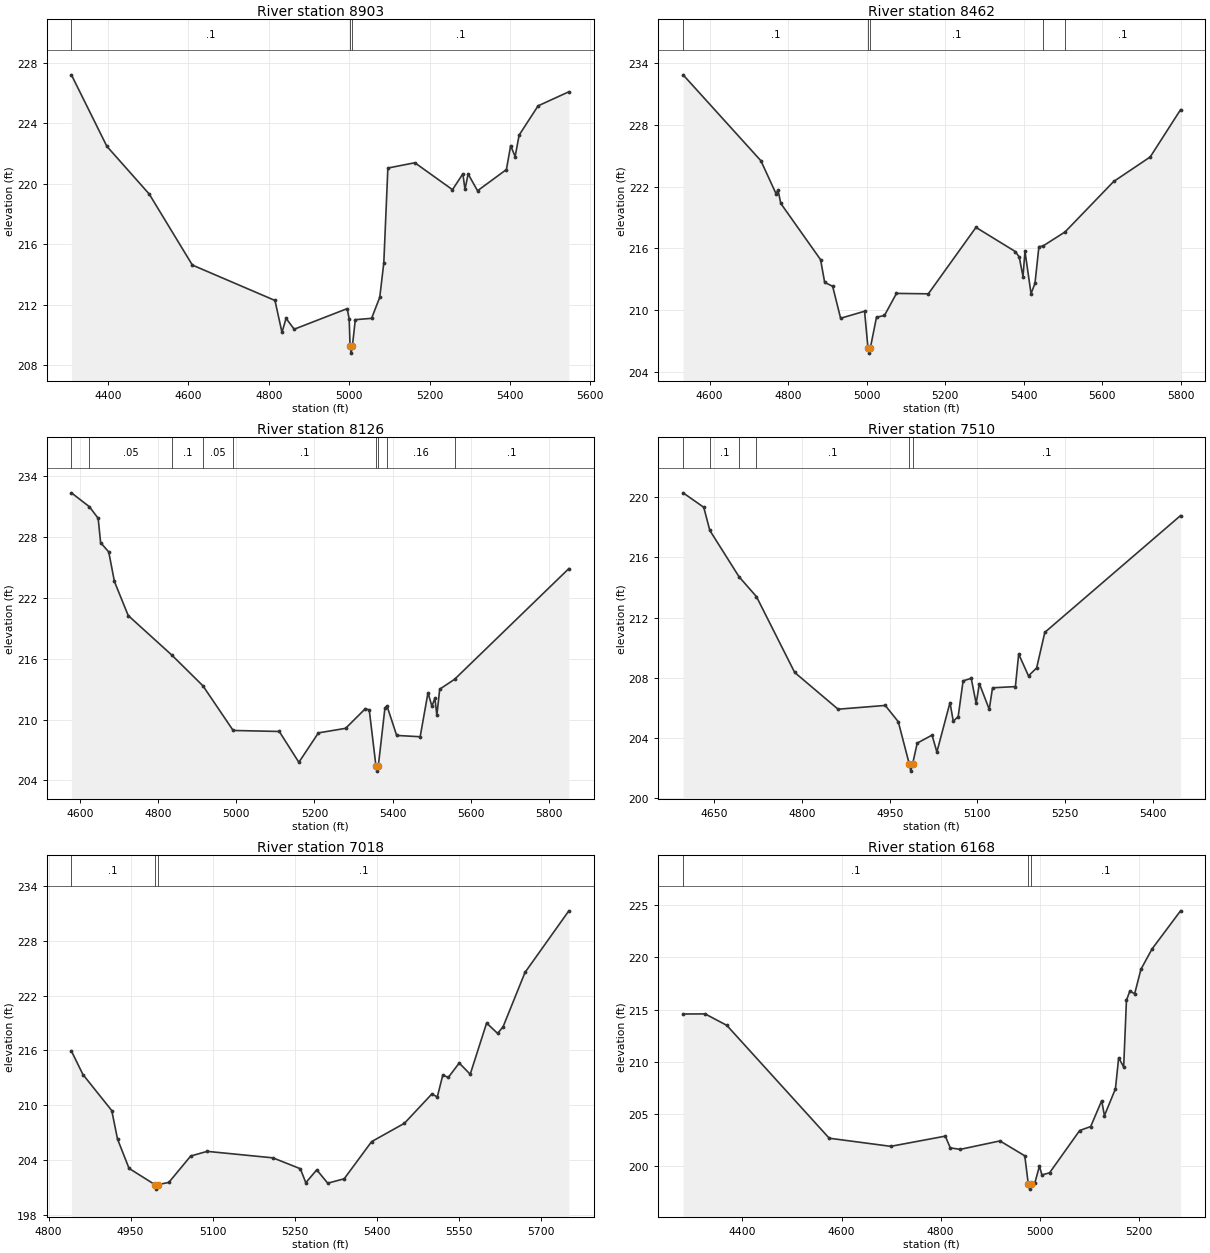
Type RM Length L Ch R = 1 ,8903    ,441,441,441
BEGIN DESCRIPTION:
JULIAN CREEK 16.0
END DESCRIPTION:
XS GIS Cut Line= 3
      2269760.79     13203680.93      2270570.99      13203812.7
       2270964.5     13203676.68
#Sta/Elev= 30
  4309.1  227.19  4397.2  222.47  4502.7  219.31  4609.9  214.62  4815.4  212.28
  4832.8  210.17    4843   211.1  4863.2  210.38  4994.9  211.74    5000  211.05
  5002.1   209.3  5004.8   208.8  5008.1   209.3  5015.2  211.01  5055.7   211.1
    5076  212.49  5086.1  214.77  5096.2  221.03  5163.3  221.38  5256.9   219.6
  5282.7  220.65    5288  219.62  5295.8  220.64  5319.2  219.53    5391  220.93
  5401.6  222.51  5412.7  221.79  5422.7  223.21  5469.8  225.14  5546.3  226.07
#Mann= 3 ,-1 , 0
  4309.1      .1       0  5002.1     .07       0  5008.1      .1       0
Bank Sta=5002.1,5008.1
XS Rating Curve= 0 ,0
Exp/Cntr=0.3,0.1

Type RM Length L Ch R = 1 ,8462    ,336,336,336
BEGIN DESCRIPTION:
JULIAN CREEK 15.0
END DESCRIPTION:
XS GIS Cut Line= 3
      2269682.66     13203910.32      2270375.75     13204032.35
      2270937.68     13203996.86
#Sta/Elev= 30
  4532.4  232.83  4730.5   224.5    4769  221.31    4774  221.67  4781.2  220.36
  4882.5  214.91  4892.9  212.71  4913.2  212.33  4933.5  209.23  4994.5  209.91
  5003.2  206.35  5005.9  205.85  5009.2  206.35  5024.9  209.33  5045.2   209.5
  5075.7  211.64  5156.9   211.6  5278.2  218.04  5378.4   215.7  5388.4  215.17
    5398  213.27    5403  215.73  5418.5  211.61  5428.5  212.62  5438.5  216.17
  5448.6  216.23  5505.1   217.6  5628.9  222.49    5722  224.87  5799.2  229.45
#Mann= 5 ,-1 , 0
  4532.4      .1       0  5003.2     .07       0  5009.2      .1       0
  5448.6     .16       0  5505.1      .1       0
Bank Sta=5003.2,5009.2
XS Rating Curve= 0 ,0
Exp/Cntr=0.3,0.1

Type RM Length L Ch R = 1 ,8126    ,616,616,616
BEGIN DESCRIPTION:
JULIAN CREEK 14.0
END DESCRIPTION:
XS GIS Cut Line= 3
      2269672.91     13204456.98      2269887.66     13204291.04
      2270887.69     13204246.86
#Sta/Elev= 30
  4578.4  232.35  4624.4  230.98  4646.8  229.84  4653.1  227.44  4673.9  226.52
  4688.4  223.61  4723.7  220.25  4835.3  216.35  4914.9  213.32  4992.1  208.92
  5110.1  208.82  5160.2  205.78  5210.2  208.68  5279.8  209.13  5330.3  211.07
  5340.3  210.94  5357.4  205.41  5360.1  204.91  5363.4  205.41  5380.4  211.14
  5385.6  211.34  5410.4  208.43  5470.5   208.3  5490.5  212.64  5500.5  211.32
  5508.2   212.1  5513.2  210.41  5520.5  212.99  5558.4  213.96  5850.8  224.88
#Mann= 9 ,-1 , 0
  4578.4      .1       0  4624.4     .05       0  4835.3      .1       0
  4914.9     .05       0  4992.1      .1       0  5357.4     .07       0
  5363.4      .1       0  5385.6     .16       0  5558.4      .1       0
Bank Sta=5357.4,5363.4
XS Rating Curve= 0 ,0
Exp/Cntr=0.3,0.1

Type RM Length L Ch R = 1 ,7510    ,492,492,492
BEGIN DESCRIPTION:
JULIAN CREEK 13.0
END DESCRIPTION:
XS GIS Cut Line= 3
      2270037.73     13204896.85      2270387.72     13204696.85
      2270787.71     13204496.86
#Sta/Elev= 30
  4596.9  220.28  4632.2  219.32  4642.5  217.79  4692.5  214.71  4722.3  213.39
  4787.6  208.36  4861.8  205.92  4942.4  206.17  4964.7  205.09  4983.3  202.31
  4986.1  201.81  4989.3  202.31  4997.1  203.67  5022.4   204.2  5030.7  203.08
  5053.1  206.36  5058.7  205.12  5067.1  205.43  5075.5   207.8  5089.4  207.97
  5097.8   206.3  5103.4  207.61  5120.2  205.91  5125.8  207.34  5164.9  207.42
  5170.5  209.58  5187.3  208.13  5201.2  208.66  5215.2  211.02  5447.2  218.77
#Mann= 6 ,-1 , 0
  4596.9     .05       0  4642.5      .1       0  4692.5     .05       0
  4722.3      .1       0  4983.3     .07       0  4989.3      .1       0
Bank Sta=4983.3,4989.3
XS Rating Curve= 0 ,0
Exp/Cntr=0.3,0.1

Type RM Length L Ch R = 1 ,7018    ,850,850,850
BEGIN DESCRIPTION:
JULIAN CREEK 12.0
END DESCRIPTION:
XS GIS Cut Line= 3
      2270187.73     13205046.86      2270337.72     13205096.86
      2271087.76     13205146.86
#Sta/Elev= 30
  4841.9  215.93    4863  213.36  4915.7  209.42  4926.2  206.31  4947.3   203.1
  4994.4  201.33  4997.1  200.83  5000.4  201.33    5020  201.56  5060.1  204.45
  5090.2  204.96  5210.5  204.25  5260.6  203.06  5270.6  201.53  5290.6  202.94
  5310.7  201.48  5340.8  201.96  5390.9  206.02    5451  208.03  5501.1  211.23
  5511.1  210.91  5521.2  213.31  5531.2  213.04  5551.2  214.62  5571.3  213.39
  5601.3  218.99  5621.4  217.86  5631.4  218.58  5671.5  224.52  5751.7  231.26
#Mann= 3 ,-1 , 0
  4841.9      .1       0  4994.4     .07       0  5000.4      .1       0
Bank Sta=4994.4,5000.4
XS Rating Curve= 0 ,0
Exp/Cntr=0.3,0.1

Type RM Length L Ch R = 1 ,6168    ,553,553,553
BEGIN DESCRIPTION:
JULIAN CREEK 11.0
END DESCRIPTION:
XS GIS Cut Line= 4
      2270102.42      13205301.4      2270346.47     13205433.18
      2270862.72     13205396.85      2271048.89     13205301.62
#Sta/Elev= 30
  4280.3  214.57  4324.7  214.58  4368.5  213.48  4575.2  202.64  4699.3  201.86
  4809.5  202.84  4819.6  201.71  4839.6  201.57  4919.8  202.38  4969.9  200.95
    4977  198.25  4979.7  197.75    4983  198.25    4990  198.31  4999.5  199.96
  5004.5  199.11    5020  199.32  5080.7  203.38  5102.9  203.76  5125.1  206.24
  5130.7  204.81  5152.9  207.39  5159.4  210.37  5169.5  209.48  5175.1  215.88
  5181.9  216.77  5191.7  216.52  5204.4  218.87  5226.8  220.82  5284.3  224.48
#Mann= 3 ,-1 , 0
  4280.3      .1       0    4977     .07       0    4983      .1       0
Bank Sta=4977,4983
XS Rating Curve= 0 ,0
Exp/Cntr=0.3,0.1