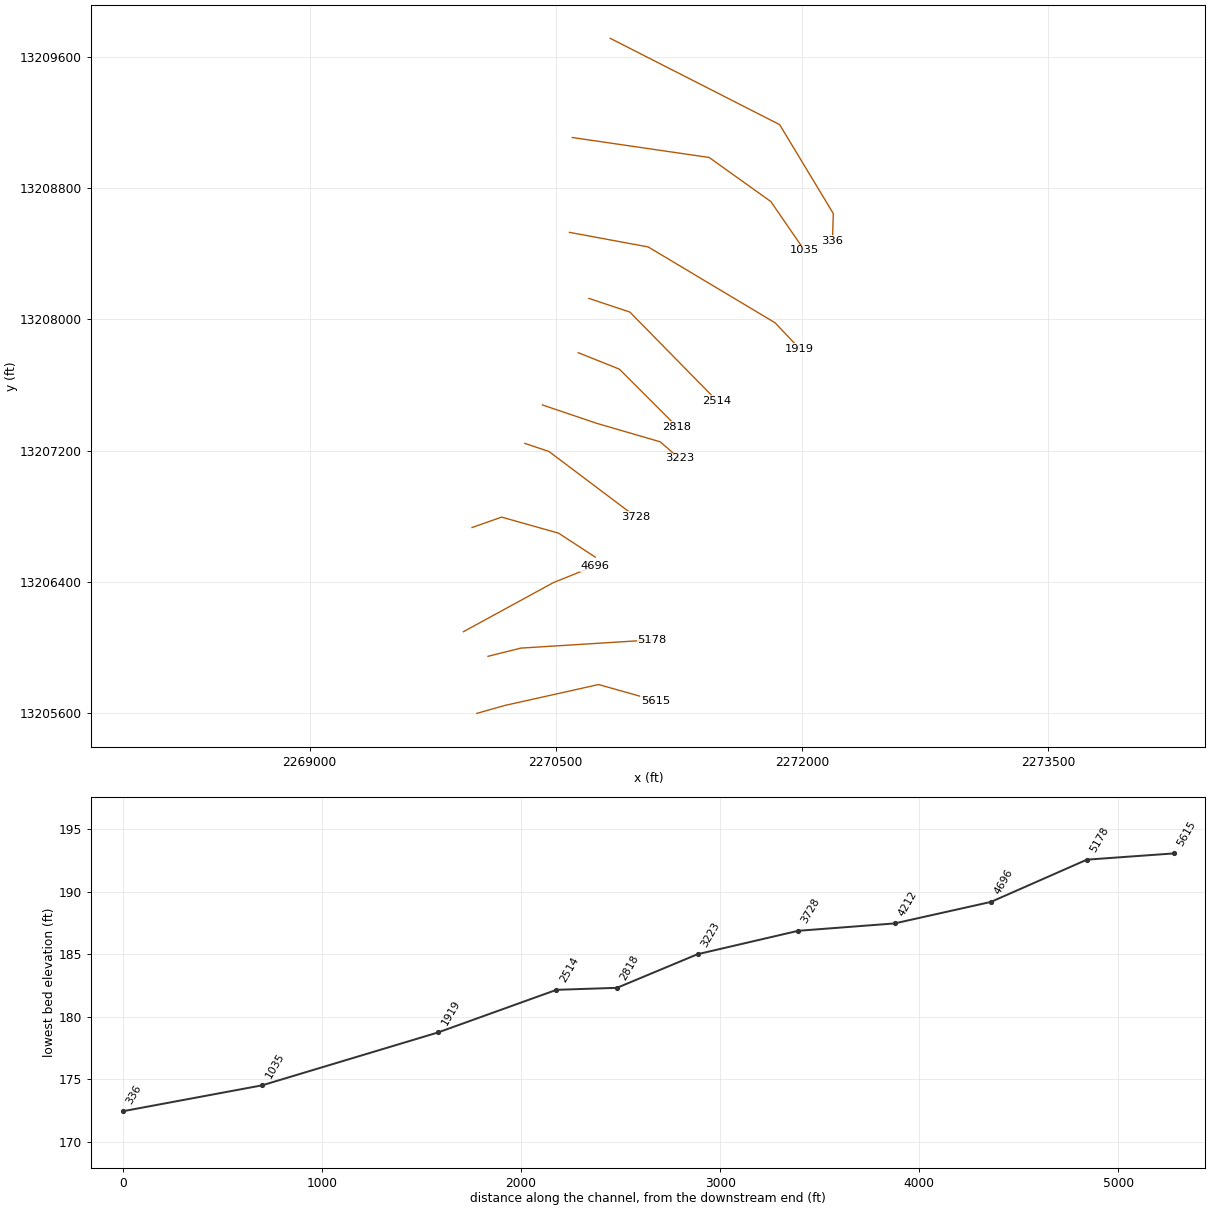
HEC-RAS study JULIAN CREEK.prj: JULIAN CREEK Base Level Engineering

--- JULIAN CREEK.g01 (geometry) --- (continued)

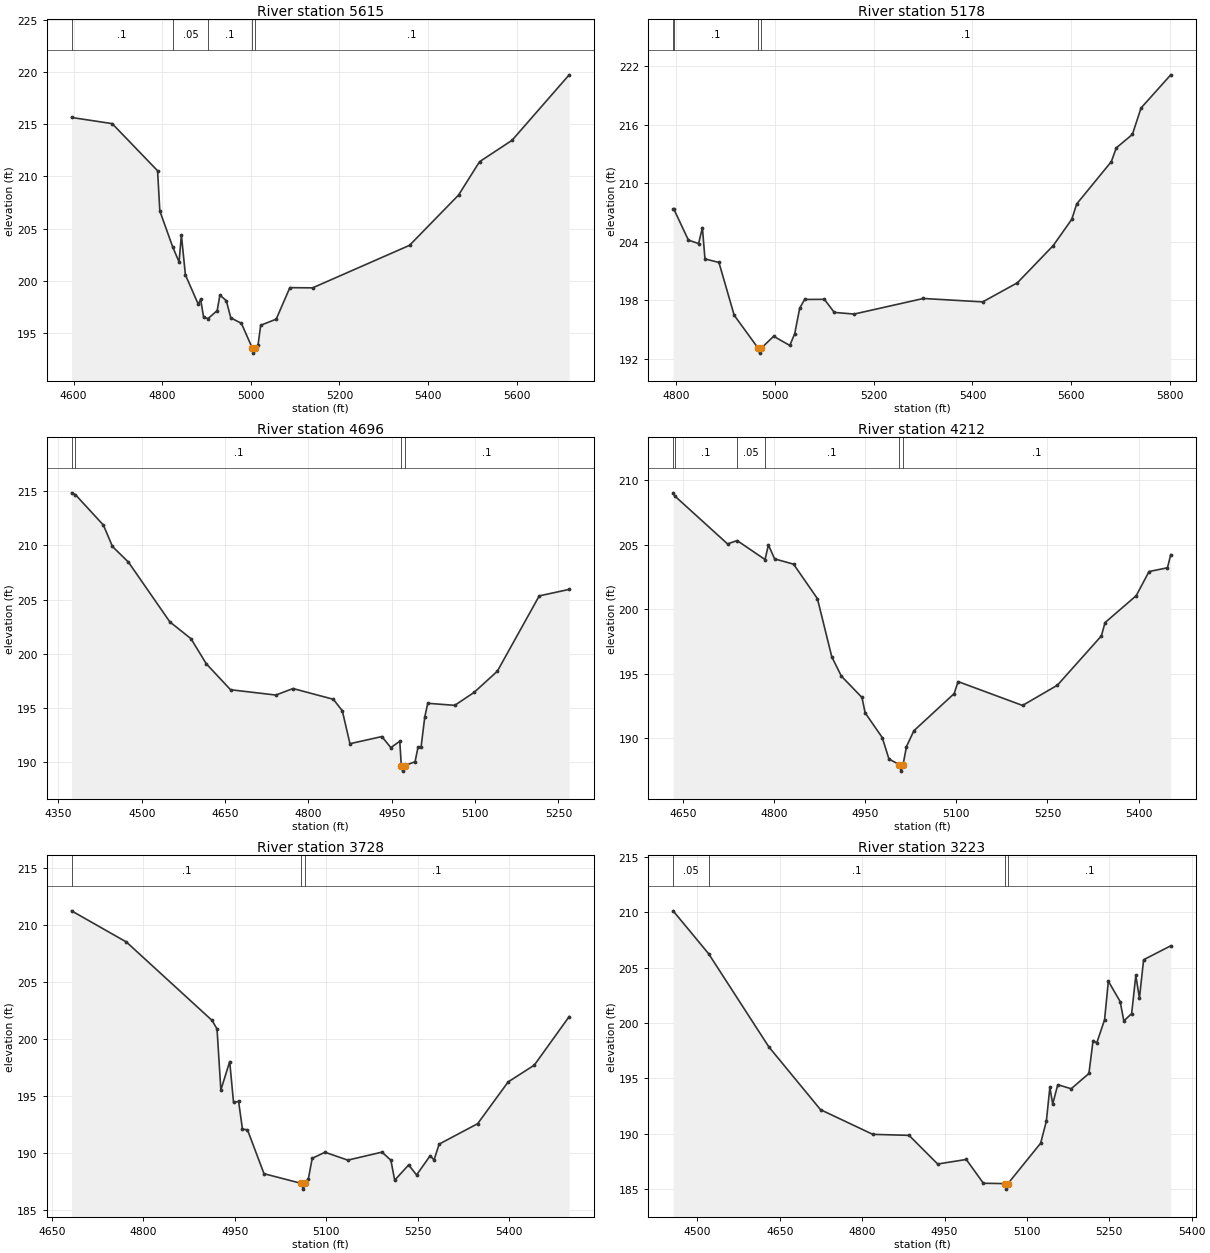
Type RM Length L Ch R = 1 ,5615    ,437,437,437
BEGIN DESCRIPTION:
JULIAN CREEK 10.0
END DESCRIPTION:
XS GIS Cut Line= 4
      2270019.45     13205599.14      2270187.72     13205646.85
      2270761.35     13205774.85      2271107.92     13205677.22
#Sta/Elev= 30
  4595.5  215.66  4687.2  215.07  4789.6  210.55  4794.7  206.69  4824.1   203.2
  4838.1  201.81  4843.3  204.39  4852.4  200.56  4881.6  197.73  4886.7  198.23
  4893.4  196.51  4903.6  196.38  4924.1  197.14  4930.2  198.63  4944.6  198.09
  4954.8  196.44  4978.7  195.92  5003.1  193.56  5005.8  193.06  5009.1  193.56
  5016.3  193.85  5022.2  195.73  5057.3  196.32    5088  199.34  5139.3  199.32
  5358.1   203.4  5468.6  208.22    5516  211.42  5589.3  213.47  5718.2  219.75
#Mann= 5 ,-1 , 0
  4595.5      .1       0  4824.1     .05       0  4903.6      .1       0
  5003.1     .07       0  5009.1      .1       0
Bank Sta=5003.1,5009.1
XS Rating Curve= 0 ,0
Exp/Cntr=0.3,0.1

Type RM Length L Ch R = 1 ,5178    ,482,482,482
BEGIN DESCRIPTION:
JULIAN CREEK 9.0
END DESCRIPTION:
XS GIS Cut Line= 3
      2270087.68     13205946.84      2270287.72     13205996.85
      2271087.76     13206046.86
#Sta/Elev= 30
  4793.8  207.36  4795.1  207.36  4824.8  204.16  4845.4  203.81  4853.1  205.44
  4858.3  202.23  4886.6  201.87  4917.5  196.45  4966.1  193.06  4968.8  192.56
  4972.1  193.06  4997.4  194.29  5030.1  193.35  5040.1  194.56  5050.1  197.16
  5060.1  198.07  5100.2  198.08  5120.2  196.74  5160.3  196.57  5300.6  198.17
  5420.8  197.82    5491  199.78  5563.6   203.6  5601.2   206.3  5611.2  207.88
  5681.3  212.22  5691.3  213.63  5723.9  215.01  5741.4  217.72  5801.6  221.13
#Mann= 4 ,-1 , 0
  4793.8     .05       0  4795.1      .1       0  4966.1     .07       0
  4972.1      .1       0
Bank Sta=4966.1,4972.1
XS Rating Curve= 0 ,0
Exp/Cntr=0.3,0.1

Type RM Length L Ch R = 1 ,4696    ,484,484,484
BEGIN DESCRIPTION:
JULIAN CREEK 8.0
END DESCRIPTION:
XS GIS Cut Line= 3
      2269937.72     13206096.85      2270487.72     13206396.85
      2270737.76     13206496.87
#Sta/Elev= 30
  4373.5  214.86  4380.3   214.7  4430.9  211.88  4447.1  209.91    4476  208.46
  4550.5  202.95  4588.5   201.4    4616  199.09  4659.7  196.69  4741.3   196.2
  4772.2   196.8  4844.8  195.81  4860.9  194.75  4874.7  191.71  4932.1  192.37
  4948.3  191.35  4964.4  191.94  4967.1  189.68  4969.8  189.18  4973.1  189.68
  4991.9  190.05  4997.2   191.4  5002.7   191.4  5009.4  194.19  5014.8  195.44
  5063.3  195.25  5098.3  196.45    5140   198.4  5215.4  205.35  5269.3  205.95
#Mann= 4 ,-1 , 0
  4373.5     .05       0  4380.3      .1       0  4967.1     .07       0
  4973.1      .1       0
Bank Sta=4967.1,4973.1
XS Rating Curve= 0 ,0
Exp/Cntr=0.3,0.1

Type RM Length L Ch R = 1 ,4212    ,484,484,484
BEGIN DESCRIPTION:
JULIAN CREEK 7.0
END DESCRIPTION:
XS GIS Cut Line= 4
      2269990.12      13206731.5      2270170.75     13206794.97
       2270517.3     13206697.35      2270741.11     13206551.38
#Sta/Elev= 30
  4634.2  209.03  4636.6   208.8  4723.8  205.07  4739.5  205.33  4785.4  203.86
    4791  204.99  4801.2  203.91  4832.4   203.5  4871.6  200.83  4895.2  196.33
  4910.9  194.83  4944.9  193.17  4950.1  191.98  4978.3  190.06  4989.3   188.4
  5006.5  187.96  5009.3  187.46  5012.5  187.96  5018.1  189.36  5030.3  190.59
  5096.6  193.47    5103   194.4  5209.1  192.55  5266.4  194.12  5338.8  197.94
  5344.8  198.97  5396.1  201.06  5417.2  202.93  5447.5  203.22  5452.9  204.24
#Mann= 6 ,-1 , 0
  4634.2     .05       0  4636.6      .1       0  4739.5     .05       0
  4785.4      .1       0  5006.5     .07       0  5012.5      .1       0
Bank Sta=5006.5,5012.5
XS Rating Curve= 0 ,0
Exp/Cntr=0.3,0.1

Type RM Length L Ch R = 1 ,3728    ,505,505,505
BEGIN DESCRIPTION:
JULIAN CREEK 6.0
END DESCRIPTION:
XS GIS Cut Line= 3
      2270312.34       13207244.      2270458.73      13207195.2
      2270987.71     13206796.86
#Sta/Elev= 30
  4682.2  211.24  4772.2  208.51  4912.6  201.65  4920.9   200.9  4927.2  195.55
  4941.7  198.04    4948  194.46  4956.3  194.55  4962.6  192.13  4970.9  192.06
    4998  188.22  5059.5  187.37  5062.3  186.87  5065.5  187.37  5070.8  187.78
  5077.1  189.57  5098.1   190.1  5135.4  189.41  5191.6  190.11  5206.2   189.4
  5212.4  187.65  5235.3  188.99  5248.3  188.11  5270.7   189.8    5277  189.42
  5285.3  190.81  5348.5   192.6  5398.6  196.26  5441.5  197.73  5498.7  201.98
#Mann= 3 ,-1 , 0
  4682.2      .1       0  5059.5     .07       0  5065.5      .1       0
Bank Sta=5059.5,5065.5
XS Rating Curve= 0 ,0
Exp/Cntr=0.3,0.1

Type RM Length L Ch R = 1 ,3223    ,405,405,405
BEGIN DESCRIPTION:
JULIAN CREEK 5.0
END DESCRIPTION:
XS GIS Cut Line= 4
      2270419.72     13207478.29      2270751.59     13207366.04
      2271137.18     13207253.78       2271253.2     13207152.26
#Sta/Elev= 30
  4455.8  210.15  4520.5  206.27  4629.9  197.87  4724.2  192.18  4819.4  189.95
  4885.4  189.86  4937.5  187.27  4989.6  187.68  5020.8  185.53  5059.5   185.5
  5062.2     185  5065.5   185.5    5125  189.15  5135.4  191.14  5141.8  194.19
    5147  192.69  5156.2  194.44  5180.6  194.07  5212.9  195.45  5220.5  198.43
  5227.1   198.2  5241.4   200.3  5248.3  203.79  5269.8  201.95  5276.5   200.2
  5290.7  200.86  5298.3  204.31  5304.9  202.26  5312.5  205.73  5361.9  206.99
#Mann= 4 ,-1 , 0
  4455.8     .05       0  4520.5      .1       0  5059.5     .07       0
  5065.5      .1       0
Bank Sta=5059.5,5065.5
XS Rating Curve= 0 ,0
Exp/Cntr=0.3,0.1

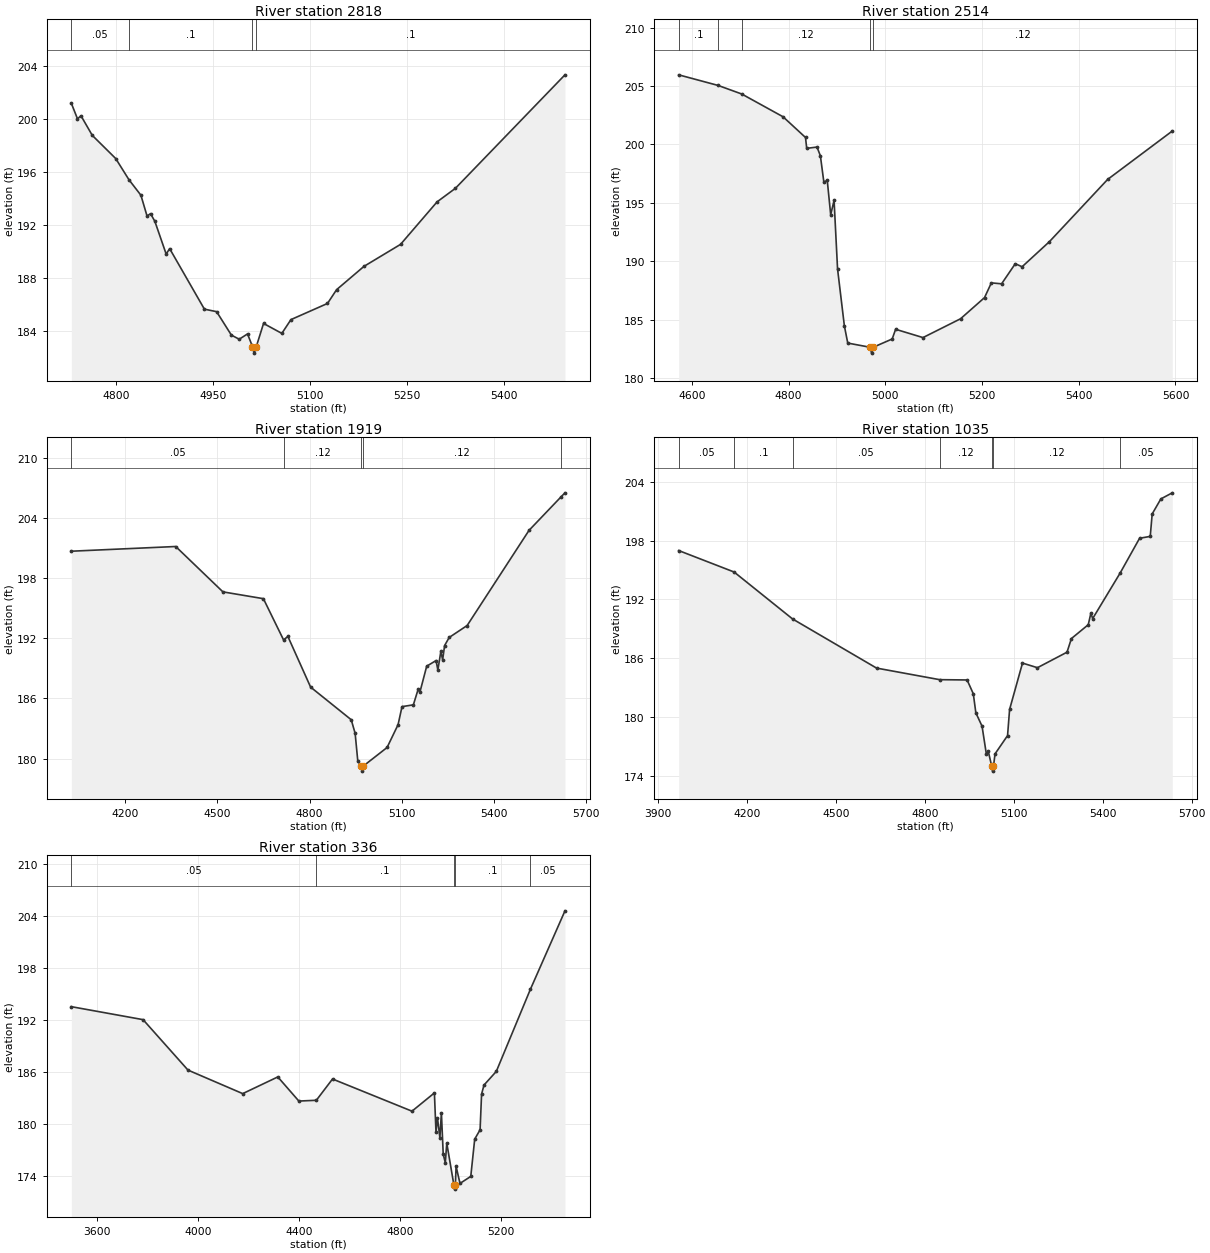
Type RM Length L Ch R = 1 ,2818    ,304,304,304
BEGIN DESCRIPTION:
JULIAN CREEK 4.0
END DESCRIPTION:
XS GIS Cut Line= 3
      2270637.68     13207796.87      2270887.72     13207696.85
      2271237.74     13207346.84
#Sta/Elev= 30
  4730.7  201.17  4740.2     200  4745.6  200.23  4763.1  198.75  4799.4     197
  4819.9   195.4  4838.4  194.23  4847.9  192.66  4853.3  192.84    4860  192.26
  4877.5  189.79  4882.9   190.2  4936.7  185.63  4955.6  185.44  4978.5  183.67
  4990.6  183.36  5003.5  183.76  5011.1  182.81  5013.9  182.31  5017.1  182.81
  5028.3  184.55  5056.6   183.8  5070.7  184.84  5127.3  186.06  5141.4   187.1
  5183.8  188.86  5240.4  190.52    5297  193.73  5325.3  194.75    5495  203.32
#Mann= 4 ,-1 , 0
  4730.7     .05       0  4819.9      .1       0  5011.1     .07       0
  5017.1      .1       0
Bank Sta=5011.1,5017.1
XS Rating Curve= 0 ,0
Exp/Cntr=0.3,0.1

Type RM Length L Ch R = 1 ,2514    ,595,595,595
BEGIN DESCRIPTION:
JULIAN CREEK 3.0
END DESCRIPTION:
XS GIS Cut Line= 3
      2270702.79     13208127.46      2270951.71     13208044.49
      2271483.23     13207503.21
#Sta/Elev= 30
  4572.4  205.96  4654.2  205.05  4702.9  204.32  4788.4  202.37  4834.8   200.6
  4837.3  199.67  4858.6  199.78  4865.6  199.03  4872.8  196.77  4879.8  196.93
  4886.9  193.99  4893.9  195.22  4901.1  189.35  4915.2  184.48  4922.2  183.01
  4968.7  182.65  4971.4  182.15  4974.7  182.65  5014.1  183.36  5021.2  184.19
  5077.8  183.48  5155.5  185.09  5205.1   186.9  5219.2  188.16  5240.4  188.08
  5268.7   189.8  5282.8  189.54  5339.4  191.69  5459.7  197.01  5593.4  201.15
#Mann= 5 ,-1 , 0
  4572.4      .1       0  4654.2     .05       0  4702.9     .12       0
  4968.7     .07       0  4974.7     .12       0
Bank Sta=4968.7,4974.7
XS Rating Curve= 0 ,0
Exp/Cntr=0.3,0.1

Type RM Length L Ch R = 1 ,1919    ,884,884,884
BEGIN DESCRIPTION:
Mapping XS 2bd5d95e
END DESCRIPTION:
XS GIS Cut Line= 4
      2270583.58     13208530.23      2271063.54     13208441.35
      2271836.83     13207979.16      2271986.65     13207820.52
#Sta/Elev= 30
  4024.3   200.7  4364.1  201.17  4517.8  196.64  4649.6  195.96  4715.3  191.84
  4729.3  192.19  4803.3  187.13  4935.6  183.87  4948.3  182.51  4956.9  179.76
  4968.6  179.24  4971.4  178.74  4974.6  179.24  5052.3   181.1  5088.1  183.38
  5100.9  185.18  5137.9  185.36  5153.4  186.91  5159.3  186.64  5181.3  189.22
  5211.8  189.78  5217.6  188.84  5227.4  190.69  5233.2  189.86  5239.6  191.28
  5254.6  192.09    5313  193.28  5514.4  202.78  5617.5  206.09  5631.5  206.53
#Mann= 5 ,-1 , 0
  4024.3     .05       0  4715.3     .12       0  4968.6     .07       0
  4974.6     .12       0  5617.5     .05       0
Bank Sta=4968.6,4974.6
XS Rating Curve= 0 ,0
Exp/Cntr=0.3,0.1

Type RM Length L Ch R = 1 ,1035    ,699,699,699
BEGIN DESCRIPTION:
Mapping XS f0a0cce0
END DESCRIPTION:
XS GIS Cut Line= 4
       2270601.3     13209107.98      2271434.92     13208986.51
      2271810.75     13208718.06       2272015.2     13208421.13
#Sta/Elev= 30
  3969.8  196.99  4156.9   194.8  4353.9  190.02  4637.3  185.01  4850.1  183.83
  4942.7   183.8  4963.6  182.39  4972.2  180.45  4993.1  179.09  5007.8  176.21
    5014  176.54  5025.7  175.01  5028.5  174.51  5031.7  175.01  5036.9  176.27
  5079.1  178.13    5086   180.8  5129.5  185.52  5179.9  185.05  5279.6  186.63
  5294.5  188.02  5351.3  189.43  5360.1   190.6  5366.2  190.06  5458.5  194.68
  5524.4  198.24  5560.3  198.43  5566.9  200.72  5596.1  202.25  5634.6  202.87
#Mann= 7 ,-1 , 0
  3969.8     .05       0  4156.9      .1       0  4353.9     .05       0
  4850.1     .12       0  5025.7     .07       0  5031.7     .12       0
  5458.5     .05       0
Bank Sta=5025.7,5031.7
XS Rating Curve= 0 ,0
Exp/Cntr=0.3,0.1

Type RM Length L Ch R = 1 ,336     ,0,0,0
BEGIN DESCRIPTION:
JULIAN CREEK 1.0
END DESCRIPTION:
XS GIS Cut Line= 4
      2270832.44     13209712.38      2271864.44     13209186.63
      2272191.47     13208644.85      2272186.63     13208480.36
#Sta/Elev= 30
  3498.5  193.53  3782.7  192.03  3960.6   186.2  4177.4  183.48  4316.4  185.41
  4399.8  182.62  4469.1  182.71  4533.2  185.17    4848  181.45  4936.8  183.56
  4943.1  179.03    4949  180.66  4958.6  178.37  4964.5  181.27  4971.8  176.46
    4980  175.49  4985.8  177.76  5013.9  172.94  5016.6  172.44  5019.9  172.94
  5022.7  175.08  5038.2   173.1  5080.9  173.91  5096.5  178.22  5117.8   179.3
  5123.7  183.42  5133.3  184.47  5182.1  186.05  5317.1  195.54  5454.1  204.61
#Mann= 5 ,-1 , 0
  3498.5     .05       0  4469.1      .1       0  5013.9     .07       0
  5019.9      .1       0  5317.1     .05       0
Bank Sta=5013.9,5019.9
XS Rating Curve= 0 ,0
Exp/Cntr=0.3,0.1

Chan Stop Cuts=-1
Use User Specified Reach Order=0
Composite Channel Slope=5