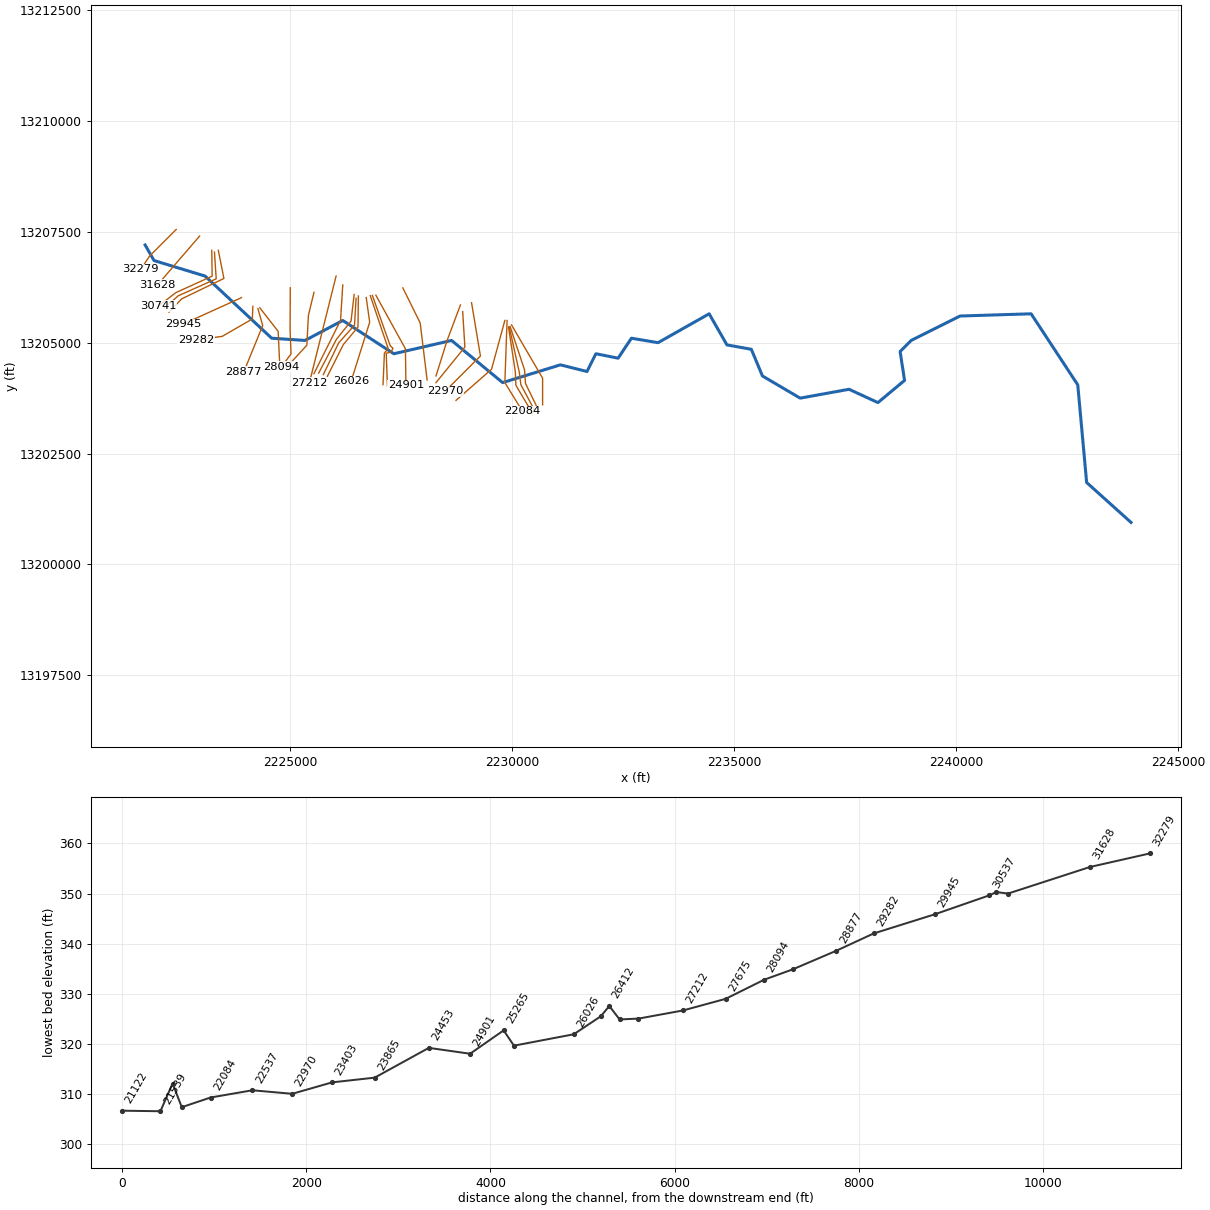
--- KENTUCK CREEK.prj (project) ---

Proj Title=KENTUCK CREEK Base Level Engineering
Current Plan=p01
Default Exp/Contr=0.3,0.1
English Units
Geom File=g01
Flow File=f01
Plan File=p01
Y Axis Title=Elevation
X Axis Title(PF)=Main Channel Distance
X Axis Title(XS)=Station
BEGIN DESCRIPTION:
KENTUCK CREEK
END DESCRIPTION:
DSS Export Rating Curves= 0
DSS Export Rating Curve Sorted= 0
DSS Export Volume Flow Curves= 0
DXF OffsetX= 0
DXF OffsetY= 0
DXF ScaleX= 1
DXF ScaleY= 10

--- KENTUCK CREEK.p01 (plan) ---

Plan Title=Multiple Run
Short Identifier=Multiple
Geom File=g01
Flow File=f01
Subcritical Flow
K Sum by GR= 0
Std Step Tol= 0.01
Critical Tol= 0.01
Num of Std Step Trials= 20
Max Error Tol= 0.3
Flow Tol Ratio= 0.001
Split Flow NTrial= 30
Split Flow Tol= 0.02
Split Flow Ratio= 0.02
Log Output Level= 0
Friction Slope Method= 1
Unsteady Friction Slope Method= 2
Unsteady Bridges Friction Slope Method= 1
Parabolic Critical Depth
Global Vel Dist=  1 , 1 , 1
Global Log Level= 0
CheckData=True
Encroach Param= -1, 0, 0, 0
BEGIN DESCRIPTION:
Multiple Run
END DESCRIPTION:

--- KENTUCK CREEK.f01 (steady flow) ---

Flow Title=Multiple
Program Version=4.10
Number of Profiles= 7
Profile Names=10-year,25-year,50-year,1pct_min,100-year,1pct_plu,500-year
River Rch & RM=KENTUCK CREEK,Reach-1         ,32279
     187     257     314     283     382     517     576
River Rch & RM=KENTUCK CREEK,Reach-1         ,28877
     477     686     866     802    1084    1466    1728
River Rch & RM=KENTUCK CREEK,Reach-1         ,28405
     477     686     866     802    1084    1466    1728
River Rch & RM=KENTUCK CREEK,Reach-1         ,27212
     477     686     866     802    1084    1466    1728
River Rch & RM=KENTUCK CREEK,Reach-1         ,22084
     536     775     980     910    1231    1665    1974
River Rch & RM=KENTUCK CREEK,Reach-1         ,19428
     590     854    1083    1007    1362    1841    2188
River Rch & RM=KENTUCK CREEK,Reach-1         ,17112
     616     893    1131    1052    1422    1923    2284
River Rch & RM=KENTUCK CREEK,Reach-1         ,11391
     628     910    1153    1072    1449    1960    2326
River Rch & RM=KENTUCK CREEK,Reach-1         ,7480
     947    1394    1786    1676    2267    3066    3712
River Rch & RM=KENTUCK CREEK,Reach-1         ,6317
    1093    1614    2074    1951    2638    3568    4340
Boundary for River Rch & Prof#=KENTUCK CREEK,Reach-1         , 1
Up Type= 0
Dn Type= 3
Dn Slope=0.0005
Boundary for River Rch & Prof#=KENTUCK CREEK,Reach-1         , 2
Up Type= 0
Dn Type= 3
Dn Slope=0.0005
Boundary for River Rch & Prof#=KENTUCK CREEK,Reach-1         , 3
Up Type= 0
Dn Type= 3
Dn Slope=0.0005
Boundary for River Rch & Prof#=KENTUCK CREEK,Reach-1         , 4
Up Type= 0
Dn Type= 3
Dn Slope=0.0005
Boundary for River Rch & Prof#=KENTUCK CREEK,Reach-1         , 5
Up Type= 0
Dn Type= 3
Dn Slope=0.0005
Boundary for River Rch & Prof#=KENTUCK CREEK,Reach-1         , 6
Up Type= 0
Dn Type= 3
Dn Slope=0.0005
Boundary for River Rch & Prof#=KENTUCK CREEK,Reach-1         , 7
Up Type= 0
Dn Type= 3
Dn Slope=0.0005
DSS Import GetInterval= 0
DSS Import GetPeak= 0
DSS Import FillOption= 0

--- KENTUCK CREEK.g01 (geometry) ---

Geom Title=Existing Conditions
Program Version=4.10

River Reach=KENTUCK CREEK   ,Reach-1
Reach XY= 30
      2221737.72     13207196.85      2221937.72     13206846.85
      2223087.72     13206496.85      2224587.72     13205096.86
      2225337.72     13205046.85      2226187.72     13205496.85
      2227337.72     13204746.85      2228637.72     13205046.85
      2229787.72     13204096.85      2231087.72     13204496.85
      2231687.72     13204346.85      2231887.72     13204746.85
      2232387.72     13204646.85      2232687.72     13205096.86
      2233287.72     13204996.85      2234437.72     13205646.85
      2234837.72     13204946.86      2235387.72     13204846.85
      2235637.72     13204246.85      2236487.72     13203746.85
      2237587.72     13203946.86      2238237.72     13203646.86
      2238837.72     13204146.86      2238737.72     13204796.86
      2238987.72     13205046.85      2240087.72     13205596.86
      2241687.72     13205646.85      2242737.72     13204046.85
      2242937.72     13201846.86      2243937.72     13200946.85

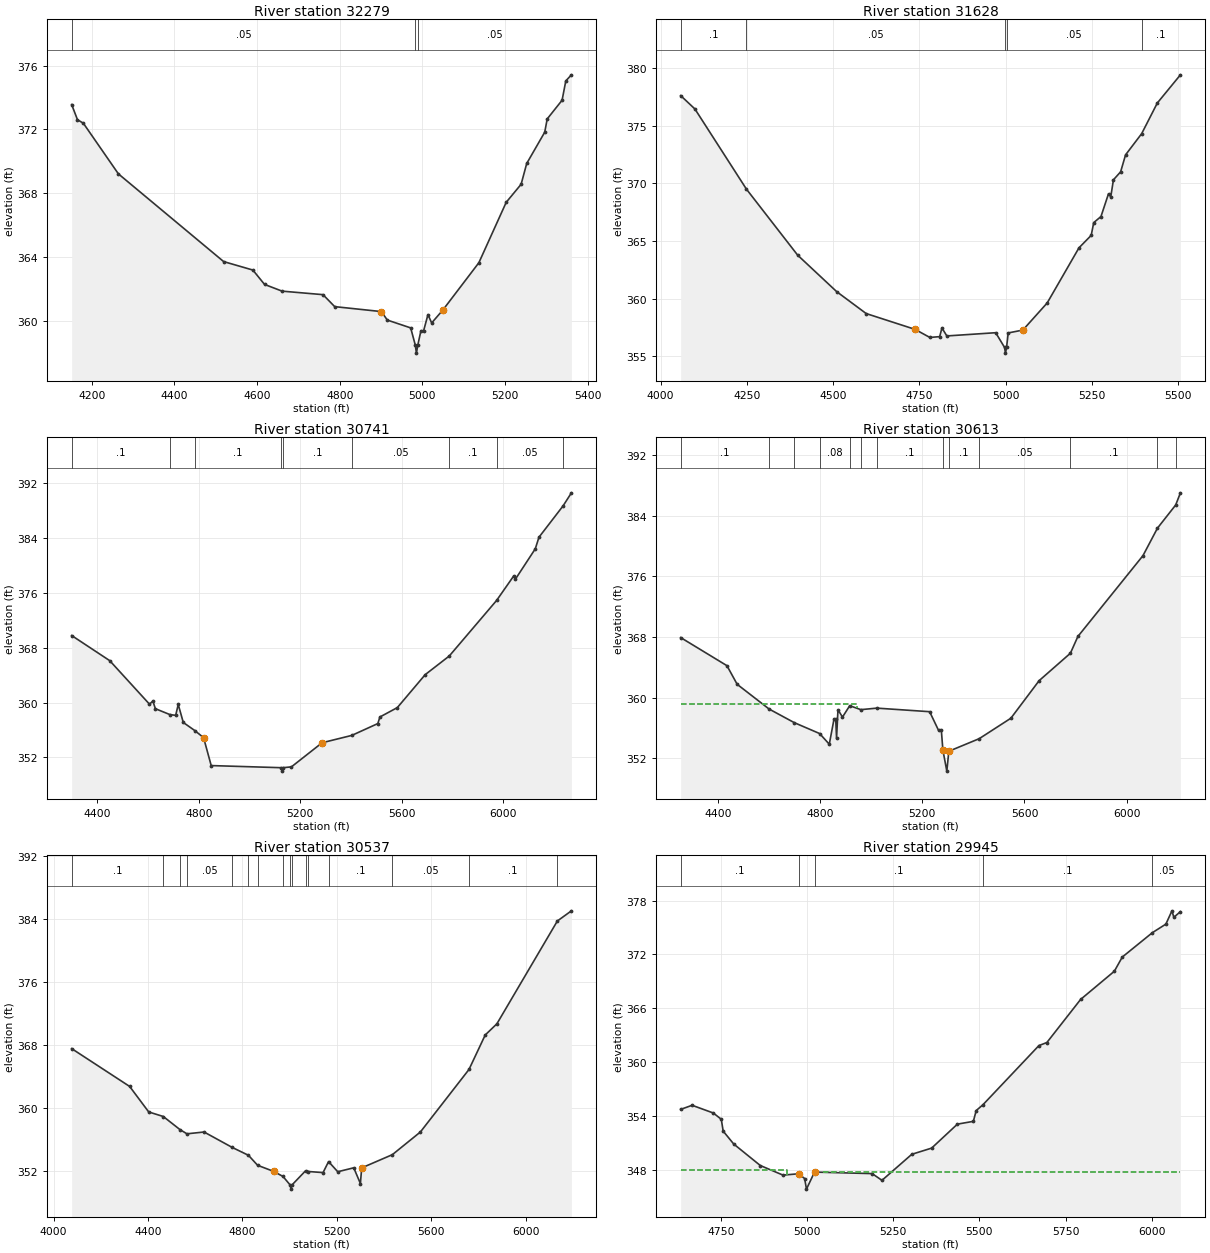
Type RM Length L Ch R = 1 ,32279   ,651,651,651
BEGIN DESCRIPTION:
KENTUCK CREEK 63.0
END DESCRIPTION:
XS GIS Cut Line= 3
       2222437.7     13207546.84      2221837.72     13206946.85
       2221637.7     13206646.82
#Sta/Elev= 30
  4151.5  373.56  4165.6  372.61  4179.8  372.39  4264.6  369.22  4519.2  363.73
  4589.9   363.2  4618.2   362.3  4660.6  361.88  4759.6  361.66  4787.9  360.91
    4901   360.6  4915.1  360.07  4971.7  359.58  4982.9   358.5  4985.6     358
  4988.9   358.5  4996.5   359.4    5003   359.4  5013.5  360.41  5022.5  359.89
  5049.6   360.7  5136.7  363.66  5202.8  367.44  5238.9  368.57  5252.4  369.87
    5296  371.83    5302  372.66    5338  373.83    5347  375.04  5360.6  375.42
#Mann= 3 ,-1 , 0
  4151.5     .05       0  4982.9     .03       0  4988.9     .05       0
Bank Sta=4901,5049.6
XS Rating Curve= 0 ,0
Exp/Cntr=0.3,0.1

Type RM Length L Ch R = 1 ,31628   ,887,887,887
BEGIN DESCRIPTION:
KENTUCK CREEK 62.0
END DESCRIPTION:
XS GIS Cut Line= 2
      2222964.69     13207398.13       2222019.3     13206300.95
#Sta/Elev= 30
  4058.2  377.62  4099.5  376.46  4248.8  369.51  4397.4  363.78  4510.4  360.62
  4595.9  358.72  4737.5  357.35  4780.3  356.65  4808.8  356.72  4815.4  357.47
  4829.6  356.78  4971.2  357.06  4996.7  355.79  4999.5  355.29  5002.7  355.79
  5007.4  357.04  5049.9  357.29  5120.4  359.64  5212.5  364.42  5247.9   365.5
  5255.3  366.61  5276.2  367.13  5298.1  369.11  5304.7  368.86  5312.4  370.32
  5333.2  371.01  5347.5  372.48  5394.2  374.32  5439.6  376.98  5506.5  379.42
#Mann= 5 ,-1 , 0
  4058.2      .1       0  4248.8     .05       0  4996.7     .03       0
  5002.7     .05       0  5394.2      .1       0
Bank Sta=4737.5,5049.9
XS Rating Curve= 0 ,0
Exp/Cntr=0.3,0.1

Type RM Length L Ch R = 1 ,30741   ,128,128,128
BEGIN DESCRIPTION:
KENTUCK CREEK 60.0
END DESCRIPTION:
XS GIS Cut Line= 4
      2223238.12     13207076.93       2223246.8     13206495.33
      2222426.49     13206122.07      2222041.45     13205823.56
#Sta/Elev= 30
  4298.5  369.79  4448.6  366.12  4605.3  359.77  4618.6  360.22  4628.6  359.11
  4685.8  358.25  4708.6  358.14  4718.6  359.73  4738.6   357.1  4784.6   355.9
  4818.6  354.88  4848.6  350.81  5125.2   350.5  5127.9     350  5131.2   350.5
  5164.8  350.62  5285.7  354.14  5402.6  355.21  5505.4  356.94  5513.6   357.9
  5582.3  359.27  5692.2  364.08  5787.1   366.8  5973.5   374.9  6041.1  378.48
  6047.4  377.99  6126.1  382.44  6140.6  384.13  6235.6   388.7  6268.6  390.61
#Mann= 9 ,-1 , 0
  4298.5      .1       0  4685.8     .05       0  4784.6      .1       0
  5125.2     .07       0  5131.2      .1       0  5402.6     .05       0
  5787.1      .1       0  5973.5     .05       0  6235.6      .1       0
Bank Sta=4818.6,5285.7
XS Rating Curve= 0 ,0
Exp/Cntr=0.3,0.1

Type RM Length L Ch R = 1 ,30613   ,76,76,76
BEGIN DESCRIPTION:
KENTUCK CREEK 61.0
END DESCRIPTION:
XS GIS Cut Line= 4
      2223298.88     13207037.83      2223337.94     13206434.57
      2222482.91     13206052.62      2222171.53     13205775.84
#Sta/Elev= 30
  4253.2  367.92  4434.5  364.21  4474.6  361.75  4599.7  358.49  4698.6  356.69
  4797.4  355.26  4835.4  353.85  4854.1   357.2  4860.6   357.2  4863.9  354.62
  4869.4   358.4  4887.1  357.43  4915.5  358.93    4959  358.41  5021.6  358.61
  5228.5  358.14  5263.2  355.69  5274.2  355.74  5280.4  353.07  5295.8   350.3
  5303.6  352.92  5422.6  354.58  5546.7  357.28  5657.5  362.24  5779.8  365.85
  5809.1  368.06  6064.2  378.73  6120.8  382.35  6192.3  385.41  6210.8  387.01
#Mann= 13 ,-1 , 0
  4253.2      .1       0  4599.7     .05       0  4698.6      .1       0
  4797.4     .08       0  4915.5      .1       0    4959     .08       0
  5021.6      .1       0  5280.4     .07       0  5303.6      .1       0
  5422.6     .05       0  5779.8      .1       0  6120.8     .05       0
  6192.3      .1       0
#XS Ineff= 2 , 0
         4943.72  359.21
Permanent Ineff=
       F       F
Bank Sta=5280.4,5303.6
XS Rating Curve= 0 ,0
Exp/Cntr=0.3,0.1

Type RM Length L Ch R = 1 ,30537   ,592,592,592
BEGIN DESCRIPTION:
KENTUCK CREEK 59.0
END DESCRIPTION:
XS GIS Cut Line= 4
      2223385.69     13207076.91      2223511.56     13206443.25
      2222561.03     13205983.18      2222274.55     13205683.68
#Sta/Elev= 30
  4076.8   367.5  4322.4  362.69  4403.1  359.45  4464.9  358.87  4535.3  357.21
  4565.1  356.67  4637.6   356.9  4756.8  354.94  4825.5  353.94  4864.3  352.67
  4932.6  351.89  4971.8  351.25  5002.9  350.14  5005.7  349.64  5008.9  350.14
  5067.4  351.97  5079.3  351.88  5141.5  351.74  5164.8  353.14  5203.7  351.85
  5271.4  352.35  5299.6  350.35  5305.1  352.34  5434.9  354.02  5553.6   356.9
  5759.5  364.85  5828.2  369.23  5877.6  370.65  6133.8  383.72  6193.3  385.01
#Mann= 16 ,-1 , 0
  4076.8      .1       0  4464.9     .05       0  4535.3     .08       0
  4565.1     .05       0  4756.8      .1       0  4825.5     .05       0
  4864.3      .1       0  4971.8     .08       0  5002.9     .07       0
  5008.9     .08       0  5067.4      .1       0  5079.3     .08       0
  5164.8      .1       0  5434.9     .05       0  5759.5      .1       0
  6133.8     .05       0
Bank Sta=4932.6,5305.1
XS Rating Curve= 0 ,0
Exp/Cntr=0.3,0.1

Type RM Length L Ch R = 1 ,29945   ,663,663,663
BEGIN DESCRIPTION:
KENTUCK CREEK 58.0
END DESCRIPTION:
XS GIS Cut Line= 2
      2223907.95     13206011.45      2222588.53      13205412.5
#Sta/Elev= 30
  4633.8  354.74    4667   355.2  4728.5  354.34  4751.6  353.64  4757.1  352.32
  4787.8  350.88  4864.7  348.49  4930.6  347.42  4975.7  347.57  4993.3  347.04
  4998.6  345.86  5021.9  347.76  5188.9  347.59  5217.5  346.84    5304  349.74
  5361.5  350.43  5436.2   353.1  5482.4  353.41  5490.7  354.61  5510.5  355.27
  5672.5  361.85  5695.6  362.19  5793.4  366.99  5891.2  370.13  5914.2  371.71
  6001.6  374.43  6040.6  375.38  6058.2  376.86  6063.7  376.14  6082.8  376.77
#Mann= 5 ,-1 , 0
  4633.8      .1       0  4975.7     .07       0  5021.9      .1       0
  5510.5      .1       0  6001.6     .05       0
#XS Ineff= 2 , 0
       0 4941.61  347.94 5045.06       0  347.77
Permanent Ineff=
       T       T
Bank Sta=4975.7,5021.9
XS Rating Curve= 0 ,0
Exp/Cntr=0.3,0.1

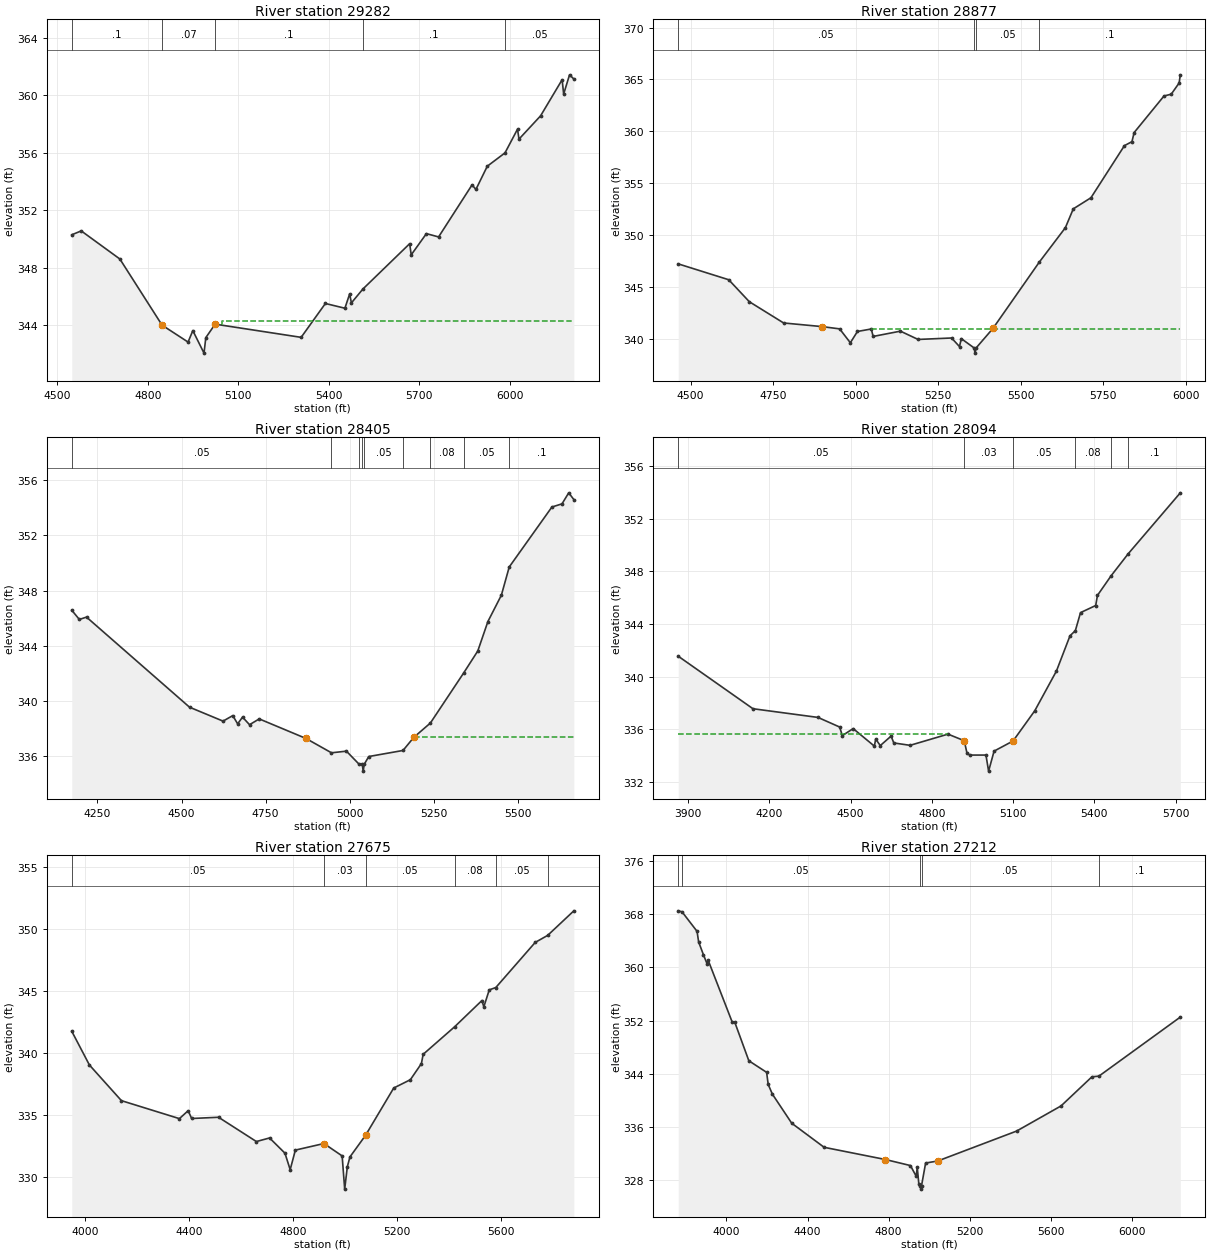
Type RM Length L Ch R = 1 ,29282   ,405,405,405
BEGIN DESCRIPTION:
KENTUCK CREEK 57.0
END DESCRIPTION:
XS GIS Cut Line= 4
      2224164.01     13205816.15      2224150.99     13205529.68
      2223473.91     13205139.05      2222883.59     13205056.58
#Sta/Elev= 30
  4547.5  350.29  4578.9  350.56    4707   348.6  4846.9  343.99  4933.1  342.81
  4948.8  343.61  4985.9  342.04  4991.9  343.12  5022.8  344.06  5307.9  343.14
  5388.3   345.5    5453  345.17  5468.8  346.17  5474.5  345.54  5512.7  346.51
  5667.8  349.67  5672.8  348.89  5723.2  350.37  5763.6  350.14  5874.6  353.77
  5887.3  353.45  5925.1  355.07  5983.8     356  6025.2  357.65  6030.2  356.96
  6101.7  358.58  6173.2   361.1  6178.2   360.1  6197.7  361.44    6212  361.15
#Mann= 5 ,-1 , 0
  4547.5      .1       0  4846.9     .07       0  5022.8      .1       0
  5512.7      .1       0  5983.8     .05       0
#XS Ineff= 2 , 0
       0                 5045.48       0   344.3
Permanent Ineff=
       F       T
Bank Sta=4846.9,5022.8
XS Rating Curve= 0 ,0
Exp/Cntr=0.3,0.1

Type RM Length L Ch R = 1 ,28877   ,472,472,472
BEGIN DESCRIPTION:
Mapping XS 1ab8fbe7
END DESCRIPTION:
XS GIS Cut Line= 3
      2224276.87     13205764.02      2224385.37     13205382.11
      2223960.32     13204341.17
#Sta/Elev= 30
  4462.7  347.21  4615.7  345.68  4678.1  343.56    4782  341.51  4898.2  341.16
  4951.8  340.94  4984.2   339.6  5005.8  340.69  5047.8  340.93  5053.2  340.21
    5136  340.72  5189.5  339.92    5291  340.06    5315  339.23  5320.4     340
  5359.3   339.1    5362   338.6  5365.3   339.1  5416.3  340.98  5556.3  347.36
  5635.8   350.7  5659.8  352.52  5713.3  353.59  5814.8  358.62  5837.5     359
  5844.2  359.88  5934.7  363.41  5956.5  363.58  5980.5  364.66  5984.1  365.45
#Mann= 4 ,-1 , 0
  4462.7     .05       0  5359.3     .03       0  5365.3     .05       0
  5556.3      .1       0
#XS Ineff= 2 , 0
                         5048.66          340.95
Permanent Ineff=
       F       F
Bank Sta=4898.2,5416.3
XS Rating Curve= 0 ,0
Exp/Cntr=0.3,0.1

Type RM Length L Ch R = 1 ,28405   ,311,311,311
BEGIN DESCRIPTION:
Mapping XS e68b314b
END DESCRIPTION:
XS GIS Cut Line= 3
      2224320.28     13205781.38      2224732.59      13205251.9
      2224771.65     13204431.71
#Sta/Elev= 30
  4173.7  346.57  4196.2   345.9  4217.5  346.07  4523.7  339.53  4623.3  338.52
  4652.2  338.92  4666.7  338.32  4681.2  338.81    4702  338.26  4730.9  338.68
  4869.9  337.26  4945.6  336.22    4990  336.34  5026.1  335.43    5037  335.39
  5039.8  334.89    5043  335.39  5056.4  335.95  5158.2  336.39  5190.2  337.34
  5239.5  338.38  5338.3  342.01  5380.4  343.61  5410.5  345.75  5450.5  347.66
  5473.9  349.71  5600.7  354.06  5630.7  354.29  5650.7  355.09  5665.9   354.6
#Mann= 9 ,-1 , 0
  4173.7     .05       0  4945.6     .07       0  5026.1     .05       0
    5037     .07       0    5043     .05       0  5158.2     .07       0
  5239.5     .08       0  5338.3     .05       0  5473.9      .1       0
#XS Ineff= 2 , 0
                         5190.15          337.36
Permanent Ineff=
       F       F
Bank Sta=4869.9,5190.2
XS Rating Curve= 0 ,0
Exp/Cntr=0.3,0.1

Type RM Length L Ch R = 1 ,28094   ,419,419,419
BEGIN DESCRIPTION:
KENTUCK CREEK 56.0
END DESCRIPTION:
XS GIS Cut Line= 4
      2225006.03      13206232.8      2225001.69     13205277.94
      2225023.39     13204744.09      2224807.44     13204450.39
#Sta/Elev= 30
  3863.9  341.55  4139.8  337.56  4379.8   336.9  4459.8  336.17  4469.8  335.52
  4509.8  336.05    4588  334.72    4593  335.26  4609.8  334.76  4649.8  335.48
  4659.8  334.96  4719.9  334.78  4859.9  335.63  4919.9  335.13  4929.9  334.19
    4940  334.04    5000  334.04  5009.8  332.82    5030  334.34  5100.1  335.11
  5180.1   337.4  5260.2  340.42  5310.3   343.1  5330.1  343.49  5349.2  344.86
  5405.2   345.4  5411.7  346.17  5462.5  347.67  5525.2  349.33  5717.6  353.96
#Mann= 6 ,-1 , 0
  3863.9     .05       0  4919.9     .03       0  5100.1     .05       0
  5330.1     .08       0  5462.5     .05       0  5525.2      .1       0
#XS Ineff= 2 , 0
         4859.38  335.66
Permanent Ineff=
       F       F
Bank Sta=4919.9,5100.1
XS Rating Curve= 0 ,0
Exp/Cntr=0.3,0.1

Type RM Length L Ch R = 1 ,27675   ,463,463,463
BEGIN DESCRIPTION:
KENTUCK CREEK 55.0
END DESCRIPTION:
XS GIS Cut Line= 4
      2225539.87     13206132.93      2225414.01      13205607.8
      2225379.29      13204939.4      2224888.87     13204405.58
#Sta/Elev= 30
  3948.1  341.74    4016  339.02  4139.4  336.14  4362.7  334.69  4396.5  335.33
  4409.9   334.7  4513.5   334.8  4659.3  332.84  4710.1  333.13  4769.4   331.9
  4789.5  330.57  4809.5  332.15  4919.6  332.68  4989.7  331.68  4999.5     329
  5009.7  330.81  5019.8   331.6  5079.8  333.34  5188.4  337.16  5252.5  337.83
    5295  339.13  5301.8  339.88  5422.9   342.1  5528.1  344.22  5535.5  343.71
  5556.4  345.08  5581.7  345.27  5733.4  348.91  5781.6  349.48  5882.3  351.46
#Mann= 6 ,-1 , 0
  3948.1     .05       0  4919.6     .03       0  5079.8     .05       0
  5422.9     .08       0  5581.7     .05       0  5781.6      .1       0
Bank Sta=4919.6,5079.8
XS Rating Curve= 0 ,0
Exp/Cntr=0.3,0.1

Type RM Length L Ch R = 1 ,27212   ,483,483,483
BEGIN DESCRIPTION:
KENTUCK CREEK 54.0
END DESCRIPTION:
XS GIS Cut Line= 3
      2226037.71     13206496.82      2225737.72     13205296.85
      2225437.73     13204096.89
#Sta/Elev= 30
  3763.1  368.48  3781.8  368.33  3855.8   365.4  3863.6  363.81  3886.8  361.92
  3904.8  360.55    3910   361.1  4028.5  351.81  4041.4  351.77    4111  345.96
  4198.6  344.22  4206.3  342.41  4226.9  340.95  4322.3  336.58    4482  332.96
  4783.5  331.13  4907.2  330.22  4935.6  328.61  4940.7  329.97  4948.5  327.47
  4955.8  327.18  4958.5  326.68  4961.8  327.18    4982   330.6  5041.2   330.9
  5430.3   335.4  5649.4  339.18  5801.4  343.55  5835.8  343.65  6236.9  352.52
#Mann= 5 ,-1 , 0
  3763.1      .1       0  3781.8     .05       0  4955.8     .03       0
  4961.8     .05       0  5835.8      .1       0
Bank Sta=4783.5,5041.2
XS Rating Curve= 0 ,0
Exp/Cntr=0.3,0.1

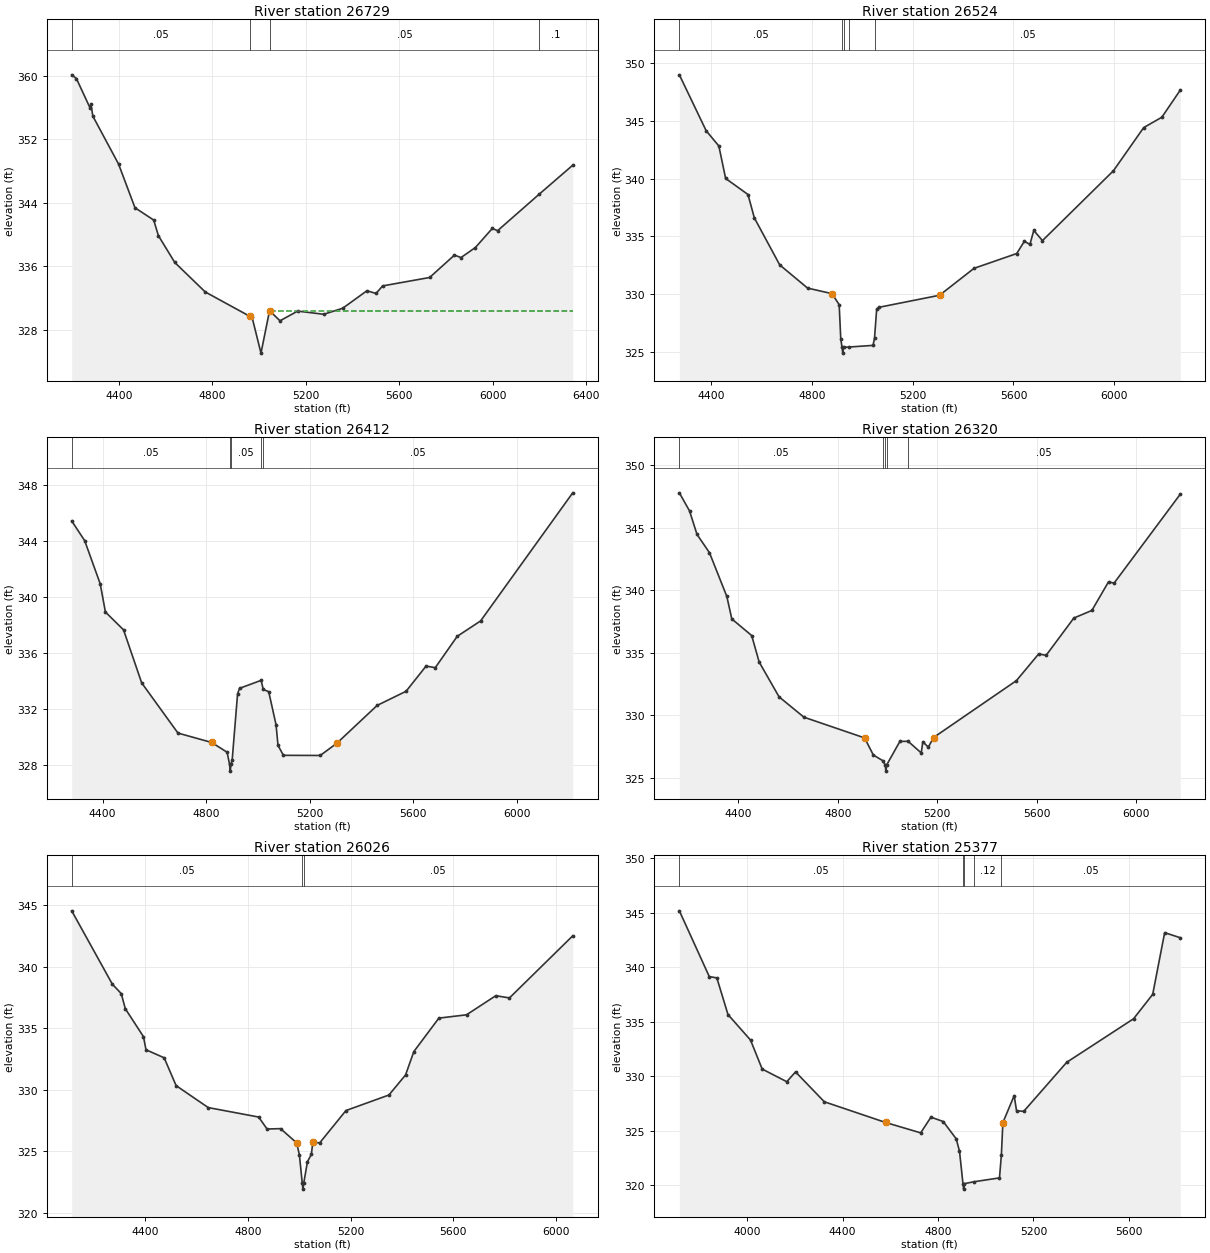
Type RM Length L Ch R = 1 ,26729   ,205,205,205
BEGIN DESCRIPTION:
KENTUCK CREEK 53.0
END DESCRIPTION:
XS GIS Cut Line= 3
      2226187.72     13206296.89      2226137.72     13205496.85
      2225537.74     13204296.89
#Sta/Elev= 30
  4198.4  360.09  4218.5  359.62  4276.1  355.97  4281.1  356.36  4288.6   354.9
  4398.8  348.86    4469  343.36  4549.1  341.81  4569.2  339.85  4639.3  336.47
  4769.6  332.76  4959.9   329.7  4969.9  329.58  5008.1  325.06  5044.7   330.4
  5089.4  329.13  5164.9  330.35  5276.7  329.95  5357.8  330.71  5461.2  332.91
  5500.3  332.57  5528.3  333.52  5729.5  334.58  5835.7   337.4  5863.7  337.09
  5925.2  338.35  5997.8  340.76  6020.2  340.47  6198.4  345.07  6341.6  348.71
#Mann= 4 ,-1 , 0
  4198.4     .05       0  4959.9     .03       0  5044.7     .05       0
  6198.4      .1       0
#XS Ineff= 2 , 0
                         5044.59           330.4
Permanent Ineff=
       F       F
Bank Sta=4959.9,5044.7
XS Rating Curve= 0 ,0
Exp/Cntr=0.3,0.1

Type RM Length L Ch R = 1 ,26524   ,112,112,112
BEGIN DESCRIPTION:
Mapping XS 04993ac1
END DESCRIPTION:
XS GIS Cut Line= 4
      2226444.08     13206082.51      2226374.63     13205483.51
      2226044.77     13205071.19      2225645.54     13204311.78
#Sta/Elev= 30
  4273.5  348.98  4379.9  344.14  4430.2  342.82  4457.2  340.01  4545.9  338.62
  4571.1   336.6  4671.8  332.53  4782.5  330.52  4879.1  330.04  4907.9  329.09
  4914.3  326.11  4919.3  325.39  4922.1  324.89  4925.3  325.39  4948.2  325.42
  5042.4  325.56  5048.3  326.19  5056.8  328.69  5064.3  328.85  5306.5   329.9
  5443.3  332.23  5612.8  333.51  5643.2  334.57  5665.2   334.3  5680.6  335.51
    5715  334.63  5996.9  340.68  6116.8  344.41    6189  345.31  6262.5  347.67
#Mann= 5 ,-1 , 0
  4273.5     .05       0  4919.3     .07       0  4925.3     .05       0
  4948.2     .07       0  5048.3     .05       0
Bank Sta=4879.1,5306.5
XS Rating Curve= 0 ,0
Exp/Cntr=0.3,0.1

Type RM Length L Ch R = 1 ,26412   ,92,92,92
BEGIN DESCRIPTION:
KENTUCK CREEK 52.0
END DESCRIPTION:
XS GIS Cut Line= 4
      2226487.72     13205996.85      2226452.76     13205392.37
      2226096.85     13204993.06      2225749.62     13204276.88
#Sta/Elev= 30
  4280.8  345.46  4330.9  344.05    4391  340.96    4411  338.95  4481.1  337.67
  4551.2  333.88  4691.5  330.29  4821.7  329.62  4881.5  328.92  4890.7  328.07
  4893.4  327.57  4896.7  328.07  4900.9  328.35  4921.8  333.09  4929.3  333.49
  5012.9  334.06  5021.1  333.41  5042.2  333.25  5070.6  330.88  5078.1  329.41
    5099   328.7  5241.2  328.69  5304.7  329.55  5461.4  332.27  5573.1  333.28
  5650.3  335.08    5686  334.97  5770.8  337.21  5861.1  338.31  6217.1  347.47
#Mann= 5 ,-1 , 0
  4280.8     .05       0  4890.7     .03       0  4896.7     .05       0
  5012.9     .07       0  5021.1     .05       0
Bank Sta=4821.7,5304.7
XS Rating Curve= 0 ,0
Exp/Cntr=0.3,0.1

Type RM Length L Ch R = 1 ,26320   ,294,294,294
BEGIN DESCRIPTION:
Mapping XS aab37245
END DESCRIPTION:
XS GIS Cut Line= 4
      2226539.56     13206047.78      2226530.88     13205348.96
      2226201.02       13204954.      2225840.78     13204237.86
#Sta/Elev= 30
  4162.5  347.81  4203.4  346.36  4233.4  344.48  4283.4  343.02  4353.4  339.51
  4373.4  337.71  4453.4  336.38  4483.4  334.26  4563.5  331.47  4663.5  329.84
  4907.5  328.18  4942.7  326.81  4980.4  326.36  4990.4  326.02  4993.1  325.52
  4996.4  326.02  5049.4   327.9  5082.5  327.91  5135.3  326.98  5141.8  327.87
  5163.8  327.44  5184.7  328.21  5518.3  332.77  5607.8  334.91  5637.5  334.79
  5749.1  337.78  5821.7  338.39  5888.6  340.68    5911  340.58  6177.6  347.71
#Mann= 5 ,-1 , 0
  4162.5     .05       0  4980.4     .07       0  4990.4     .07       0
  4996.4     .07       0  5082.5     .05       0
Bank Sta=4907.5,5184.7
XS Rating Curve= 0 ,0
Exp/Cntr=0.3,0.1

Type RM Length L Ch R = 1 ,26026   ,649,649,649
BEGIN DESCRIPTION:
KENTUCK CREEK 51.0
END DESCRIPTION:
XS GIS Cut Line= 3
      2226715.92     13206013.54      2226794.04     13205458.01
      2226377.68     13204130.88
#Sta/Elev= 30
  4112.9  344.52  4271.1  338.57  4305.9   337.8  4321.6  336.58  4392.3  334.31
  4402.4  333.24  4473.1  332.59  4519.7  330.33  4644.8  328.55  4841.4  327.78
  4873.9  326.81  4926.6  326.84  4989.5  325.68    5000   324.7    5011  322.43
  5013.8  321.93    5017  322.43  5031.4  324.16  5046.5  324.75  5052.4  325.75
  5078.9  325.68  5181.4  328.31  5348.8  329.57  5413.6   331.2    5446   333.1
  5543.3  335.81  5651.1  336.08  5765.1  337.63  5818.4  337.45  6064.8  342.49
#Mann= 3 ,-1 , 0
  4112.9     .05       0    5011     .03       0    5017     .05       0
Bank Sta=4989.5,5052.4
XS Rating Curve= 0 ,0
Exp/Cntr=0.3,0.1

Type RM Length L Ch R = 1 ,25377   ,112,112,112
BEGIN DESCRIPTION:
Mapping XS 609cf087
END DESCRIPTION:
XS GIS Cut Line= 4
      2226807.79     13206055.57      2227208.83     13204868.06
       2227125.5     13204758.69      2227094.28     13204051.08
#Sta/Elev= 30
  3716.4  345.18  3841.7  339.15  3873.4  339.03  3920.1  335.67  4014.5  333.33
  4063.4  330.67  4166.5  329.51  4203.2  330.41  4323.8  327.67  4580.7  325.77
  4727.5  324.82  4770.5  326.26  4821.9  325.86  4876.1  324.28  4890.1  323.15
  4904.7  320.16  4907.5  319.66  4910.7  320.16  4948.9  320.33  5057.7  320.69
  5065.6  322.78  5071.9  325.76  5119.2  328.23  5129.2  326.85  5159.2  326.79
  5339.4  331.29  5619.4  335.28  5699.7  337.52  5749.8  343.18  5815.6  342.71
#Mann= 5 ,-1 , 0
  3716.4     .05       0  4904.7     .07       0  4910.7     .05       0
  4948.9     .12       0  5065.6     .05       0
Bank Sta=4580.7,5071.9
XS Rating Curve= 0 ,0
Exp/Cntr=0.3,0.1

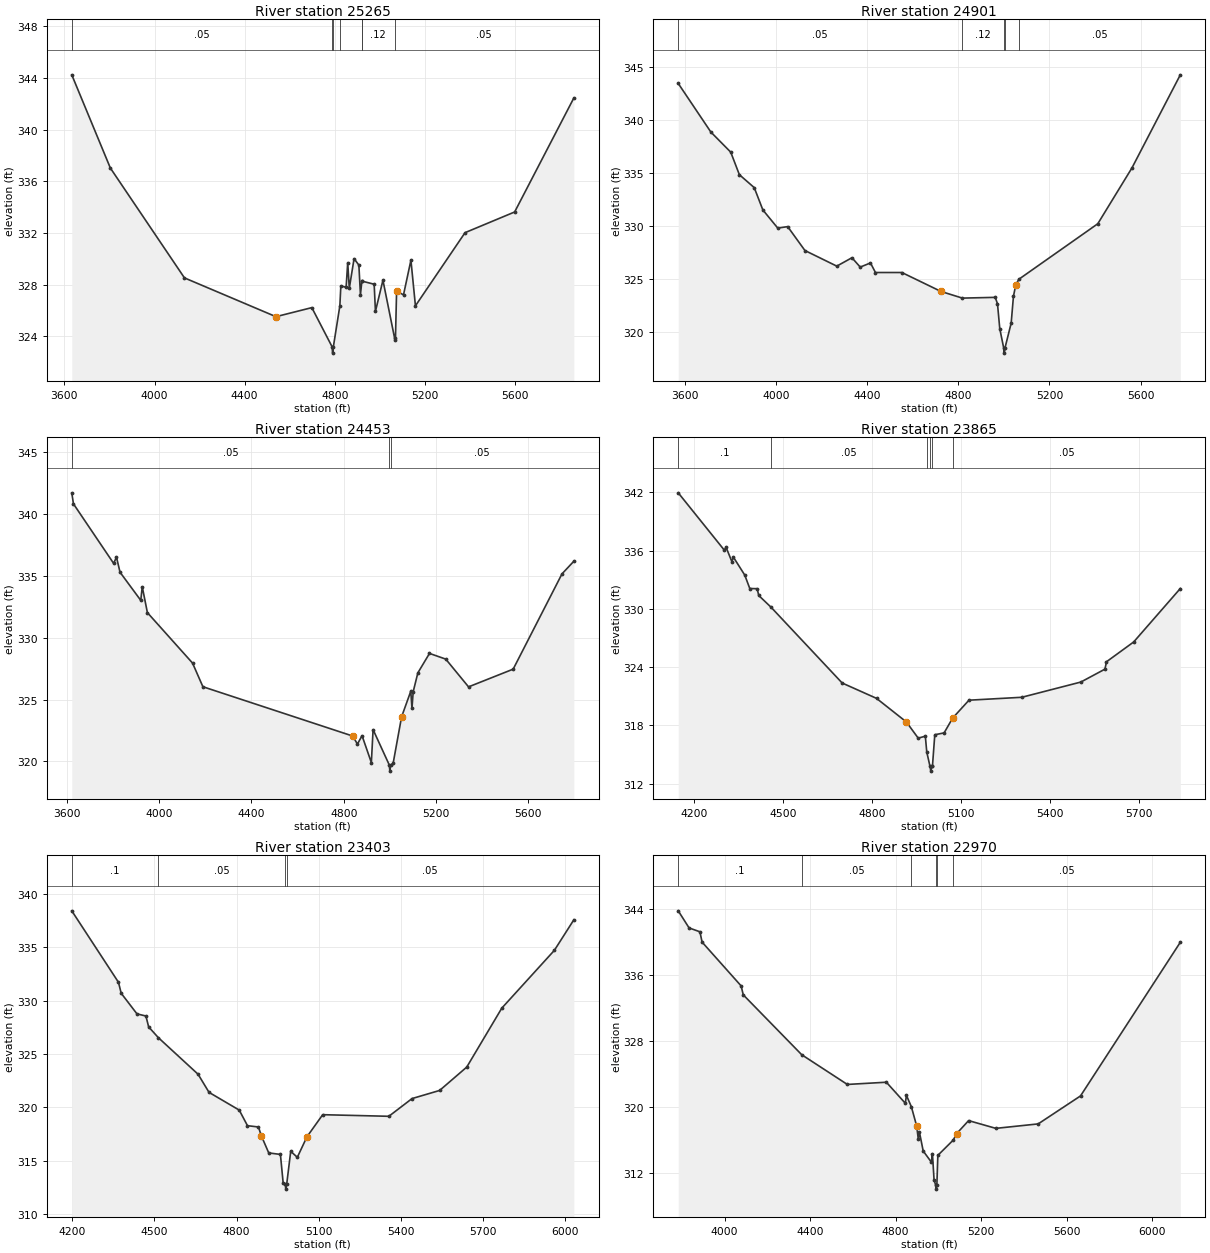
Type RM Length L Ch R = 1 ,25265   ,364,364,364
BEGIN DESCRIPTION:
Mapping XS 9b3fb79a
END DESCRIPTION:
XS GIS Cut Line= 6
      2226854.65     13206060.82      2227255.71     13204930.56
      2227318.21     13204868.06      2227276.54     13204784.73
      2227167.17     13204758.69      2227193.21     13204024.34
#Sta/Elev= 30
  3632.7  344.24  3803.9  337.03  4132.8  328.53  4538.8  325.53    4698  326.23
  4787.7  323.21  4790.4  322.71  4793.7  323.21  4822.4  326.37  4826.8  327.91
  4850.2   327.8  4857.3  329.71  4864.3  327.72  4885.5  330.02  4906.8  329.52
  4913.8  327.23  4920.1  328.28  4920.6  328.28  4974.7  328.04  4980.3  325.94
  5013.6  328.35  5065.6  323.85    5069   323.7  5074.2   327.5  5104.9  327.22
  5137.8   329.9  5157.8  326.37    5378  332.03  5598.1  333.63  5860.8  342.45
#Mann= 7 ,-1 , 0
  3632.7     .05       0  4787.7     .07       0  4793.7     .05       0
  4822.4     .12       0  4920.1     .05       0  4920.6     .12       0
  5065.6     .05       0
Bank Sta=4538.8,5074.2
XS Rating Curve= 0 ,0
Exp/Cntr=0.3,0.1

Type RM Length L Ch R = 1 ,24901   ,448,448,448
BEGIN DESCRIPTION:
KENTUCK CREEK 50.0
END DESCRIPTION:
XS GIS Cut Line= 3
      2226932.78     13206065.99      2227599.46     13204857.65
      2227609.87     13204034.77
#Sta/Elev= 30
  3571.5  343.44  3714.8  338.86  3801.9  336.97  3839.7  334.85    3905  333.63
  3942.8  331.53  4008.2  329.82  4051.7  329.96  4127.4  327.71  4267.2  326.24
  4333.7  327.03    4370  326.15    4415  326.54  4436.8  325.64  4552.7  325.64
    4724  323.86  4818.2  323.23  4962.3   323.3  4972.3   322.7  4982.3  320.36
  4999.4  318.55  5002.1  318.05  5005.4  318.55  5032.4  320.88  5042.4  323.41
  5052.4  324.45  5065.8     325  5412.4  330.23  5562.4  335.49  5774.5  344.25
#Mann= 5 ,-1 , 0
  3571.5     .05       0  4818.2     .12       0  4999.4     .07       0
  5005.4     .12       0  5065.8     .05       0
Bank Sta=4724,5052.4
XS Rating Curve= 0 ,0
Exp/Cntr=0.3,0.1

Type RM Length L Ch R = 1 ,24453   ,588,588,588
BEGIN DESCRIPTION:
KENTUCK CREEK 49.0
END DESCRIPTION:
XS GIS Cut Line= 3
      2227540.55     13206230.61      2227931.19     13205440.65
      2228087.45     13204155.88
#Sta/Elev= 30
  3621.3  341.68  3628.6  340.79  3802.5  335.99  3815.1  336.48  3830.5  335.27
  3920.3     333  3926.7   334.1    3949  332.01  4144.6  327.94  4189.5  326.03
  4838.8  322.05    4859   321.4  4879.1  322.08  4919.4  319.91  4926.9  322.57
    4997  319.72  4999.7  319.22    5003  319.72  5013.7  319.84  5050.4   323.6
  5090.3  325.67  5095.4  324.28  5100.7  325.63  5120.9  327.15  5171.3  328.72
  5241.8  328.26  5340.5  326.02  5533.9  327.45  5745.5  335.14  5796.8  336.16
#Mann= 3 ,-1 , 0
  3621.3     .05       0    4997     .03       0    5003     .05       0
Bank Sta=4838.8,5050.4
XS Rating Curve= 0 ,0
Exp/Cntr=0.3,0.1

Type RM Length L Ch R = 1 ,23865   ,462,462,462
BEGIN DESCRIPTION:
KENTUCK CREEK 48.0
END DESCRIPTION:
XS GIS Cut Line= 3
      2228837.72     13205846.85      2228537.72     13205046.85
      2228287.71     13204246.81
#Sta/Elev= 30
  4145.6  341.96  4301.3  336.04  4306.7  336.36  4326.3  334.88  4331.6  335.33
  4369.9  333.48  4386.8   332.1  4411.7  332.08    4417  331.38  4458.5  330.17
  4698.3  322.36    4814  320.78  4914.6  318.35  4954.6  316.68  4978.6  316.88
  4983.5  315.24  4994.3  313.78  4997.1  313.28  5000.3  313.78  5002.6  313.78
  5010.5  317.03  5041.9  317.22  5070.8  318.75  5125.7  320.59  5303.8  320.89
  5502.9  322.46  5584.1  323.79  5589.3  324.55    5681  326.59  5838.2   332.1
#Mann= 6 ,-1 , 0
  4145.6      .1       0  4458.5     .05       0  4983.5     .12       0
  4994.3     .07       0  5000.3     .12       0  5070.8     .05       0
Bank Sta=4914.6,5070.8
XS Rating Curve= 0 ,0
Exp/Cntr=0.3,0.1

Type RM Length L Ch R = 1 ,23403   ,433,433,433
BEGIN DESCRIPTION:
KENTUCK CREEK 47.0
END DESCRIPTION:
XS GIS Cut Line= 3
      2228887.72     13205696.89      2228937.72     13204896.85
      2228287.71     13204096.84
#Sta/Elev= 30
  4198.4   338.4  4368.8  331.71  4378.8  330.68  4436.4  328.75    4469  328.55
    4479  327.53  4514.5  326.52  4659.3   323.1  4699.4   321.4  4809.6  319.74
  4839.7  318.28  4879.8  318.16  4889.8  317.36  4917.3  315.73  4959.9  315.59
  4969.9  312.92    4977  312.84  4979.7  312.34    4983  312.84  4997.5  315.88
  5021.6  315.32  5056.7  317.24  5114.2  319.31  5355.6  319.16  5440.3  320.82
  5540.9  321.58    5640  323.77  5767.9  329.29  5959.7   334.7  6030.8  337.56
#Mann= 4 ,-1 , 0
  4198.4      .1       0  4514.5     .05       0    4977     .03       0
    4983     .05       0
Bank Sta=4889.8,5056.7
XS Rating Curve= 0 ,0
Exp/Cntr=0.3,0.1

Type RM Length L Ch R = 1 ,22970   ,433,433,433
BEGIN DESCRIPTION:
KENTUCK CREEK 46.0
END DESCRIPTION:
XS GIS Cut Line= 3
      2229087.71      13205896.9      2229287.72     13204696.85
       2228487.7     13203896.83
#Sta/Elev= 30
  3783.4  343.77  3834.1   341.7  3884.8  341.23    3895  339.98  4077.4  334.68
  4087.6  333.59  4360.9  326.34  4574.2  322.74  4756.7  323.01  4845.4  320.46
  4850.5  321.42  4873.8  320.03  4898.6  317.69  4906.2  316.08  4911.3  316.97
    4929  314.68  4967.1  313.33  4972.1  314.36  4979.7  311.22  4986.9  310.56
  4989.6  310.06  4992.9  310.56  4997.5  314.15  5069.8  316.01  5084.9  316.77
  5141.4  318.36  5268.7  317.42  5466.7  317.96  5664.7  321.35  6131.4  339.96
#Mann= 6 ,-1 , 0
  3783.4      .1       0  4360.9     .05       0  4873.8      .1       0
  4986.9     .07       0  4992.9      .1       0  5069.8     .05       0
Bank Sta=4898.6,5084.9
XS Rating Curve= 0 ,0
Exp/Cntr=0.3,0.1

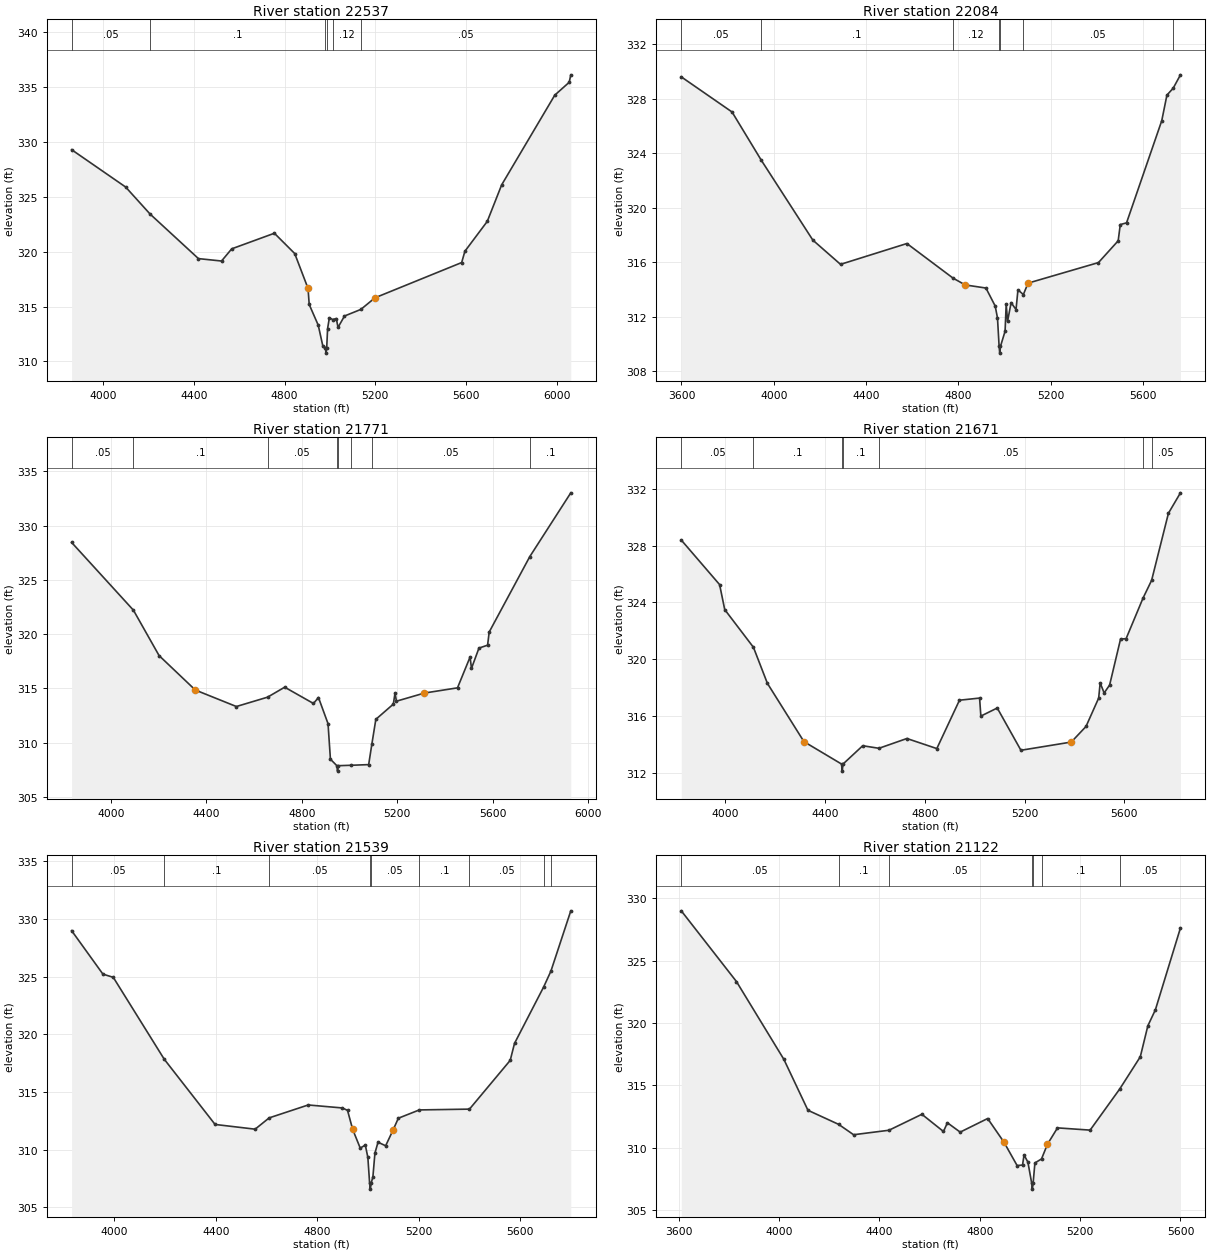
Type RM Length L Ch R = 1 ,22537   ,453,453,453
BEGIN DESCRIPTION:
KENTUCK CREEK 45.0
END DESCRIPTION:
XS GIS Cut Line= 3
      2229837.73     13205496.88      2229537.72     13204396.85
      2228737.73     13203696.86
#Sta/Elev= 30
  3859.8  329.29  4098.2  325.89    4206  323.43  4419.5  319.37  4521.5  319.15
  4566.4  320.26  4754.7  321.68  4844.5  319.83  4903.3  316.65  4908.4  315.19
  4948.2  313.31  4968.9  311.38  4979.7  311.26  4982.5  310.76  4985.7  311.26
  4989.6     313  4997.4  313.98  5012.1  313.82    5028  313.91  5035.6   313.1
  5064.1  314.14  5136.2  314.74  5198.8   315.8  5581.3  319.01  5595.6  320.04
  5694.3  322.76  5757.9  326.09  5992.3  334.26  6055.9  335.43    6063  336.11
#Mann= 6 ,-1 , 0
  3859.8     .05       0    4206      .1       0  4979.7     .07       0
  4985.7      .1       0  5012.1     .12       0  5136.2     .05       0
Bank Sta=4903.3,5198.8
XS Rating Curve= 0 ,0
Exp/Cntr=0.3,0.1

Type RM Length L Ch R = 1 ,22084   ,313,313,313
BEGIN DESCRIPTION:
KENTUCK CREEK 44.0
END DESCRIPTION:
XS GIS Cut Line= 3
      2229887.72     13205496.86      2229837.72     13204096.85
      2230237.71     13203446.87
#Sta/Elev= 30
  3599.1  329.61  3819.2  327.03  3945.5   323.5  4169.5  317.62  4289.5  315.84
  4577.2  317.37  4777.2  314.83  4829.9  314.33  4919.9   314.1    4960  312.78
    4970   311.9    4977  309.82  4979.7  309.32    4983  309.82  5002.9  310.93
  5007.7  312.93  5013.6  311.65    5029  313.03  5050.3  312.52  5058.7  313.97
  5082.1  313.62  5102.4  314.46  5407.7  315.97  5493.2  317.57  5502.3  318.76
  5529.5  318.89  5682.1  326.39  5704.5  328.27  5731.8  328.78  5763.2  329.76
#Mann= 7 ,-1 , 0
  3599.1     .05       0  3945.5      .1       0  4777.2     .12       0
    4977     .07       0    4983     .12       0  5082.1     .05       0
  5731.8      .1       0
Bank Sta=4829.9,5102.4
XS Rating Curve= 0 ,0
Exp/Cntr=0.3,0.1

Type RM Length L Ch R = 1 ,21771   ,100,100,100
BEGIN DESCRIPTION:
Mapping XS 58dd5547
END DESCRIPTION:
XS GIS Cut Line= 4
       2229920.2     13205348.88      2230072.97     13204341.98
      2230086.86     13204036.42      2230475.74     13203376.71
#Sta/Elev= 30
  3836.3  328.45  4095.1  322.21  4202.5  318.03  4354.2  314.86  4526.1  313.34
  4656.6   314.2  4728.4  315.12  4848.9  313.62  4869.9  314.17  4909.9  311.76
  4919.9  308.49  4946.9  307.89  4949.7  307.39  4952.9  307.89  5007.1  307.93
  5080.1  307.99  5093.4  309.88  5110.1  312.16  5183.3  313.56  5190.5  314.58
  5196.3  313.83  5313.4  314.58    5452  315.06  5504.7   317.9  5510.5  316.85
  5541.8  318.72    5578  318.99  5584.7   320.2  5754.8  327.15  5926.4  333.02
#Mann= 8 ,-1 , 0
  3836.3     .05       0  4095.1      .1       0  4656.6     .05       0
  4946.9     .03       0  4952.9     .05       0  5007.1     .12       0
  5093.4     .05       0  5754.8      .1       0
Bank Sta=4354.2,5313.4
XS Rating Curve= 0 ,0
Exp/Cntr=0.3,0.1

Type RM Length L Ch R = 1 ,21671   ,132,132,132
BEGIN DESCRIPTION:
KENTUCK CREEK 43.0
END DESCRIPTION:
XS GIS Cut Line= 4
      2229937.72     13205346.87      2230163.25     13204328.09
      2230197.97     13204050.31      2230517.43     13203453.06
#Sta/Elev= 30
  3824.3   328.4  3977.9  325.26  3998.4   323.5  4113.5  320.84  4169.4   318.3
  4315.9  314.19  4466.6  312.61  4469.3  312.11  4472.6  312.61  4551.5   313.9
  4616.6  313.72  4728.6  314.41  4848.5   313.7  4939.3  317.11  5019.9  317.26
    5025  315.99  5090.7  316.56  5185.6  313.58  5387.5  314.16  5446.5  315.26
  5497.2  317.26  5503.2  318.33  5519.2  317.62  5541.1  318.18    5585  321.43
  5606.9  321.44  5674.8   324.3  5709.4  325.56  5776.8  330.29    5825  331.73
#Mann= 7 ,-1 , 0
  3824.3     .05       0  4113.5      .1       0  4466.6     .03       0
  4472.6      .1       0  4616.6     .05       0  5674.8      .1       0
  5709.4     .05       0
Bank Sta=4315.9,5387.5
XS Rating Curve= 0 ,0
Exp/Cntr=0.3,0.1

Type RM Length L Ch R = 1 ,21539   ,417,417,417
BEGIN DESCRIPTION:
Mapping XS e7fa405d
END DESCRIPTION:
XS GIS Cut Line= 4
      2229954.93     13205362.77      2230281.31     13204383.64
      2230302.14     13204078.09      2230579.15     13203510.21
#Sta/Elev= 30
  3830.8     329  3954.3  325.23  3995.2  324.95  4196.3  317.85    4397  312.19
  4555.1  311.78  4610.5  312.76  4764.6  313.88  4899.8  313.62  4919.8  313.41
  4939.9  311.77  4969.9  310.14    4990   310.4    5000  309.33    5007  307.08
  5009.8  306.58    5013  307.08    5020  307.67  5027.9   309.7  5040.1  310.65
  5070.2  310.34  5100.2  311.74  5120.3  312.73  5203.1  313.45  5401.1  313.52
  5561.9  317.75  5578.8  319.22  5694.2  324.13  5722.5  325.49    5801  330.72
#Mann= 9 ,-1 , 0
  3830.8     .05       0  4196.3      .1       0  4610.5     .05       0
    5007     .03       0    5013     .05       0  5203.1      .1       0
  5401.1     .05       0  5694.2      .1       0  5722.5     .05       0
Bank Sta=4939.9,5100.2
XS Rating Curve= 0 ,0
Exp/Cntr=0.3,0.1

Type RM Length L Ch R = 1 ,21122   ,483,483,483
BEGIN DESCRIPTION:
KENTUCK CREEK 42.0
END DESCRIPTION:
XS GIS Cut Line= 3
      2229987.74     13205396.82      2230687.72     13204196.85
      2230687.72     13203596.85
#Sta/Elev= 30
  3610.8     329  3830.7  323.33  4019.7  317.09  4115.6  313.01  4238.1  311.88
  4297.5  311.05  4438.3  311.41  4569.6  312.69  4655.6  311.31  4671.3  312.01
  4722.2  311.26  4831.7  312.35  4896.2  310.47  4949.1  308.58  4970.6  308.62
  4976.8  309.43  4992.1  308.85    5007  307.19  5009.8  306.69    5013  307.19
    5020  308.79  5046.3  309.11    5070  310.29    5110   311.6    5240  311.42
  5358.4  314.73    5440   317.3    5470  319.78    5500  321.06    5600  327.63
#Mann= 7 ,-1 , 0
  3610.8     .05       0  4238.1      .1       0  4438.3     .05       0
    5007     .03       0    5013     .05       0  5046.3      .1       0
  5358.4     .05       0
Bank Sta=4896.2,5070
XS Rating Curve= 0 ,0
Exp/Cntr=0.3,0.1