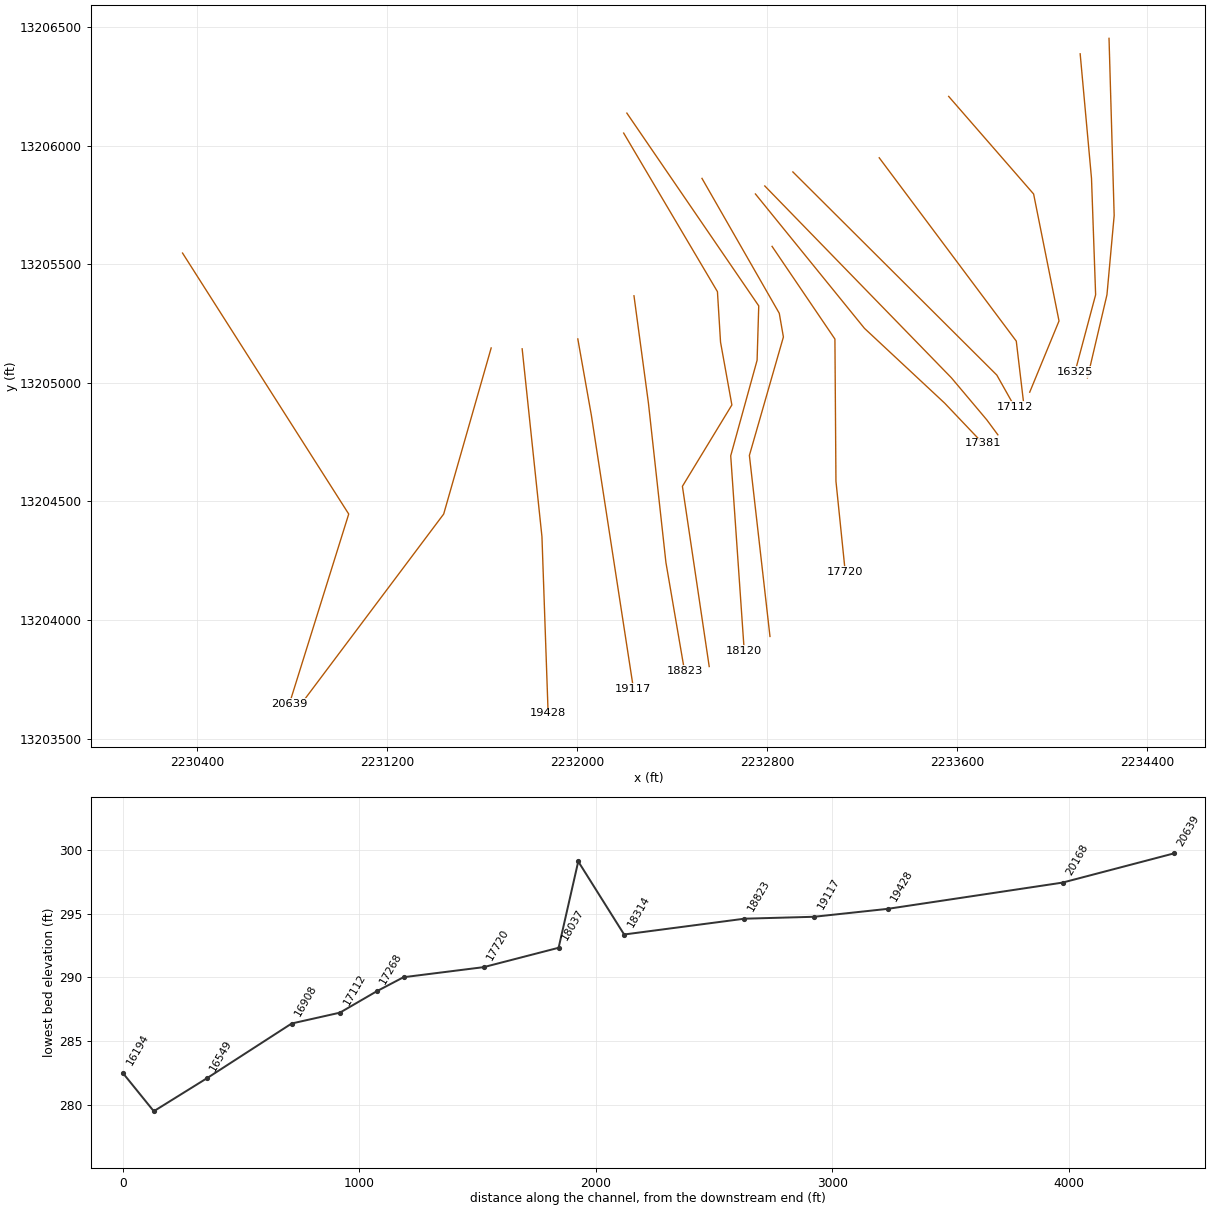
HEC-RAS study KENTUCK CREEK.prj: KENTUCK CREEK Base Level Engineering

--- KENTUCK CREEK.g01 (geometry) --- (continued)

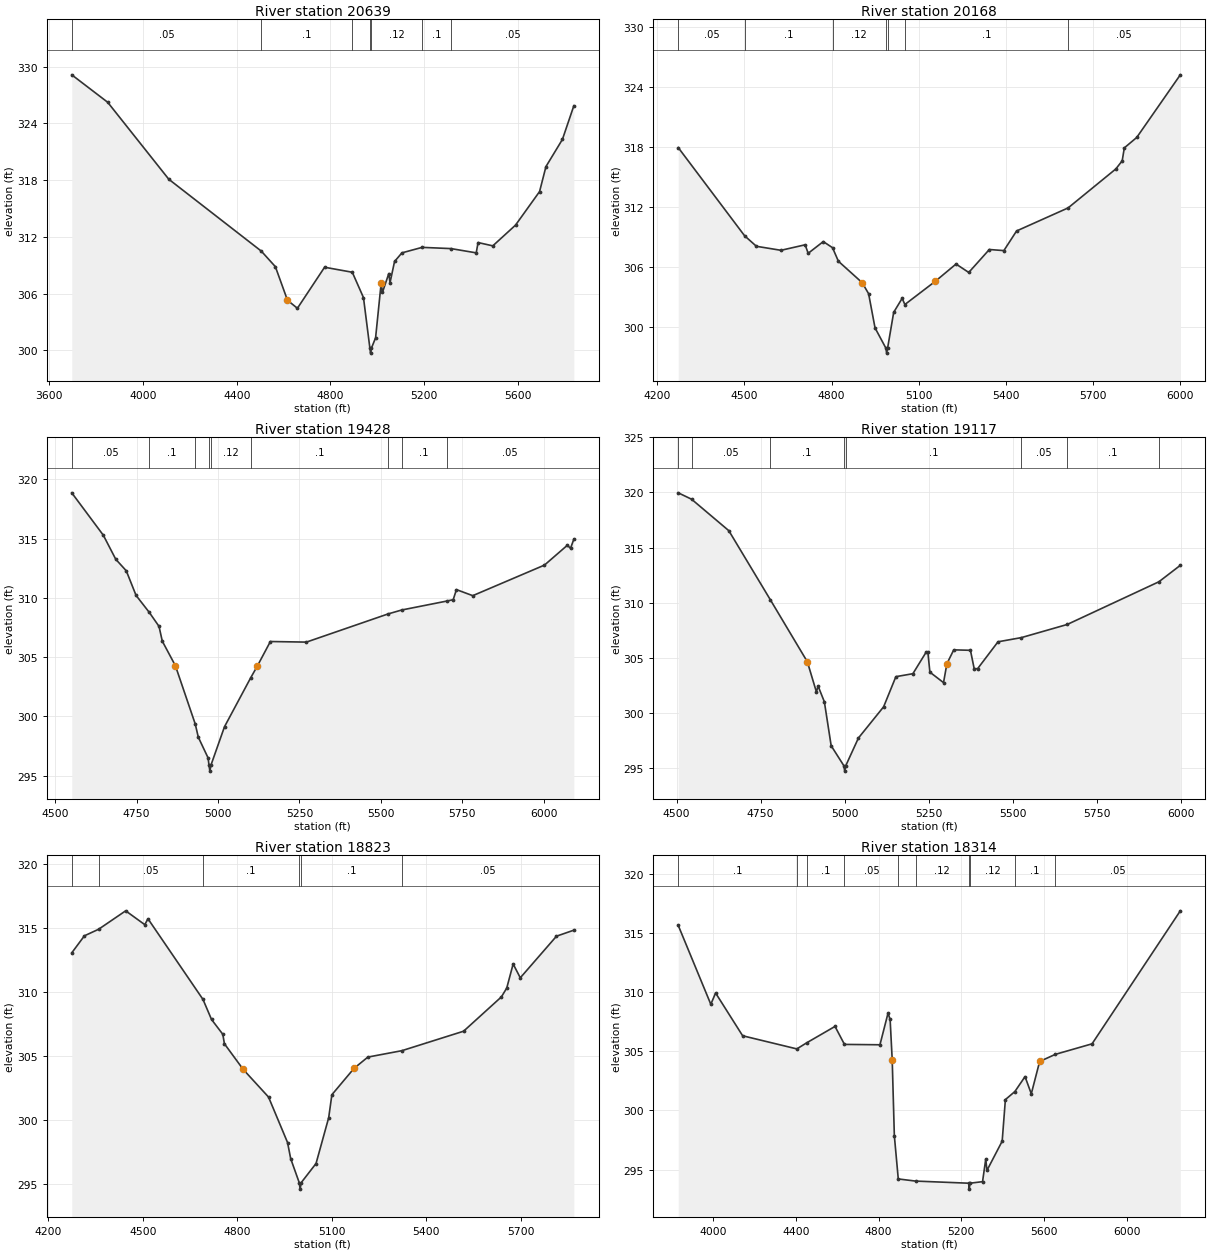
Type RM Length L Ch R = 1 ,20639   ,471,471,471
BEGIN DESCRIPTION:
KENTUCK CREEK 41.0
END DESCRIPTION:
XS GIS Cut Line= 3
      2230337.74     13205546.82      2231037.72     13204446.86
      2230787.71     13203646.81
#Sta/Elev= 30
  3696.2  329.14  3849.4  326.24  4110.2   318.1  4504.5  310.51  4564.8  308.86
  4616.5  305.31  4658.8  304.46  4774.8   308.8    4893  308.27  4940.7  305.59
  4968.2  300.22    4971  299.72  4974.2  300.22  4992.4  301.34  5016.2  307.13
  5021.5  306.13  5048.7  308.13    5054  307.17  5073.3  309.41  5104.8  310.32
  5190.9   310.9  5314.3  310.77  5421.7  310.32  5429.6  311.41  5492.4  311.06
  5589.3  313.25    5692   316.8  5719.2  319.44  5789.4  322.31  5838.2  325.87
#Mann= 7 ,-1 , 0
  3696.2     .05       0  4504.5      .1       0    4893     .12       0
  4968.2     .07       0  4974.2     .12       0  5190.9      .1       0
  5314.3     .05       0
Bank Sta=4616.5,5016.2
XS Rating Curve= 0 ,0
Exp/Cntr=0.3,0.1

Type RM Length L Ch R = 1 ,20168   ,740,740,740
BEGIN DESCRIPTION:
KENTUCK CREEK 40.0
END DESCRIPTION:
XS GIS Cut Line= 3
      2231637.72     13205146.84      2231437.72     13204446.86
      2230837.72     13203646.85
#Sta/Elev= 30
    4272  317.94  4500.4  309.14  4541.1  308.09  4625.6  307.69  4708.8  308.24
  4719.2  307.39  4771.2  308.56    4803  307.95  4823.2   306.6  4905.1  304.46
  4927.2  303.36  4949.3  299.95  4986.6  297.93  4989.3  297.43  4992.6  297.93
  5013.5   301.5  5042.7   302.9    5052  302.28  5157.3  304.61  5228.1  306.32
  5271.9  305.48  5342.7  307.77  5392.7  307.66  5436.5  309.62  5613.8  311.92
  5778.1  315.81    5800  316.62  5807.3  317.91    5850  318.95    6000   325.2
#Mann= 7 ,-1 , 0
    4272     .05       0  4500.4      .1       0    4803     .12       0
  4986.6     .07       0  4992.6     .12       0    5052      .1       0
  5613.8     .05       0
Bank Sta=4905.1,5157.3
XS Rating Curve= 0 ,0
Exp/Cntr=0.3,0.1

Type RM Length L Ch R = 1 ,19428   ,311,311,311
BEGIN DESCRIPTION:
KENTUCK CREEK 39.0
END DESCRIPTION:
XS GIS Cut Line= 3
      2231768.25     13205143.19      2231851.59      13204351.5
      2231877.63     13203606.72
#Sta/Elev= 30
  4551.2  318.86  4648.1  315.28  4686.3  313.25  4718.5  312.28  4748.6   310.2
  4789.1  308.77    4819  307.59  4829.1  306.34  4869.3  304.27  4930.2  299.35
  4939.7  298.23  4969.8  296.48  4972.4  295.87  4975.2  295.37  4978.4  295.87
  5020.1  299.12  5100.7  303.26  5120.7  304.23  5160.9  306.31  5271.5  306.26
  5522.4  308.64  5564.1  308.97  5701.7  309.72  5722.1  309.84  5732.1  310.69
  5782.2  310.18  6002.3  312.76  6072.4  314.43  6082.4  314.18  6092.5  314.95
#Mann= 9 ,-1 , 0
  4551.2     .05       0  4789.1      .1       0  4930.2     .12       0
  4972.4     .07       0  4978.4     .12       0  5100.7      .1       0
  5522.4     .12       0  5564.1      .1       0  5701.7     .05       0
Bank Sta=4869.3,5120.7
XS Rating Curve= 0 ,0
Exp/Cntr=0.3,0.1

Type RM Length L Ch R = 1 ,19117   ,294,294,294
BEGIN DESCRIPTION:
KENTUCK CREEK 38.0
END DESCRIPTION:
XS GIS Cut Line= 3
      2232002.63     13205184.87      2232059.92     13204861.92
      2232236.93     13203711.35
#Sta/Elev= 30
    4505  319.97  4544.7  319.39  4655.3  316.54  4778.7  310.28  4888.7  304.66
  4915.6  301.93  4920.6  302.46  4939.3  301.03  4959.5  297.05    4997  295.25
  4999.8  294.75    5003  295.25  5040.5  297.75  5115.4  300.58  5151.8  303.31
  5202.4  303.58  5241.9  305.54  5246.9  305.52  5252.9  303.72  5293.4  302.77
  5303.5  304.49  5323.8  305.74  5373.4   305.7  5384.5  304.04  5394.6  304.03
  5455.3  306.47  5524.8  306.85    5661  308.04  5933.5  311.91  5997.1   313.4
#Mann= 8 ,-1 , 0
    4505      .1       0  4544.7     .05       0  4778.7      .1       0
    4997     .07       0    5003      .1       0  5524.8     .05       0
    5661      .1       0  5933.5     .05       0
Bank Sta=4888.7,5303.5
XS Rating Curve= 0 ,0
Exp/Cntr=0.3,0.1

Type RM Length L Ch R = 1 ,18823   ,509,509,509
BEGIN DESCRIPTION:
KENTUCK CREEK 37.0
END DESCRIPTION:
XS GIS Cut Line= 4
      2232239.23     13205366.67      2232299.99     13204915.29
      2232373.78     13204242.55       2232451.9     13203786.83
#Sta/Elev= 30
  4274.5  313.05  4314.7  314.38  4359.7  314.89  4445.7  316.33  4506.4  315.25
  4516.5  315.71  4691.3  309.41  4718.3  307.85  4754.2  306.69  4759.3  305.95
  4818.9  303.95  4899.4  301.79  4959.8  298.24  4969.8  296.98    4997   295.1
  4999.8   294.6    5003   295.1  5050.3   296.6  5090.5  300.18  5100.6  301.97
    5171  304.03  5214.9  304.91  5322.9  305.41  5518.9  306.93    5639  309.61
    5656   310.3  5676.3  312.18    5699   311.1    5814  314.35  5869.1  314.82
#Mann= 6 ,-1 , 0
  4274.5      .1       0  4359.7     .05       0  4691.3      .1       0
    4997     .07       0    5003      .1       0  5322.9     .05       0
Bank Sta=4818.9,5171
XS Rating Curve= 0 ,0
Exp/Cntr=0.3,0.1

Type RM Length L Ch R = 1 ,18314   ,194,194,194
BEGIN DESCRIPTION:
Mapping XS 08e469b8
END DESCRIPTION:
XS GIS Cut Line= 6
      2232195.81     13206052.47      2232590.79     13205384.04
      2232603.81     13205171.37      2232651.56     13204906.61
      2232443.22     13204563.73      2232556.07     13203804.18
#Sta/Elev= 30
  3831.1  315.63  3988.6  308.97  4011.8  309.92  4142.5  306.31  4404.6   305.2
  4451.7  305.71  4589.2   307.1  4634.8  305.58  4806.4  305.55  4845.5  308.22
  4855.6  307.69  4865.7  304.27    4876  297.87    4895  294.22  4978.4  294.04
  5235.5  293.86  5238.3  293.36  5241.5  293.86  5302.5  293.99    5318   295.9
  5323.8  294.94  5397.4  297.41  5412.9  300.92  5458.8   301.6  5507.9  302.86
  5538.2  301.41  5578.6  304.14  5654.4  304.74    5832  305.63  6258.7  316.86
#Mann= 10 ,-1 , 0
  3831.1      .1       0  4404.6     .16       0  4451.7      .1       0
  4634.8     .05       0    4895      .1       0  4978.4     .12       0
  5235.5     .07       0  5241.5     .12       0  5458.8      .1       0
  5654.4     .05       0
Bank Sta=4865.7,5578.6
XS Rating Curve= 0 ,0
Exp/Cntr=0.3,0.1

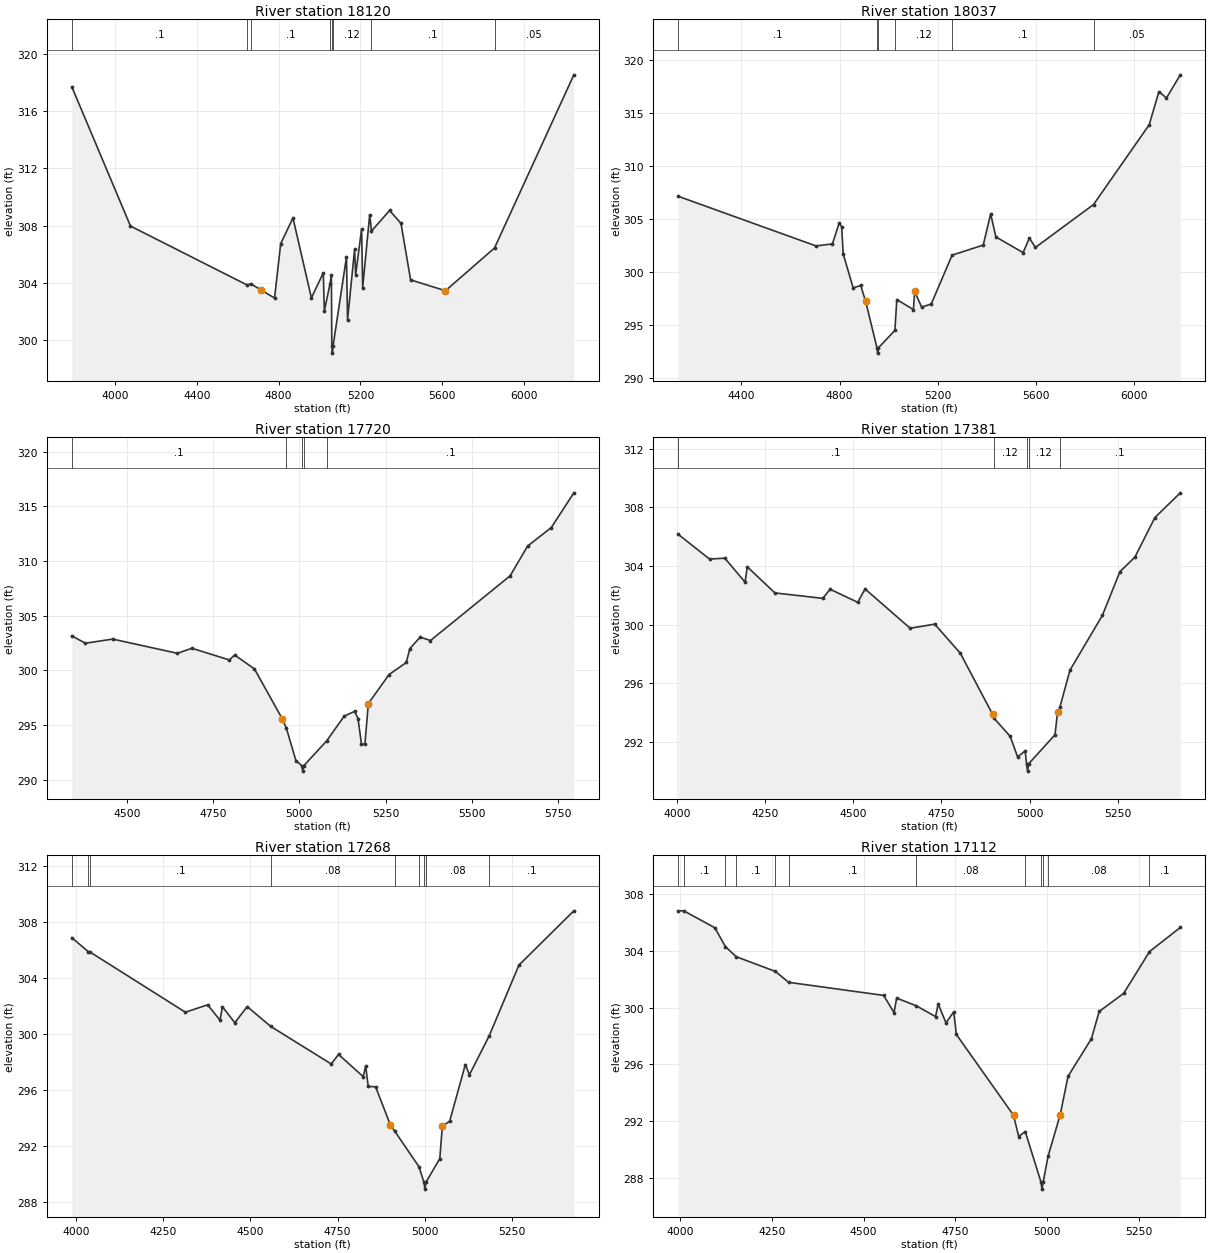
Type RM Length L Ch R = 1 ,18120   ,83,83,83
BEGIN DESCRIPTION:
KENTUCK CREEK 36.0
END DESCRIPTION:
XS GIS Cut Line= 5
       2232209.2     13206136.68      2232764.73     13205324.21
      2232757.79     13205095.04      2232646.68     13204692.27
      2232703.55     13203870.57
#Sta/Elev= 30
  3788.3  317.71  4075.4  307.97  4647.1  303.84  4663.2  303.94  4715.3  303.49
  4779.9  302.94  4809.9  306.74  4869.9  308.54    4960  302.95  5018.2   304.7
  5023.4  302.04  5051.1  303.94  5057.7  304.52  5059.9  299.59  5062.7  299.09
  5065.9  299.59  5131.6  305.81  5136.8  301.41  5171.2  306.35  5176.4  304.58
  5205.6  307.77  5210.7  303.67  5245.1  308.77  5253.8  307.62  5342.3  309.06
  5398.1  308.16  5445.1  304.21  5615.5  303.45  5855.5  306.44  6243.3  318.54
#Mann= 8 ,-1 , 0
  3788.3      .1       0  4647.1     .05       0  4663.2      .1       0
  5051.1     .12       0  5059.9     .07       0  5065.9     .12       0
  5253.8      .1       0  5855.5     .05       0
Bank Sta=4715.3,5615.5
XS Rating Curve= 0 ,0
Exp/Cntr=0.3,0.1

Type RM Length L Ch R = 1 ,18037   ,317,317,317
BEGIN DESCRIPTION:
KENTUCK CREEK 35.0
END DESCRIPTION:
XS GIS Cut Line= 5
      2232525.68     13205861.48      2232851.21      13205292.9
      2232868.57     13205193.07      2232725.34     13204693.94
      2232812.05     13203930.93
#Sta/Elev= 30
  4143.4  307.14  4704.3  302.45    4771  302.64  4798.6  304.62  4808.6  304.27
  4814.9  301.69  4855.5  298.48  4885.9  298.72  4906.4   297.2  4952.3  292.82
    4955  292.32  4958.3  292.82  5025.3  294.47  5033.1  297.38  5100.6  296.44
  5105.8  298.15  5134.3  296.66  5173.3  296.97  5258.2  301.58  5384.9  302.53
  5415.1  305.48  5436.4   303.3  5547.1  301.82  5572.7  303.19  5597.4  302.31
  5833.8  306.36  6060.4   313.9    6100  317.03  6130.8  316.43  6187.1  318.62
#Mann= 6 ,-1 , 0
  4143.4      .1       0  4952.3     .07       0  4958.3      .1       0
  5025.3     .12       0  5258.2      .1       0  5833.8     .05       0
Bank Sta=4906.4,5105.8
XS Rating Curve= 0 ,0
Exp/Cntr=0.3,0.1

Type RM Length L Ch R = 1 ,17720   ,339,339,339
BEGIN DESCRIPTION:
Mapping XS e5ce8780
END DESCRIPTION:
XS GIS Cut Line= 4
      2232820.85     13205574.99      2233085.58     13205184.39
      2233089.92     13204585.43      2233128.99     13204203.46
#Sta/Elev= 30
  4340.6  303.17  4380.1  302.49  4459.1  302.87  4646.7  301.57  4688.7  302.03
  4797.4  300.96  4812.5  301.42    4870  300.14    4950  295.61  4962.4  294.73
    4990  291.77    5007   291.3  5009.8   290.8    5013   291.3  5079.3  293.57
    5130  295.83    5160  296.26    5170  295.61    5180  293.28    5190  293.27
    5200  296.98    5260  299.63    5310  300.73    5320  301.99    5350  303.05
    5380  302.74    5611  308.66  5661.3  311.37  5730.2  313.07  5795.4  316.24
#Mann= 5 ,-1 , 0
  4340.6      .1       0  4962.4     .12       0    5007     .07       0
    5013     .12       0  5079.3      .1       0
Bank Sta=4950,5200
XS Rating Curve= 0 ,0
Exp/Cntr=0.3,0.1

Type RM Length L Ch R = 1 ,17381   ,113,113,113
BEGIN DESCRIPTION:
Mapping XS 0da5c2db
END DESCRIPTION:
XS GIS Cut Line= 4
      2232750.77     13205795.79      2233209.89     13205229.63
      2233547.87     13204914.18      2233708.39     13204745.22
#Sta/Elev= 30
  4003.2  306.17    4092  304.48  4135.2  304.54  4192.7  302.91  4199.1  303.95
  4277.4  302.17  4413.2   301.8    4434  302.42  4512.4  301.53  4533.2  302.44
  4661.1  299.76  4730.7  300.04  4803.3  298.06  4895.1  293.88  4898.3  293.64
  4944.9  292.38  4965.9  290.98  4987.4  291.39  4991.3  290.51    4994  290.01
  4997.3  290.51    5072  292.49  5079.3  294.04  5085.7  294.36  5114.5   296.9
  5206.5  300.64  5256.2  303.62  5298.7  304.61  5355.3  307.31  5427.5     309
#Mann= 5 ,-1 , 0
  4003.2      .1       0  4898.3     .12       0  4991.3     .07       0
  4997.3     .12       0  5085.7      .1       0
Bank Sta=4895.1,5079.3
XS Rating Curve= 0 ,0
Exp/Cntr=0.3,0.1

Type RM Length L Ch R = 1 ,17268   ,156,156,156
BEGIN DESCRIPTION:
KENTUCK CREEK 34.0
END DESCRIPTION:
XS GIS Cut Line= 4
      2232790.23     13205829.56      2233576.04     13205021.21
      2233725.32     13204843.77       2233771.9     13204780.75
#Sta/Elev= 30
  3988.6  306.89  4036.4  305.88  4039.9  305.88    4314  301.56  4377.7  302.09
    4413  300.99  4420.1  301.95  4455.4  300.81  4490.9  301.96  4558.6  300.54
  4731.4  297.86  4752.5  298.54  4823.2  296.95  4830.2  297.72  4837.4  296.25
  4858.5  296.23  4900.9   293.5  4913.7  293.04  4982.8  290.51  4996.9  289.41
  4999.7  288.91  5002.9  289.41  5042.4  291.09  5049.6  293.41  5070.7  293.77
  5115.5  297.82  5127.3  297.09  5183.6  299.86    5269  304.93  5426.2  308.81
#Mann= 9 ,-1 , 0
  3988.6      .1       0  4036.4     .08       0  4039.9      .1       0
  4558.6     .08       0  4913.7     .12       0  4982.8     .08       0
  4996.9     .07       0  5002.9     .08       0  5183.6      .1       0
Bank Sta=4900.9,5049.6
XS Rating Curve= 0 ,0
Exp/Cntr=0.3,0.1

Type RM Length L Ch R = 1 ,17112   ,204,204,204
BEGIN DESCRIPTION:
KENTUCK CREEK 33.0
END DESCRIPTION:
XS GIS Cut Line= 3
      2232908.55     13205888.68      2233767.56     13205032.48
      2233843.19     13204898.03
#Sta/Elev= 30
  3995.2  306.81  4010.3  306.81  4094.9  305.62  4123.7  304.29  4153.1  303.58
  4259.6  302.55  4295.9  301.78  4554.5  300.86  4582.8  299.65  4589.9  300.67
  4643.3  300.13  4695.9  299.37    4703  300.26  4724.2  298.93  4745.4   299.7
  4752.5  298.11  4908.1  292.43  4922.2  290.93    4940  291.28  4982.9  287.73
  4985.6  287.23  4988.9  287.73  5002.4  289.56  5035.4  292.48  5056.6  295.17
  5120.2  297.81  5141.4  299.73    5208     301  5278.4  303.94  5362.3  305.64
#Mann= 12 ,-1 , 0
  3995.2     .08       0  4010.3      .1       0  4123.7     .08       0
  4153.1      .1       0  4259.6     .08       0  4295.9      .1       0
  4643.3     .08       0    4940     .12       0  4982.9     .07       0
  4988.9     .12       0  5002.4     .08       0  5278.4      .1       0
Bank Sta=4908.1,5035.4
XS Rating Curve= 0 ,0
Exp/Cntr=0.3,0.1

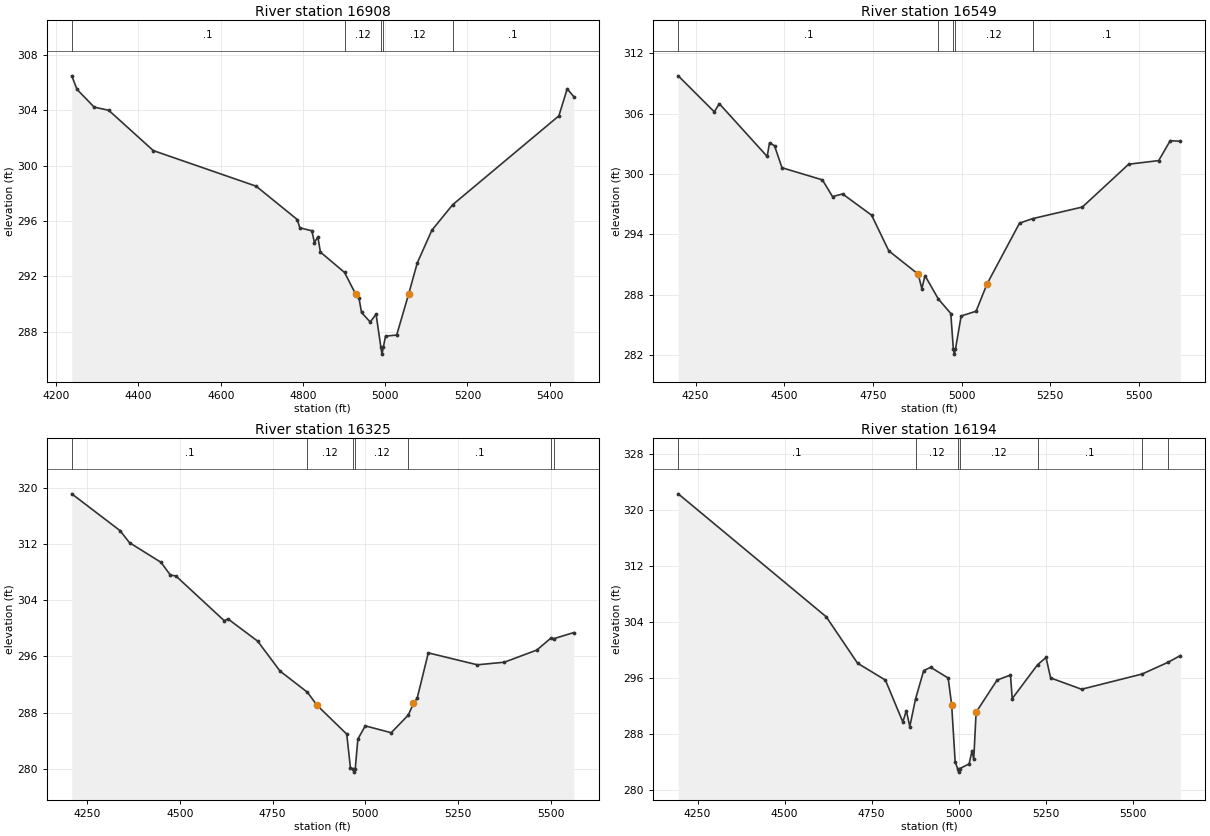
Type RM Length L Ch R = 1 ,16908   ,359,359,359
BEGIN DESCRIPTION:
Mapping XS 3d4d51d7
END DESCRIPTION:
XS GIS Cut Line= 3
      2233272.21     13205948.29      2233849.47     13205175.71
      2233879.73     13204920.72
#Sta/Elev= 30
  4237.7  306.48  4250.5   305.5  4292.2  304.22  4327.6  303.99    4436  301.08
  4686.1  298.51  4786.2   296.1  4792.4   295.5  4821.6  295.29  4827.9  294.44
  4836.2  294.85  4842.5  293.75  4901.2  292.28  4927.9  290.73  4936.3  290.42
  4942.5  289.39  4963.5   288.7  4977.9  289.26  4989.5  286.88  4992.3  286.38
  4995.5  286.88  5000.9  287.68    5028  287.76  5057.2  290.73    5078  292.96
  5113.4  295.32  5164.1  297.17  5422.5  303.59  5442.7  305.54  5458.9  304.97
#Mann= 5 ,-1 , 0
  4237.7      .1       0  4901.2     .12       0  4989.5     .07       0
  4995.5     .12       0  5164.1      .1       0
Bank Sta=4927.9,5057.2
XS Rating Curve= 0 ,0
Exp/Cntr=0.3,0.1

Type RM Length L Ch R = 1 ,16549   ,224,224,224
BEGIN DESCRIPTION:
KENTUCK CREEK 32.0
END DESCRIPTION:
XS GIS Cut Line= 4
      2233564.74     13206207.01      2233922.47     13205795.76
       2234029.5     13205260.62      2233906.09     13204960.51
#Sta/Elev= 30
  4201.1  309.76  4302.7  306.18  4316.9  306.99  4451.8  301.74  4458.4  303.09
  4472.6   302.8  4493.5  300.62  4607.5  299.41    4636  297.75  4664.5  298.01
  4746.2   295.9  4794.7  292.35  4877.6  290.03  4887.8  288.59  4896.7  289.89
  4934.2  287.57  4969.4  286.12  4976.6  282.58  4979.4  282.08  4982.6  282.58
  4998.6  285.87  5040.8  286.35  5071.4  289.05  5163.2  295.11  5200.4  295.56
  5340.3  296.71  5470.9  300.97  5555.5  301.33  5587.9  303.31  5616.4  303.25
#Mann= 5 ,-1 , 0
  4201.1      .1       0  4934.2     .12       0  4976.6     .07       0
  4982.6     .12       0  5200.4      .1       0
Bank Sta=4877.6,5071.4
XS Rating Curve= 0 ,0
Exp/Cntr=0.3,0.1

Type RM Length L Ch R = 1 ,16325   ,131,131,131
BEGIN DESCRIPTION:
Mapping XS b49b6620
END DESCRIPTION:
XS GIS Cut Line= 4
      2234118.57     13206386.62      2234166.31     13205861.47
      2234183.67     13205371.02      2234096.86     13205045.47
#Sta/Elev= 30
  4207.9   319.2  4338.2  313.95  4363.7  312.23  4448.7  309.43  4474.2   307.6
  4488.8  307.49  4619.4   301.1  4629.4  301.36  4709.7  298.18  4769.9  293.92
  4843.9  290.89  4869.9  289.03    4950  284.92    4960  280.09    4967     280
  4969.7   279.5    4973     280    4980  284.21    5000   286.1    5070  285.12
  5116.3  287.65  5130.1  289.32  5140.1  290.04  5170.1  296.51  5302.4  294.81
  5375.2  295.18  5462.8  296.91    5501  298.62  5508.9  298.54  5562.9  299.41
#Mann= 7 ,-1 , 0
  4207.9      .1       0  4843.9     .12       0    4967     .07       0
    4973     .12       0  5116.3      .1       0    5501     .05       0
  5508.9      .1       0
Bank Sta=4869.9,5130.1
XS Rating Curve= 0 ,0
Exp/Cntr=0.3,0.1

Type RM Length L Ch R = 1 ,16194   ,69,69,69
BEGIN DESCRIPTION:
Mapping XS f90d985a
END DESCRIPTION:
XS GIS Cut Line= 4
       2234240.1      13206451.8       2234261.8     13205705.22
      2234231.42     13205371.02      2234149.24      13205020.7
#Sta/Elev= 30
  4194.5  322.36  4619.6  304.75  4709.7   298.1  4789.7  295.68  4839.7  289.68
  4849.7  291.31  4859.7  289.03  4876.4  293.02  4899.7  297.05  4919.8  297.51
  4969.9  295.98  4979.9  292.18    4990     284    4997     283  4999.8   282.5
    5003     283  5030.1  283.68  5038.4  285.55  5043.4  284.31  5050.2  291.08
  5110.5  295.69  5148.9   296.4  5153.9  293.03  5226.7  297.88    5251  298.92
  5264.3  295.99  5353.2  294.37  5527.1  296.55  5601.4  298.23  5636.8  299.19
#Mann= 7 ,-1 , 0
  4194.5      .1       0  4876.4     .12       0    4997     .07       0
    5003     .12       0  5226.7      .1       0  5527.1     .05       0
  5601.4      .1       0
Bank Sta=4979.9,5050.2
XS Rating Curve= 0 ,0
Exp/Cntr=0.3,0.1