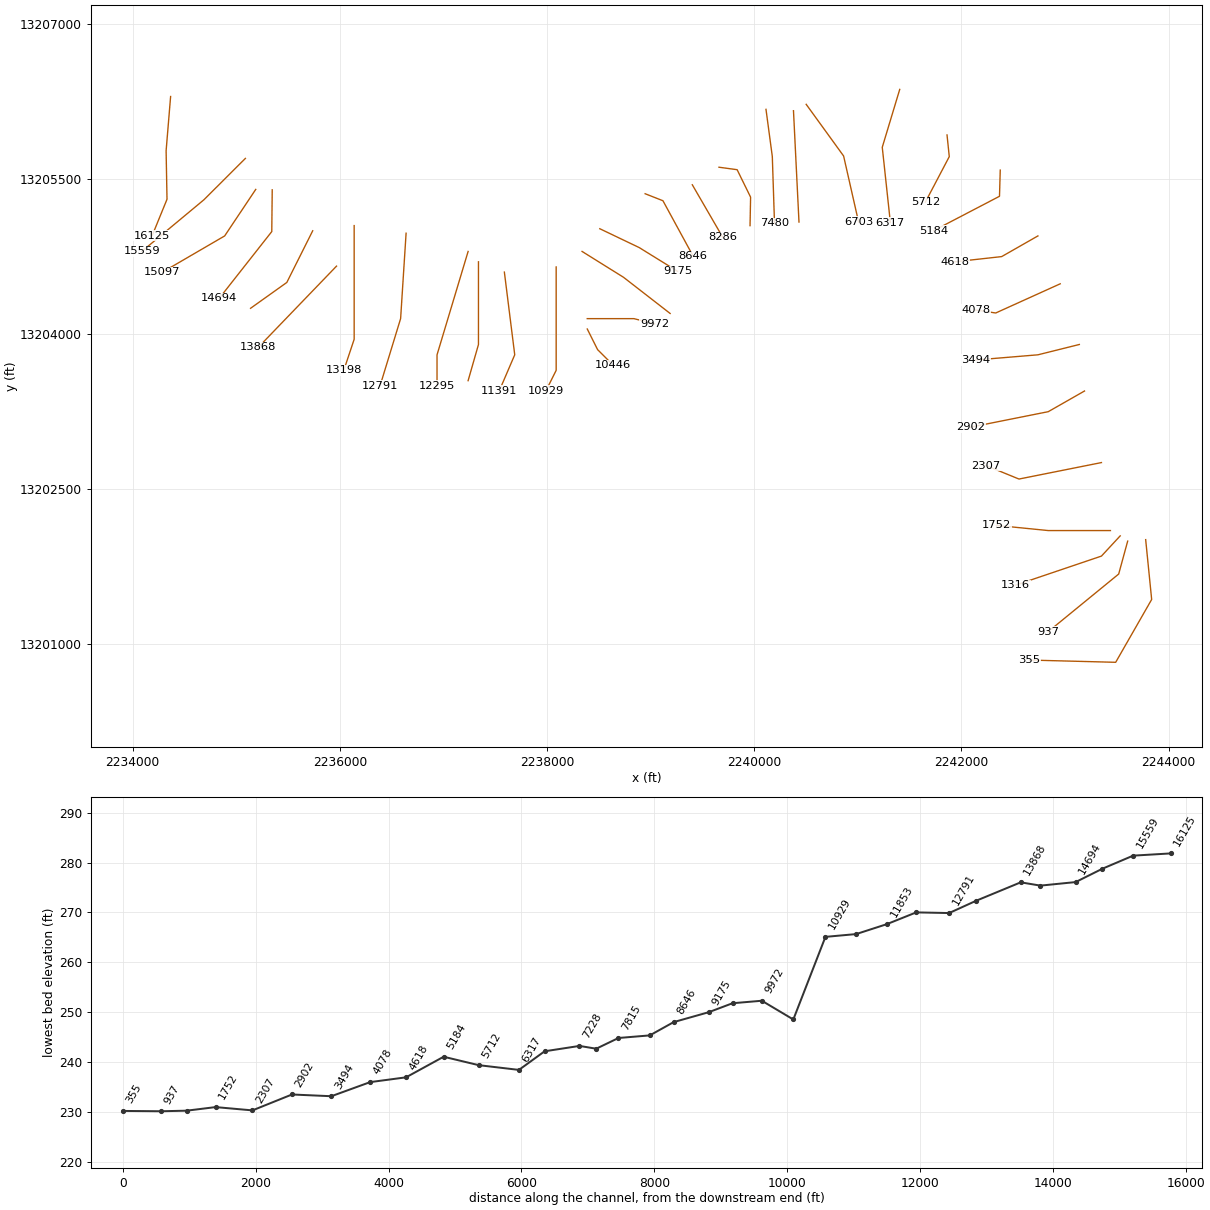
HEC-RAS study KENTUCK CREEK.prj: KENTUCK CREEK Base Level Engineering

--- KENTUCK CREEK.g01 (geometry) --- (continued)

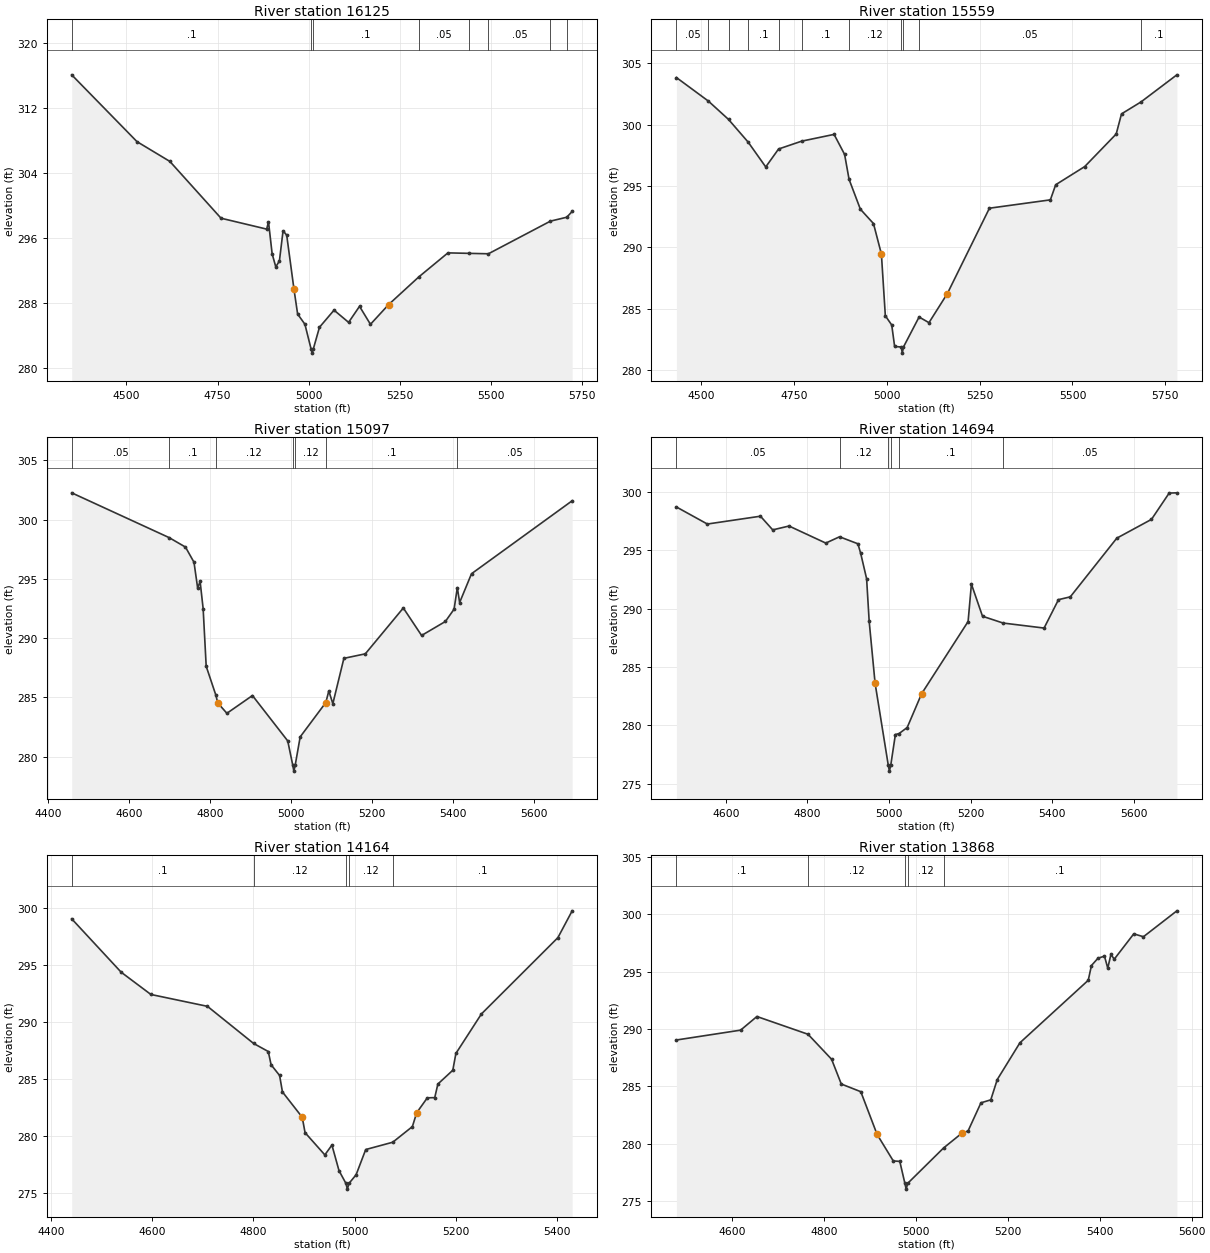
Type RM Length L Ch R = 1 ,16125   ,566,566,566
BEGIN DESCRIPTION:
KENTUCK CREEK 31.0
END DESCRIPTION:
XS GIS Cut Line= 4
      2234365.97     13206295.54      2234322.56     13205770.33
      2234331.24     13205301.58      2234188.37      13204950.9
#Sta/Elev= 30
  4349.5  316.04  4528.8  307.83  4619.1   305.4  4759.6  298.42    4885  297.08
    4890  297.98    4900  294.05    4910  292.44    4920  293.17    4930  296.87
    4940  296.34    4960  289.69    4970  286.64    4990  285.39    5007  282.34
  5009.8  281.84    5013  282.34    5030  285.02    5070  287.12    5110  285.62
    5140  287.59    5170  285.38    5220  287.81  5302.9  291.21  5382.8  294.16
  5441.4   294.1    5494  294.05  5664.3  298.06  5709.1  298.54    5724  299.25
#Mann= 8 ,-1 , 0
  4349.5      .1       0    5007     .07       0    5013      .1       0
  5302.9     .05       0  5441.4      .1       0    5494     .05       0
  5664.3      .1       0  5709.1     .05       0
Bank Sta=4960,5220
XS Rating Curve= 0 ,0
Exp/Cntr=0.3,0.1

Type RM Length L Ch R = 1 ,15559   ,462,462,462
BEGIN DESCRIPTION:
KENTUCK CREEK 30.0
END DESCRIPTION:
XS GIS Cut Line= 3
      2235087.73     13205696.87      2234687.72     13205296.85
      2234087.74     13204796.87
#Sta/Elev= 30
  4434.3  303.83  4520.4  301.91  4574.5  300.42  4627.4  298.57  4674.7  296.55
  4709.2  298.01  4771.5  298.65  4858.6   299.2  4886.9  297.57  4898.9  295.54
  4929.3  293.11  4964.6  291.94  4985.9  289.46  4996.5  284.43  5013.7  283.68
  5021.5  281.93  5039.3  281.89  5042.1  281.39  5045.3  281.89  5087.3  284.33
  5113.9  283.87  5163.4  286.24  5276.6  293.19  5440.6  293.87  5454.9   295.1
    5533  296.58  5617.7  299.23    5632  300.87  5684.3  301.84    5781  304.05
#Mann= 11 ,-1 , 0
  4434.3     .05       0  4520.4      .1       0  4574.5     .05       0
  4627.4      .1       0  4709.2     .05       0  4771.5      .1       0
  4898.9     .12       0  5039.3     .07       0  5045.3     .12       0
  5087.3     .05       0  5684.3      .1       0
Bank Sta=4985.9,5163.4
XS Rating Curve= 0 ,0
Exp/Cntr=0.3,0.1

Type RM Length L Ch R = 1 ,15097   ,403,403,403
BEGIN DESCRIPTION:
KENTUCK CREEK 29.0
END DESCRIPTION:
XS GIS Cut Line= 3
       2235187.7     13205396.83      2234887.72     13204946.86
      2234287.74     13204596.87
#Sta/Elev= 30
  4459.2  302.26  4699.7  298.48  4740.1  297.68  4761.1   296.4  4770.1  294.23
  4776.2  294.78  4783.7  292.48  4791.2  287.62  4815.2  285.17  4819.7  284.53
  4842.3  283.65  4905.4  285.15  4992.5  281.32  5004.9  279.27  5007.6  278.77
  5010.9  279.27  5023.2  281.66  5086.5  284.56  5093.9  285.54  5103.8  284.46
  5131.1  288.29    5184  288.67  5277.8  292.54  5322.9  290.22  5381.6   291.4
  5403.1  292.44  5411.1  294.26  5416.8     293  5446.1  295.43  5694.6  301.59
#Mann= 7 ,-1 , 0
  4459.2     .05       0  4699.7      .1       0  4815.2     .12       0
  5004.9     .07       0  5010.9     .12       0  5086.5      .1       0
  5411.1     .05       0
Bank Sta=4819.7,5086.5
XS Rating Curve= 0 ,0
Exp/Cntr=0.3,0.1

Type RM Length L Ch R = 1 ,14694   ,530,530,530
BEGIN DESCRIPTION:
KENTUCK CREEK 28.0
END DESCRIPTION:
XS GIS Cut Line= 3
      2235346.87      13205392.7      2235342.53     13204989.08
      2234834.71     13204342.37
#Sta/Elev= 30
  4479.1  298.69  4554.9  297.23    4685   297.9    4715  296.73    4755  297.06
    4845   295.6  4878.7  296.14  4923.7  295.54  4930.5  294.72    4945  292.55
  4951.3   288.9  4965.8   283.6  4998.1  276.59  5000.8  276.09  5004.1  276.59
  5015.5  279.22  5024.3   279.3  5044.4  279.82  5079.7  282.71  5193.6  288.89
  5201.7  292.09  5228.9  289.34  5279.2  288.76  5379.7  288.33    5415  290.76
  5443.9     291  5557.8  296.02  5642.8  297.63  5686.1  299.88    5705   299.9
#Mann= 6 ,-1 , 0
  4479.1     .05       0  4878.7     .12       0  4998.1     .07       0
  5004.1     .12       0  5024.3      .1       0  5279.2     .05       0
Bank Sta=4965.8,5079.7
XS Rating Curve= 0 ,0
Exp/Cntr=0.3,0.1

Type RM Length L Ch R = 1 ,14164   ,296,296,296
BEGIN DESCRIPTION:
KENTUCK CREEK 27.0
END DESCRIPTION:
XS GIS Cut Line= 3
      2235737.71     13204996.84      2235487.72     13204496.85
      2235137.73     13204246.86
#Sta/Elev= 30
    4441  299.07  4538.8  294.39  4597.5  292.44  4709.3   291.4  4800.4  288.15
  4829.5  287.44  4835.1  286.28  4851.9  285.34  4857.5   283.9  4896.6  281.68
  4902.2  280.33  4941.3  278.38  4955.3  279.24  4969.3     277    4983  275.88
  4985.8  275.38    4989  275.88  5003.1  276.64  5022.1  278.85  5075.5  279.49
  5114.3  280.86  5122.9  282.08  5143.8  283.38  5158.5   283.4  5164.7  284.59
  5194.2   285.8  5200.3  287.27  5250.7  290.73  5401.9  297.42  5430.1  299.77
#Mann= 5 ,-1 , 0
    4441      .1       0  4800.4     .12       0    4983     .07       0
    4989     .12       0  5075.5      .1       0
Bank Sta=4896.6,5122.9
XS Rating Curve= 0 ,0
Exp/Cntr=0.3,0.1

Type RM Length L Ch R = 1 ,13868   ,670,670,670
BEGIN DESCRIPTION:
KENTUCK CREEK 26.0
END DESCRIPTION:
XS GIS Cut Line= 2
      2235967.51     13204654.86      2235212.32     13203869.28
#Sta/Elev= 30
  4478.2  289.05    4618  289.91  4653.5   291.1  4764.8  289.55  4816.1  287.37
  4837.2  285.21  4879.7  284.54  4915.2  280.81  4950.4   278.5  4964.6  278.46
  4975.7  276.54  4978.5  276.04  4981.7  276.54  5059.9  279.63  5099.1   280.9
  5113.3  281.12  5141.3  283.57  5162.7  283.83  5176.8   285.6  5226.2  288.81
  5374.9  294.26  5381.9  295.55    5396  296.18  5410.2  296.37  5417.4  295.32
  5424.3  296.52  5431.5   296.1    5474  298.31  5495.1  298.06  5567.9  300.32
#Mann= 5 ,-1 , 0
  4478.2      .1       0  4764.8     .12       0  4975.7     .07       0
  4981.7     .12       0  5059.9      .1       0
Bank Sta=4915.2,5099.1
XS Rating Curve= 0 ,0
Exp/Cntr=0.3,0.1

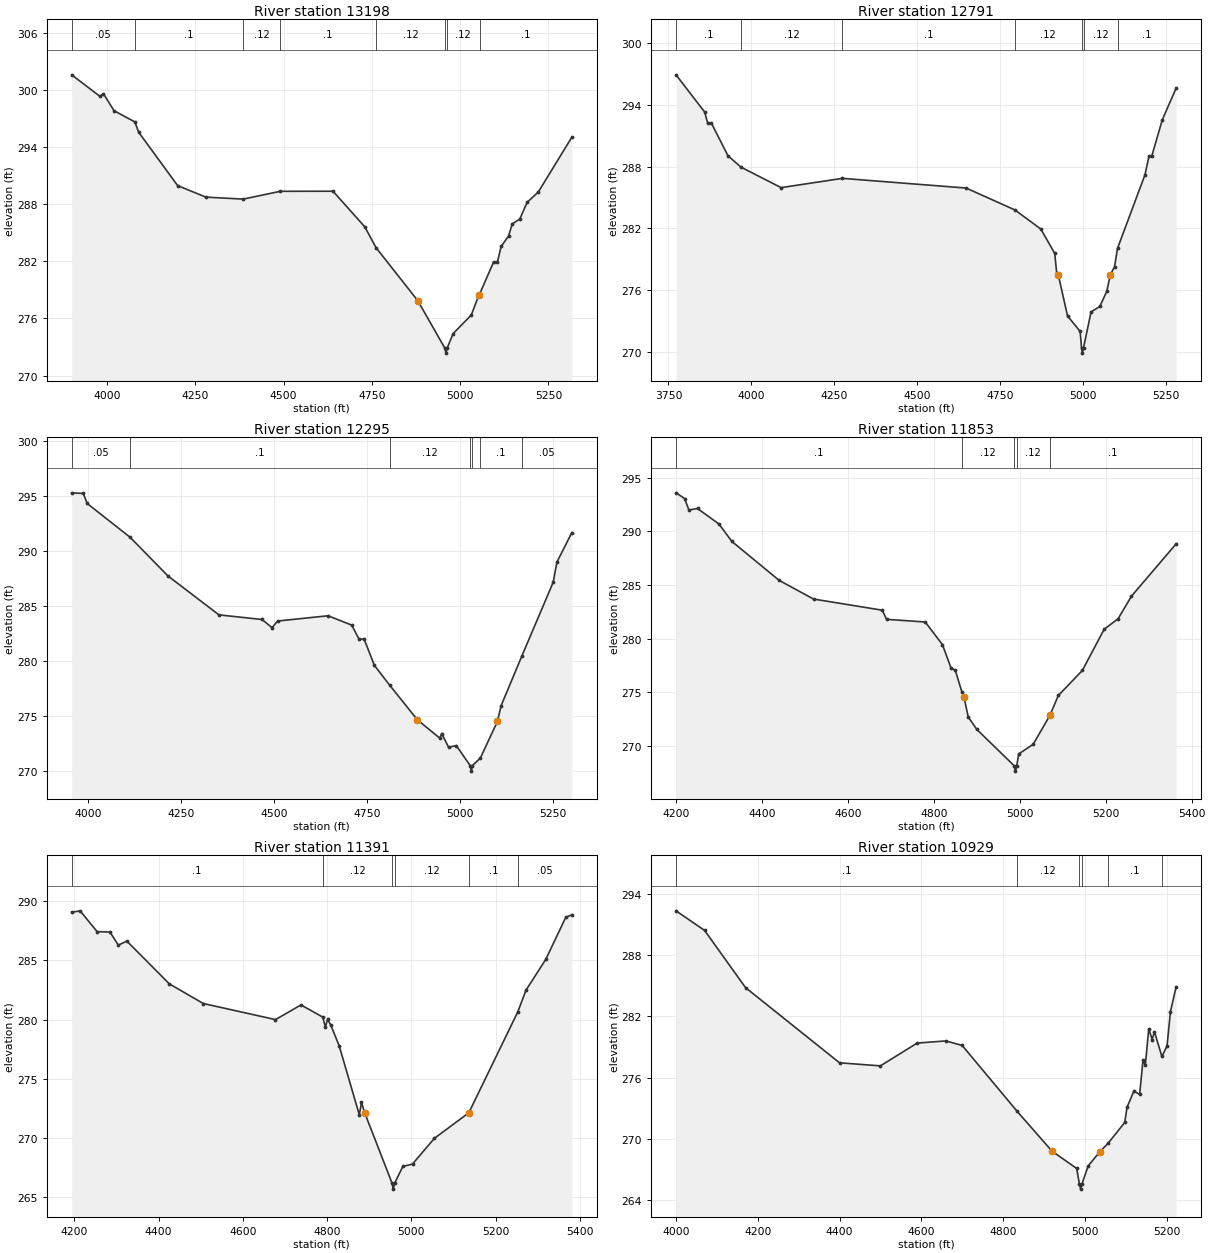
Type RM Length L Ch R = 1 ,13198   ,407,407,407
BEGIN DESCRIPTION:
KENTUCK CREEK 25.0
END DESCRIPTION:
XS GIS Cut Line= 3
      2236137.72     13205046.86      2236137.72     13203946.86
      2236037.73     13203646.88
#Sta/Elev= 30
    3900  301.57    3980  299.31    3990  299.59    4020   297.8  4078.7  296.63
    4090  295.53    4200  289.94    4280  288.73  4385.8  288.52  4490.7  289.34
    4640  289.35    4730  285.61  4761.7  283.43    4880  277.86    4957  272.85
  4959.8  272.35    4963  272.85    4980   274.4  5031.6  276.35  5052.7  278.42
  5054.9  278.53  5094.9  281.93  5105.4  281.89    5116  283.55    5137  284.64
  5147.6  285.92  5168.7  286.42  5189.7  288.18  5221.4  289.27  5316.2  295.02
#Mann= 8 ,-1 , 0
    3900     .05       0  4078.7      .1       0  4385.8     .12       0
  4490.7      .1       0  4761.7     .12       0    4957     .07       0
    4963     .12       0  5054.9      .1       0
Bank Sta=4880,5052.7
XS Rating Curve= 0 ,0
Exp/Cntr=0.3,0.1

Type RM Length L Ch R = 1 ,12791   ,496,496,496
BEGIN DESCRIPTION:
KENTUCK CREEK 24.0
END DESCRIPTION:
XS GIS Cut Line= 3
      2236639.03     13204973.03      2236586.17     13204147.14
      2236387.71     13203496.83
#Sta/Elev= 30
  3772.9  296.92  3859.3   293.3    3868  292.26  3879.3  292.24  3929.4  289.06
  3968.7  287.95  4089.7  285.96  4274.4  286.86  4647.2  285.92  4794.6  283.79
  4872.6  281.93  4914.4  279.57  4920.2  277.68  4925.4  277.44    4953  273.49
    4991  271.99  4995.1  270.38  4997.8  269.88  5001.1  270.38  5023.8  273.88
  5050.4  274.42  5071.3  275.89  5081.7  277.47  5094.7  278.28  5103.6  280.06
  5186.3   287.2  5198.3     289  5207.2  289.06  5238.6  292.55  5280.4  295.64
#Mann= 7 ,-1 , 0
  3772.9      .1       0  3968.7     .12       0  4274.4      .1       0
  4794.6     .12       0  4995.1     .07       0  5001.1     .12       0
  5103.6      .1       0
Bank Sta=4925.4,5081.7
XS Rating Curve= 0 ,0
Exp/Cntr=0.3,0.1

Type RM Length L Ch R = 1 ,12295   ,442,442,442
BEGIN DESCRIPTION:
KENTUCK CREEK 23.0
END DESCRIPTION:
XS GIS Cut Line= 3
      2237237.71     13204796.83      2236937.72     13203796.86
      2236937.72     13203496.86
#Sta/Elev= 30
    3956  295.32  3987.3  295.26  3997.7  294.35  4113.3  291.27  4214.4  287.77
  4351.8  284.22  4467.5   283.8  4494.5  283.06  4509.3  283.66    4645  284.14
  4708.5  283.29  4728.6  281.99  4741.6  282.04  4769.4  279.63  4810.9  277.81
  4885.2  274.67  4945.2  273.01  4950.4  273.43  4968.7  272.19  4989.6  272.33
    5027  270.51  5029.8  270.01    5033  270.51  5054.3   271.2    5100  274.53
    5110  275.96  5166.1  280.51    5250  287.19    5260  289.02    5300   291.7
#Mann= 7 ,-1 , 0
    3956     .05       0  4113.3      .1       0  4810.9     .12       0
    5027     .07       0    5033     .12       0  5054.3      .1       0
  5166.1     .05       0
Bank Sta=4885.2,5100
XS Rating Curve= 0 ,0
Exp/Cntr=0.3,0.1

Type RM Length L Ch R = 1 ,11853   ,462,462,462
BEGIN DESCRIPTION:
KENTUCK CREEK 22.0
END DESCRIPTION:
XS GIS Cut Line= 3
      2237337.72     13204696.85      2237337.72     13203896.85
      2237237.72     13203546.86
#Sta/Elev= 30
    4200  293.59    4220  293.06    4230  291.99    4250  292.13    4300  290.68
    4330  289.06    4440  285.43    4520  283.69    4680  282.65    4690   281.8
    4780  281.55    4820  279.44    4840  277.27    4850  277.04    4865  275.07
    4870   274.6    4880   272.7    4900  271.54    4987  268.15  4989.8  267.65
    4993  268.15  4997.5  269.25  5031.2  270.15  5070.2  272.85  5089.7   274.7
  5145.6  277.03  5196.3  280.87  5228.8  281.85    5260  283.96    5364  288.84
#Mann= 5 ,-1 , 0
    4200      .1       0    4865     .12       0    4987     .07       0
    4993     .12       0  5070.2      .1       0
Bank Sta=4870,5070.2
XS Rating Curve= 0 ,0
Exp/Cntr=0.3,0.1

Type RM Length L Ch R = 1 ,11391   ,462,462,462
BEGIN DESCRIPTION:
KENTUCK CREEK 21.0
END DESCRIPTION:
XS GIS Cut Line= 3
      2237587.72     13204596.83      2237687.72     13203796.86
      2237537.72     13203446.84
#Sta/Elev= 30
  4193.8  289.07  4213.9   289.2  4254.2  287.44  4284.5  287.41  4304.6   286.3
  4324.8  286.64  4425.6  283.02  4506.2  281.36  4677.5     280    4738  281.24
  4789.8  280.21  4795.9  279.36    4801  280.01  4808.5  279.56  4828.7  277.78
  4876.5  271.94  4881.6     273  4889.1  272.13  4954.2  266.16  4956.9  265.66
  4960.2  266.16  4979.8  267.58  5002.7  267.78  5054.4  269.95  5136.4  272.12
  5252.8  280.67    5272  282.49  5319.1   285.1  5366.3  288.64  5380.8  288.87
#Mann= 6 ,-1 , 0
  4193.8      .1       0  4789.8     .12       0  4954.2     .07       0
  4960.2     .12       0  5136.4      .1       0  5252.8     .05       0
Bank Sta=4889.1,5136.4
XS Rating Curve= 0 ,0
Exp/Cntr=0.3,0.1

Type RM Length L Ch R = 1 ,10929   ,483,483,483
BEGIN DESCRIPTION:
KENTUCK CREEK 20.0
END DESCRIPTION:
XS GIS Cut Line= 3
      2238087.72     13204646.86      2238087.72     13203646.86
      2237987.72     13203446.86
#Sta/Elev= 30
    4000  292.33    4070  290.41    4170  284.82    4400  277.46    4500  277.16
    4590  279.39    4660   279.6    4700  279.16  4834.8   272.7    4920  268.81
    4980  267.13    4987   265.6  4989.8   265.1    4993   265.6  5008.4  267.38
  5036.3  268.73  5056.9  269.58  5097.8  271.62  5103.4  273.11  5120.2   274.7
  5134.2  274.36  5142.5  277.75  5148.1  277.21  5156.5   280.8  5164.9  279.74
  5170.5   280.5  5188.6  278.08  5201.2  279.09  5209.6  282.47  5223.6   284.9
#Mann= 6 ,-1 , 0
    4000      .1       0  4834.8     .12       0    4987     .07       0
    4993     .12       0  5056.9      .1       0  5188.6     .08       0
Bank Sta=4920,5036.3
XS Rating Curve= 0 ,0
Exp/Cntr=0.3,0.1

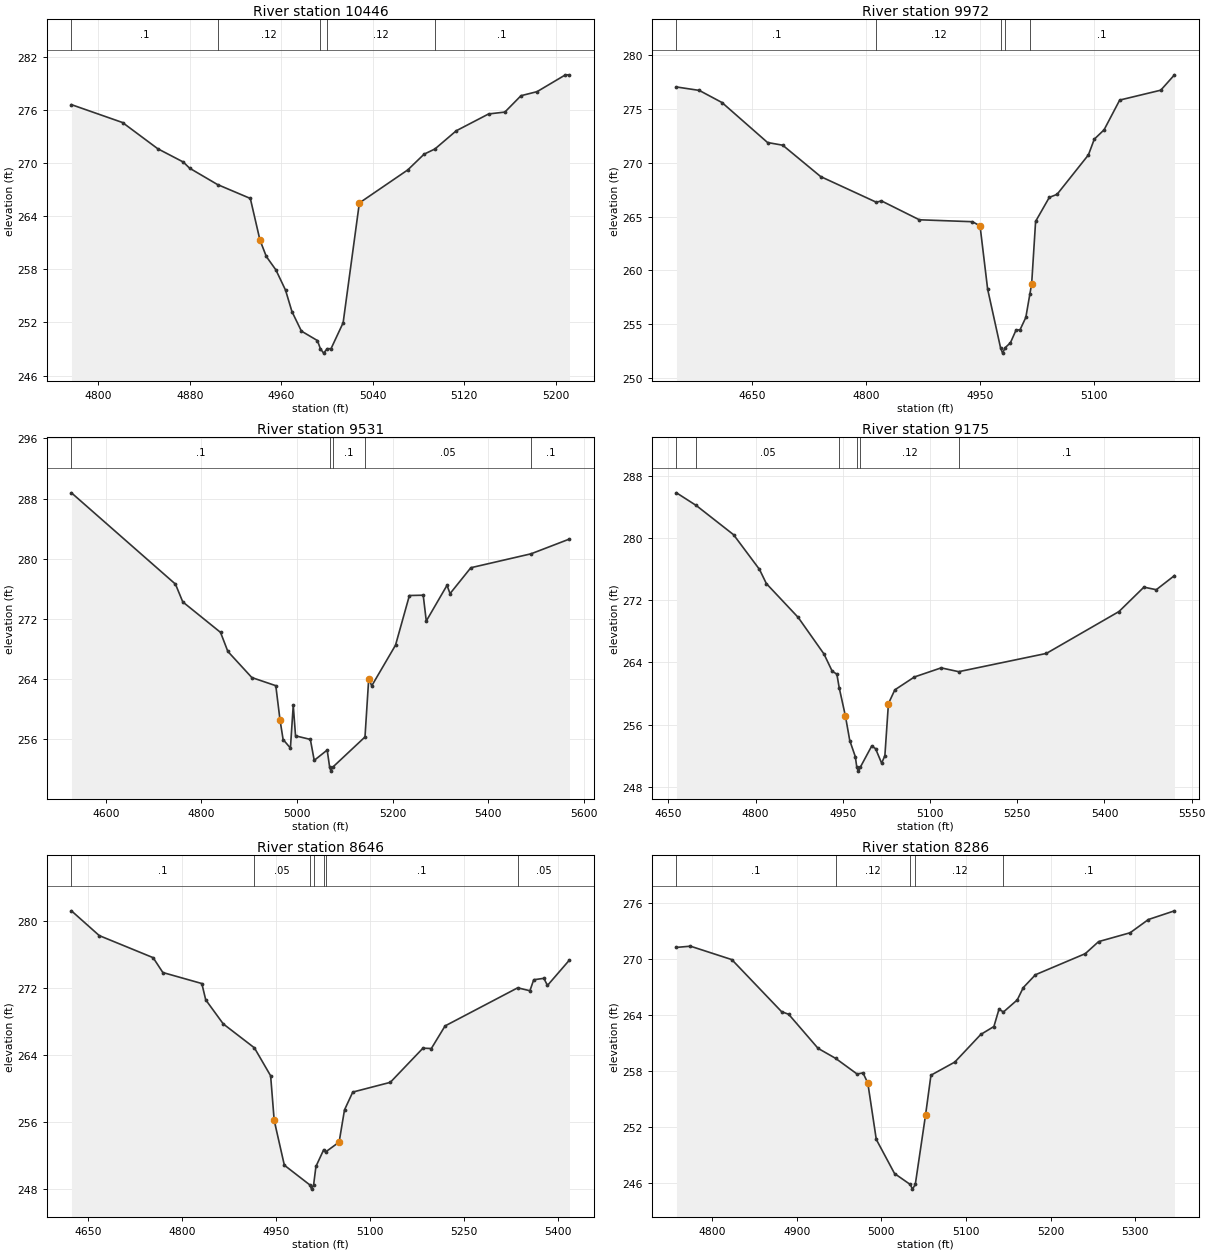
Type RM Length L Ch R = 1 ,10446   ,474,474,474
BEGIN DESCRIPTION:
KENTUCK CREEK 19.0
END DESCRIPTION:
XS GIS Cut Line= 3
      2238387.72     13204046.85      2238487.72     13203846.85
       2238637.7     13203696.88
#Sta/Elev= 30
  4776.4  276.61  4821.1  274.59  4851.9  271.63  4874.2  270.13  4879.8  269.43
  4904.2  267.58  4932.9  266.01  4941.3  261.32  4946.9  259.45  4955.3  257.93
  4963.7  255.65  4969.3  253.23  4977.6  251.02  4991.6  249.95  4994.2  249.03
    4997  248.53  5000.2  249.03  5003.5  249.03  5014.1  251.96  5028.3   265.5
  5070.7  269.24  5084.9  271.01  5094.4   271.6  5113.1  273.66  5141.4  275.56
  5155.6  275.77  5169.7  277.62  5183.8  278.08  5208.6  279.98  5212.1  279.98
#Mann= 5 ,-1 , 0
  4776.4      .1       0  4904.2     .12       0  4994.2     .07       0
  5000.2     .12       0  5094.4      .1       0
Bank Sta=4941.3,5028.3
XS Rating Curve= 0 ,0
Exp/Cntr=0.3,0.1

Type RM Length L Ch R = 1 ,9972    ,441,441,441
BEGIN DESCRIPTION:
KENTUCK CREEK 18.0
END DESCRIPTION:
XS GIS Cut Line= 3
      2238387.72     13204146.85      2238837.72     13204146.86
      2239037.76     13204096.84
#Sta/Elev= 30
    4550  277.06    4580  276.74    4610  275.61    4670  271.89    4690  271.64
    4740  268.72  4813.4  266.33    4820  266.46    4870   264.7    4940  264.52
    4950  264.13    4960  258.24    4977  252.79  4979.7  252.29    4983  252.79
    4990  253.25  4997.5  254.45  5002.6  254.45  5010.3  255.61  5015.7  257.81
    5018  258.74  5023.2  264.55  5041.2  266.78  5051.5  267.07  5092.8  270.74
  5100.5   272.2  5113.4  273.07    5134  275.84  5188.1  276.76  5206.2  278.19
#Mann= 5 ,-1 , 0
    4550      .1       0  4813.4     .12       0    4977     .07       0
    4983     .12       0  5015.7      .1       0
Bank Sta=4950,5018
XS Rating Curve= 0 ,0
Exp/Cntr=0.3,0.1

Type RM Length L Ch R = 1 ,9531    ,356,356,356
BEGIN DESCRIPTION:
KENTUCK CREEK 17.0
END DESCRIPTION:
XS GIS Cut Line= 3
      2238337.72     13204796.86      2238737.72     13204546.85
      2239187.73     13204196.85
#Sta/Elev= 30
  4528.3  288.76  4745.9  276.63  4761.2  274.27  4840.2  270.22  4855.5  267.69
  4905.7  264.22  4955.8  263.14  4964.6   258.6  4971.1  255.99  4986.4  254.85
  4992.3  260.54  4997.1  256.48  5028.1     256  5036.2  253.22  5063.3  254.59
  5068.5  252.29  5071.2  251.79  5074.5  252.29  5142.4  256.33  5150.2  264.08
  5156.5  263.12  5206.3  268.53  5235.3  275.12  5264.2  275.16  5270.6  271.73
    5314  276.48  5320.3  275.37  5363.8  278.81  5489.8  280.66  5570.1  282.62
#Mann= 5 ,-1 , 0
  4528.3      .1       0  5068.5     .07       0  5074.5      .1       0
  5142.4     .05       0  5489.8      .1       0
Bank Sta=4964.6,5150.2
XS Rating Curve= 0 ,0
Exp/Cntr=0.3,0.1

Type RM Length L Ch R = 1 ,9175    ,529,529,529
BEGIN DESCRIPTION:
KENTUCK CREEK 16.0
END DESCRIPTION:
XS GIS Cut Line= 3
      2238508.91     13205016.55      2238889.16     13204834.24
      2239258.92     13204605.09
#Sta/Elev= 30
  4663.8  285.82  4697.8  284.19    4762  280.43  4806.6  275.96  4818.4  274.14
  4873.2  269.78  4917.5  265.08  4931.6  262.87  4939.7  262.48  4943.7  260.74
  4954.3  257.13  4961.9  253.93  4971.4  251.87    4974   250.5  4976.7     250
    4980   250.5  4999.6  253.23  5006.3  252.89  5016.7  251.02  5022.3  251.99
  5028.4  258.69  5039.4  260.46  5073.1  262.12  5119.1  263.29  5149.3   262.8
  5300.1  265.15    5425  270.54  5467.9  273.68  5489.2  273.35  5520.5  275.17
#Mann= 6 ,-1 , 0
  4663.8      .1       0  4697.8     .05       0  4943.7     .12       0
    4974     .07       0    4980     .12       0  5149.3      .1       0
Bank Sta=4954.3,5028.4
XS Rating Curve= 0 ,0
Exp/Cntr=0.3,0.1

Type RM Length L Ch R = 1 ,8646    ,360,360,360
BEGIN DESCRIPTION:
Mapping XS c382bf6d
END DESCRIPTION:
XS GIS Cut Line= 3
      2238946.42     13205355.08      2239118.33     13205287.37
      2239409.72     13204751.41
#Sta/Elev= 30
  4623.6  281.16    4668  278.21    4754  275.58  4769.5  273.81  4831.7   272.5
  4837.9  270.56  4865.9  267.69  4915.6  264.84  4941.5  261.51  4947.2  256.19
  4963.4  250.86  5004.1  248.51  5006.8  248.01  5010.1  248.51  5013.8  250.71
  5026.3  252.72  5029.3  252.44  5050.8  253.61  5059.4  257.45  5072.6  259.57
  5132.5  260.73  5184.6   264.8    5198  264.76  5219.9  267.45  5335.8  271.99
  5355.3  271.64  5361.4  272.95  5377.6  273.12  5383.3  272.27  5418.4   275.3
#Mann= 7 ,-1 , 0
  4623.6      .1       0  4915.6     .05       0  5004.1    .035       0
  5010.1     .05       0  5026.3     .12       0  5029.3      .1       0
  5335.8     .05       0
Bank Sta=4947.2,5050.8
XS Rating Curve= 0 ,0
Exp/Cntr=0.3,0.1

Type RM Length L Ch R = 1 ,8286    ,471,471,471
BEGIN DESCRIPTION:
KENTUCK CREEK 15.0
END DESCRIPTION:
XS GIS Cut Line= 2
      2239401.85     13205441.61       2239696.4     13204932.13
#Sta/Elev= 30
    4758  271.25  4774.5  271.38  4823.4  269.94  4882.2  264.36  4890.6  264.08
  4925.3  260.43    4946  259.36  4971.4  257.68  4978.4   257.8  4984.1  256.71
  4994.1  250.67  5015.7  247.01  5034.2  245.84  5036.9  245.34  5040.2  245.84
  5052.3  253.27  5058.7  257.55  5086.9  258.96  5117.6  261.92  5133.1  262.77
  5139.1  264.62  5144.4  264.33  5160.7  265.62  5167.8  266.94  5182.2  268.32
  5241.1  270.58  5256.8  271.87  5294.1  272.82  5315.7  274.24  5346.5  275.17
#Mann= 5 ,-1 , 0
    4758      .1       0    4946     .12       0  5034.2     .07       0
  5040.2     .12       0  5144.4      .1       0
Bank Sta=4984.1,5052.3
XS Rating Curve= 0 ,0
Exp/Cntr=0.3,0.1

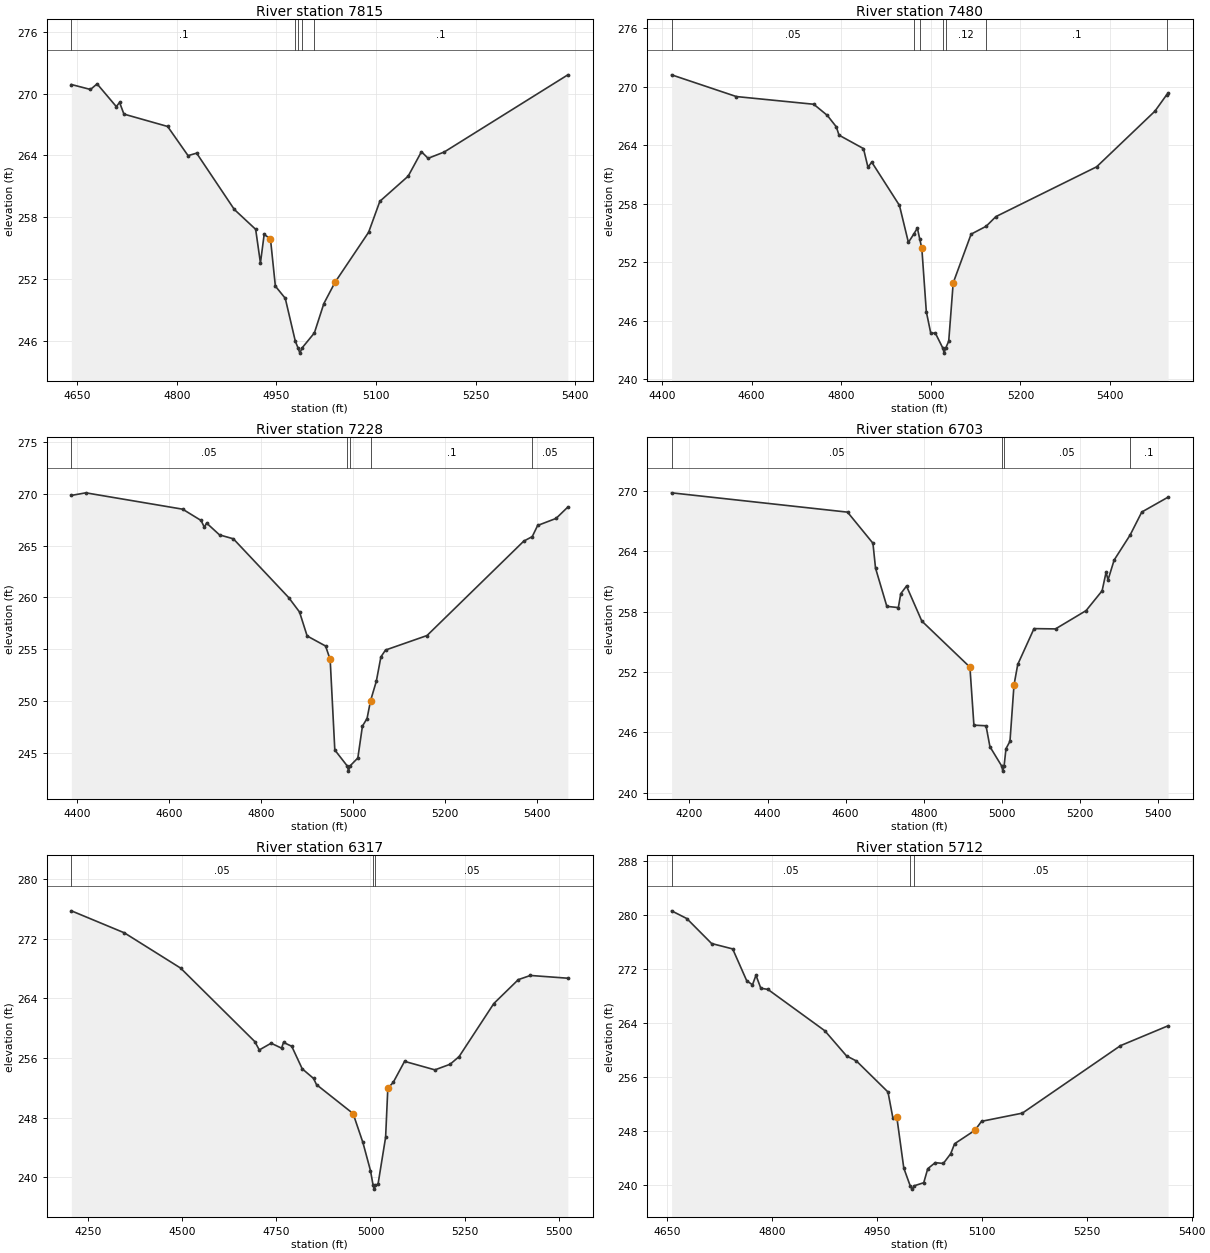
Type RM Length L Ch R = 1 ,7815    ,335,335,335
BEGIN DESCRIPTION:
KENTUCK CREEK 14.0
END DESCRIPTION:
XS GIS Cut Line= 4
      2239659.23     13205611.49       2239834.4      13205587.6
      2239964.43     13205322.23      2239959.12     13205046.19
#Sta/Elev= 30
  4640.8  270.88  4669.6   270.4  4679.6  270.94  4708.5  268.74  4713.5  269.14
    4720  268.01  4785.9  266.81  4816.7  263.98  4829.6  264.22  4886.4  258.76
  4918.6  256.83  4925.8  253.56  4931.4  256.33  4940.9  255.91  4948.3  251.32
  4963.2  250.14  4978.4  245.97  4982.5  245.32  4985.2  244.82  4988.5  245.32
  5007.1  246.78  5021.4  249.63  5038.3   251.7  5088.9  256.55  5105.8  259.55
  5148.5  261.99  5168.5  264.36  5178.5  263.72  5202.8  264.33  5389.2  271.82
#Mann= 5 ,-1 , 0
  4640.8      .1       0  4978.4     .12       0  4982.5     .07       0
  4988.5     .12       0  5007.1      .1       0
Bank Sta=4940.9,5038.3
XS Rating Curve= 0 ,0
Exp/Cntr=0.3,0.1

Type RM Length L Ch R = 1 ,7480    ,252,252,252
BEGIN DESCRIPTION:
KENTUCK CREEK 13.0
END DESCRIPTION:
XS GIS Cut Line= 3
      2240113.04     13206171.43      2240174.08     13205714.98
      2240195.31     13205067.44
#Sta/Elev= 30
  4421.3  271.23  4565.9     269  4738.7  268.21  4768.9  267.07  4789.1  265.89
  4795.1  265.04  4849.7  263.66  4859.7  261.75  4868.2  262.27    4930  257.83
    4950  254.03  4961.6  254.86    4970   255.5  4975.1  254.43    4980  253.41
    4990  246.92    5000   244.7    5010  244.74    5027  243.17  5029.8  242.67
    5033  243.17    5040  243.89    5050  249.88    5090  254.88  5123.6  255.69
  5145.3  256.68  5370.2  261.79  5500.3   267.5  5526.2  269.16  5529.7  269.32
#Mann= 7 ,-1 , 0
  4421.3     .05       0  4961.6      .1       0  4975.1     .12       0
    5027     .07       0    5033     .12       0  5123.6      .1       0
  5526.2     .05       0
Bank Sta=4980,5050
XS Rating Curve= 0 ,0
Exp/Cntr=0.3,0.1

Type RM Length L Ch R = 1 ,7228    ,525,525,525
BEGIN DESCRIPTION:
KENTUCK CREEK 12.0
END DESCRIPTION:
XS GIS Cut Line= 2
      2240378.42     13206158.21      2240431.47     13205081.32
#Sta/Elev= 30
  4387.9  269.85  4419.3   270.1  4629.6  268.52  4669.6  267.43  4676.6  266.78
  4681.6  267.18  4709.6  266.04  4739.7  265.66  4859.8  259.99  4883.4  258.59
  4899.9  256.28  4939.9  255.31  4949.9  254.01    4960  245.27    4987  243.73
  4989.7  243.23    4993  243.73    5010   244.5    5020  247.58    5030  248.31
  5037.5  250.01  5050.1   251.9  5060.1  254.26  5070.1  254.92  5160.2  256.32
  5370.4  265.44  5388.7  265.87  5400.5  266.95  5440.5  267.63  5466.1  268.73
#Mann= 5 ,-1 , 0
  4387.9     .05       0    4987     .03       0    4993     .05       0
  5037.5      .1       0  5388.7     .05       0
Bank Sta=4949.9,5037.5
XS Rating Curve= 0 ,0
Exp/Cntr=0.3,0.1

Type RM Length L Ch R = 1 ,6703    ,386,386,386
BEGIN DESCRIPTION:
Mapping XS 2f61575c
END DESCRIPTION:
XS GIS Cut Line= 3
      2240501.07     13206219.83      2240862.22     13205720.24
      2241006.67     13205082.25
#Sta/Elev= 30
  4154.5  269.82  4604.8   267.9  4669.8  264.81  4676.4  262.34  4705.4  258.53
  4734.8  258.41    4741  259.79  4755.7  260.55  4794.9  257.07    4918  252.49
  4928.2  246.72  4959.2  246.66  4969.2  244.58  4999.4  242.65  5002.1  242.15
  5005.4  242.65  5010.3  244.38  5020.5  245.12  5030.8  250.71  5040.4  252.76
    5082  256.32    5137  256.29  5215.3  258.11  5256.3  260.08  5266.4  261.92
  5271.5  261.17  5287.1  263.14  5327.9  265.62  5357.8  267.91  5425.1  269.39
#Mann= 4 ,-1 , 0
  4154.5     .05       0  4999.4     .03       0  5005.4     .05       0
  5327.9      .1       0
Bank Sta=4918,5030.8
XS Rating Curve= 0 ,0
Exp/Cntr=0.3,0.1

Type RM Length L Ch R = 1 ,6317    ,605,605,605
BEGIN DESCRIPTION:
KENTUCK CREEK 11.0
END DESCRIPTION:
XS GIS Cut Line= 3
      2241403.93     13206364.24      2241235.41      13205804.5
      2241313.66     13205076.15
#Sta/Elev= 30
  4206.6  275.71  4347.2  272.76  4496.3  268.04    4693   258.2  4705.2  257.07
  4736.5  257.97  4764.2  257.31  4769.4  258.08  4791.2  257.56    4819  254.54
  4849.1  253.25  4856.9  252.42    4954  248.54  4979.9  244.68    5000  240.91
  5007.1  238.92  5009.8  238.42  5013.1  238.92  5020.1  239.08  5040.2  245.36
  5046.1  251.95  5060.3  252.71  5090.5  255.54    5171   254.4  5211.2  255.15
  5235.2  256.18  5327.3  263.29  5392.2  266.49  5424.4  267.05  5523.7  266.68
#Mann= 3 ,-1 , 0
  4206.6     .05       0  5007.1     .03       0  5013.1     .05       0
Bank Sta=4954,5046.1
XS Rating Curve= 0 ,0
Exp/Cntr=0.3,0.1

Type RM Length L Ch R = 1 ,5712    ,528,528,528
BEGIN DESCRIPTION:
KENTUCK CREEK 10.0
END DESCRIPTION:
XS GIS Cut Line= 3
      2241860.51     13205923.71      2241882.22     13205713.85
      2241650.68     13205272.48
#Sta/Elev= 30
  4656.9  280.57  4678.6  279.43  4714.1  275.73  4744.2  274.93  4764.3  270.21
  4772.5  269.62  4777.5  271.03  4784.4  269.11  4794.5  268.94  4875.8  262.82
  4906.9  259.09    4921  258.34  4966.1  253.75  4973.1  249.91  4978.7  250.05
  4988.7  242.48  4997.8  239.87  5000.6  239.37  5003.8  239.87  5017.2  240.32
  5022.9  242.39  5033.6  243.29  5045.2  243.17  5055.7  244.61  5061.3  246.09
  5090.3  248.08  5099.8  249.41  5158.1  250.62  5298.3  260.61  5366.3  263.55
#Mann= 3 ,-1 , 0
  4656.9     .05       0  4997.8     .03       0  5003.8     .05       0
Bank Sta=4978.7,5090.3
XS Rating Curve= 0 ,0
Exp/Cntr=0.3,0.1

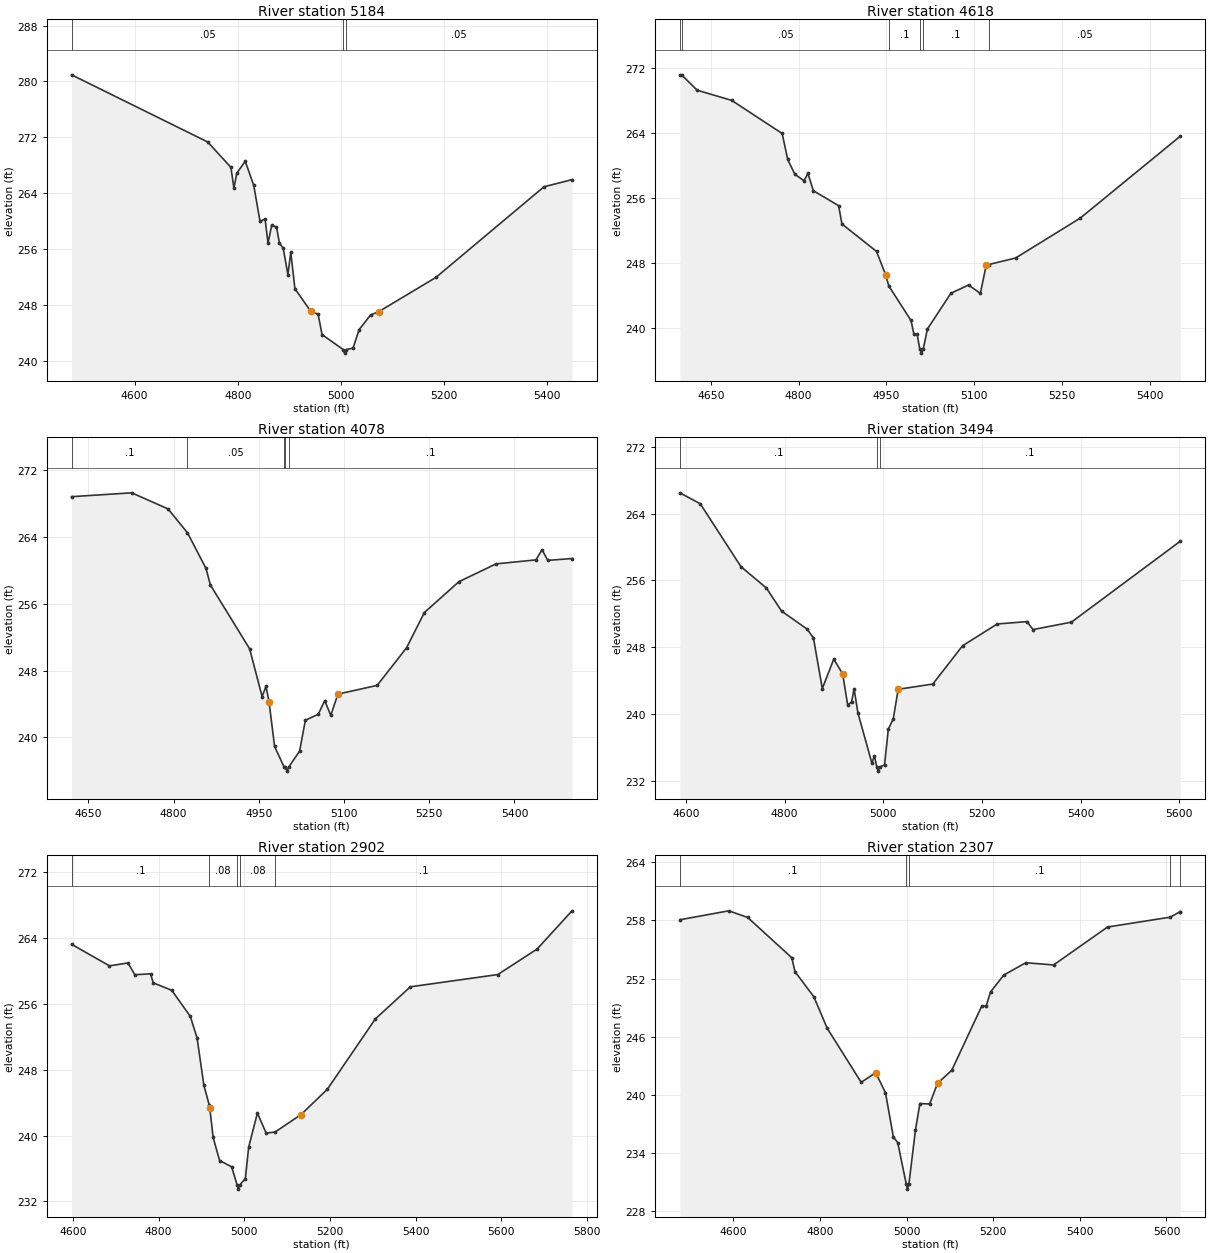
Type RM Length L Ch R = 1 ,5184    ,566,566,566
BEGIN DESCRIPTION:
KENTUCK CREEK 9.0
END DESCRIPTION:
XS GIS Cut Line= 3
      2242374.25     13205583.61      2242367.02     13205330.35
      2241731.47     13204998.13
#Sta/Elev= 30
  4477.8  280.95  4741.7  271.33  4786.8  267.69  4792.6  264.68  4798.2  266.85
  4814.6  268.56  4831.1   265.1  4843.2  259.97  4853.1  260.26  4858.8  256.82
  4865.8  259.37  4875.2  259.14  4880.9  256.83  4888.3  256.08  4897.3  252.31
  4902.9  255.51  4910.9  250.31  4941.4  247.07    4956  246.62  4963.5  243.72
  5004.7  241.56  5007.4  241.06  5010.7  241.56  5023.7  241.79  5035.4  244.43
  5057.6  246.52  5073.9  247.02  5184.3  251.91  5393.8   264.9  5448.3  265.93
#Mann= 3 ,-1 , 0
  4477.8     .05       0  5004.7     .03       0  5010.7     .05       0
Bank Sta=4941.4,5073.9
XS Rating Curve= 0 ,0
Exp/Cntr=0.3,0.1

Type RM Length L Ch R = 1 ,4618    ,540,540,540
BEGIN DESCRIPTION:
KENTUCK CREEK 8.0
END DESCRIPTION:
XS GIS Cut Line= 3
      2242737.71     13204946.85      2242387.72     13204746.85
      2241937.69     13204696.85
#Sta/Elev= 30
  4596.9  271.13  4600.3  271.09  4626.4  269.24  4685.4  267.99  4771.8  263.92
  4781.2  260.73  4793.4  258.92  4809.2   258.1  4815.7  259.03  4825.1  256.89
  4868.3  255.05    4874   252.8  4933.1  249.43  4948.9  246.52    4954   245.2
  4992.1  240.94  4997.1  239.26  5002.5  239.26  5007.1  237.43  5009.8  236.93
  5013.1  237.43  5020.1  239.89  5060.4  244.29  5090.6   245.3  5110.7  244.27
  5120.7  247.73  5125.3  247.82    5171  248.62  5281.7  253.53  5452.8   263.6
#Mann= 6 ,-1 , 0
  4596.9      .1       0  4600.3     .05       0    4954      .1       0
  5007.1     .07       0  5013.1      .1       0  5125.3     .05       0
Bank Sta=4948.9,5120.7
XS Rating Curve= 0 ,0
Exp/Cntr=0.3,0.1

Type RM Length L Ch R = 1 ,4078    ,584,584,584
BEGIN DESCRIPTION:
KENTUCK CREEK 7.0
END DESCRIPTION:
XS GIS Cut Line= 3
      2242953.16     13204483.78      2242330.84     13204201.56
      2242135.49      13204230.5
#Sta/Elev= 30
  4620.5   268.8  4726.4  269.26  4790.2  267.34  4824.5  264.48  4857.1  260.22
  4864.9  258.23  4933.9   250.6  4955.9  244.88  4962.7  246.13  4968.2  244.19
  4977.8  238.92  4994.5  236.47  4996.8  236.47  4999.5  235.97  5002.8  236.47
  5021.8  238.36    5032  242.06  5054.7  242.77  5066.1  244.41  5076.7  242.63
  5089.2  245.18  5158.4  246.23  5210.1  250.73  5241.4  254.94  5302.4  258.64
  5367.6  260.76  5437.8  261.24  5448.5  262.46  5458.6  261.18  5501.3   261.4
#Mann= 5 ,-1 , 0
  4620.5      .1       0  4824.5     .05       0  4994.5      .1       0
  4996.8     .07       0  5002.8      .1       0
Bank Sta=4968.2,5089.2
XS Rating Curve= 0 ,0
Exp/Cntr=0.3,0.1

Type RM Length L Ch R = 1 ,3494    ,592,592,592
BEGIN DESCRIPTION:
KENTUCK CREEK 6.0
END DESCRIPTION:
XS GIS Cut Line= 3
      2243137.71     13203896.85      2242737.72     13203796.86
       2242137.7     13203746.85
#Sta/Elev= 30
  4587.7   266.5  4628.9  265.19  4711.4  257.65  4762.9  255.09  4793.8  252.32
  4845.4  250.17  4858.3  249.11  4876.3  243.04  4899.5  246.56  4917.5  244.81
  4927.8  241.05  4935.6  241.43  4940.7  243.02  4948.5  240.11  4976.8   234.1
    4982  234.99  4986.7  233.64  4989.4  233.14  4992.7  233.64  5002.5  233.89
    5010  238.15  5020.1   239.4  5030.1  242.95  5100.3  243.58  5160.6  248.17
  5230.8  250.78    5291  251.06  5303.5  250.11  5381.3     251  5602.1  260.71
#Mann= 3 ,-1 , 0
  4587.7      .1       0  4986.7     .07       0  4992.7      .1       0
Bank Sta=4917.5,5030.1
XS Rating Curve= 0 ,0
Exp/Cntr=0.3,0.1

Type RM Length L Ch R = 1 ,2902    ,595,595,595
BEGIN DESCRIPTION:
KENTUCK CREEK 5.0
END DESCRIPTION:
XS GIS Cut Line= 3
      2243187.71     13203446.85      2242837.72     13203246.85
      2242087.67     13203096.85
#Sta/Elev= 30
  4596.9  263.26  4685.4  260.64  4728.6  260.99  4744.5  259.56  4781.2  259.67
  4787.6  258.57  4830.8  257.66    4874   254.5  4889.9  251.85  4905.7  246.11
  4918.1  243.74  4919.4  243.39  4927.3  239.77  4942.4  236.97  4970.5   236.2
  4983.3  233.99  4986.1  233.49  4989.3  233.99  5002.5  234.78  5010.2  238.58
  5030.6  242.75    5051   240.3  5071.9  240.43  5132.6  242.56  5193.8  245.63
  5305.9  254.19  5387.5  258.09  5591.5  259.58  5683.3  262.68  5764.9  267.33
#Mann= 5 ,-1 , 0
  4596.9      .1       0  4918.1     .08       0  4983.3     .07       0
  4989.3     .08       0  5071.9      .1       0
Bank Sta=4919.4,5132.6
XS Rating Curve= 0 ,0
Exp/Cntr=0.3,0.1

Type RM Length L Ch R = 1 ,2307    ,555,555,555
BEGIN DESCRIPTION:
KENTUCK CREEK 4.0
END DESCRIPTION:
XS GIS Cut Line= 3
      2243351.05     13202754.39      2242555.15     13202595.21
      2242236.73     13202725.47
#Sta/Elev= 30
  4476.5  258.07  4589.2  258.99  4632.9  258.31  4734.9  254.15  4742.2  252.72
  4785.8  250.13  4816.4   246.9  4895.1  241.31  4928.6   242.3  4951.2  240.23
  4969.4  235.68  4979.6  235.08  4999.2   230.8    5002   230.3  5005.2   230.8
  5020.4  236.39  5030.6  239.12  5053.2  239.08  5071.4  241.21  5104.2  242.55
  5173.4  249.16  5183.6  249.16  5193.8  250.63  5224.4  252.37  5275.3  253.64
  5339.4  253.41  5463.9  257.32  5609.1  258.34  5630.2  258.87  5632.2  258.87
#Mann= 5 ,-1 , 0
  4476.5      .1       0  4999.2     .07       0  5005.2      .1       0
  5609.1     .05       0  5630.2     .08       0
Bank Sta=4928.6,5071.4
XS Rating Curve= 0 ,0
Exp/Cntr=0.3,0.1

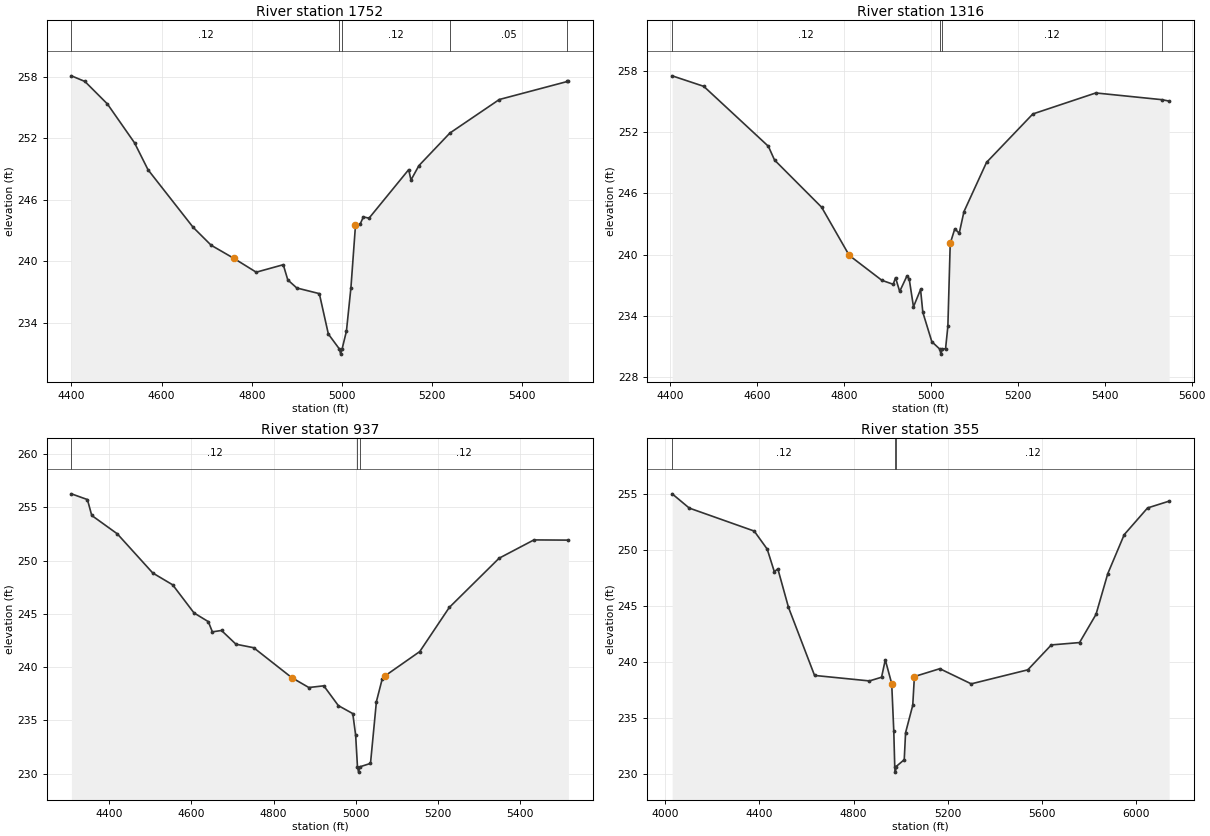
Type RM Length L Ch R = 1 ,1752    ,436,436,436
BEGIN DESCRIPTION:
KENTUCK CREEK 3.0
END DESCRIPTION:
XS GIS Cut Line= 3
      2243437.72     13202096.85      2242837.72     13202096.85
      2242337.71     13202146.86
#Sta/Elev= 30
    4400   258.1    4430  257.55    4480  255.35    4540  251.57    4570  248.94
    4670  243.33    4710  241.58    4760  240.31    4810  238.95    4870  239.68
    4880   238.2    4900  237.41    4950  236.86    4970  232.92  4994.5  231.46
  4997.3  230.96  5000.5  231.46  5010.1   233.2  5020.1  237.45  5030.2  243.53
  5040.2  243.61  5047.7  244.34  5060.3  244.22  5148.2  248.95  5153.3  247.94
  5170.8  249.34  5239.6  252.52  5349.2  255.79  5500.3  257.55  5502.5  257.55
#Mann= 5 ,-1 , 0
    4400     .12       0  4994.5     .07       0  5000.5     .12       0
  5239.6     .05       0  5500.3      .1       0
Bank Sta=4760,5030.2
XS Rating Curve= 0 ,0
Exp/Cntr=0.3,0.1

Type RM Length L Ch R = 1 ,1316    ,379,379,379
BEGIN DESCRIPTION:
Mapping XS cf6884c7
END DESCRIPTION:
XS GIS Cut Line= 3
      2243531.97     13202045.27      2243351.09     13201849.92
      2242520.86     13201568.37
#Sta/Elev= 30
  4405.4  257.54    4478  256.51  4626.6  250.63  4640.8  249.28  4749.1  244.65
  4812.5  239.93  4887.6  237.48  4913.7  237.09    4919  237.74  4928.6  236.39
  4945.1  237.89  4950.4  237.64  4960.3  234.88  4976.6  236.58  4981.8  234.34
  5002.5  231.46  5020.6  230.74  5023.4  230.24  5026.6  230.74  5034.1  230.77
  5039.4  232.98  5044.8   241.1  5055.3  242.53  5065.5   242.1  5076.4  244.22
  5128.3  249.05  5234.8   253.8  5379.6  255.86  5531.7   255.2  5548.3  255.06
#Mann= 4 ,-1 , 0
  4405.4     .12       0  5020.6     .07       0  5026.6     .12       0
  5531.7     .05       0
Bank Sta=4812.5,5044.8
XS Rating Curve= 0 ,0
Exp/Cntr=0.3,0.1

Type RM Length L Ch R = 1 ,937     ,582,582,582
BEGIN DESCRIPTION:
KENTUCK CREEK 2.0
END DESCRIPTION:
XS GIS Cut Line= 3
      2243604.33      13201994.6      2243517.51     13201676.26
      2242837.35      13201119.1
#Sta/Elev= 30
  4308.2  256.28  4347.2  255.74  4357.7  254.25  4419.9  252.52  4506.2  248.84
  4554.6  247.73  4606.5  245.09  4641.3  244.27  4651.2  243.31  4673.4  243.44
  4708.6  242.15  4751.7  241.82  4844.3  239.01  4885.9  238.08  4922.3  238.24
  4957.7  236.38  4992.8  235.63  4999.8  233.59  5004.2  230.63  5006.9  230.13
  5010.2  230.63  5035.9  230.95  5050.3  236.76  5064.5   238.9  5071.1  239.17
  5155.8  241.46  5227.5   245.6  5348.8  250.23  5433.5  251.95  5517.4  251.93
#Mann= 3 ,-1 , 0
  4308.2     .12       0  5004.2     .07       0  5010.2     .12       0
Bank Sta=4844.3,5071.1
XS Rating Curve= 0 ,0
Exp/Cntr=0.3,0.1

Type RM Length L Ch R = 1 ,355     ,0,0,0
BEGIN DESCRIPTION:
KENTUCK CREEK 1.0
END DESCRIPTION:
XS GIS Cut Line= 4
        2243778.     13202009.16      2243835.89     13201430.24
      2243488.57     13200822.44       2242656.5     13200844.14
#Sta/Elev= 30
  4028.6     255  4101.3  253.73  4377.6  251.68  4432.9  250.07  4463.1  248.06
  4478.1  248.31  4523.4  244.88  4634.3  238.81  4867.7  238.32  4919.3  238.65
  4935.2   240.2  4962.5  238.08  4971.3  233.86  4975.4  230.69  4978.1  230.19
  4981.4  230.69  5015.8   231.3  5021.5  233.71    5052  236.15    5059  238.71
  5167.1  239.41  5300.8  238.06  5541.4  239.31  5641.4  241.53  5761.5  241.74
  5831.5  244.25  5881.5  247.88  5951.5  251.36  6050.8  253.74  6142.8  254.35
#Mann= 3 ,-1 , 0
  4028.6     .12       0  4975.4     .07       0  4981.4     .12       0
Bank Sta=4962.5,5059
XS Rating Curve= 0 ,0
Exp/Cntr=0.3,0.1

Chan Stop Cuts=-1
Use User Specified Reach Order=0
Composite Channel Slope=5