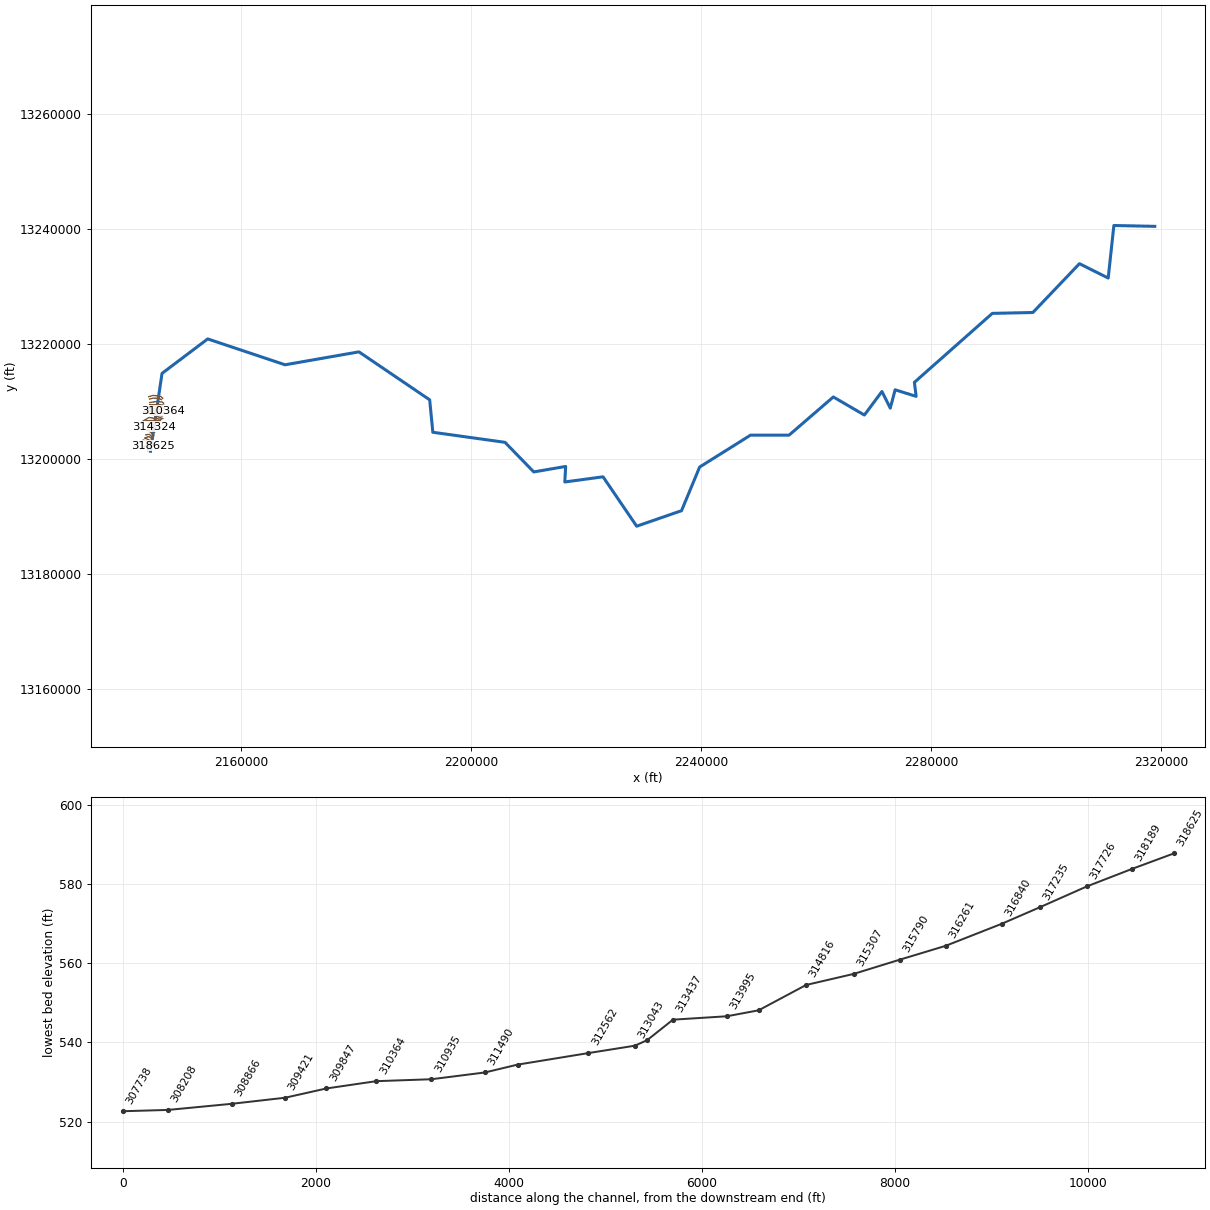
--- LAGARTO CREEK.prj (project) ---

Proj Title=LAGARTO CREEK Base Level Engineering
Current Plan=p01
Default Exp/Contr=0.3,0.1
English Units
Geom File=g01
Flow File=f01
Plan File=p01
Y Axis Title=Elevation
X Axis Title(PF)=Main Channel Distance
X Axis Title(XS)=Station
BEGIN DESCRIPTION:
LAGARTO CREEK
END DESCRIPTION:
DSS Export Rating Curves= 0
DSS Export Rating Curve Sorted= 0
DSS Export Volume Flow Curves= 0
DXF OffsetX= 0
DXF OffsetY= 0
DXF ScaleX= 1
DXF ScaleY= 10

--- LAGARTO CREEK.p01 (plan) ---

Plan Title=Multiple Run
Short Identifier=Multiple
Geom File=g01
Flow File=f01
Subcritical Flow
K Sum by GR= 0
Std Step Tol= 0.01
Critical Tol= 0.01
Num of Std Step Trials= 20
Max Error Tol= 0.3
Flow Tol Ratio= 0.001
Split Flow NTrial= 30
Split Flow Tol= 0.02
Split Flow Ratio= 0.02
Log Output Level= 0
Friction Slope Method= 1
Unsteady Friction Slope Method= 2
Unsteady Bridges Friction Slope Method= 1
Parabolic Critical Depth
Global Vel Dist=  1 , 1 , 1
Global Log Level= 0
CheckData=True
Encroach Param= -1, 0, 0, 0
BEGIN DESCRIPTION:
Multiple Run
END DESCRIPTION:

--- LAGARTO CREEK.f01 (steady flow) ---

Flow Title=Multiple
Program Version=4.10
Number of Profiles= 7
Profile Names=10-year,25-year,50-year,1pct_min,100-year,1pct_plu,500-year
River Rch & RM=LAGARTO CREEK,Reach-1         ,318625
     169     235     289     263     356     481     545
River Rch & RM=LAGARTO CREEK,Reach-1         ,313170
     297     426     536     496     671     907    1070
River Rch & RM=LAGARTO CREEK,Reach-1         ,311827
     496     723     920     858    1161    1569    1881
River Rch & RM=LAGARTO CREEK,Reach-1         ,310364
     496     723     920     858    1161    1569    1881
River Rch & RM=LAGARTO CREEK,Reach-1         ,300616
     517     754     959     895    1210    1636    1961
River Rch & RM=LAGARTO CREEK,Reach-1         ,297097
     648     951    1215    1138    1539    2081    2512
River Rch & RM=LAGARTO CREEK,Reach-1         ,288858
     678     995    1271    1191    1610    2178    2629
River Rch & RM=LAGARTO CREEK,Reach-1         ,287858
     914    1356    1745    1645    2224    3008    3678
River Rch & RM=LAGARTO CREEK,Reach-1         ,284733
     914    1356    1745    1645    2224    3008    3678
River Rch & RM=LAGARTO CREEK,Reach-1         ,283228
     914    1356    1745    1645    2224    3008    3678
River Rch & RM=LAGARTO CREEK,Reach-1         ,278984
     914    1356    1745    1645    2224    3008    3678
River Rch & RM=LAGARTO CREEK,Reach-1         ,277252
     955    1417    1824    1719    2325    3145    3845
River Rch & RM=LAGARTO CREEK,Reach-1         ,273632
    1109    1653    2133    2014    2724    3684    4522
River Rch & RM=LAGARTO CREEK,Reach-1         ,272759
    1109    1653    2133    2014    2724    3684    4522
River Rch & RM=LAGARTO CREEK,Reach-1         ,268291
    1724    2601    3387    3225    4362    5899    7359
River Rch & RM=LAGARTO CREEK,Reach-1         ,265367
    1724    2601    3387    3225    4362    5899    7359
River Rch & RM=LAGARTO CREEK,Reach-1         ,262254
    1728    2602    3384    3218    4351    5885    7320
River Rch & RM=LAGARTO CREEK,Reach-1         ,259889
    1853    2795    3638    3463    4684    6334    7894
River Rch & RM=LAGARTO CREEK,Reach-1         ,256049
    1853    2795    3638    3463    4684    6334    7894
River Rch & RM=LAGARTO CREEK,Reach-1         ,255421
    1865    2811    3659    3481    4707    6366    7926
River Rch & RM=LAGARTO CREEK,Reach-1         ,250524
    1867    2814    3661    3482    4709    6369    7924
River Rch & RM=LAGARTO CREEK,Reach-1         ,247889
    1928    2903    3775    3589    4853    6564    8157
River Rch & RM=LAGARTO CREEK,Reach-1         ,242213
    1937    2916    3790    3601    4870    6587    8178
River Rch & RM=LAGARTO CREEK,Reach-1         ,237765
    2362    3569    4653    4433    5995    8107   10115
River Rch & RM=LAGARTO CREEK,Reach-1         ,237086
    2629    3982    5201    4963    6712    9077   11360
River Rch & RM=LAGARTO CREEK,Reach-1         ,235589
    2629    3982    5201    4963    6712    9077   11360
River Rch & RM=LAGARTO CREEK,Reach-1         ,232895
    2682    4061    5303    5060    6842    9254   11577
River Rch & RM=LAGARTO CREEK,Reach-1         ,231816
    2682    4061    5303    5060    6842    9254   11577
River Rch & RM=LAGARTO CREEK,Reach-1         ,228794
    2845    4313    5637    5382    7279    9843   12332
River Rch & RM=LAGARTO CREEK,Reach-1         ,225694
    2790    4216    5496    5235    7079    9574   11933
River Rch & RM=LAGARTO CREEK,Reach-1         ,225036
    2790    4216    5496    5235    7079    9574   11933
River Rch & RM=LAGARTO CREEK,Reach-1         ,214513
    2944    4452    5808    5535    7486   10123   12631
River Rch & RM=LAGARTO CREEK,Reach-1         ,213181
    2944    4452    5808    5535    7486   10123   12631
River Rch & RM=LAGARTO CREEK,Reach-1         ,210646
    2947    4454    5809    5534    7484   10121   12620
River Rch & RM=LAGARTO CREEK,Reach-1         ,210089
    3073    4644    6058    5772    7806   10556   13164
River Rch & RM=LAGARTO CREEK,Reach-1         ,209566
    3073    4644    6058    5772    7806   10556   13164
River Rch & RM=LAGARTO CREEK,Reach-1         ,206798
    3067    4632    6038    5750    7776   10516   13099
River Rch & RM=LAGARTO CREEK,Reach-1         ,200244
    3060    4615    6010    5716    7730   10455   12992
River Rch & RM=LAGARTO CREEK,Reach-1         ,199117
    3130    4717    6141    5838    7896   10678   13258
River Rch & RM=LAGARTO CREEK,Reach-1         ,195953
    3130    4717    6141    5838    7896   10678   13258
River Rch & RM=LAGARTO CREEK,Reach-1         ,189103
    3130    4717    6141    5838    7896   10678   13258
River Rch & RM=LAGARTO CREEK,Reach-1         ,183146
    3120    4699    6114    5809    7856   10624   13176
River Rch & RM=LAGARTO CREEK,Reach-1         ,180569
    3152    4747    6177    5870    7938   10736   13317
River Rch & RM=LAGARTO CREEK,Reach-1         ,177048
    3155    4748    6175    5865    7932   10727   13291
River Rch & RM=LAGARTO CREEK,Reach-1         ,170472
    3778    5705    7439    7081    9576   12950   16111
River Rch & RM=LAGARTO CREEK,Reach-1         ,169216
    3768    5682    7403    7041    9522   12878   15993
River Rch & RM=LAGARTO CREEK,Reach-1         ,167653
    3795    5727    7465    7103    9606   12990   16147
River Rch & RM=LAGARTO CREEK,Reach-1         ,165701
    3794    5721    7452    7087    9584   12961   16090
River Rch & RM=LAGARTO CREEK,Reach-1         ,161961
    3842    5795    7551    7182    9713   13136   16316
River Rch & RM=LAGARTO CREEK,Reach-1         ,159967
    3853    5807    7562    7189    9723   13149   16314
River Rch & RM=LAGARTO CREEK,Reach-1         ,159072
    3853    5807    7562    7189    9723   13149   16314
River Rch & RM=LAGARTO CREEK,Reach-1         ,154185
    3831    5766    7503    7126    9638   13034   16141
River Rch & RM=LAGARTO CREEK,Reach-1         ,146446
    3873    5827    7580    7197    9733   13163   16290
River Rch & RM=LAGARTO CREEK,Reach-1         ,142593
    4154    6252    8135    7726   10449   14130   17493
River Rch & RM=LAGARTO CREEK,Reach-1         ,136215
    4172    6272    8156    7741   10468   14157   17501
River Rch & RM=LAGARTO CREEK,Reach-1         ,135833
    4172    6272    8156    7741   10468   14157   17501
River Rch & RM=LAGARTO CREEK,Reach-1         ,130961
    4172    6272    8156    7741   10468   14157   17501
River Rch & RM=LAGARTO CREEK,Reach-1         ,130253
    4202    6317    8215    7797   10545   14260   17629
River Rch & RM=LAGARTO CREEK,Reach-1         ,128067
    4202    6317    8215    7797   10545   14260   17629
River Rch & RM=LAGARTO CREEK,Reach-1         ,125103
    4197    6300    8185    7760   10494   14192   17506
River Rch & RM=LAGARTO CREEK,Reach-1         ,118862
    4301    6462    8401    7970   10779   14577   18006
River Rch & RM=LAGARTO CREEK,Reach-1         ,118340
    4301    6462    8401    7970   10779   14577   18006
River Rch & RM=LAGARTO CREEK,Reach-1         ,117620
    4285    6435    8362    7931   10726   14505   17904
River Rch & RM=LAGARTO CREEK,Reach-1         ,113575
    4430    6651    8641    8194   11081   14986   18487
River Rch & RM=LAGARTO CREEK,Reach-1         ,111581
    4475    6719    8730    8279   11196   15141   15141
River Rch & RM=LAGARTO CREEK,Reach-1         ,103213
    4482    6728    8741    8288   11208   15158   18697
River Rch & RM=LAGARTO CREEK,Reach-1         ,102203
    4493    6735    8742    8281   11200   15146   18646
River Rch & RM=LAGARTO CREEK,Reach-1         ,93999
    4507    6758    8772    8310   11238   15198   18711
River Rch & RM=LAGARTO CREEK,Reach-1         ,90177
    4576    6859    8902    8432   11403   15421   18979
River Rch & RM=LAGARTO CREEK,Reach-1         ,81329
    4597    6887    8936    8461   11443   15475   19033
River Rch & RM=LAGARTO CREEK,Reach-1         ,78025
    4629    6931    8991    8511   11510   15566   19132
River Rch & RM=LAGARTO CREEK,Reach-1         ,71741
    4612    6902    8949    8467   11450   15485   19013
River Rch & RM=LAGARTO CREEK,Reach-1         ,67304
    4639    6941    8997    8510   11509   15565   19103
River Rch & RM=LAGARTO CREEK,Reach-1         ,60284
    4702    7036    9122    8631   11672   15785   19381
River Rch & RM=LAGARTO CREEK,Reach-1         ,58671
    4702    7036    9122    8631   11672   15785   19381
River Rch & RM=LAGARTO CREEK,Reach-1         ,57855
    4707    7037    9119    8623   11662   15771   19341
River Rch & RM=LAGARTO CREEK,Reach-1         ,55215
    4769    7130    9238    8734   11812   15974   19583
River Rch & RM=LAGARTO CREEK,Reach-1         ,53189
    4769    7130    9238    8734   11812   15974   19583
River Rch & RM=LAGARTO CREEK,Reach-1         ,47691
    4818    7207    9344    8839   11953   16166   19838
River Rch & RM=LAGARTO CREEK,Reach-1         ,47203
    4944    7395    9584    9062   12255   16573   20315
River Rch & RM=LAGARTO CREEK,Reach-1         ,39931
    4944    7395    9584    9062   12255   16573   20315
River Rch & RM=LAGARTO CREEK,Reach-1         ,37089
    4960    7421    9620    9097   12303   16639   20404
River Rch & RM=LAGARTO CREEK,Reach-1         ,35557
    5016    7508    9736    9210   12456   16845   20668
River Rch & RM=LAGARTO CREEK,Reach-1         ,33843
    5016    7508    9736    9210   12456   16845   20668
River Rch & RM=LAGARTO CREEK,Reach-1         ,33040
    5043    7547    9786    9256   12518   16929   20765
River Rch & RM=LAGARTO CREEK,Reach-1         ,31393
    5043    7547    9786    9256   12518   16929   20765
River Rch & RM=LAGARTO CREEK,Reach-1         ,29976
    5054    7559    9798    9264   12529   16944   20765
River Rch & RM=LAGARTO CREEK,Reach-1         ,25270
    5039    7532    9758    9221   12470   16864   20645
River Rch & RM=LAGARTO CREEK,Reach-1         ,18954
    5031    7519    9740    9203   12446   16831   20599
River Rch & RM=LAGARTO CREEK,Reach-1         ,18615
    5153    7696    9966    9410   12726   17211   21033
River Rch & RM=LAGARTO CREEK,Reach-1         ,17823
    5153    7696    9966    9410   12726   17211   21033
Boundary for River Rch & Prof#=LAGARTO CREEK,Reach-1         , 1
Up Type= 0
Dn Type= 3
Dn Slope=0.00006
Boundary for River Rch & Prof#=LAGARTO CREEK,Reach-1         , 2
Up Type= 0
Dn Type= 3
Dn Slope=0.00006
Boundary for River Rch & Prof#=LAGARTO CREEK,Reach-1         , 3
Up Type= 0
Dn Type= 3
Dn Slope=0.00006
Boundary for River Rch & Prof#=LAGARTO CREEK,Reach-1         , 4
Up Type= 0
Dn Type= 3
Dn Slope=0.00006
Boundary for River Rch & Prof#=LAGARTO CREEK,Reach-1         , 5
Up Type= 0
Dn Type= 3
Dn Slope=0.00006
Boundary for River Rch & Prof#=LAGARTO CREEK,Reach-1         , 6
Up Type= 0
Dn Type= 3
Dn Slope=0.00006
Boundary for River Rch & Prof#=LAGARTO CREEK,Reach-1         , 7
Up Type= 0
Dn Type= 3
Dn Slope=0.00006
DSS Import GetInterval= 0
DSS Import GetPeak= 0
DSS Import FillOption= 0

--- LAGARTO CREEK.g01 (geometry) ---

Geom Title=Existing Conditions
Program Version=4.10

River Reach=LAGARTO CREEK   ,Reach-1
Reach XY= 30
      2144237.72     13201346.86      2146237.72     13214896.85
      2154187.72     13220896.85      2167637.72     13216396.85
      2180487.72     13218646.85      2192787.72     13210296.85
      2193337.72     13204646.85      2205887.72     13202896.85
      2210887.72     13197746.86      2216437.72     13198696.86
      2216287.72     13195996.85      2222937.72     13196896.86
      2228787.72     13188296.85      2236587.72     13190996.86
      2239737.72     13198596.85      2248587.72     13204146.86
      2255287.72     13204146.86      2262987.72     13210796.85
      2268387.72     13207646.85      2271437.72     13211746.85
      2272887.72     13208846.85      2273737.72     13212046.85
      2277387.72     13210896.85      2277087.72     13213346.85
      2290637.72     13225346.85      2297687.72     13225496.85
      2305787.72     13233996.86      2310787.72     13231496.85
      2311777.87       13240642.      2318887.72     13240496.85

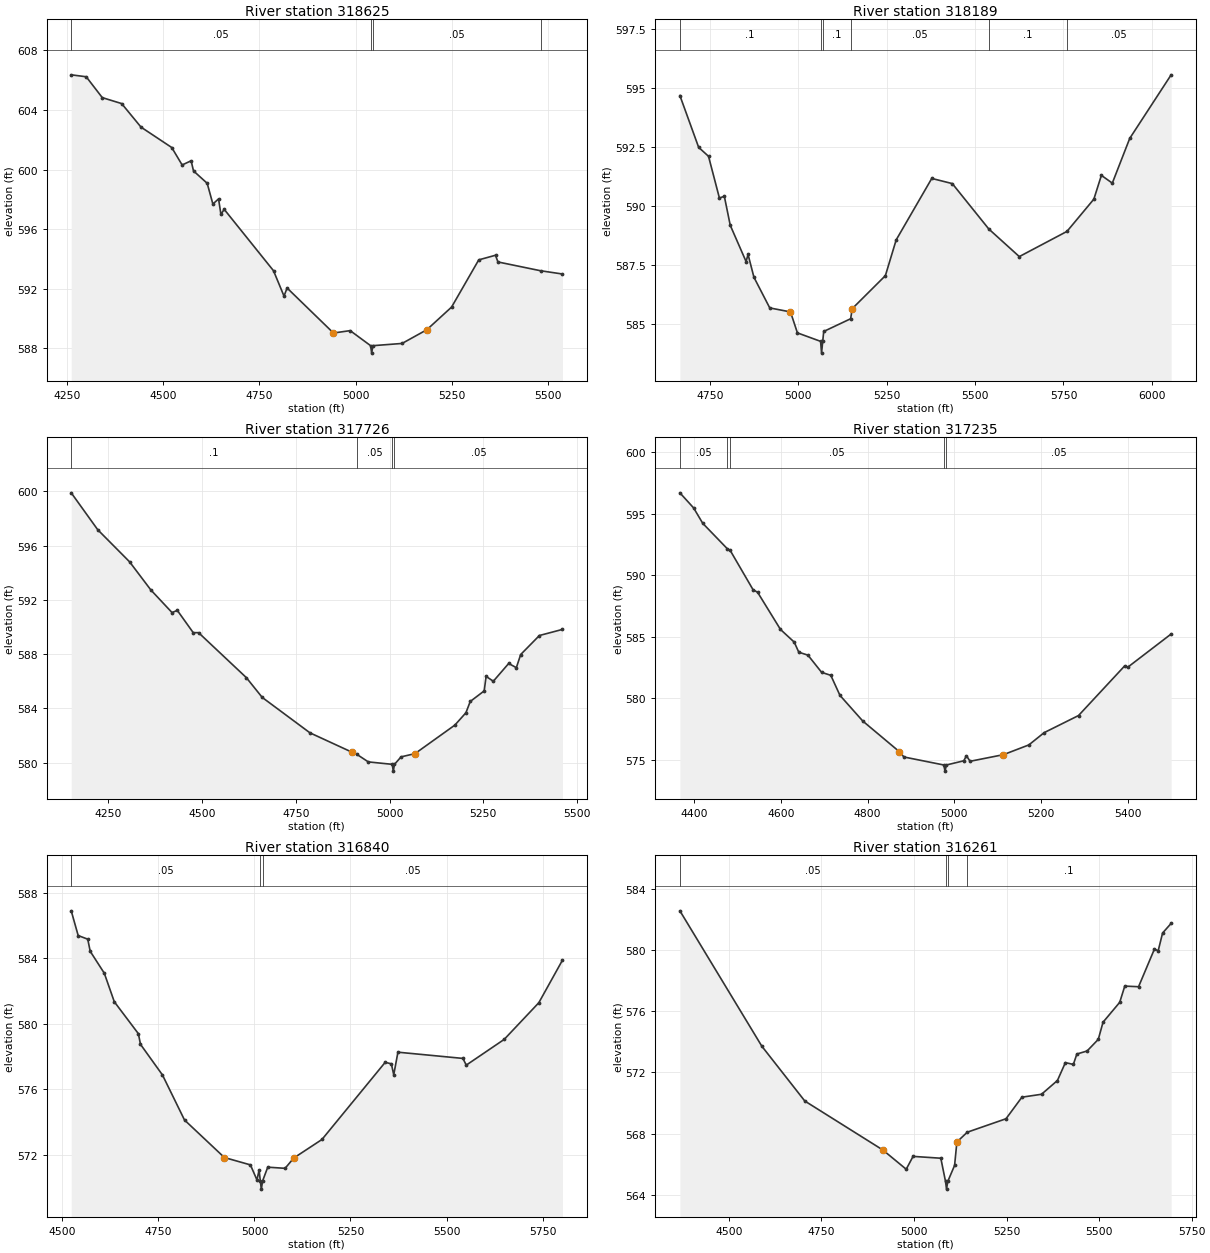
Type RM Length L Ch R = 1 ,318625  ,436,436,436
BEGIN DESCRIPTION:
LAGARTO CREEK 339.0
END DESCRIPTION:
XS GIS Cut Line= 3
      2143688.62     13201462.22      2143960.09     13201844.18
      2144603.36     13202336.09
#Sta/Elev= 30
  4260.1  606.36  4299.1  606.23  4340.9  604.83  4391.3  604.43  4441.7  602.85
  4521.7  601.48  4548.7  600.31  4572.1  600.59  4578.3  599.91  4613.9  599.08
  4628.7  597.69  4643.5  598.03  4649.6     597  4658.2  597.33  4786.5  593.21
  4813.8  591.51  4821.9  592.05  4942.5  589.03    4986  589.19  5039.2  588.18
  5041.9  587.68  5045.2  588.18  5121.1  588.33  5185.5  589.25  5249.9  590.77
  5320.6  593.94  5364.2  594.25  5370.5   593.8  5481.4  593.21  5538.5  592.99
#Mann= 4 ,-1 , 0
  4260.1     .05       0  5039.2     .03       0  5045.2     .05       0
  5481.4      .1       0
Bank Sta=4942.5,5185.5
XS Rating Curve= 0 ,0
Exp/Cntr=0.3,0.1

Type RM Length L Ch R = 1 ,318189  ,463,463,463
BEGIN DESCRIPTION:
LAGARTO CREEK 337.0
END DESCRIPTION:
XS GIS Cut Line= 3
      2143687.72     13201946.86      2143837.72     13202246.85
      2144737.76     13202796.88
#Sta/Elev= 30
  4664.6  594.69  4717.7  592.49  4745.6  592.11  4776.4  590.34  4790.4  590.41
  4807.1  589.18  4851.9  587.64  4857.5  587.94  4874.2  586.97  4918.9  585.67
  4977.6   585.5  4997.2  584.61  5062.8  584.25  5065.5  583.75  5068.8  584.25
  5071.6  584.67  5147.8  585.21  5152.4  585.64  5246.1  587.04  5276.7  588.56
  5377.4  591.17  5435.5  590.95  5538.9  589.02  5625.1  587.85    5760  588.92
  5836.1  590.29  5857.4   591.3  5888.3  590.97  5937.6  592.87  6054.8  595.57
#Mann= 6 ,-1 , 0
  4664.6      .1       0  5062.8     .07       0  5068.8      .1       0
  5147.8     .05       0  5538.9      .1       0    5760     .05       0
Bank Sta=4977.6,5152.4
XS Rating Curve= 0 ,0
Exp/Cntr=0.3,0.1

Type RM Length L Ch R = 1 ,317726  ,491,491,491
BEGIN DESCRIPTION:
LAGARTO CREEK 336.0
END DESCRIPTION:
XS GIS Cut Line= 3
      2143087.74     13202046.88      2143687.72     13202646.86
      2144137.74     13202546.85
#Sta/Elev= 30
  4151.5  599.88  4222.2  597.16    4307   594.8  4363.6  592.73  4420.2  591.06
  4434.3  591.22  4476.7  589.58  4490.9  589.58  4618.2  586.27  4660.6  584.81
  4787.9   582.2    4901  580.76  4912.1  580.63  4943.4  580.06  5007.2  579.88
    5010  579.38  5013.2  579.88  5030.7  580.43  5067.9  580.67  5174.1  582.77
  5203.6  583.68  5215.1  584.51  5252.3  585.29  5257.4  586.36  5276.6     586
  5317.6  587.31    5338     587  5349.6  587.97  5399.5  589.37    5461  589.82
#Mann= 4 ,-1 , 0
  4151.5      .1       0  4912.1     .05       0  5007.2     .03       0
  5013.2     .05       0
Bank Sta=4901,5067.9
XS Rating Curve= 0 ,0
Exp/Cntr=0.3,0.1

Type RM Length L Ch R = 1 ,317235  ,395,395,395
BEGIN DESCRIPTION:
LAGARTO CREEK 335.0
END DESCRIPTION:
XS GIS Cut Line= 3
      2142987.68     13203296.87      2143587.72     13203096.85
      2143987.72     13202796.85
#Sta/Elev= 30
  4367.5  596.71  4399.2  595.48  4420.2  594.23  4477.2  592.15  4483.4  592.03
  4536.2  588.83  4546.7  588.62  4599.4   585.6  4631.1  584.57  4641.6  583.75
  4662.7  583.51  4694.3  582.11  4715.4  581.87  4736.5  580.24  4789.2  578.15
  4873.5  575.66    4884  575.23  4975.9  574.58  4978.7  574.08  4981.9  574.58
  5021.9  574.92  5028.1  575.33  5036.5  574.88  5113.5  575.42  5171.9  576.21
  5207.3  577.21  5286.5   578.6  5392.7  582.63    5400  582.53    5500  585.23
#Mann= 5 ,-1 , 0
  4367.5     .05       0  4477.2      .1       0  4483.4     .05       0
  4975.9     .03       0  4981.9     .05       0
Bank Sta=4873.5,5113.5
XS Rating Curve= 0 ,0
Exp/Cntr=0.3,0.1

Type RM Length L Ch R = 1 ,316840  ,579,579,579
BEGIN DESCRIPTION:
LAGARTO CREEK 334.0
END DESCRIPTION:
XS GIS Cut Line= 3
      2143247.02     13203618.17      2143552.58     13203514.01
       2144413.2     13203097.58
#Sta/Elev= 30
    4523   586.9  4541.1  585.39    4566  585.17  4572.4  584.43  4609.1  583.09
  4635.1  581.35  4697.8   579.4  4703.3  578.75  4760.5  576.88  4817.9  574.13
  4921.7  571.84  4989.5  571.39  5006.5  570.47  5012.1  571.08  5015.2  570.41
  5017.9  569.91  5021.2  570.41  5034.6  571.25  5079.8  571.18  5102.4  571.81
  5175.7  572.94  5340.3  577.65  5356.4  577.56  5362.6  576.89  5373.5  578.27
  5542.7  577.89  5551.4  577.48  5650.1  579.05  5740.3  581.29  5801.9  583.89
#Mann= 3 ,-1 , 0
    4523     .05       0  5015.2     .03       0  5021.2     .05       0
Bank Sta=4921.7,5102.4
XS Rating Curve= 0 ,0
Exp/Cntr=0.3,0.1

Type RM Length L Ch R = 1 ,316261  ,471,471,471
BEGIN DESCRIPTION:
LAGARTO CREEK 333.0
END DESCRIPTION:
XS GIS Cut Line= 3
      2143337.68     13203696.84      2143937.72     13203896.85
       2144537.7     13203546.87
#Sta/Elev= 30
  4367.5  582.56  4588.9  573.71  4704.9  570.13  4915.7  566.93  4978.9  565.67
  4997.4  566.51  5072.4  566.39  5085.1  564.87  5087.8  564.37  5091.1  564.87
  5109.6  565.92  5115.8  567.45  5143.8  568.09  5248.5  568.97  5291.5  570.38
  5344.4  570.57  5387.4  571.47  5408.9  572.64  5430.4  572.52  5439.9   573.2
  5467.6   573.4  5497.8  574.16  5510.6  575.28  5555.7  576.58  5569.3  577.64
  5606.6   577.6  5649.6  580.07  5659.5  579.94  5671.5  581.11  5694.6  581.74
#Mann= 4 ,-1 , 0
  4367.5     .05       0  5085.1     .03       0  5091.1     .05       0
  5143.8      .1       0
Bank Sta=4915.7,5115.8
XS Rating Curve= 0 ,0
Exp/Cntr=0.3,0.1

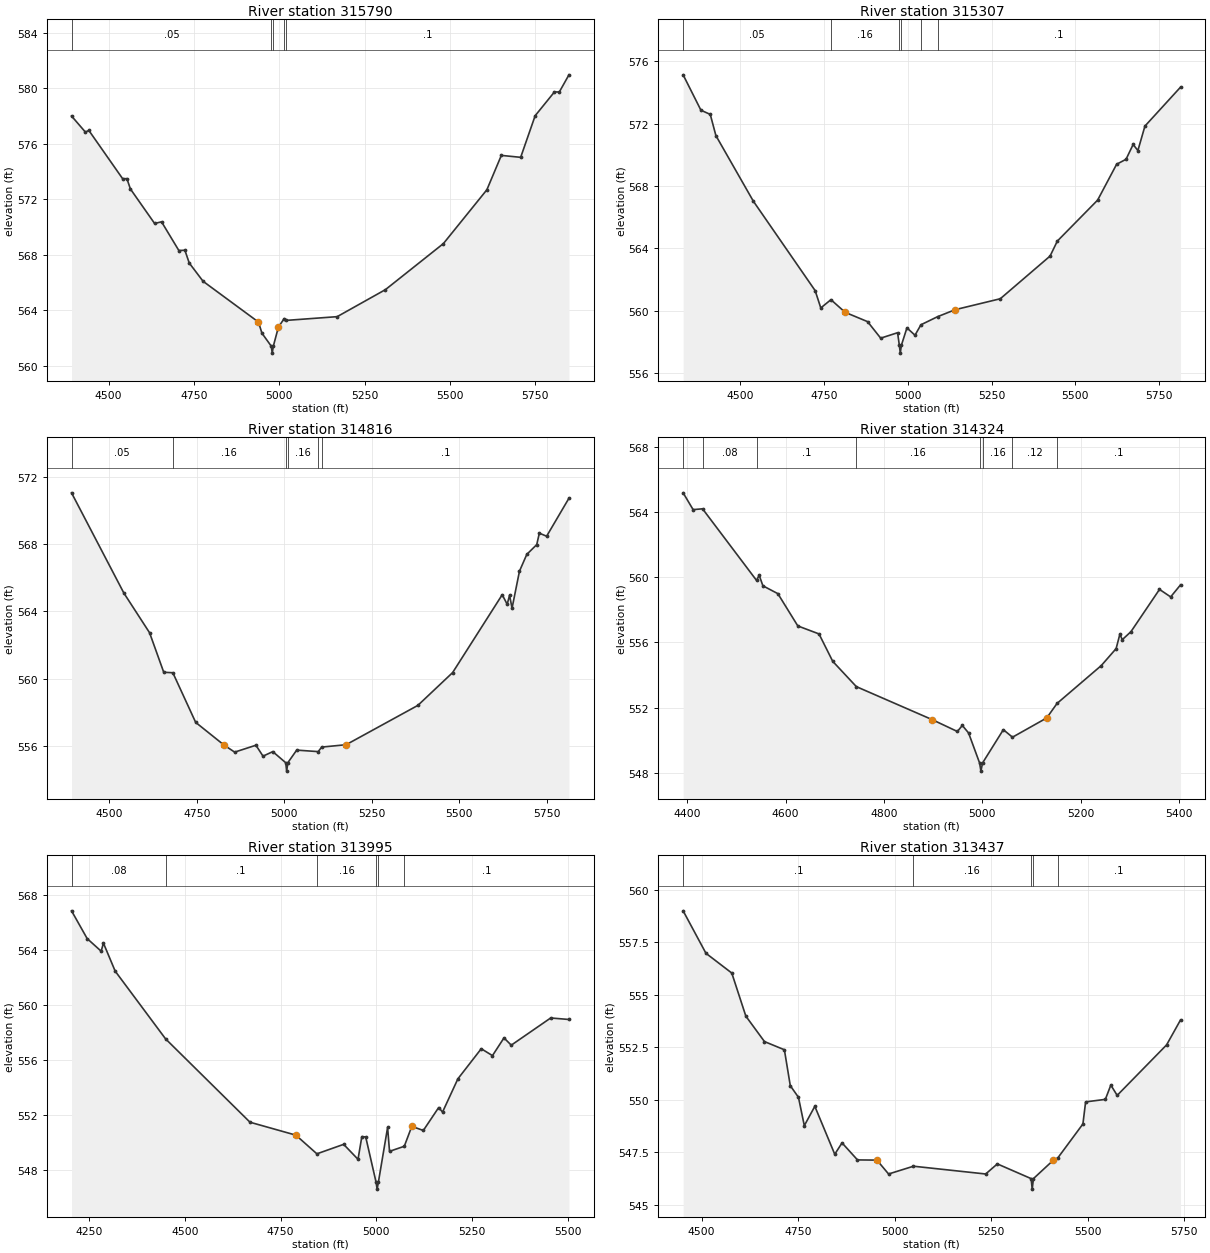
Type RM Length L Ch R = 1 ,315790  ,483,483,483
BEGIN DESCRIPTION:
LAGARTO CREEK 332.0
END DESCRIPTION:
XS GIS Cut Line= 3
       2143437.7     13204196.85      2144037.72     13204296.86
       2144637.7     13203696.87
#Sta/Elev= 30
  4391.7  578.01  4432.3  576.85  4442.4  576.97  4541.3  573.49  4553.9  573.49
  4564.1  572.75    4635  570.26  4655.3  570.38    4706  568.31  4723.7  568.33
  4736.4  567.41    4777  566.09  4939.2  563.15  4949.3  562.35  4976.7  561.41
  4979.5  560.91  4982.7  561.41  4997.5  562.78  5014.4   563.4  5020.2  563.27
  5169.7  563.54  5311.1  565.49  5480.8  568.81  5608.1  572.69  5650.5  575.17
  5707.1  575.03  5749.5  578.03  5806.1  579.75  5820.2  579.74  5848.5  580.98
#Mann= 5 ,-1 , 0
  4391.7     .05       0  4976.7     .04       0  4982.7     .05       0
  5014.4     .12       0  5020.2      .1       0
Bank Sta=4939.2,4997.5
XS Rating Curve= 0 ,0
Exp/Cntr=0.3,0.1

Type RM Length L Ch R = 1 ,315307  ,491,491,491
BEGIN DESCRIPTION:
LAGARTO CREEK 331.0
END DESCRIPTION:
XS GIS Cut Line= 3
      2143637.74     13204996.85      2144237.72     13204696.85
      2144787.69     13204096.89
#Sta/Elev= 30
  4329.2  575.14  4382.3  572.87  4410.2   572.6    4427  571.24  4538.8  567.03
  4723.3  561.29  4740.1  560.18  4770.4  560.71  4812.7   559.9  4879.8   559.3
  4918.9  558.24  4969.3  558.59  4974.6  557.78  4977.4  557.28  4980.6  557.78
  4997.2   558.9  5021.3  558.43    5039   559.1  5088.8  559.62  5141.5  560.07
  5275.9  560.77  5424.5  563.51  5446.1  564.47  5566.4   567.1  5623.1   569.4
  5651.2  569.72  5672.4  570.67  5686.6  570.28  5707.6  571.85  5813.9  574.35
#Mann= 6 ,-1 , 0
  4329.2     .05       0  4770.4     .16       0  4974.6     .07       0
  4980.6     .16       0    5039     .12       0  5088.8      .1       0
Bank Sta=4812.7,5141.5
XS Rating Curve= 0 ,0
Exp/Cntr=0.3,0.1

Type RM Length L Ch R = 1 ,314816  ,492,492,492
BEGIN DESCRIPTION:
LAGARTO CREEK 330.0
END DESCRIPTION:
XS GIS Cut Line= 3
       2143737.7     13205046.85      2144337.72     13205146.85
      2144937.69     13204596.88
#Sta/Elev= 30
  4391.7  571.05  4541.3  565.09  4614.8  562.73  4655.3  560.38  4681.4  560.35
  4746.6   557.4  4827.7  556.05  4858.1  555.63  4918.9  556.04  4939.2  555.39
  4967.1  555.66  5004.1     555  5006.8   554.5  5010.1     555  5035.5  555.75
  5096.9  555.66    5107  555.93  5176.7  556.07    5382  558.41  5481.3  560.36
  5623.1  564.99  5637.3  564.42  5644.1  564.96  5651.2  564.19  5672.4  566.39
  5693.4  567.39  5721.8  567.97  5729.2  568.65  5750.1  568.47  5813.9  570.73
#Mann= 6 ,-1 , 0
  4391.7     .05       0  4681.4     .16       0  5004.1     .07       0
  5010.1     .16       0  5096.9     .12       0    5107      .1       0
Bank Sta=4827.7,5176.7
XS Rating Curve= 0 ,0
Exp/Cntr=0.3,0.1

Type RM Length L Ch R = 1 ,314324  ,329,329,329
BEGIN DESCRIPTION:
LAGARTO CREEK 329.0
END DESCRIPTION:
XS GIS Cut Line= 3
       2143837.7     13205496.85      2144437.72     13205596.86
      2144837.71     13205646.85
#Sta/Elev= 30
  4391.7  565.17    4412  564.14  4431.2  564.19    4541   559.8  4546.3  560.12
  4553.9  559.47  4584.3  558.99  4624.9  557.01    4668  556.52  4695.9  554.84
  4743.9  553.29  4898.6  551.26  4949.3  550.54  4959.4  550.91  4972.1  550.45
  4994.5  548.61  4997.2  548.11  5000.5  548.61  5042.8  550.65  5061.4  550.19
    5131  551.37    5152  552.26  5241.9  554.58  5272.1  555.62  5279.7   556.5
  5284.7  556.17  5302.3  556.66  5360.3  559.25    5383  558.79  5403.1  559.53
#Mann= 8 ,-1 , 0
  4391.7      .1       0  4431.2     .08       0    4541      .1       0
  4743.9     .16       0  4994.5     .07       0  5000.5     .16       0
  5061.4     .12       0    5152      .1       0
Bank Sta=4898.6,5131
XS Rating Curve= 0 ,0
Exp/Cntr=0.3,0.1

Type RM Length L Ch R = 1 ,313995  ,558,558,558
BEGIN DESCRIPTION:
Mapping XS 7e5d7c49
END DESCRIPTION:
XS GIS Cut Line= 4
      2143768.12     13205770.22      2144032.85     13205935.14
       2144857.5     13205865.69      2144896.27     13205710.63
#Sta/Elev= 30
  4203.8  566.87  4244.6  564.85  4281.2  563.93  4287.1  564.52  4317.8  562.48
  4449.4  557.55    4670  551.48  4789.8  550.54  4844.7  549.18  4914.6  549.87
  4952.1  548.78  4962.1  550.43  4972.2  550.41  4999.3  547.11    5002  546.61
  5005.3  547.11  5029.4   551.1  5034.4  549.36    5073  549.73  5092.6  551.18
  5122.7  550.88  5162.8  552.55  5172.9  552.22    5213  554.64    5274  556.83
  5303.3  556.33  5333.4  557.62  5352.4  557.09  5455.4  559.07  5503.1  558.96
#Mann= 6 ,-1 , 0
  4203.8     .08       0  4449.4      .1       0  4844.7     .16       0
  4999.3     .07       0  5005.3     .16       0    5073      .1       0
Bank Sta=4789.8,5092.6
XS Rating Curve= 0 ,0
Exp/Cntr=0.3,0.1

Type RM Length L Ch R = 1 ,313437  ,267,267,267
BEGIN DESCRIPTION:
LAGARTO CREEK 328.0
END DESCRIPTION:
XS GIS Cut Line= 4
       2143820.2     13206121.78      2144163.11     13206340.43
      2144788.06     13206273.68      2144840.14     13206026.29
#Sta/Elev= 30
  4452.1  558.99  4511.2  556.97  4578.1  556.03  4614.5  553.98  4662.7  552.77
  4714.3  552.38  4729.6  550.67  4750.7  550.12  4765.9  548.77  4793.1  549.69
  4844.7  547.41  4863.6  547.95  4903.6  547.14  4953.9  547.13  4984.1  546.47
  5048.6  546.84  5235.5  546.47  5265.7  546.95  5353.2  546.25    5356  545.75
  5359.2  546.25  5410.9  547.13  5422.5  547.24  5487.3  548.85  5494.3   549.9
  5545.4  550.02  5559.6   550.7    5576  550.21  5703.9  552.61  5740.1   553.8
#Mann= 5 ,-1 , 0
  4452.1      .1       0  5048.6     .16       0  5353.2     .07       0
  5359.2     .16       0  5422.5      .1       0
Bank Sta=4953.9,5410.9
XS Rating Curve= 0 ,0
Exp/Cntr=0.3,0.1

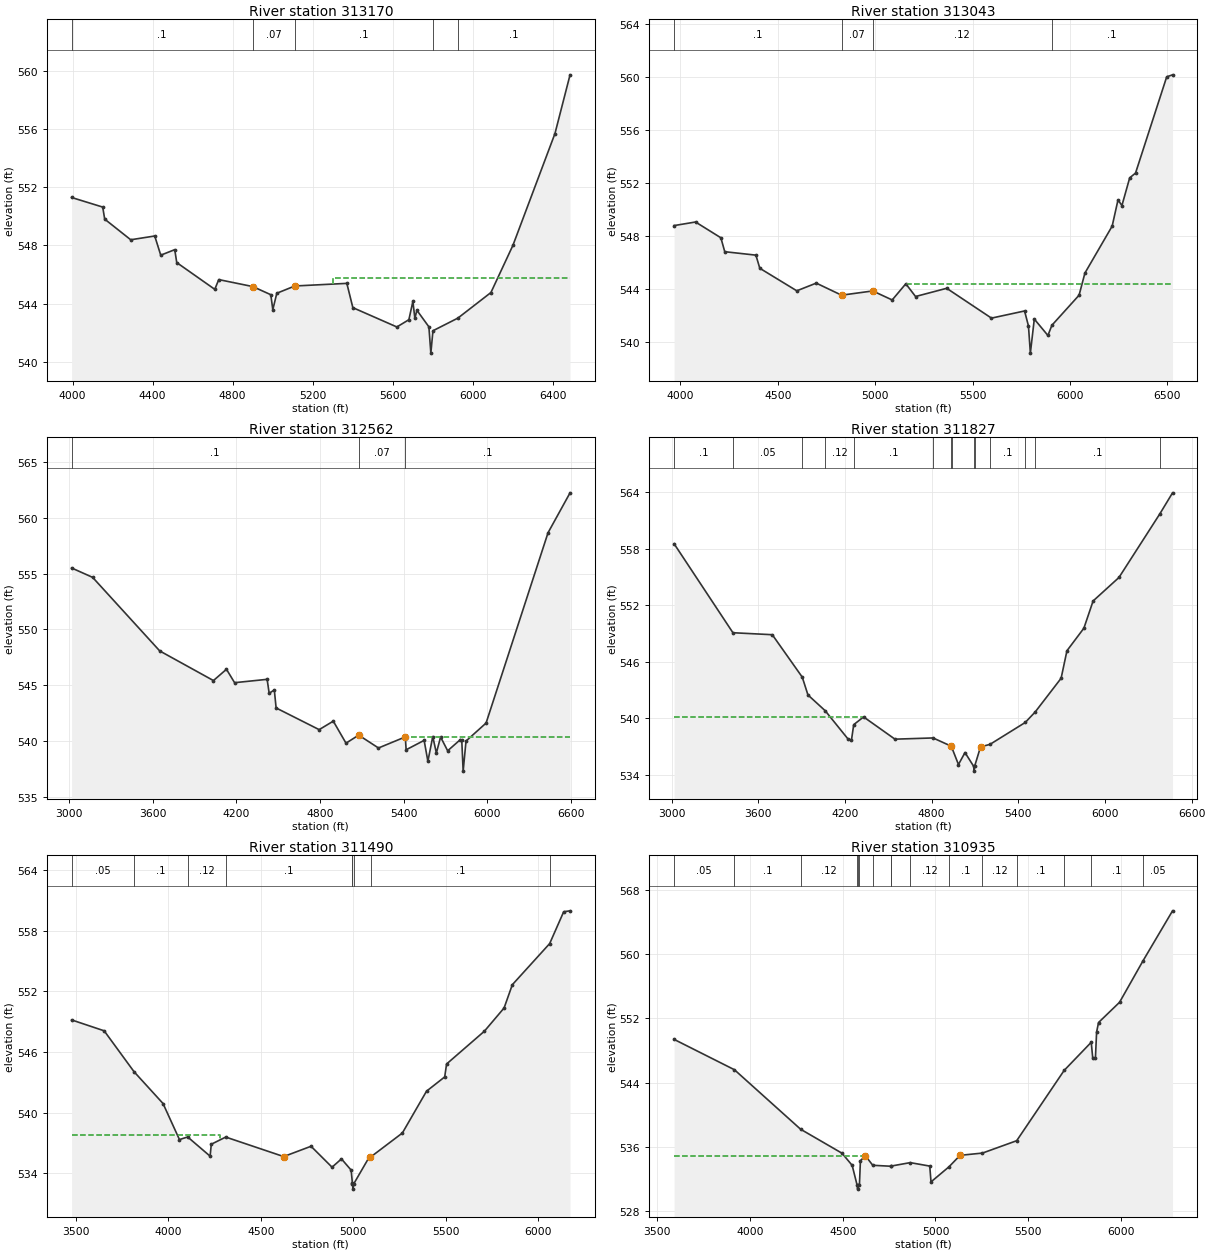
Type RM Length L Ch R = 1 ,313170  ,127,127,127
BEGIN DESCRIPTION:
Mapping XS 750ff51d
END DESCRIPTION:
XS GIS Cut Line= 2
      2143412.17     13206560.14      2145903.07     13206560.14
#Sta/Elev= 30
    3995   551.3  4150.5  550.64  4160.5  549.81  4290.5  548.39  4410.5  548.65
  4440.5  547.33  4510.5  547.71  4520.5  546.82  4710.5  544.98  4730.5  545.65
  4900.5  545.17  4990.5  544.61  5000.5  543.58  5020.5  544.71  5110.5  545.21
  5370.5  545.39  5400.5  543.72  5620.5  542.39  5680.5  542.89  5700.5  544.15
  5710.5  542.98  5720.5  543.54  5780.5   542.4  5790.3  540.59  5800.8  542.13
  5925.4     543  6090.5  544.76  6200.5  548.01  6410.5   555.7  6485.9  559.74
#Mann= 5 ,-1 , 0
    3995      .1       0  4900.5     .07       0  5110.5      .1       0
  5800.8     .12       0  5925.4      .1       0
#XS Ineff= 2 , 0
       0                 5300.53       0  545.74
Permanent Ineff=
       F       T
Bank Sta=4900.5,5110.5
XS Rating Curve= 0 ,0
Exp/Cntr=0.3,0.1

Type RM Length L Ch R = 1 ,313043  ,481,481,481
BEGIN DESCRIPTION:
LAGARTO CREEK 327.0
END DESCRIPTION:
XS GIS Cut Line= 2
      2143377.48     13206672.98      2145937.77     13206696.86
#Sta/Elev= 30
  3967.1  548.81  4077.3  549.08  4207.4  547.89  4227.4  546.84  4387.4  546.58
  4407.4  545.59  4597.4  543.89  4697.4  544.47  4827.4  543.56  4987.4  543.88
  5087.4   543.2  5157.4  544.42  5207.4  543.46  5367.4  544.08  5597.4  541.83
  5767.4  542.37  5787.4  541.24  5797.2  539.19  5817.4  541.76  5887.4  540.52
  5907.7  541.29  6047.4  543.56  6077.4  545.23  6217.4  548.77  6247.4  550.75
  6267.4  550.32  6307.4  552.41  6337.4  552.77  6497.5  560.03  6527.5  560.18
#Mann= 4 ,-1 , 0
  3967.1      .1       0  4827.4     .07       0  4987.4     .12       0
  5907.7      .1       0
#XS Ineff= 2 , 0
       0                 5157.71       0  544.42
Permanent Ineff=
       F       T
Bank Sta=4827.4,4987.4
XS Rating Curve= 0 ,0
Exp/Cntr=0.3,0.1

Type RM Length L Ch R = 1 ,312562  ,735,735,735
BEGIN DESCRIPTION:
LAGARTO CREEK 326.0
END DESCRIPTION:
XS GIS Cut Line= 3
      2142726.18     13206472.33      2143983.14     13207229.28
      2146064.59     13206896.25
#Sta/Elev= 30
    3018   555.5  3168.9  554.66  3650.2  548.08  4035.4  545.43  4128.8  546.44
  4187.1  545.24  4420.6  545.54  4435.1  544.29    4472  544.59    4485  542.98
  4793.7  541.04    4895   541.8  4986.2  539.83  5077.3  540.55  5219.1   539.4
  5411.5  540.39  5417.5  539.24  5546.6  540.08  5573.5  538.21  5608.6  540.42
  5634.3  538.95  5664.7  540.38  5715.3  539.15  5806.5  540.15  5816.6  540.07
  5826.5  537.33    5847  540.02  5990.9  541.63  6435.3  558.65  6593.2  562.22
#Mann= 3 , 0 , 0
    3018      .1       0  5077.3     .07       0  5411.5      .1       0
#XS Ineff= 2 , 0
       0                 5412.37       0   540.4
Permanent Ineff=
       F       T
Bank Sta=5077.3,5411.5
XS Rating Curve= 0 ,0
Exp/Cntr=0.3,0.1

Type RM Length L Ch R = 1 ,311827  ,337,337,337
BEGIN DESCRIPTION:
LAGARTO CREEK 325.0
END DESCRIPTION:
XS GIS Cut Line= 3
      2143142.82     13208270.97      2145323.41     13207416.78
      2146363.94     13207035.26
#Sta/Elev= 30
  3017.5  558.53  3424.8  549.09  3697.3  548.88  3904.7  544.38  3944.1  542.49
  4063.9  540.81  4220.8  537.83  4245.3   537.7  4260.9  539.34  4329.4  540.16
  4546.4   537.8    4810  537.93  4936.7  537.05  4940.9  536.87  4985.9  535.11
  5031.1  536.38  5091.5  534.91  5094.2  534.41  5097.5  534.91  5138.5  536.98
  5204.3  537.25    5448  539.57  5516.7  540.68  5696.4  544.26  5736.8  547.18
    5854  549.57  5917.9  552.46  6096.8  554.95  6379.4  561.69  6467.7  563.93
#Mann= 14 ,-1 , 0
  3017.5      .1       0  3424.8     .05       0  3904.7      .1       0
  4063.9     .12       0  4260.9      .1       0    4810     .12       0
  4936.7      .1       0  4940.9     .12       0  5091.5     .07       0
  5097.5     .12       0  5204.3      .1       0    5448     .12       0
  5516.7      .1       0  6379.4     .05       0
#XS Ineff= 2 , 0
         4326.42  540.16
Permanent Ineff=
       F       F
Bank Sta=4936.7,5138.5
XS Rating Curve= 0 ,0
Exp/Cntr=0.3,0.1

Type RM Length L Ch R = 1 ,311490  ,555,555,555
BEGIN DESCRIPTION:
LAGARTO CREEK 324.0
END DESCRIPTION:
XS GIS Cut Line= 3
      2143760.02     13208475.82      2145556.92     13207625.12
      2146251.41     13207477.54
#Sta/Elev= 30
  3475.7  549.18  3652.1   548.1  3813.5  544.06  3970.6  540.91  4059.6  537.34
    4104   537.6  4225.5   535.7  4231.9  536.88  4310.1  537.59  4623.8  535.66
  4771.8  536.68  4885.5  534.61  4936.5  535.43  4988.9  534.32  4995.7  533.03
  4996.2  532.94    4999  532.44  5002.2  532.94  5088.5  535.66  5097.6  535.66
  5266.1  537.99    5397  542.13  5495.3  543.54  5505.5  544.82    5710  548.06
  5816.8  550.36  5861.3  552.66  6063.5  556.73  6139.4  559.88  6173.8  559.97
#Mann= 9 ,-1 , 0
  3475.7     .05       0  3813.5      .1       0    4104     .12       0
  4310.1      .1       0  4995.7     .12       0  4996.2     .07       0
  5002.2     .12       0  5097.6      .1       0  6063.5     .05       0
#XS Ineff= 2 , 0
         4280.68  537.77
Permanent Ineff=
       F       F
Bank Sta=4623.8,5088.5
XS Rating Curve= 0 ,0
Exp/Cntr=0.3,0.1

Type RM Length L Ch R = 1 ,310935  ,571,571,571
BEGIN DESCRIPTION:
LAGARTO CREEK 323.0
END DESCRIPTION:
XS GIS Cut Line= 3
      2143760.05     13208601.68       2145587.3     13208211.05
      2146368.53     13207968.01
#Sta/Elev= 30
  3591.2  549.38  3916.4   545.6  4273.2  538.19  4496.5   535.2  4551.1  533.69
  4577.7  531.23  4580.5  530.73  4583.7  531.23  4590.2  531.23  4595.5  534.25
  4621.6  534.91    4662   533.7  4759.4  533.58    4763  533.61    4864  534.03
  4969.3   533.6    4976  531.63  5072.4   533.5  5132.9  534.94  5253.4  535.22
  5437.9  536.76  5693.5  545.51  5839.7  549.02  5847.7  547.05  5862.2  547.05
  5868.6   550.3  5879.1  551.48  5992.3     554  6118.6  559.16  6277.9  565.39
#Mann= 16 ,-1 , 0
  3591.2     .05       0  3916.4      .1       0  4273.2     .12       0
  4577.7     .07       0  4583.7     .12       0  4590.2      .1       0
    4662     .16       0  4759.4     .12       0    4763      .1       0
    4864     .12       0  5072.4      .1       0  5253.4     .12       0
  5437.9      .1       0  5693.5     .05       0  5839.7      .1       0
  6118.6     .05       0
#XS Ineff= 2 , 0
         4609.66  534.91
Permanent Ineff=
       F       F
Bank Sta=4621.6,5132.9
XS Rating Curve= 0 ,0
Exp/Cntr=0.3,0.1

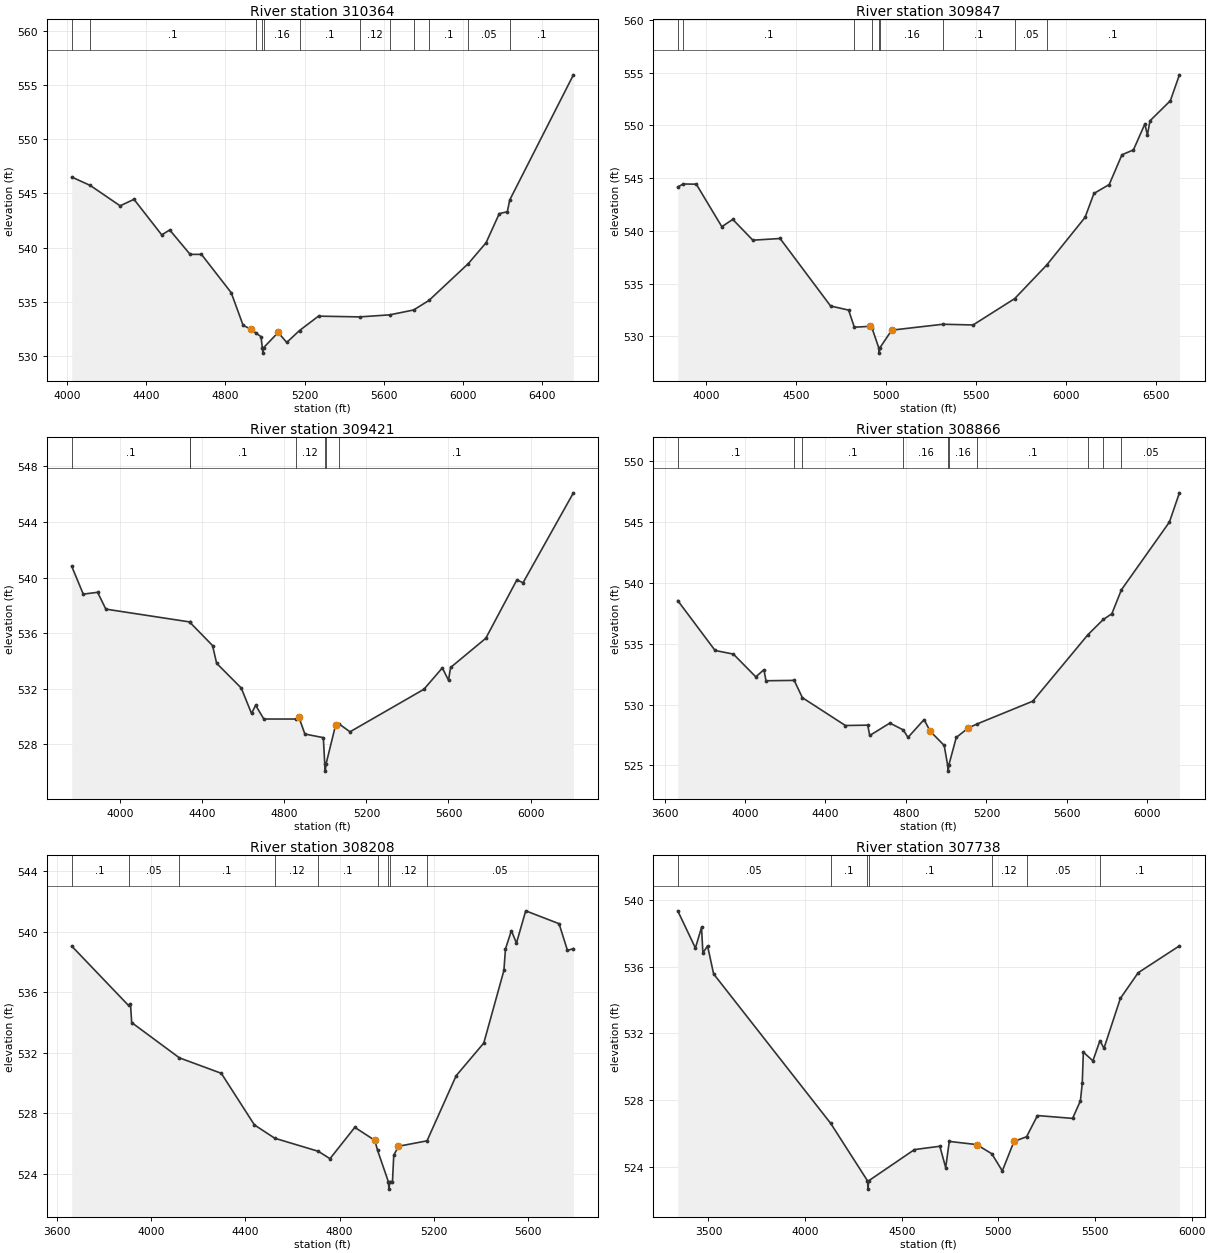
Type RM Length L Ch R = 1 ,310364  ,517,517,517
BEGIN DESCRIPTION:
LAGARTO CREEK 321.0
END DESCRIPTION:
XS GIS Cut Line= 3
      2143964.01     13208831.72      2145517.86     13208727.55
      2146429.27       13208376.
#Sta/Elev= 30
  4024.1  546.52  4117.8  545.74  4268.4  543.86  4338.5  544.46  4478.8  541.17
  4518.9  541.63  4622.1  539.37  4679.3  539.37  4829.6  535.83  4889.8  532.81
  4929.8  532.45  4955.6  532.09    4980  531.76    4987  530.74  4989.7  530.24
    4993  530.74  5066.8  532.15  5110.2  531.23  5174.7  532.33  5270.6  533.66
  5478.7  533.59  5630.8  533.78  5751.1  534.23  5828.5  535.11  6027.5  538.52
  6117.2  540.45  6183.8  543.14  6224.4  543.31  6236.6   544.4  6558.3  555.97
#Mann= 12 ,-1 , 0
  4024.1     .05       0  4117.8      .1       0  4955.6     .16       0
    4987     .07       0    4993     .16       0  5174.7      .1       0
  5478.7     .12       0  5630.8      .1       0  5751.1     .12       0
  5828.5      .1       0  6027.5     .05       0  6236.6      .1       0
Bank Sta=4929.8,5066.8
XS Rating Curve= 0 ,0
Exp/Cntr=0.3,0.1

Type RM Length L Ch R = 1 ,309847  ,426,426,426
BEGIN DESCRIPTION:
LAGARTO CREEK 320.0
END DESCRIPTION:
XS GIS Cut Line= 4
      2144006.02     13209119.01      2144521.94     13209201.81
      2146228.85     13209099.91      2146617.34     13208705.05
#Sta/Elev= 30
  3843.4  544.16  3874.3  544.44  3946.4  544.42  4088.2  540.39    4149  541.08
  4260.4  539.11  4411.8  539.27  4692.3  532.87  4792.5  532.48  4824.1  530.86
  4912.7  530.94  4922.6  530.77  4959.8   528.9  4962.5   528.4  4965.8   528.9
  5032.1  530.58  5316.6  531.14  5483.7  531.07  5714.9  533.57  5892.5  536.75
  6105.6  541.27    6155  543.54  6239.9  544.39  6310.6  547.21  6374.3  547.67
  6437.9  550.13    6452  549.08  6466.2  550.43  6579.3  552.33  6629.8  554.79
#Mann= 9 ,-1 , 0
  3843.4     .05       0  3874.3      .1       0  4824.1     .12       0
  4922.6     .16       0  4959.8     .07       0  4965.8     .16       0
  5316.6      .1       0  5714.9     .05       0  5892.5      .1       0
Bank Sta=4912.7,5032.1
XS Rating Curve= 0 ,0
Exp/Cntr=0.3,0.1

Type RM Length L Ch R = 1 ,309421  ,555,555,555
BEGIN DESCRIPTION:
LAGARTO CREEK 319.0
END DESCRIPTION:
XS GIS Cut Line= 3
      2144101.59      13209431.1       2145929.5     13209450.21
      2146540.91     13209367.41
#Sta/Elev= 30
  3763.8  540.81  3819.9  538.81  3889.9  538.94  3929.9  537.73  4337.8  536.81
    4339  536.79    4450  535.11    4470  533.83    4590  532.05    4640  530.22
    4660  530.81    4700  529.82    4856  529.82    4870  529.99    4900  528.74
    4990  528.48    4997  526.57  4999.7  526.07    5003  526.57    5050   529.4
  5067.2  529.46    5120   528.9    5480  531.96    5570   533.5  5600.1  532.61
  5610.2  533.53  5781.7  535.63  5933.1  539.83  5963.4  539.63  6208.8   546.1
#Mann= 7 ,-1 , 0
  3763.8      .1       0  4337.8     .05       0    4339      .1       0
    4856     .12       0    4997     .07       0    5003     .12       0
  5067.2      .1       0
Bank Sta=4870,5050
XS Rating Curve= 0 ,0
Exp/Cntr=0.3,0.1

Type RM Length L Ch R = 1 ,308866  ,658,658,658
BEGIN DESCRIPTION:
LAGARTO CREEK 318.0
END DESCRIPTION:
XS GIS Cut Line= 4
      2144114.33     13209825.98       2145025.1      13209966.1
      2146209.74     13209940.62      2146521.46     13209711.61
#Sta/Elev= 30
  3665.8  538.55  3851.3  534.45  3942.4  534.15  4053.7  532.28  4094.1  532.87
  4104.3  531.96  4244.6  531.99  4285.1  530.57  4498.9  528.28  4609.9  528.31
  4619.9  527.46  4719.9  528.48  4786.5  527.92    4810   527.3    4890  528.77
    4920  527.82    4990  526.64    5007  525.03  5009.8  524.53    5013  525.03
    5050   527.3    5110  528.08  5155.1  528.42  5430.1  530.28    5705  535.76
  5780.8     537  5823.2  537.47  5870.8  539.44  6109.4  545.01    6159  547.41
#Mann= 10 ,-1 , 0
  3665.8      .1       0  4244.6     .05       0  4285.1      .1       0
  4786.5     .16       0    5007     .07       0    5013     .16       0
  5155.1      .1       0    5705     .05       0  5780.8      .1       0
  5870.8     .05       0
Bank Sta=4920,5110
XS Rating Curve= 0 ,0
Exp/Cntr=0.3,0.1

Type RM Length L Ch R = 1 ,308208  ,470,470,470
BEGIN DESCRIPTION:
LAGARTO CREEK 317.0
END DESCRIPTION:
XS GIS Cut Line= 4
      2144076.14     13210424.68      2144700.28     13210596.63
      2145611.05     13210539.31      2146144.42     13210342.48
#Sta/Elev= 30
  3663.8  539.04  3904.6  535.12    3913  535.24  3918.1  533.99  4120.6  531.66
  4298.3  530.64  4438.9  527.23  4525.4  526.35  4709.8  525.49  4759.5     525
  4864.8  527.07  4949.9  526.21  4961.2  525.56    5007  523.49  5009.8  522.99
    5013  523.49  5024.6  523.49  5030.1  525.23  5050.1  525.82  5171.2  526.18
  5294.8  530.48  5412.1  532.64  5497.4  537.43    5504  538.85  5529.1  540.06
  5550.7  539.24  5589.9  541.37  5731.4  540.52  5767.2  538.75  5792.3  538.88
#Mann= 9 ,-1 , 0
  3663.8      .1       0  3904.6     .05       0  4120.6      .1       0
  4525.4     .12       0  4709.8      .1       0  4961.2     .12       0
    5007     .07       0    5013     .12       0  5171.2     .05       0
Bank Sta=4949.9,5050.1
XS Rating Curve= 0 ,0
Exp/Cntr=0.3,0.1

Type RM Length L Ch R = 1 ,307738  ,719,719,719
BEGIN DESCRIPTION:
LAGARTO CREEK 316.0
END DESCRIPTION:
XS GIS Cut Line= 4
      2143929.61     13210845.02      2144719.38     13211074.31
      2145974.09     13210895.98      2146362.21     13210571.48
#Sta/Elev= 30
  3341.2  539.34  3432.6  537.11  3464.2  538.35  3471.3  536.81  3495.4  537.24
  3526.7  535.56  4132.6   526.6  4322.9  523.16  4325.6  522.66  4328.9  523.16
  4565.9  525.03  4697.2  525.23  4727.5  523.95  4746.1  525.52  4887.9  525.33
  4966.2  524.78  5020.4  523.75    5081  525.52    5146   525.8  5202.3  527.07
  5384.1   526.9  5424.5  527.95  5434.1     529  5439.7  530.87  5489.2  530.35
  5525.6  531.56  5546.4   531.1  5631.2  534.09  5723.4  535.63  5936.8  537.24
#Mann= 7 ,-1 , 0
  3341.2     .05       0  4132.6      .1       0  4322.9     .07       0
  4328.9      .1       0  4966.2     .12       0    5146     .05       0
  5525.6      .1       0
Bank Sta=4887.9,5081
XS Rating Curve= 0 ,0
Exp/Cntr=0.3,0.1