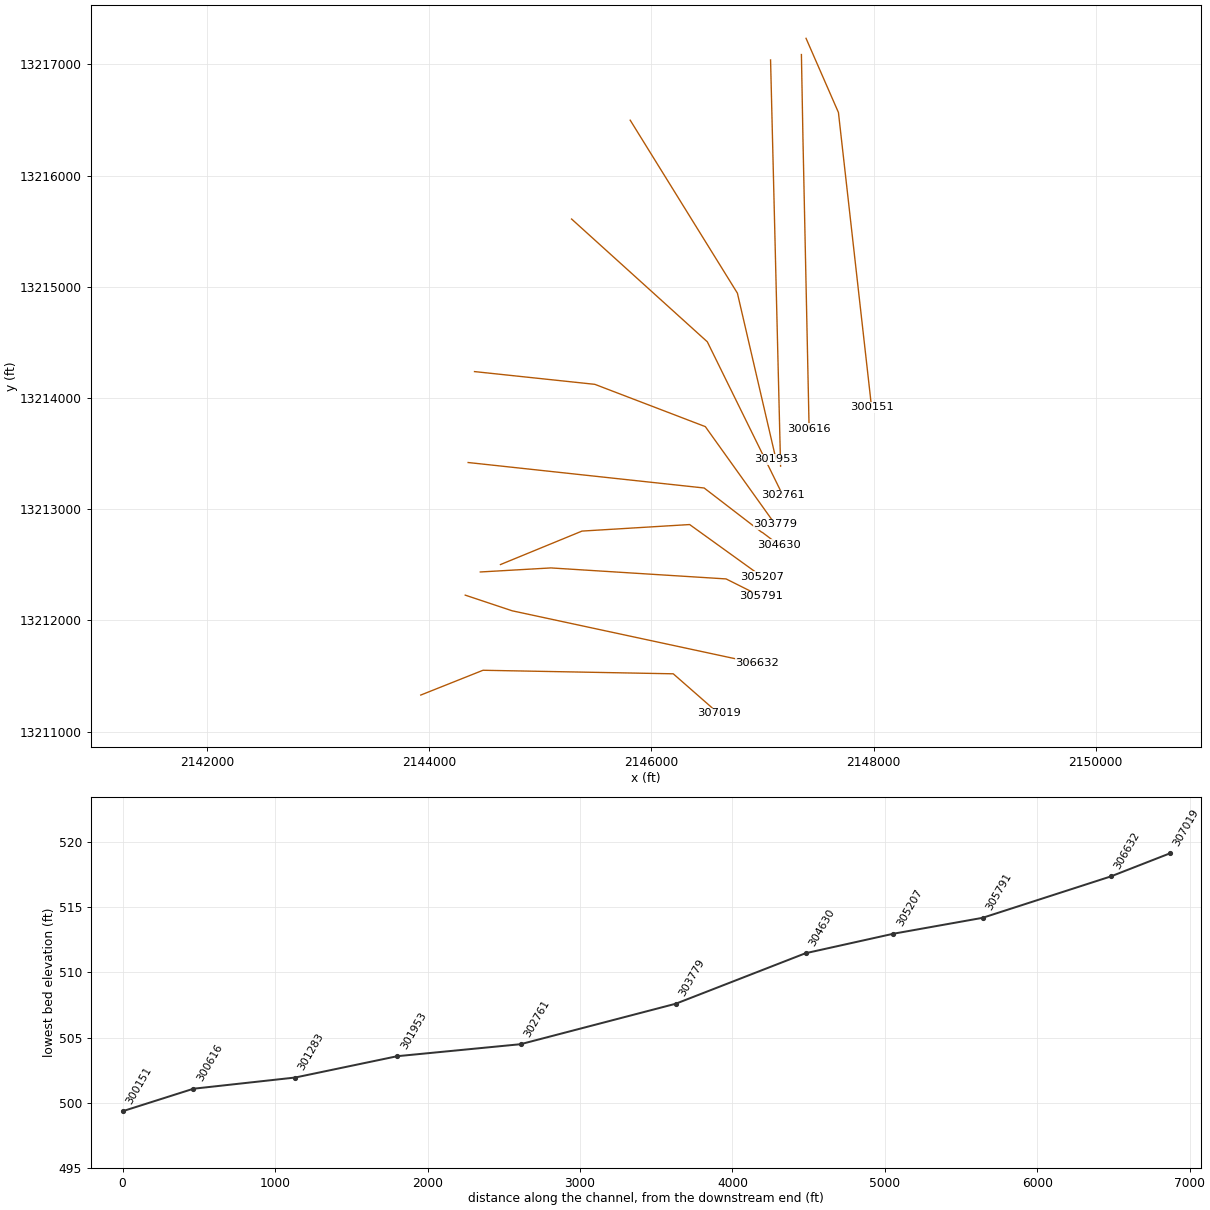
HEC-RAS study LAGARTO CREEK.prj: LAGARTO CREEK Base Level Engineering

--- LAGARTO CREEK.g01 (geometry) --- (continued)

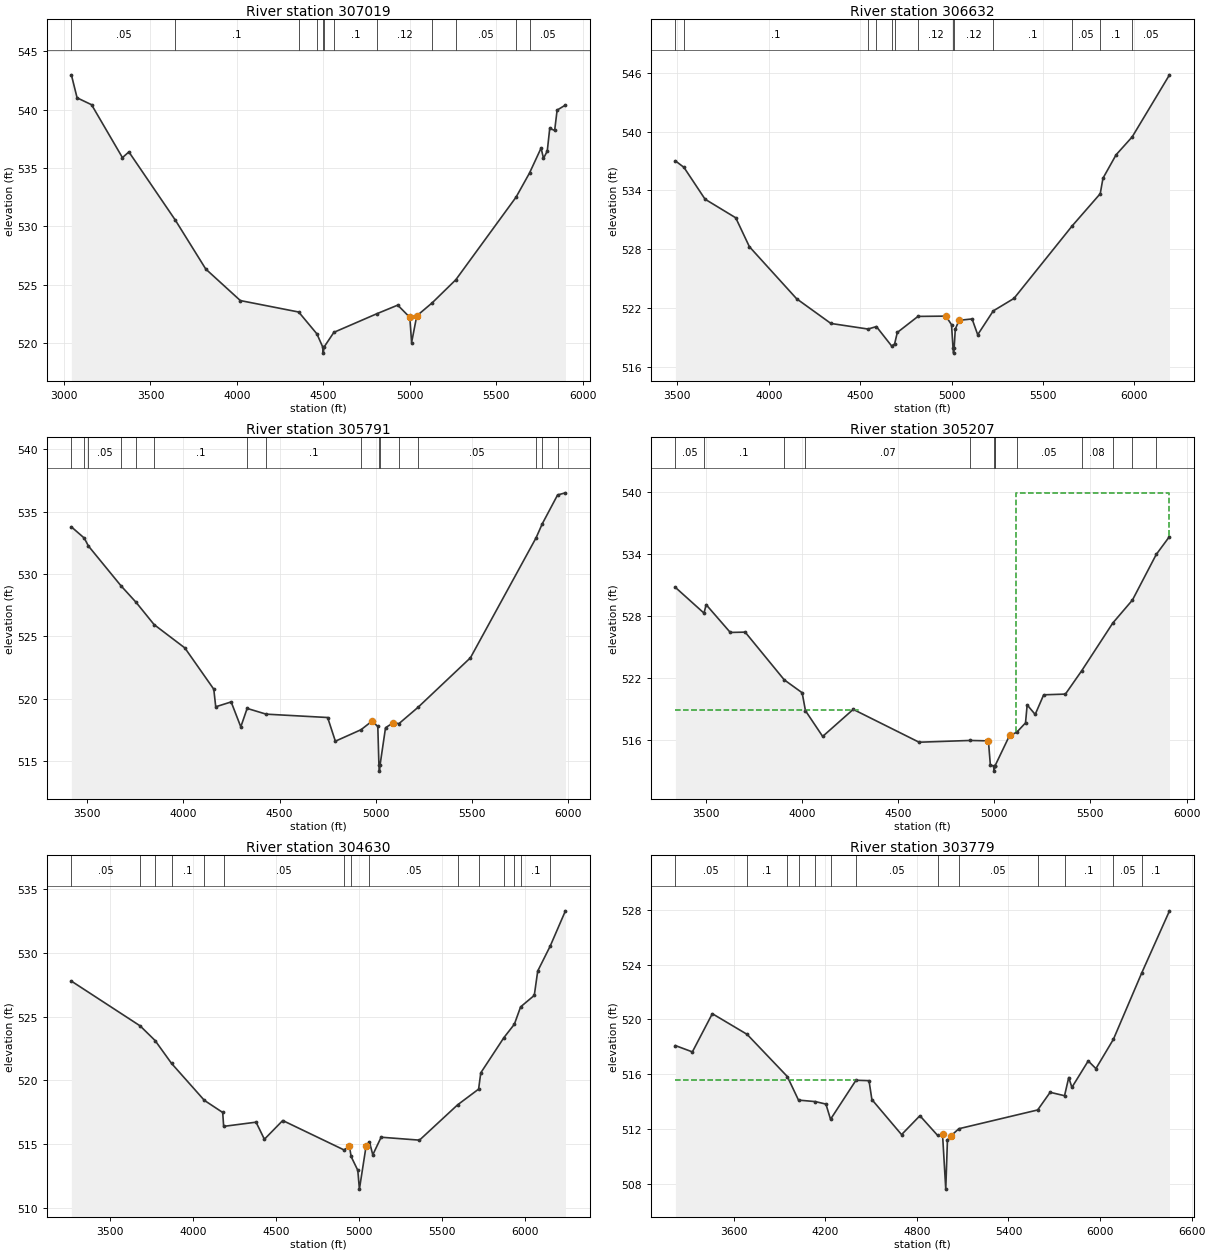
Type RM Length L Ch R = 1 ,307019  ,387,387,387
BEGIN DESCRIPTION:
LAGARTO CREEK 315.0
END DESCRIPTION:
XS GIS Cut Line= 4
      2143923.26     13211329.08      2144483.73     13211551.99
        2146197.     13211520.15      2146603.66     13211164.32
#Sta/Elev= 30
  3042.6  542.98  3075.7  541.01  3159.4  540.42    3338  535.89  3375.2  536.38
  3643.7  530.54  3819.8  526.35  4019.8  523.65  4357.2  522.67  4462.4   520.8
  4496.9  519.65  4499.7  519.15  4502.9  519.65  4560.7  520.93  4808.6  522.52
    4930  523.26    5000  522.21    5010  520.05    5040  522.34  5129.4  523.46
  5265.6  525.43  5614.3  532.51  5691.9  534.57  5758.9  536.71  5772.8  535.83
  5794.6  536.45  5808.9  538.39  5837.4  538.22  5851.6  539.96  5899.7  540.39
#Mann= 12 ,-1 , 0
  3042.6     .05       0  3643.7      .1       0  4357.2     .05       0
  4462.4     .16       0  4496.9     .07       0  4502.9     .16       0
  4560.7      .1       0  4808.6     .12       0  5129.4      .1       0
  5265.6     .05       0  5614.3      .1       0  5691.9     .05       0
Bank Sta=5000,5040
XS Rating Curve= 0 ,0
Exp/Cntr=0.3,0.1

Type RM Length L Ch R = 1 ,306632  ,841,841,841
BEGIN DESCRIPTION:
LAGARTO CREEK 314.0
END DESCRIPTION:
XS GIS Cut Line= 3
      2144323.97      13212227.6      2144745.85     13212086.98
      2146953.47     13211613.17
#Sta/Elev= 30
  3489.7  537.01  3536.3  536.35  3651.8   533.1  3819.6   531.2  3894.2  528.25
  4152.8  522.93  4340.2  520.41  4543.1  519.84    4589  520.09  4672.4  518.11
  4688.5  518.31  4703.4  519.49  4816.4  521.13  4969.3  521.16    5000  520.28
  5008.3  517.88    5011  517.38  5014.3  517.88  5020.5  519.82  5040.9  520.73
  5112.5  520.87  5143.2  519.26  5228.1  521.69  5341.7  522.97  5660.2  530.38
  5813.4  533.66  5828.4  535.24    5900  537.63  5988.5  539.47  6192.3   545.8
#Mann= 13 ,-1 , 0
  3489.7     .05       0  3536.3      .1       0  4543.1     .16       0
    4589     .12       0  4672.4     .16       0  4688.5      .1       0
  4816.4     .12       0  5008.3     .07       0  5014.3     .12       0
  5228.1      .1       0  5660.2     .05       0  5813.4      .1       0
  5988.5     .05       0
Bank Sta=4969.3,5040.9
XS Rating Curve= 0 ,0
Exp/Cntr=0.3,0.1

Type RM Length L Ch R = 1 ,305791  ,584,584,584
BEGIN DESCRIPTION:
LAGARTO CREEK 313.0
END DESCRIPTION:
XS GIS Cut Line= 5
      2144459.42     13212435.94      2145094.81     13212472.39
      2146672.93     13212373.43      2146975.02     13212222.39
      2146984.05     13212217.88
#Sta/Elev= 30
  3418.8  533.79  3485.8  532.89  3507.1  532.26  3676.1  529.07  3755.3  527.73
  3848.5  525.95  4008.1  524.08  4158.3  520.77  4168.4  519.36  4248.5  519.75
  4298.6  517.75  4331.5  519.23  4430.1  518.77  4749.5   518.5  4789.6   516.6
  4922.7  517.52    4980  518.21    5010  517.78  5015.8   514.7  5018.5   514.2
  5021.8   514.7  5050.1  517.68  5090.2  518.08  5119.8  518.01  5218.3  519.31
    5491  523.29  5832.1  532.92  5863.8  534.03  5943.6  536.35  5984.3  536.52
#Mann= 16 ,-1 , 0
  3418.8     .05       0  3485.8      .1       0  3507.1     .05       0
  3676.1      .1       0  3755.3     .05       0  3848.5      .1       0
  4331.5     .05       0  4430.1      .1       0  4922.7     .05       0
  5015.8     .04       0  5021.8     .05       0  5119.8     .08       0
  5218.3     .05       0  5832.1     .08       0  5863.8     .05       0
  5943.6     .08       0
Bank Sta=4980,5090.2
XS Rating Curve= 0 ,0
Exp/Cntr=0.3,0.1

Type RM Length L Ch R = 1 ,305207  ,577,577,577
BEGIN DESCRIPTION:
LAGARTO CREEK 311.0
END DESCRIPTION:
XS GIS Cut Line= 4
      2144641.11     13212502.74      2145375.22     13212803.72
      2146344.26     13212862.45      2146997.63     13212392.61
#Sta/Elev= 30
  3342.5  530.77    3491  528.28  3502.3   529.1  3627.7  526.41  3705.1  526.44
  3908.3  521.82  4001.4  520.57  4018.6  518.83  4108.1  516.34    4267  518.96
  4609.3  515.78    4875  515.95  4969.9  515.91    4980  513.58    4997  513.48
  4999.7  512.98    5003  513.48    5004  513.48  5080.1  516.44  5116.5  516.73
  5162.8  517.65  5171.4  519.39  5213.1  518.47  5257.3  520.37  5370.3  520.44
  5454.6  522.69    5617  527.33  5718.9  529.55  5842.5  533.96  5911.5   535.7
#Mann= 13 ,-1 , 0
  3342.5     .05       0    3491      .1       0  3908.3     .08       0
  4018.6     .07       0    4875     .12       0    4997     .07       0
    5003     .12       0    5004     .07       0  5116.5     .05       0
  5454.6     .08       0    5617     .05       0  5718.9     .08       0
  5842.5     .05       0
#XS Ineff= 2 , 0
         4292.05  518.94 5115.34          539.93
Permanent Ineff=
       F       F
Bank Sta=4969.9,5080.1
XS Rating Curve= 0 ,0
Exp/Cntr=0.3,0.1

Type RM Length L Ch R = 1 ,304630  ,851,851,851
BEGIN DESCRIPTION:
LAGARTO CREEK 310.0
END DESCRIPTION:
XS GIS Cut Line= 5
      2144350.04     13213420.31      2146475.02     13213191.14
      2146990.64     13212795.31      2147001.06      13212790.1
      2147146.11     13212681.31
#Sta/Elev= 30
  3264.9  527.79  3679.6  524.28    3770  523.13    3869  521.34  4067.1  518.44
  4177.8  517.49  4183.5   516.4    4379  516.73  4429.3  515.39  4539.9  516.86
  4910.1  514.55  4942.3  514.86  4952.3  514.04  4992.5  512.96  5002.4  511.48
  5042.8  514.86  5062.9  515.19  5083.1  514.17  5133.4  515.55  5364.7  515.32
  5594.8  518.09  5721.4  519.32  5734.6   520.6  5874.1  523.36  5937.2  524.41
  5974.8  525.77  6057.3  526.67    6078  528.58  6153.1  530.53  6245.2   533.3
#Mann= 15 ,-1 , 0
  3264.9     .05       0  3679.6     .08       0    3770     .05       0
    3869      .1       0  4067.1     .08       0  4183.5     .05       0
  4910.1     .12       0  4952.3     .07       0  5062.9     .05       0
  5594.8     .08       0  5721.4     .05       0  5874.1      .1       0
  5937.2     .05       0  5974.8      .1       0  6153.1     .05       0
#XS Ineff= 2 , 0
         4535.23  516.61
Permanent Ineff=
       F       F
Bank Sta=4942.3,5042.8
XS Rating Curve= 0 ,0
Exp/Cntr=0.3,0.1

Type RM Length L Ch R = 1 ,303779  ,1018,1018,1018
BEGIN DESCRIPTION:
LAGARTO CREEK 309.0
END DESCRIPTION:
XS GIS Cut Line= 4
      2144407.31     13214238.02      2145490.64     13214123.43
      2146485.43     13213743.23      2147115.64     13212863.02
#Sta/Elev= 30
  3217.9  518.08  3328.9  517.62  3459.6  520.41  3687.5   518.9  3951.1  515.82
  4024.2   514.1  4135.1  513.99  4203.8  513.81  4234.1   512.7  4400.8  515.55
  4486.1  515.52    4505  514.14  4699.4  511.58  4819.6  512.96  4935.8  511.52
  4967.9  511.61    4989   507.6    5000  511.19  5021.4  511.48  5074.9  512.01
  5591.1  513.38  5672.9  514.67  5767.2  514.42  5794.6  515.75  5815.4  515.03
  5922.3  516.96  5972.7   516.4  6087.3  518.54  6272.7  523.38  6454.8  527.92
#Mann= 13 ,-1 , 0
  3217.9     .05       0  3687.5      .1       0  3951.1     .05       0
  4024.2      .1       0  4135.1     .08       0  4234.1      .1       0
  4400.8     .05       0  4935.8     .03       0  5074.9     .05       0
  5591.1     .08       0  5767.2      .1       0  6087.3     .05       0
  6272.7      .1       0
#XS Ineff= 2 , 0
         4407.95  515.58
Permanent Ineff=
       F       F
Bank Sta=4967.9,5021.4
XS Rating Curve= 0 ,0
Exp/Cntr=0.3,0.1

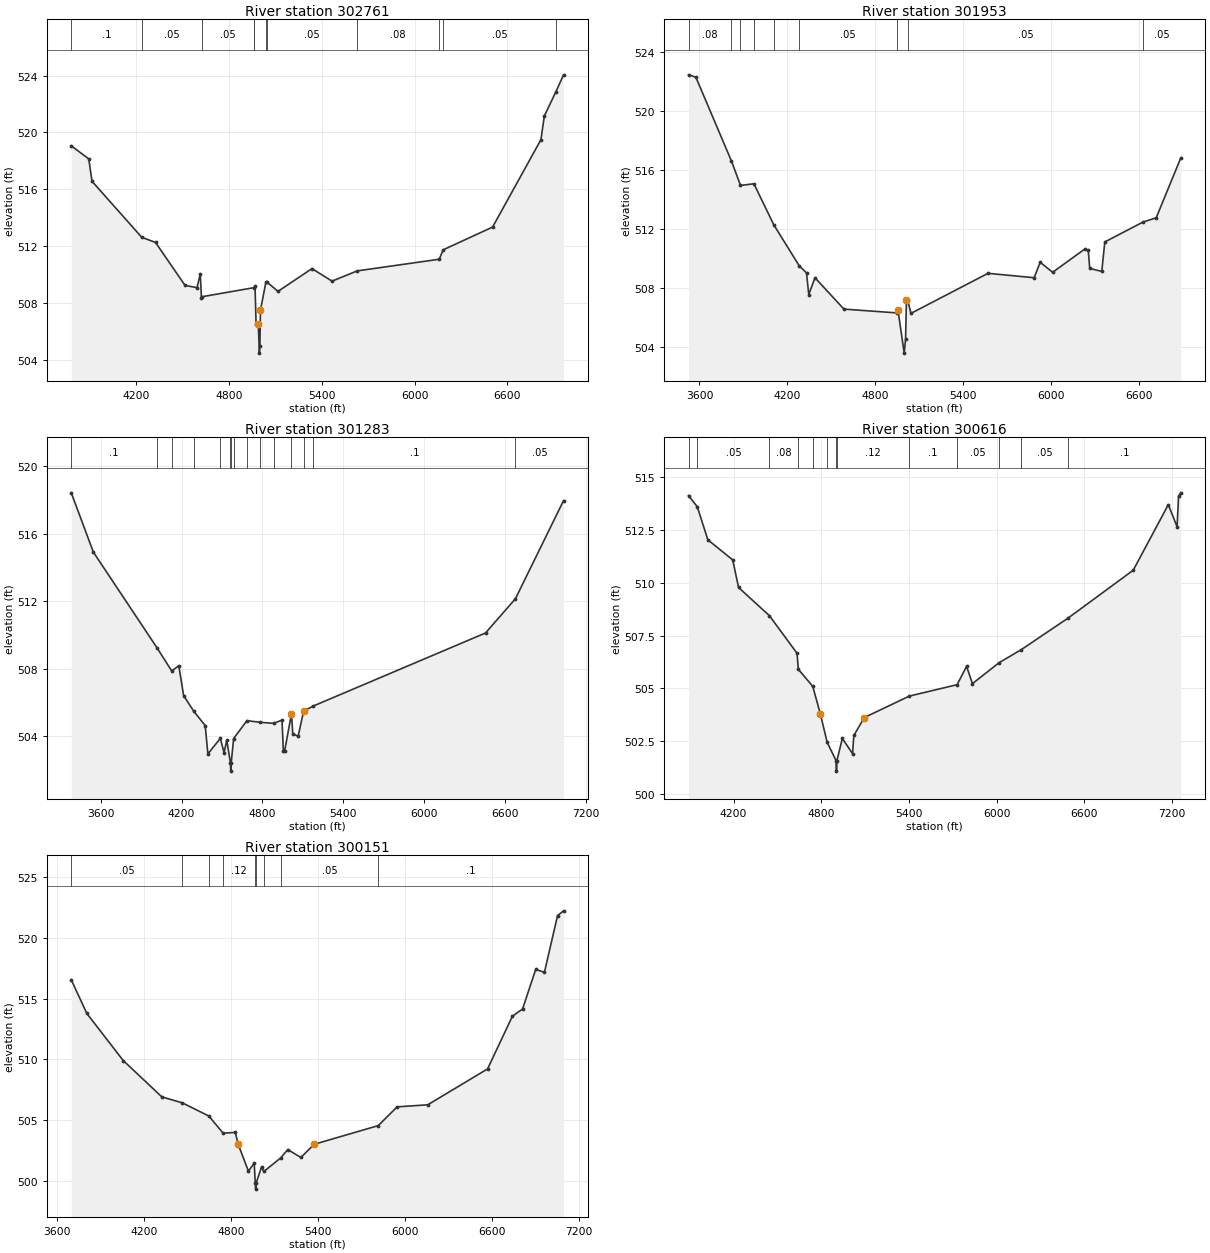
Type RM Length L Ch R = 1 ,302761  ,808,808,808
BEGIN DESCRIPTION:
LAGARTO CREEK 308.0
END DESCRIPTION:
XS GIS Cut Line= 3
      2145281.32     13215610.04      2146503.58     13214505.84
      2147183.43     13213125.33
#Sta/Elev= 30
  3778.5  519.06  3891.7  518.14  3912.6  516.57  4234.6  512.63  4323.6  512.27
  4514.8  509.25  4592.6  509.09  4613.5  510.07    4621  508.33  4627.7  508.46
  4960.3  509.09  4967.7  509.19  4974.5  506.56  4988.7  506.56  4995.9  504.49
  4999.1  504.99  5002.9  507.51  5038.7  509.51  5045.5  509.48  5116.4  508.83
  5336.1  510.43  5466.3  509.55  5629.1  510.27  6160.2  511.09  6185.1  511.75
  6505.2  513.35  6817.9  519.49  6840.2  521.16  6914.9  522.86  6964.5  524.05
#Mann= 11 ,-1 , 0
  3778.5      .1       0  4234.6     .05       0  4627.7     .05       0
  4960.3     .12       0  4960.3     .03       0  5038.7     .12       0
  5045.5     .05       0  5629.1     .08       0  6160.2      .1       0
  6185.1     .05       0  6914.9      .1       0
Bank Sta=4988.7,5002.9
XS Rating Curve= 0 ,0
Exp/Cntr=0.3,0.1

Type RM Length L Ch R = 1 ,301953  ,670,670,670
BEGIN DESCRIPTION:
LAGARTO CREEK 307.0
END DESCRIPTION:
XS GIS Cut Line= 3
      2145809.14     13216498.89      2146774.41     13214943.34
      2147121.45     13213451.07
#Sta/Elev= 30
  3525.3  522.47  3575.3  522.31    3818  516.63  3880.3  514.96    3972  515.07
  4108.6  512.27  4280.9  509.51  4331.3  509.02  4346.6  507.55  4389.1  508.69
  4586.9  506.56  4950.2   506.3  4956.1   506.5  4998.6  503.57    5008  504.53
  5013.9  507.15  5022.3  507.15  5044.7  506.27  5571.2  508.99  5886.3  508.69
  5927.5  509.74  6012.7  509.06  6230.9  510.63  6255.9  510.56  6266.1  509.32
  6348.3  509.12  6368.9  511.12  6629.7  512.47  6720.1  512.76  6888.1  516.83
#Mann= 9 ,-1 , 0
  3525.3     .08       0    3818     .05       0  3880.3     .08       0
    3972     .05       0  4108.6      .1       0  4280.9     .05       0
  4950.2     .03       0  5022.3     .05       0  6629.7     .05       0
Bank Sta=4956.1,5013.9
XS Rating Curve= 0 ,0
Exp/Cntr=0.3,0.1

Type RM Length L Ch R = 1 ,301283  ,667,667,667
BEGIN DESCRIPTION:
LAGARTO CREEK 306.0
END DESCRIPTION:
XS GIS Cut Line= 2
      2147073.02     13217040.56       2147163.3     13213387.78
#Sta/Elev= 30
  3381.1  518.41  3544.9   514.9  4018.4  509.22  4126.7  507.86  4179.2  508.17
  4215.1   506.4  4289.8  505.48  4375.1  504.63  4395.1  502.95  4487.4  503.87
  4515.2  503.02  4535.2  503.77  4562.2  502.43  4564.9  501.93  4568.2  502.43
  4586.1  503.86  4684.9  504.92  4783.7  504.82  4882.4  504.76  4945.3  504.95
  4955.3  503.15  4965.3  503.15  5015.3  505.32  5025.3  504.13  5065.3     504
  5105.3  505.48  5178.7  505.79  6455.7  510.11  6677.9  512.14    7035  517.95
#Mann= 15 ,-1 , 0
  3381.1      .1       0  4018.4     .08       0  4126.7     .05       0
  4289.8     .12       0  4487.4      .1       0  4562.2     .07       0
  4568.2      .1       0  4586.1     .12       0  4684.9      .1       0
  4783.7     .05       0  4882.4     .12       0  5015.3     .03       0
  5105.3     .05       0  5178.7      .1       0  6677.9     .05       0
Bank Sta=5015.3,5105.3
XS Rating Curve= 0 ,0
Exp/Cntr=0.3,0.1

Type RM Length L Ch R = 1 ,300616  ,465,465,465
BEGIN DESCRIPTION:
LAGARTO CREEK 305.0
END DESCRIPTION:
XS GIS Cut Line= 3
       2147350.8     13217089.18      2147364.69     13216332.23
      2147420.24      13213721.5
#Sta/Elev= 30
  3891.9  514.14  3951.8  513.61  4024.3  512.04  4194.3  511.09  4234.3  509.78
  4445.7  508.44  4634.4  506.66  4643.2   505.9    4742  505.09  4794.4  503.77
  4840.8  502.43  4901.4  501.57  4904.2  501.07  4907.4  501.57  4944.4  502.62
  5014.4   501.9    5023  502.76  5094.5  503.61    5403  504.63  5729.7  505.17
  5794.6  506.04  5834.6  505.22  6016.4  506.21  6168.3  506.83  6489.3  508.33
  6934.9   510.6  7174.9  513.71  7234.9  512.66  7244.9  514.11  7260.3  514.27
#Mann= 13 ,-1 , 0
  3891.9     .08       0  3951.8     .05       0  4445.7     .08       0
  4643.2     .05       0    4742      .1       0  4840.8     .12       0
  4901.4     .07       0  4907.4     .12       0    5403      .1       0
  5729.7     .05       0  6016.4      .1       0  6168.3     .05       0
  6489.3      .1       0
Bank Sta=4794.4,5094.5
XS Rating Curve= 0 ,0
Exp/Cntr=0.3,0.1

Type RM Length L Ch R = 1 ,300151  ,535,535,535
BEGIN DESCRIPTION:
LAGARTO CREEK 304.0
END DESCRIPTION:
XS GIS Cut Line= 3
      2147392.46     13217235.03      2147684.13     13216568.34
      2147982.73      13213915.7
#Sta/Elev= 30
  3697.2  516.54  3804.4  513.78  4055.4  509.91  4322.2  506.92  4463.5  506.43
  4646.1  505.35  4745.2  503.94  4828.9     504  4849.1  503.02  4919.5  500.82
  4959.7  501.48  4966.8  499.84  4969.6  499.34  4972.8  499.84  5010.1  501.15
  5026.5  500.79  5141.6   501.9  5191.2  502.59  5281.8  501.94  5372.3  503.02
  5815.5  504.56  5945.9   506.1  6157.3  506.27  6569.9  509.22  6741.3  513.55
  6811.4  514.14  6901.9  517.39  6962.3  517.16  7052.9  521.82  7094.3  522.21
#Mann= 9 ,-1 , 0
  3697.2     .05       0  4463.5      .1       0  4646.1     .05       0
  4745.2     .12       0  4966.8     .07       0  4972.8     .12       0
  5026.5      .1       0  5141.6     .05       0  5815.5      .1       0
Bank Sta=4849.1,5372.3
XS Rating Curve= 0 ,0
Exp/Cntr=0.3,0.1