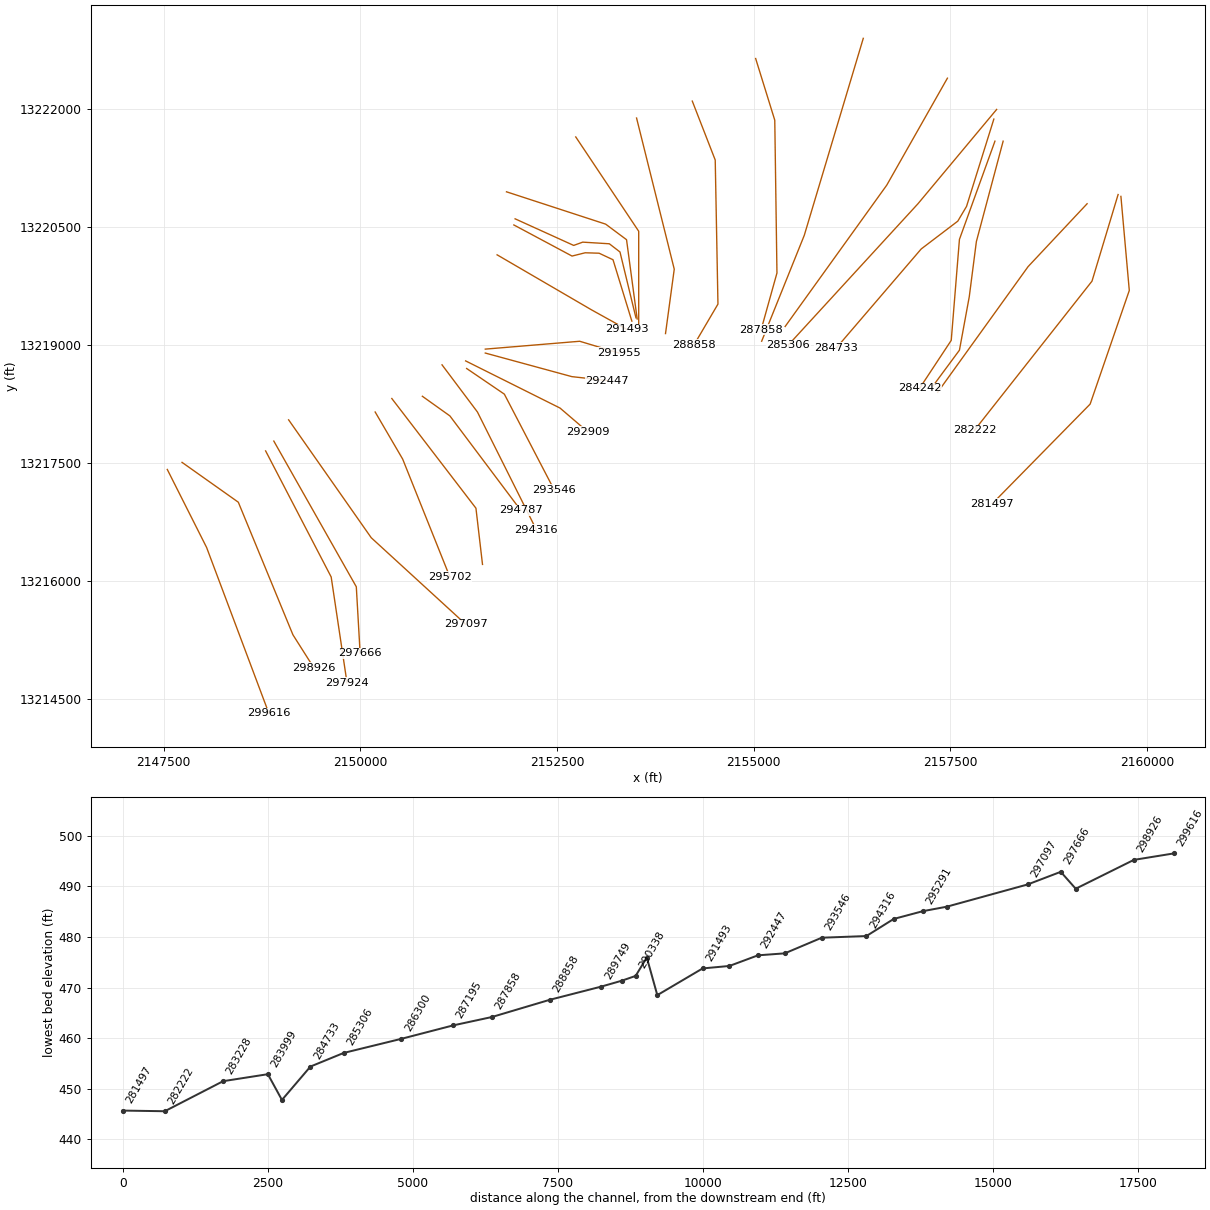
HEC-RAS study LAGARTO CREEK.prj: LAGARTO CREEK Base Level Engineering

--- LAGARTO CREEK.g01 (geometry) --- (continued)

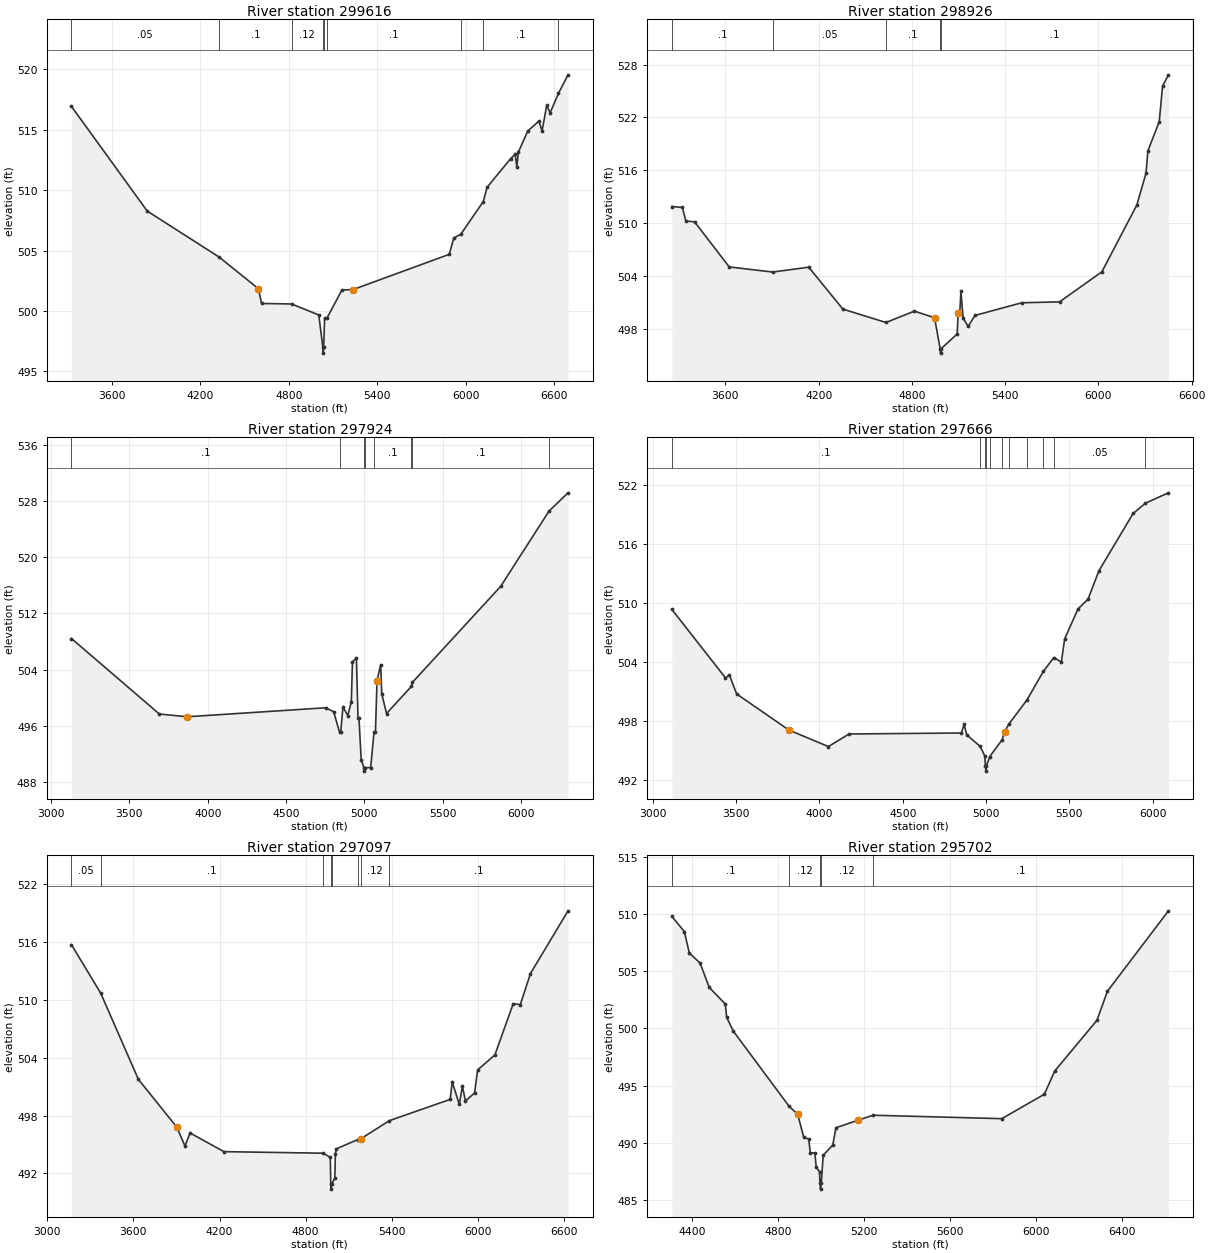
Type RM Length L Ch R = 1 ,299616  ,690,690,690
BEGIN DESCRIPTION:
LAGARTO CREEK 301.0
END DESCRIPTION:
XS GIS Cut Line= 3
      2147545.26     13217415.54      2148045.24     13216422.51
      2148836.82     13214311.65
#Sta/Elev= 30
  3326.8  516.93  3840.3  508.27  4326.7  504.47  4594.2  501.84  4615.5  500.62
  4818.9  500.58  5003.2  499.67  5030.4  497.01  5033.2  496.51  5036.4  497.01
  5042.7  499.41  5057.7  499.39  5160.2  501.74    5235  501.77  5887.8  504.69
  5918.5  506.04  5966.4  506.36  6118.5  509.06  6144.2  510.24    6303   512.6
  6334.6  512.96  6345.7  511.94  6356.4  513.16  6420.1   514.9  6495.2  515.72
  6516.6   514.9  6548.6  517.03  6571.4   516.4  6628.1  518.02    6693  519.55
#Mann= 9 ,-1 , 0
  3326.8     .05       0  4326.7      .1       0  4818.9     .12       0
  5030.4     .07       0  5036.4     .12       0  5057.7      .1       0
  5966.4     .05       0  6118.5      .1       0  6628.1     .05       0
Bank Sta=4594.2,5235
XS Rating Curve= 0 ,0
Exp/Cntr=0.3,0.1

Type RM Length L Ch R = 1 ,298926  ,1002,1002,1002
BEGIN DESCRIPTION:
LAGARTO CREEK 300.0
END DESCRIPTION:
XS GIS Cut Line= 4
      2147732.75     13217505.84      2148448.02      13216998.9
      2149142.47      13215311.4      2149406.35     13214894.74
#Sta/Elev= 30
    3256  511.88  3323.4  511.78  3345.6  510.24  3402.1  510.14  3624.9  505.02
  3904.4  504.44  4136.5  504.99  4355.9  500.23  4633.2  498.71  4816.2     500
  4945.9  499.25  4981.8  495.73  4984.6  495.23  4987.8  495.73  5091.5  497.41
  5097.3  499.74  5108.1  499.74  5115.4  502.26  5129.8  499.18  5162.2  498.26
  5205.5  499.51  5507.1  500.95  5749.7  501.05  6022.1  504.46    6247  512.04
  6306.1  515.65  6318.5  518.21  6391.4  521.52  6412.7  525.56  6450.7  526.84
#Mann= 5 ,-1 , 0
    3256      .1       0  3904.4     .05       0  4633.2      .1       0
  4981.8     .07       0  4987.8      .1       0
Bank Sta=4945.9,5097.3
XS Rating Curve= 0 ,0
Exp/Cntr=0.3,0.1

Type RM Length L Ch R = 1 ,297924  ,258,258,258
BEGIN DESCRIPTION:
LAGARTO CREEK 298.0
END DESCRIPTION:
XS GIS Cut Line= 3
      2148795.27     13217651.63      2149628.58     13216047.51
      2149829.86     13214701.03
#Sta/Elev= 30
  3130.5  508.43  3691.3  497.67  3868.4  497.28  4752.4  498.56  4803.7     498
    4841  495.08  4848.7  495.08    4863  498.69  4893.8  497.44  4916.4  499.44
  4923.7  505.12  4948.9  505.64    4959  497.11  4965.1  497.11  4979.3  491.17
  4996.5  490.03  4999.2  489.53  5002.5  490.03  5039.9  490.03  5061.4  495.08
  5070.3  495.08  5080.4  502.43  5103.6  504.69  5110.7  500.56    5141  497.74
  5299.8  501.61  5306.2  502.18    5869  515.85  6178.6  526.61  6299.6   529.2
#Mann= 8 ,-1 , 0
  3130.5      .1       0    4841     .12       0  4996.5     .07       0
  5002.5     .12       0  5061.4      .1       0  5299.8     .05       0
  5306.2      .1       0  6178.6     .05       0
Bank Sta=3868.4,5080.4
XS Rating Curve= 0 ,0
Exp/Cntr=0.3,0.1

Type RM Length L Ch R = 1 ,297666  ,569,569,569
BEGIN DESCRIPTION:
Mapping XS e83ea309
END DESCRIPTION:
XS GIS Cut Line= 3
       2148899.4      13217776.7      2149948.02     13215922.51
      2149996.63     13215075.28
#Sta/Elev= 30
  3115.4  509.32  3436.9  502.36  3459.9  502.66  3504.1  500.72  3817.3  497.05
  4054.1  495.37  4178.2  496.65  4852.3  496.75  4868.2  497.64  4884.1  496.56
  4965.3  495.38  4992.3  494.42  4996.3  493.37  4999.1  492.87  5002.3  493.37
  5021.7  494.34  5096.5  496.06  5110.7  496.85  5135.2  497.62  5244.9   500.1
  5343.8  503.02  5406.5  504.43  5451.6  503.97  5471.6  506.33  5551.7  509.38
  5611.8  510.37  5676.8  513.25  5882.3  519.09  5956.2  520.14  6094.2  521.19
#Mann= 11 ,-1 , 0
  3115.4      .1       0  4965.3     .12       0  4996.3     .07       0
  5002.3     .12       0  5021.7      .1       0  5096.5     .12       0
  5135.2      .1       0  5244.9     .05       0  5343.8      .1       0
  5406.5     .05       0  5956.2      .1       0
Bank Sta=3817.3,5110.7
XS Rating Curve= 0 ,0
Exp/Cntr=0.3,0.1

Type RM Length L Ch R = 1 ,297097  ,1395,1395,1395
BEGIN DESCRIPTION:
LAGARTO CREEK 296.0
END DESCRIPTION:
XS GIS Cut Line= 3
      2149087.71     13218046.87      2150137.72     13216546.85
      2151337.73     13215446.84
#Sta/Elev= 30
    3169  515.68  3372.7  510.66    3635  501.74  3901.4  496.82  3959.4  494.85
  3995.1  496.19    4231  494.26  4921.5   494.1  4971.7  493.67  4974.8  490.88
  4977.5  490.38  4980.8  490.88  5003.4  491.54  5007.1  494.03  5013.9  494.55
    5163  495.51  5185.3   495.6  5383.3  497.47  5806.8  499.67    5821  501.48
  5870.4  499.15  5891.9  501.05  5912.9  499.51  5976.7  500.33    5998  502.72
  6118.2  504.27  6245.9  509.58  6295.2  509.48  6366.1   512.7  6627.9  519.19
#Mann= 8 ,-1 , 0
    3169     .05       0  3372.7      .1       0  4921.5     .12       0
  4974.8     .07       0  4980.8     .12       0    5163      .1       0
  5185.3     .12       0  5383.3      .1       0
Bank Sta=3901.4,5185.3
XS Rating Curve= 0 ,0
Exp/Cntr=0.3,0.1

Type RM Length L Ch R = 1 ,295702  ,411,411,411
BEGIN DESCRIPTION:
LAGARTO CREEK 294.0
END DESCRIPTION:
XS GIS Cut Line= 3
      2150187.73     13218146.84      2150537.72     13217546.85
       2151137.7      13216046.9
#Sta/Elev= 30
  4305.4  509.78  4363.3  508.46  4386.4  506.59  4436.4  505.71  4479.4  503.58
  4553.9  502.13  4560.1  500.98  4591.1  499.77  4850.6  493.21  4890.4  492.52
    4919  490.49  4942.1  490.35  4949.1  489.14  4970.6  489.14  4976.8  487.89
  4992.1   487.5  4994.1  486.48  4996.9  485.98  5000.1  486.48  5009.4  488.94
  5053.9  489.83  5068.7  491.34    5171  491.99  5241.4  492.43  5840.1  492.13
    6038  494.26  6086.5  496.29    6283  500.72  6331.5  503.25  6615.5  510.27
#Mann= 5 ,-1 , 0
  4305.4      .1       0  4850.6     .12       0  4994.1     .07       0
  5000.1     .12       0  5241.4      .1       0
Bank Sta=4890.4,5171
XS Rating Curve= 0 ,0
Exp/Cntr=0.3,0.1

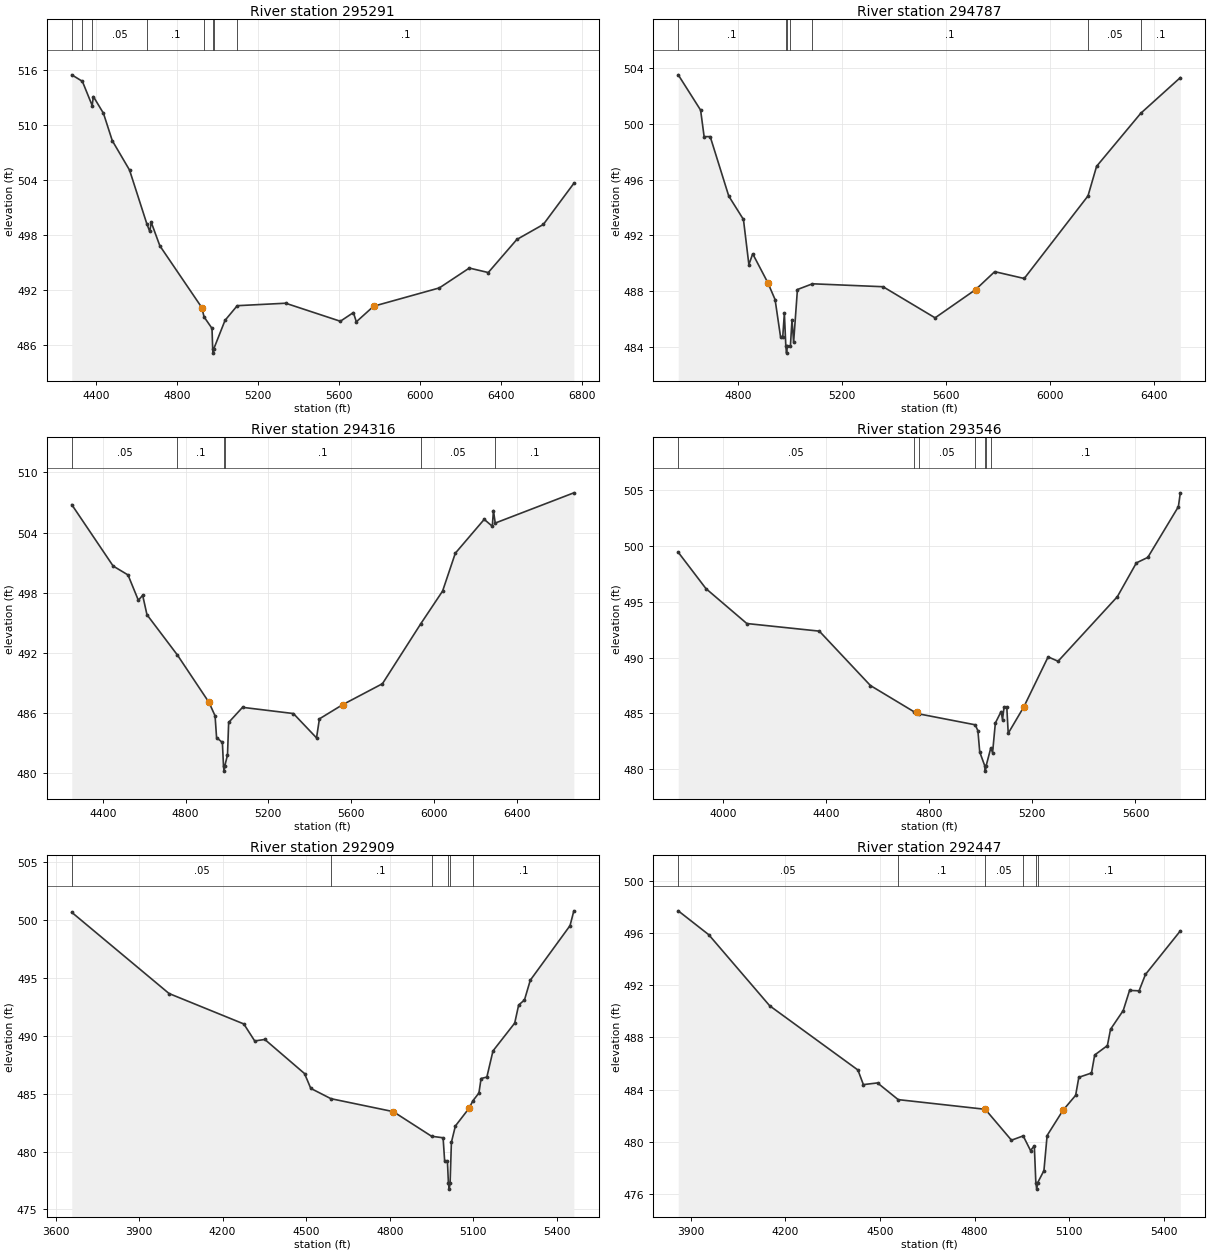
Type RM Length L Ch R = 1 ,295291  ,504,504,504
BEGIN DESCRIPTION:
LAGARTO CREEK 293.0
END DESCRIPTION:
XS GIS Cut Line= 3
      2150399.39     13218318.37      2151468.86     13216922.51
      2151552.19     13216207.21
#Sta/Elev= 30
  4279.7  515.49    4332  514.78  4380.4  512.14  4386.3  513.12  4436.1  511.29
  4479.7   508.3  4564.9  505.09  4650.4  499.21  4664.6  498.39  4672.1  499.38
  4714.5  496.82  4922.1  490.06  4932.7  489.06    4972   487.8  4975.3   485.6
    4978   485.1  4981.3   485.6  5036.3  488.68  5096.6  490.28  5335.5  490.55
  5605.6  488.58    5670  489.53  5684.5  488.52  5769.7  490.22  6094.2  492.22
  6242.3  494.39  6335.8   493.9  6476.8  497.51  6607.6  499.15  6758.3  503.64
#Mann= 8 ,-1 , 0
  4279.7     .05       0    4332      .1       0  4380.4     .05       0
  4650.4      .1       0  4932.7     .12       0  4975.3     .07       0
  4981.3     .12       0  5096.6      .1       0
Bank Sta=4922.1,5769.7
XS Rating Curve= 0 ,0
Exp/Cntr=0.3,0.1

Type RM Length L Ch R = 1 ,294787  ,471,471,471
BEGIN DESCRIPTION:
LAGARTO CREEK 292.0
END DESCRIPTION:
XS GIS Cut Line= 3
      2150787.73     13218346.85      2151137.72     13218096.85
      2152037.72     13216896.85
#Sta/Elev= 30
  4569.9  503.51  4655.9  500.98  4669.4  499.08  4692.8  499.08  4764.1  494.82
  4820.6  493.14  4841.5   489.9  4856.2  490.68    4914  488.62  4942.2   487.4
  4963.1  484.74  4971.7  484.74  4977.9  486.42  4983.5  484.06  4986.2  483.56
  4989.5  484.06  5001.1  484.06  5007.3  485.96  5013.5  484.35  5028.1  488.12
    5086  488.53  5357.3  488.32  5557.3  486.09  5713.5  488.12  5786.5   489.4
    5900  488.91  6145.1  494.83  6178.1  496.95  6347.8  500.75    6500  503.31
#Mann= 7 ,-1 , 0
  4569.9      .1       0  4983.5     .07       0  4989.5      .1       0
  5001.1     .12       0    5086      .1       0  6145.1     .05       0
  6347.8      .1       0
Bank Sta=4914,5713.5
XS Rating Curve= 0 ,0
Exp/Cntr=0.3,0.1

Type RM Length L Ch R = 1 ,294316  ,770,770,770
BEGIN DESCRIPTION:
LAGARTO CREEK 291.0
END DESCRIPTION:
XS GIS Cut Line= 3
      2151037.72     13218746.85      2151487.72     13218146.85
      2152237.74     13216646.81
#Sta/Elev= 30
    4250  506.79    4450  500.66  4521.9  499.77  4571.9  497.24  4592.7  497.74
  4613.5   495.8  4760.8  491.77  4913.5  487.04  4942.7   485.7    4950  483.53
  4978.1  483.04  4983.5  480.68  4986.2  480.18  4989.5  480.68  5002.8  481.79
  5008.4  485.04  5075.5  486.55  5321.4  485.93  5433.2   483.5  5447.2   485.4
    5559  486.81  5751.9  488.91  5937.9  494.92  6042.6  498.16  6104.1  501.94
  6243.8  505.32  6282.9  504.63  6288.5   506.2    6297  504.95  6677.1  507.97
#Mann= 6 ,-1 , 0
    4250     .05       0  4760.8      .1       0  4983.5     .07       0
  4989.5      .1       0  5937.9     .05       0    6297      .1       0
Bank Sta=4913.5,5559
XS Rating Curve= 0 ,0
Exp/Cntr=0.3,0.1

Type RM Length L Ch R = 1 ,293546  ,637,637,637
BEGIN DESCRIPTION:
LAGARTO CREEK 290.0
END DESCRIPTION:
XS GIS Cut Line= 3
      2151350.81     13218700.28      2151829.97      13218373.9
      2152461.07     13217160.24
#Sta/Elev= 30
  3826.2  499.41  3933.7  496.16  4092.3  493.04  4373.5  492.36  4571.7   487.5
  4739.8  485.17    4752  485.17  4758.9  484.97  4978.2  483.99  4988.7  483.46
  4995.8  481.56  5014.9  480.35  5017.6  479.85  5020.9  480.35  5038.7  481.92
  5045.6   481.5  5056.4  484.15  5078.6  485.17  5084.2  484.45  5090.2   485.6
  5100.7   485.6  5106.3  483.23    5167   485.6  5261.1  490.06  5299.7  489.67
  5529.7  495.44  5603.5  498.46  5647.8  498.95  5766.4  503.48  5773.9  504.72
#Mann= 7 ,-1 , 0
  3826.2     .05       0  4739.8      .1       0  4758.9     .05       0
  4978.2     .12       0  5014.9     .07       0  5020.9     .12       0
  5038.7      .1       0
Bank Sta=4752,5167
XS Rating Curve= 0 ,0
Exp/Cntr=0.3,0.1

Type RM Length L Ch R = 1 ,292909  ,462,462,462
BEGIN DESCRIPTION:
LAGARTO CREEK 289.0
END DESCRIPTION:
XS GIS Cut Line= 3
      2151337.76     13218796.84      2152537.72     13218196.85
      2152887.74     13217896.84
#Sta/Elev= 30
  3658.4  500.69  4007.7  493.67  4276.1  491.04  4315.2  489.57  4351.5   489.7
  4494.1  486.75  4516.5  485.47  4588.8  484.58  4812.7  483.46  4950.2  481.33
  4991.6   481.2  4997.2  479.17  5007.1  479.17  5010.7  477.26  5013.5  476.76
  5016.7  477.26  5021.4  480.81  5035.7  482.22  5085.1  483.76  5098.3  484.39
  5120.2  485.07  5127.9  486.32  5148.7  486.45  5170.7  488.71  5248.6  491.11
  5262.9  492.68  5283.7  493.11  5304.6  494.82  5447.3  499.54    5461  500.82
#Mann= 6 ,-1 , 0
  3658.4     .05       0  4588.8      .1       0  4950.2     .12       0
  5010.7     .07       0  5016.7     .12       0  5098.3      .1       0
Bank Sta=4812.7,5085.1
XS Rating Curve= 0 ,0
Exp/Cntr=0.3,0.1

Type RM Length L Ch R = 1 ,292447  ,492,492,492
BEGIN DESCRIPTION:
LAGARTO CREEK 288.0
END DESCRIPTION:
XS GIS Cut Line= 3
       2151587.7     13218896.86      2152687.72     13218596.85
      2153137.75     13218546.85
#Sta/Elev= 30
  3859.8   497.7  3956.6  495.87  4150.1  490.42  4429.9   485.5  4447.2  484.38
  4492.1  484.51  4557.7  483.23  4833.2  482.49  4834.2  482.48  4917.1  480.12
  4954.3  480.45  4977.5  479.33  4989.6  479.69  4994.4  476.87  4997.2  476.37
  5000.4  476.87  5020.1  477.79  5030.2  480.48  5080.5  482.41  5120.7  483.56
  5130.8  484.94    5171  485.27  5181.1  486.65  5221.4  487.37  5231.4  488.62
  5271.7  490.06  5291.8   491.6    5322  491.57  5342.1  492.82  5452.8  496.16
#Mann= 6 ,-1 , 0
  3859.8     .05       0  4557.7      .1       0  4833.2     .05       0
  4954.3     .12       0  4994.4     .07       0  5000.4      .1       0
Bank Sta=4834.2,5080.5
XS Rating Curve= 0 ,0
Exp/Cntr=0.3,0.1

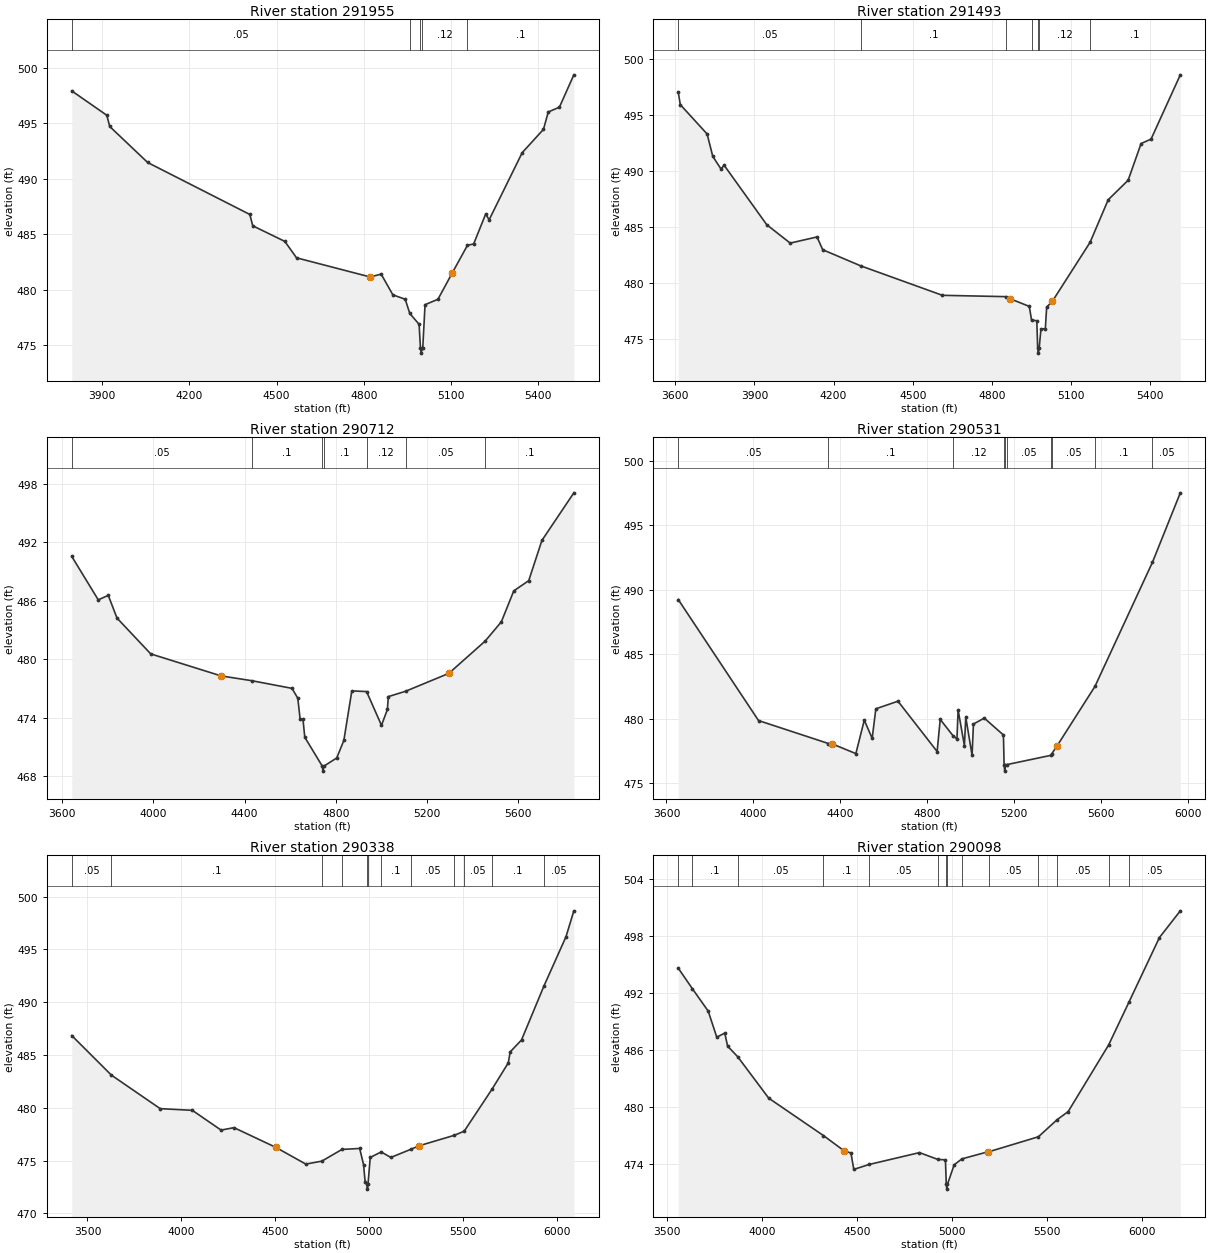
Type RM Length L Ch R = 1 ,291955  ,462,462,462
BEGIN DESCRIPTION:
LAGARTO CREEK 287.0
END DESCRIPTION:
XS GIS Cut Line= 3
      2151587.68     13218946.85      2152787.72     13219046.86
      2153287.71     13218896.86
#Sta/Elev= 30
  3795.8  497.93  3916.3  495.73  3926.3  494.72  4056.7  491.47    4408  486.78
    4418  485.76  4528.4  484.35  4568.5  482.87  4821.9  481.14  4859.5   481.4
  4899.7  479.53  4942.3  479.13  4957.9  477.85    4990  476.87  4994.5  474.77
  4997.2  474.27  5000.5  474.77  5002.6  474.77  5010.4  478.64  5054.8  479.13
  5104.4  481.53  5156.3     484  5177.5  484.12  5219.2  486.84  5230.6  486.29
  5344.5  492.36  5417.6  494.46  5434.1  496.03  5472.4  496.46    5522  499.38
#Mann= 5 ,-1 , 0
  3795.8     .05       0  4957.9     .12       0  4994.5     .07       0
  5000.5     .12       0  5156.3      .1       0
Bank Sta=4821.9,5104.4
XS Rating Curve= 0 ,0
Exp/Cntr=0.3,0.1

Type RM Length L Ch R = 1 ,291493  ,781,781,781
BEGIN DESCRIPTION:
LAGARTO CREEK 286.0
END DESCRIPTION:
XS GIS Cut Line= 3
      2151737.76     13220146.83      2152937.72     13219446.85
      2153387.74     13219196.85
#Sta/Elev= 30
  3610.8  497.08  3618.6  495.96  3720.3  493.34  3741.8  491.34  3772.8  490.22
  3784.8  490.55  3946.5  485.24  4035.4   483.6  4137.1  484.15  4158.6  483.01
  4302.8  481.57  4612.6  478.94  4854.8  478.82  4868.9  478.64  4942.1  477.95
  4950.7  476.73  4970.6  476.67  4973.8  474.28  4976.6  473.78  4979.8  474.28
  4986.4  475.95  5002.9  475.95    5008  477.89  5029.7  478.41  5172.6  483.67
  5241.4  487.47  5316.9  489.21  5366.1  492.49  5403.8  492.88  5514.8  498.62
#Mann= 7 ,-1 , 0
  3610.8     .05       0  4302.8      .1       0  4854.8     .05       0
  4950.7     .12       0  4973.8     .07       0  4979.8     .12       0
  5172.6      .1       0
Bank Sta=4868.9,5029.7
XS Rating Curve= 0 ,0
Exp/Cntr=0.3,0.1

Type RM Length L Ch R = 1 ,290712  ,181,181,181
BEGIN DESCRIPTION:
LAGARTO CREEK 285.0
END DESCRIPTION:
XS GIS Cut Line= 6
      2151950.84     13220526.92       2152690.4      13220131.1
      2152857.07     13220172.77      2153034.15     13220167.56
      2153211.23     13220084.22       2153450.8     13219303.02
#Sta/Elev= 30
  3642.5  490.55  3758.6  486.09  3802.5  486.55  3840.7  484.22  3988.6  480.54
  4296.8  478.28  4430.7  477.79  4607.8     477  4633.2  475.98  4643.5  473.82
  4655.9  473.82  4663.8  471.98  4740.8     469  4743.6   468.5  4746.8     469
  4803.8  469.85    4835  471.65    4870  476.74  4934.7  476.67    5000   473.2
    5026  474.84  5029.8  476.15  5105.4   476.7  5295.2  478.54  5454.2  481.85
  5525.3  483.83  5579.8  487.01  5645.3  488.06  5703.1  492.19  5843.1  497.08
#Mann= 7 ,-1 , 0
  3642.5     .05       0  4430.7      .1       0  4740.8     .07       0
  4746.8      .1       0  4934.7     .12       0  5105.4     .05       0
  5454.2      .1       0
Bank Sta=4296.8,5295.2
XS Rating Curve= 0 ,0
Exp/Cntr=0.3,0.1

Type RM Length L Ch R = 1 ,290531  ,193,193,193
BEGIN DESCRIPTION:
Mapping XS 9f1ee043
END DESCRIPTION:
XS GIS Cut Line= 6
      2151966.48     13220605.04      2152711.23     13220266.52
      2152825.82     13220308.18      2153164.36     13220287.35
      2153299.78     13220183.18       2153502.8     13219345.05
#Sta/Elev= 30
  3654.4  489.24  4024.2  479.86  4346.2  478.08  4363.6  478.05  4472.5   477.3
  4511.3  479.89  4547.6  478.48  4564.5  480.77  4666.4  481.36  4846.8  477.46
    4861  479.95  4920.6  478.67  4938.1  478.44  4943.4  480.68  4972.4  477.92
  4978.7  480.12  5007.7  477.17    5014  479.59    5064  480.05  5152.1  478.74
  5155.3  476.44  5158.1  475.94  5161.3  476.44  5166.5  476.44  5372.3  477.17
  5374.6  477.28    5399  477.89  5573.8  482.51  5838.6  492.13  5966.8  497.51
#Mann= 10 ,-1 , 0
  3654.4     .05       0  4346.2      .1       0  4920.6     .12       0
  5155.3     .07       0  5161.3     .12       0  5166.5     .05       0
  5372.3      .1       0  5374.6     .05       0  5573.8      .1       0
  5838.6     .05       0
Bank Sta=4363.6,5399
XS Rating Curve= 0 ,0
Exp/Cntr=0.3,0.1

Type RM Length L Ch R = 1 ,290338  ,240,240,240
BEGIN DESCRIPTION:
Mapping XS 6810be2e
END DESCRIPTION:
XS GIS Cut Line= 4
      2151857.03     13220948.82      2153117.48     13220537.35
      2153383.11     13220339.43      2153518.34     13219330.42
#Sta/Elev= 30
  3416.3  486.84    3627   483.1  3887.5  479.92  4058.7  479.76  4211.7  477.89
  4280.7  478.12    4504  476.25  4663.4  474.67  4748.7  474.95    4856  476.06
  4950.3  476.15  4971.1  474.61  4979.5  472.97  4988.9   472.8  4991.7   472.3
  4994.9   472.8  5006.6   475.3    5065  475.82  5116.4   475.3  5224.3  476.08
  5267.8  476.41  5455.5   477.4  5507.4  477.79  5655.4  481.76    5742  484.25
  5752.6   485.3  5812.6  486.42  5932.6  491.55  6049.5  496.19  6091.5  498.65
#Mann= 12 ,-1 , 0
  3416.3     .05       0    3627      .1       0  4748.7     .05       0
    4856     .12       0  4988.9     .07       0  4994.9     .12       0
    5065      .1       0  5224.3     .05       0  5455.5      .1       0
  5507.4     .05       0  5655.4      .1       0  5932.6     .05       0
Bank Sta=4504,5267.8
XS Rating Curve= 0 ,0
Exp/Cntr=0.3,0.1

Type RM Length L Ch R = 1 ,290098  ,349,349,349
BEGIN DESCRIPTION:
LAGARTO CREEK 284.0
END DESCRIPTION:
XS GIS Cut Line= 3
      2152737.73     13221646.84      2153537.72     13220446.85
      2153537.72     13219246.85
#Sta/Elev= 30
  3557.8  494.65  3631.8  492.49  3715.5  490.12  3760.6  487.37  3802.7   487.8
  3817.7  486.42  3870.7  485.31    4034  480.94  4321.8     477  4430.6  475.39
  4466.7  475.16  4481.7  473.43  4562.6  473.95  4827.2   475.2  4924.1  474.48
  4963.9  474.44  4968.5  471.85  4971.2  471.35  4974.5  471.85    5010  473.92
  5050.9  474.54    5190   475.3  5193.9   475.3  5453.2  476.87  5551.7  478.67
    5610  479.53  5822.5  486.54  5928.9  491.03    6090  497.87    6200  500.69
#Mann= 14 ,-1 , 0
  3557.8     .05       0  3631.8      .1       0  3870.7     .05       0
  4321.8      .1       0  4562.6     .05       0  4924.1     .12       0
  4968.5     .07       0  4974.5     .12       0  5050.9      .1       0
  5193.9     .05       0  5453.2      .1       0  5551.7     .05       0
  5822.5      .1       0  5928.9     .05       0
Bank Sta=4430.6,5190
XS Rating Curve= 0 ,0
Exp/Cntr=0.3,0.1

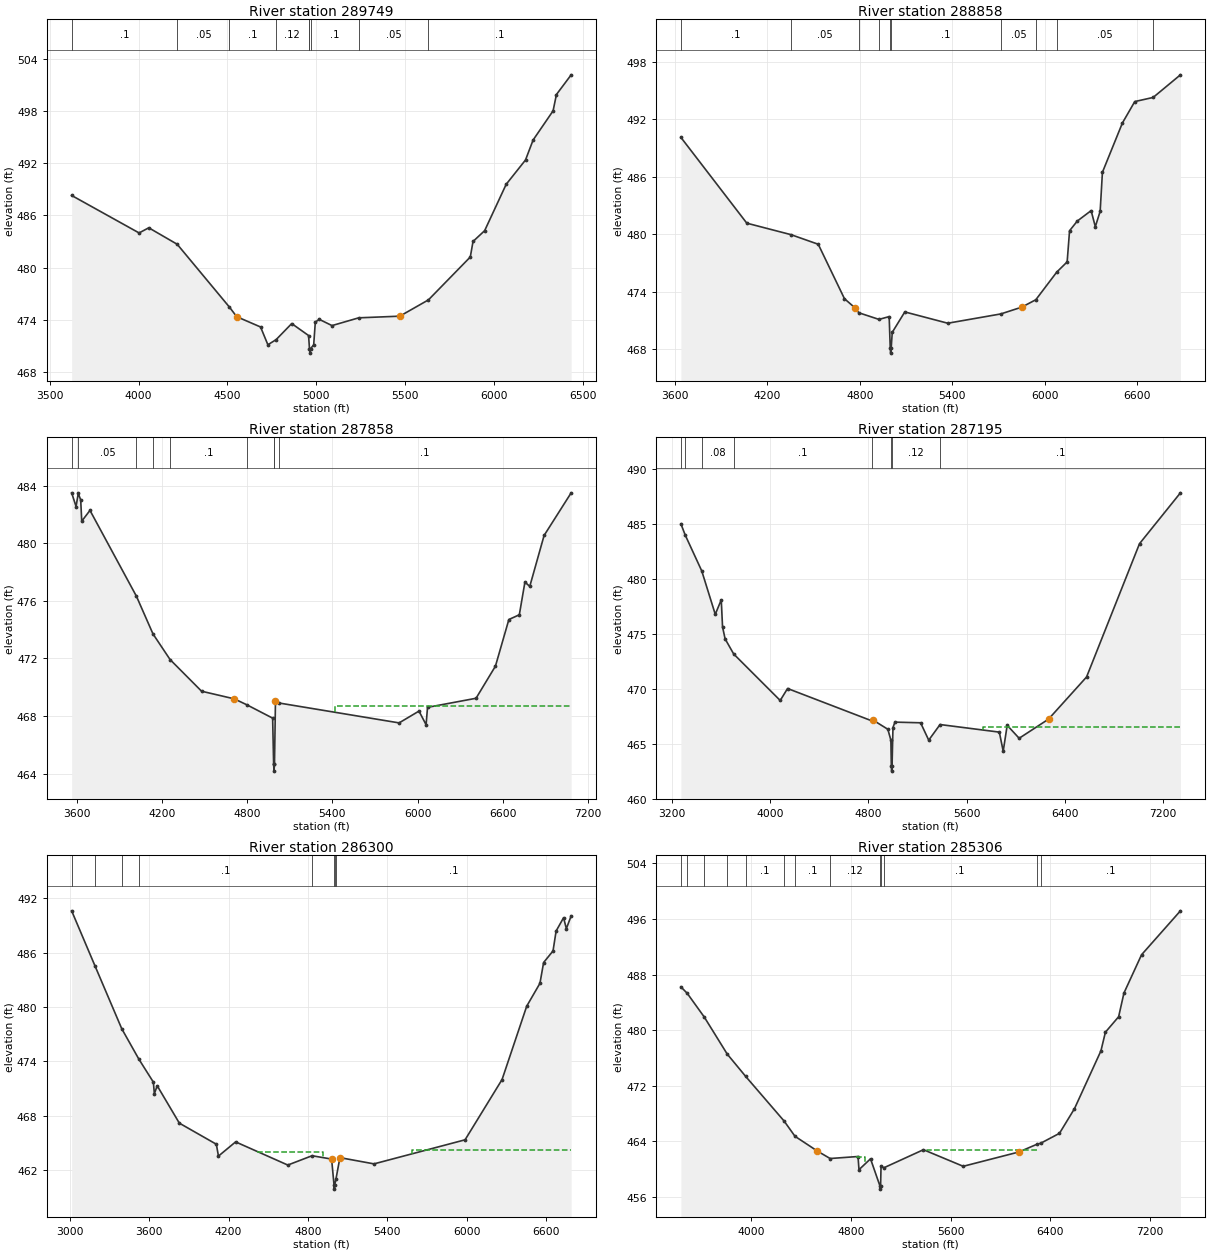
Type RM Length L Ch R = 1 ,289749  ,891,891,891
BEGIN DESCRIPTION:
LAGARTO CREEK 283.0
END DESCRIPTION:
XS GIS Cut Line= 3
      2153510.52     13221887.81      2153989.69     13219964.18
      2153878.57     13219144.69
#Sta/Elev= 30
  3623.7  488.29    4003  483.99  4057.5  484.58  4217.4  482.69  4511.1  475.48
  4552.2  474.38  4686.2   473.2  4727.4  471.16  4773.8  471.75  4861.4  473.59
  4956.2  472.22  4961.4   470.7  4964.2   470.2  4967.4   470.7    4985  471.16
  4994.1  473.75  5015.9  474.08  5088.1  473.36  5238.3  474.25  5469.4  474.44
  5630.4  476.31  5865.8  481.23  5881.1  483.01  5946.5  484.25  6067.6  489.57
  6176.3  492.36    6219  494.65  6331.4     498  6350.2  499.87  6433.1  502.13
#Mann= 9 ,-1 , 0
  3623.7      .1       0  4217.4     .05       0  4511.1      .1       0
  4773.8     .12       0  4956.2      .1       0  4961.4     .07       0
  4967.4      .1       0  5238.3     .05       0  5630.4      .1       0
Bank Sta=4552.2,5469.4
XS Rating Curve= 0 ,0
Exp/Cntr=0.3,0.1

Type RM Length L Ch R = 1 ,288858  ,1000,1000,1000
BEGIN DESCRIPTION:
LAGARTO CREEK 281.0
END DESCRIPTION:
XS GIS Cut Line= 4
      2154218.87     13222103.04      2154510.52     13221353.07
      2154545.24     13219519.73      2154240.55     13219000.36
#Sta/Elev= 30
    3639  490.09  4066.5  481.14  4353.6  479.94  4529.9  478.94  4699.9  473.26
    4770  472.28  4793.4  471.79  4923.6   471.1    4990  471.39    4997  468.08
  4999.7  467.58    5003  468.08    5010  469.75  5091.4  471.88  5370.1   470.7
  5714.3  471.67  5850.2  472.38  5941.3  473.15  6077.4  476.04  6144.6   477.1
  6160.2  480.35  6210.2  481.36  6300.1  482.45  6327.4  480.77  6358.7  482.38
  6373.4  486.45  6503.2   491.6  6583.3  493.83  6702.4  494.26  6879.5  496.62
#Mann= 10 ,-1 , 0
    3639      .1       0  4353.6     .05       0  4793.4     .12       0
  4923.6      .1       0    4997     .07       0    5003      .1       0
  5714.3     .05       0  5941.3      .1       0  6077.4     .05       0
  6702.4      .1       0
Bank Sta=4770,5850.2
XS Rating Curve= 0 ,0
Exp/Cntr=0.3,0.1

Type RM Length L Ch R = 1 ,287858  ,663,663,663
BEGIN DESCRIPTION:
Mapping XS ee7ba3ed
END DESCRIPTION:
XS GIS Cut Line= 4
      2155024.42     13222644.71      2155267.47     13221860.01
      2155295.24     13219915.57      2155093.86     13219193.34
#Sta/Elev= 30
  3565.3   483.5  3596.5  482.55  3611.8  483.46  3629.1  483.01  3636.3  481.53
  3694.3  482.28  4021.7  476.31  4137.8   473.7  4258.1  471.92  4479.9  469.72
    4710  469.19    4800  468.77    4980  467.85    4987  464.67  4989.7  464.17
    4993  464.67    5000  469.06  5025.8   468.9  5870.1  467.52  6010.1  468.34
  6060.1  467.39  6070.1   468.6  6411.6  469.23  6548.1  471.46  6642.7   474.7
  6716.3  475.03  6755.7   477.3  6789.8     477  6890.7  480.54  7081.2   483.5
#Mann= 9 ,-1 , 0
  3565.3     .08       0  3611.8     .05       0  4021.7      .1       0
  4137.8     .05       0  4258.1      .1       0    4800     .12       0
    4987     .07       0    4993     .12       0  5025.8      .1       0
#XS Ineff= 2 , 0
                         5415.91           468.7
Permanent Ineff=
       F       F
Bank Sta=4710,5000
XS Rating Curve= 0 ,0
Exp/Cntr=0.3,0.1

Type RM Length L Ch R = 1 ,287195  ,895,895,895
BEGIN DESCRIPTION:
LAGARTO CREEK 280.0
END DESCRIPTION:
XS GIS Cut Line= 3
      2156392.47     13222901.69      2155642.47     13220394.73
      2155100.79     13219047.49
#Sta/Elev= 30
  3272.7  485.04  3307.6  484.02  3442.5  480.75  3552.6   476.8  3601.3  478.12
  3611.8  475.66  3632.6  474.57  3702.7  473.19  4081.5  468.96  4141.5  470.05
  4829.1   467.1    4840  467.16  4958.2  466.34  4982.9  465.35  4986.6  463.03
  4989.3  462.53  4992.6  463.03    5000   466.5    5016  466.99    5225  466.93
  5291.2  465.35  5383.6  466.77  5866.3  466.08  5897.9  464.34  5930.3   466.7
  6027.7  465.52  6266.9  467.26  6576.9   471.1  7008.1  483.23  7341.5  487.86
#Mann= 8 ,-1 , 0
  3272.7      .1       0  3307.6     .05       0  3442.5     .08       0
  3702.7      .1       0  4829.1     .12       0  4986.6     .07       0
  4992.6     .12       0  5383.6      .1       0
#XS Ineff= 2 , 0
                            5732          466.56
Permanent Ineff=
       F       F
Bank Sta=4840,6266.9
XS Rating Curve= 0 ,0
Exp/Cntr=0.3,0.1

Type RM Length L Ch R = 1 ,286300  ,994,994,994
BEGIN DESCRIPTION:
LAGARTO CREEK 279.0
END DESCRIPTION:
XS GIS Cut Line= 3
      2157461.92     13222394.75      2156691.08     13221033.62
      2155399.41     13219235.01
#Sta/Elev= 30
  3012.9  490.62  3191.1  484.48    3392  477.59  3521.5  474.23  3631.1  471.69
  3638.6  470.41  3660.2  471.29  3827.6  467.16  4107.5  464.83  4123.4  463.52
  4253.3  465.09    4648  462.53  4831.5  463.56  4979.4  463.19  4997.4  460.37
  5000.2  459.87  5003.4  460.37    5012  460.96  5042.2  463.35    5300  462.66
    5989  465.32  6268.8  471.98  6455.4  480.09  6555.3  482.61  6583.1  484.91
  6654.3  486.19  6677.6  488.39  6734.1  489.86    6755  488.65  6791.5  490.06
#Mann= 8 ,-1 , 0
  3012.9     .05       0  3191.1      .1       0    3392     .05       0
  3521.5      .1       0  4831.5     .12       0  4997.4     .07       0
  5003.4     .12       0    5012      .1       0
#XS Ineff= 2 ,-1
 4418.18 4911.36  463.96 5586.36  6791.5  464.16
Permanent Ineff=
       F       F
Bank Sta=4979.4,5042.2
XS Rating Curve= 0 ,0
Exp/Cntr=0.3,0.1

Type RM Length L Ch R = 1 ,285306  ,573,573,573
BEGIN DESCRIPTION:
LAGARTO CREEK 277.0
END DESCRIPTION:
XS GIS Cut Line= 3
      2158087.69     13221996.82      2157087.72     13220796.85
      2155437.74     13218996.87
#Sta/Elev= 30
    3438  486.22  3488.4   485.3  3625.8  481.86  3809.2  476.54  3957.2  473.32
  4265.2  466.89  4352.5  464.69  4531.4  462.57  4633.9  461.49  4857.5  461.78
  4865.3  459.88  4957.7  461.45  5032.5  457.58  5035.2  457.08  5038.5  457.58
  5042.2  460.43  5064.1  460.15    5382  462.76  5700.8  460.37  6146.6  462.43
  6288.4  463.52  6323.6  463.71  6472.2  465.12  6592.4  468.67  6804.5     477
  6840.3  479.69  6946.4  481.92  6988.9  485.33  7130.1  490.85  7441.8  497.18
#Mann= 13 ,-1 , 0
    3438     .05       0  3488.4      .1       0  3625.8     .05       0
  3809.2     .08       0  3957.2      .1       0  4265.2     .05       0
  4352.5      .1       0  4633.9     .12       0  5032.5     .07       0
  5038.5     .12       0  5064.1      .1       0  6288.4     .05       0
  6323.6      .1       0
#XS Ineff= 2 ,-1
 4840.91 4911.93  461.76 5408.23  6305.4  462.69
Permanent Ineff=
       F       F
Bank Sta=4531.4,6146.6
XS Rating Curve= 0 ,0
Exp/Cntr=0.3,0.1

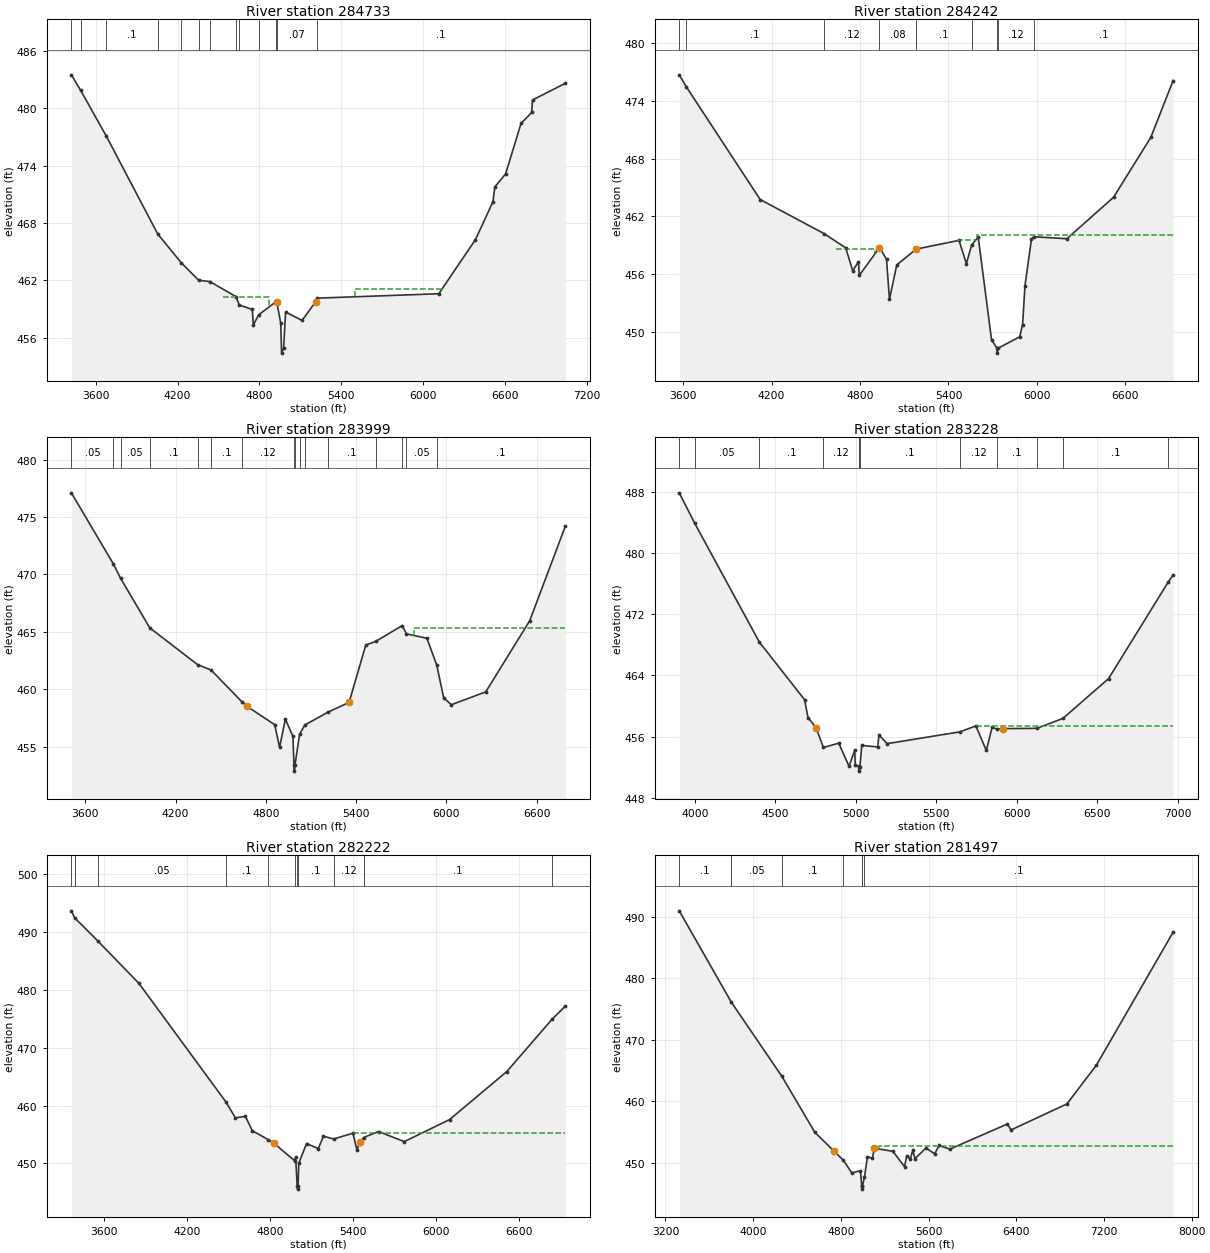
Type RM Length L Ch R = 1 ,284733  ,491,491,491
BEGIN DESCRIPTION:
LAGARTO CREEK 276.0
END DESCRIPTION:
XS GIS Cut Line= 5
       2158052.2     13221873.92      2157704.97     13220762.79
      2157593.86     13220575.29      2157128.58     13220221.12
      2156052.42     13218964.45
#Sta/Elev= 30
  3421.7   483.5    3490  481.87  3678.6  477.07  4054.6  466.86  4228.1  463.83
  4354.7  462.02  4437.1  461.87  4627.9  460.31  4653.4  459.42  4748.4  458.96
  4755.5  457.32  4795.1   458.4  4918.8  459.73  4927.9  459.71    4957  457.51
  4963.1  454.39  4977.8  454.89  4992.4  458.69  5113.1  457.81  5213.6  459.78
  5221.1  460.14  6115.9   460.6  6384.8  466.27  6513.2  470.24  6526.4  471.78
  6605.4  473.13  6718.5  478.41  6796.4  479.56    6803  480.87    7043  482.61
#Mann= 13 ,-1 , 0
  3421.7      .1       0    3490     .05       0  3678.6      .1       0
  4054.6     .08       0  4228.1      .1       0  4354.7     .08       0
  4437.1      .1       0  4627.9     .08       0  4653.4     .12       0
  4795.1     .08       0  4918.8      .1       0  4927.9     .07       0
  5221.1      .1       0
#XS Ineff= 2 ,-1
 4529.85 4872.65  460.21 5504.11 6146.77  461.07
Permanent Ineff=
       T       T
Bank Sta=4927.9,5213.6
XS Rating Curve= 0 ,0
Exp/Cntr=0.3,0.1

Type RM Length L Ch R = 1 ,284242  ,243,243,243
BEGIN DESCRIPTION:
LAGARTO CREEK 275.1
END DESCRIPTION:
XS GIS Cut Line= 4
      2158066.27     13221593.23      2157614.88     13220343.23
      2157510.72     13219058.51      2157107.97     13218447.44
#Sta/Elev= 30
  3574.3  476.71  3621.1  475.49  4123.3  463.75  4557.4   460.2  4703.2  458.73
  4750.6  456.36  4789.9  457.28  4795.2  455.87  4932.4  458.76  4979.9  457.55
    5000  453.38  5049.5  456.96  5181.6   458.6  5471.5  459.51  5521.7  457.09
  5557.4  459.03    5602  459.84  5692.3  449.18  5729.4  448.29  5732.1  447.79
  5735.4  448.29  5882.9  449.48    5903  450.75    5919  454.79  5963.2  459.65
  5980.1  459.88  6203.5  459.68  6519.6  463.98  6772.6  470.21  6924.1  476.12
#Mann= 9 ,-1 , 0
  3574.3     .05       0  3621.1      .1       0  4557.4     .12       0
  4932.4     .08       0  5181.6      .1       0  5557.4     .12       0
  5729.4     .07       0  5735.4     .12       0  5980.1      .1       0
#XS Ineff= 3 ,-1
 4634.17  4900.8  458.62 5464.77 5586.08  459.59 5594.03  6924.1  460.03
Permanent Ineff=
       T       T       T
Bank Sta=4932.4,5181.6
XS Rating Curve= 0 ,0
Exp/Cntr=0.3,0.1

Type RM Length L Ch R = 1 ,283999  ,771,771,771
BEGIN DESCRIPTION:
LAGARTO CREEK 275.0
END DESCRIPTION:
XS GIS Cut Line= 5
      2158170.44     13221593.23      2157830.16     13220315.46
      2157739.88     13219614.07      2157614.88     13218933.51
      2157282.11     13218482.89
#Sta/Elev= 30
  3507.7   477.1  3787.3   470.9    3835  469.66  4028.4  465.35  4347.1  462.14
  4435.2  461.69  4640.4  458.92  4673.3  458.53  4858.8  456.92  4891.2  454.95
  4929.4  457.41  4979.8  455.91  4986.9  453.38  4989.7  452.88  4992.9  453.38
  5024.3   456.1  5058.6  456.89    5214  458.02  5352.9  458.86  5463.8  463.85
  5531.2  464.18  5706.6  465.55  5733.2  464.83  5869.9  464.44  5935.3  462.11
  5981.7  459.25  6032.5  458.66  6261.2  459.78  6553.5  465.98  6789.3  474.18
#Mann= 16 ,-1 , 0
  3507.7     .05       0  3787.3      .1       0    3835     .05       0
  4028.4      .1       0  4347.1     .12       0  4435.2      .1       0
  4640.4     .12       0  4986.9     .07       0  4992.9     .12       0
  5024.3      .1       0  5058.6     .08       0    5214      .1       0
  5531.2     .05       0  5706.6     .12       0  5733.2     .05       0
  5935.3      .1       0
#XS Ineff= 2 , 0
                         5784.94          465.32
Permanent Ineff=
       F       F
Bank Sta=4673.3,5352.9
XS Rating Curve= 0 ,0
Exp/Cntr=0.3,0.1

Type RM Length L Ch R = 1 ,283228  ,1006,1006,1006
BEGIN DESCRIPTION:
LAGARTO CREEK 273.0
END DESCRIPTION:
XS GIS Cut Line= 3
      2159237.73     13220796.87      2158487.72     13219996.85
      2157337.72     13218396.86
#Sta/Elev= 30
  3903.4  487.86  3999.2  483.89    4401  468.35  4681.8  460.83  4702.8   458.5
  4752.6  457.19  4798.2  454.59  4893.8  455.15  4957.7  452.13  4992.9  454.23
  4996.6  452.33  5017.1  452.12  5019.1     452  5021.8   451.5  5025.1     452
  5036.8  454.86  5135.5  454.66  5143.6  456.23    5194  455.09  5646.3  456.63
  5745.2  457.41  5810.2   454.2  5845.9  457.22  5877.8  456.98  5910.9  457.05
  6124.6  457.09  6285.9  458.39    6569  463.58  6938.8  476.17  6970.4  477.13
#Mann= 12 ,-1 , 0
  3903.4      .1       0  3999.2     .05       0    4401      .1       0
  4798.2     .12       0  5017.1      .1       0  5019.1     .07       0
  5025.1      .1       0  5646.3     .12       0  5877.8      .1       0
  6124.6     .08       0  6285.9      .1       0  6938.8     .08       0
#XS Ineff= 2 , 0
                         5744.68          457.42
Permanent Ineff=
       F       F
Bank Sta=4752.6,5910.9
XS Rating Curve= 0 ,0
Exp/Cntr=0.3,0.1

Type RM Length L Ch R = 1 ,282222  ,725,725,725
BEGIN DESCRIPTION:
LAGARTO CREEK 272.0
END DESCRIPTION:
XS GIS Cut Line= 3
      2159631.84     13220914.12      2159299.98     13219811.88
       2157806.6     13217915.52
#Sta/Elev= 30
  3366.6  493.64  3390.2  492.44  3555.7  488.48  3854.6   481.1  4481.4  460.65
  4550.8  457.87    4623  458.14  4672.7  455.64  4787.1  454.12  4829.6  453.48
  4977.9  450.46  4985.4  451.05  4996.8  446.06  4999.6  445.56  5002.8  446.06
  5007.8     450    5064  453.44  5148.9  452.56  5185.9  454.69  5260.2  454.23
  5399.1  455.22  5427.8  452.33  5448.8  453.67  5475.7  454.47  5583.5  455.51
  5769.6  453.77  6096.7  457.58  6509.8  465.88  6835.9   474.9  6931.5  477.17
#Mann= 11 ,-1 , 0
  3366.6     .05       0  3390.2      .1       0  3555.7     .05       0
  4481.4      .1       0  4787.1     .12       0  4977.9      .1       0
  4996.8     .07       0  5002.8      .1       0  5260.2     .12       0
  5475.7      .1       0  6835.9     .05       0
#XS Ineff= 2 , 0
                         5399.08          455.25
Permanent Ineff=
       F       F
Bank Sta=4829.6,5448.8
XS Rating Curve= 0 ,0
Exp/Cntr=0.3,0.1

Type RM Length L Ch R = 1 ,281497  ,608,608,608
BEGIN DESCRIPTION:
LAGARTO CREEK 270.0
END DESCRIPTION:
XS GIS Cut Line= 4
       2159667.4     13220890.39      2159774.07     13219693.36
      2159276.28     13218247.39      2158033.57     13216981.01
#Sta/Elev= 30
    3326  490.94  3799.7  476.12  4262.7  464.01  4561.9  454.95  4735.6   451.9
  4823.2  450.38    4900  448.33  4978.8  448.69  4990.7  446.19  4993.5  445.69
  4996.7  446.19  5015.5  447.63  5042.3  450.95  5087.4  450.72  5105.8  452.33
    5275  451.84  5380.7  449.34  5401.9  451.15  5433.6  450.59  5456.8  452.03
  5475.9  450.66  5576.4  452.36  5655.7  451.44    5696  452.79    5795   452.2
    6318  456.27  6353.3  455.32  6862.5  459.55  7131.3  465.85  7831.3  487.48
#Mann= 7 ,-1 , 0
    3326      .1       0  3799.7     .05       0  4262.7      .1       0
  4823.2     .12       0  4990.7     .07       0  4996.7     .12       0
  5015.5      .1       0
#XS Ineff= 2 , 0
                         5149.36          452.66
Permanent Ineff=
       F       F
Bank Sta=4735.6,5105.8
XS Rating Curve= 0 ,0
Exp/Cntr=0.3,0.1