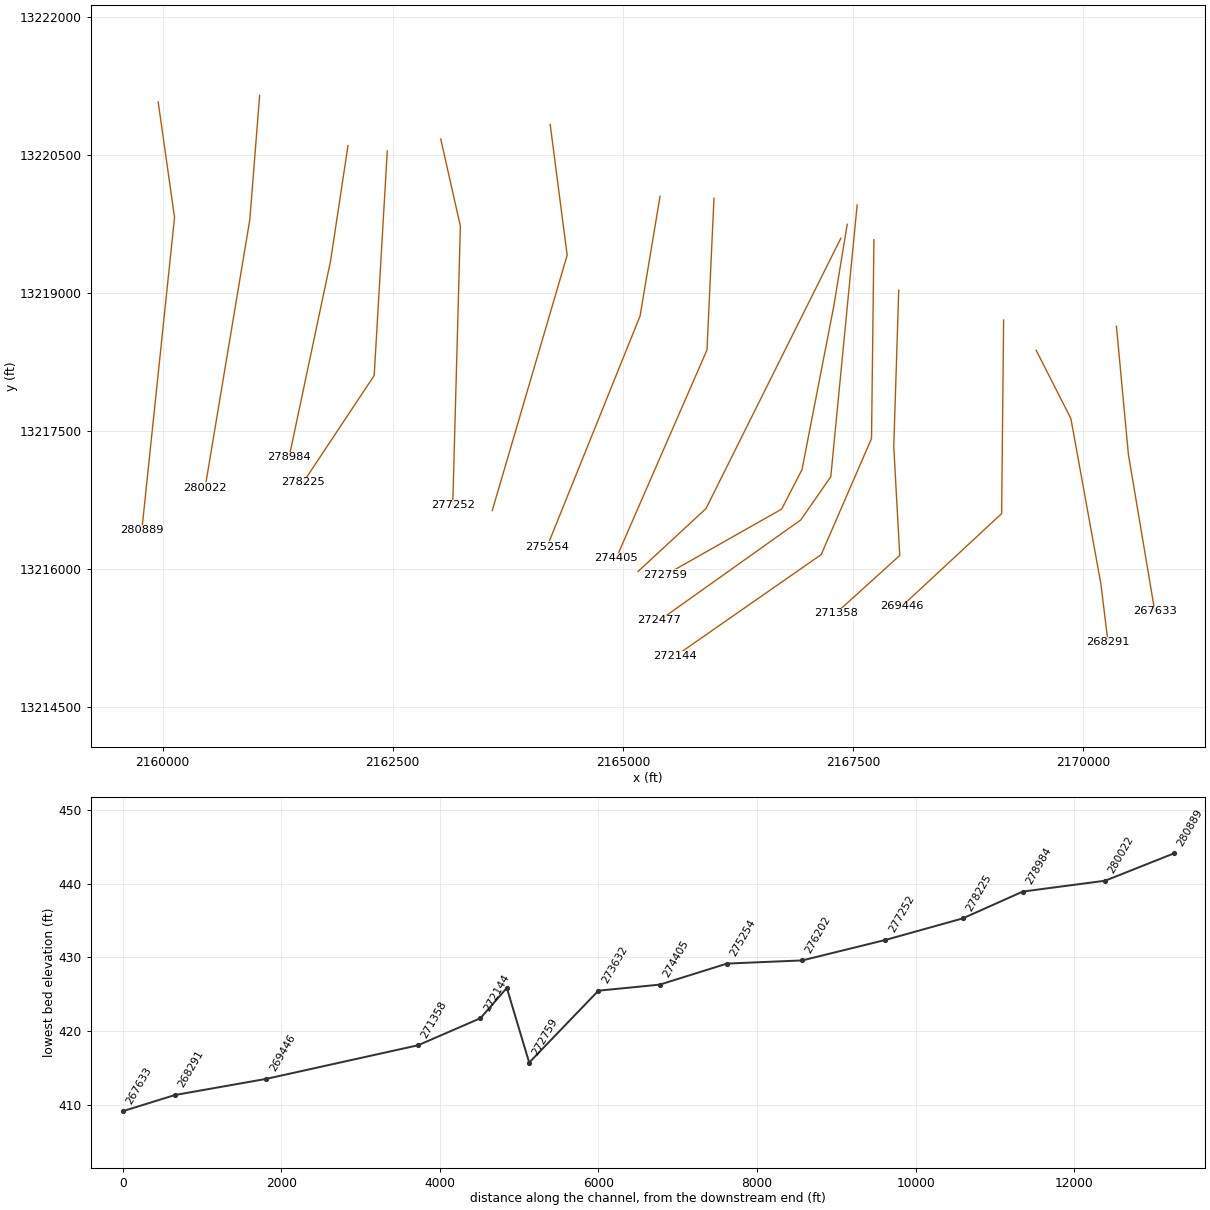
HEC-RAS study LAGARTO CREEK.prj: LAGARTO CREEK Base Level Engineering

--- LAGARTO CREEK.g01 (geometry) --- (continued)

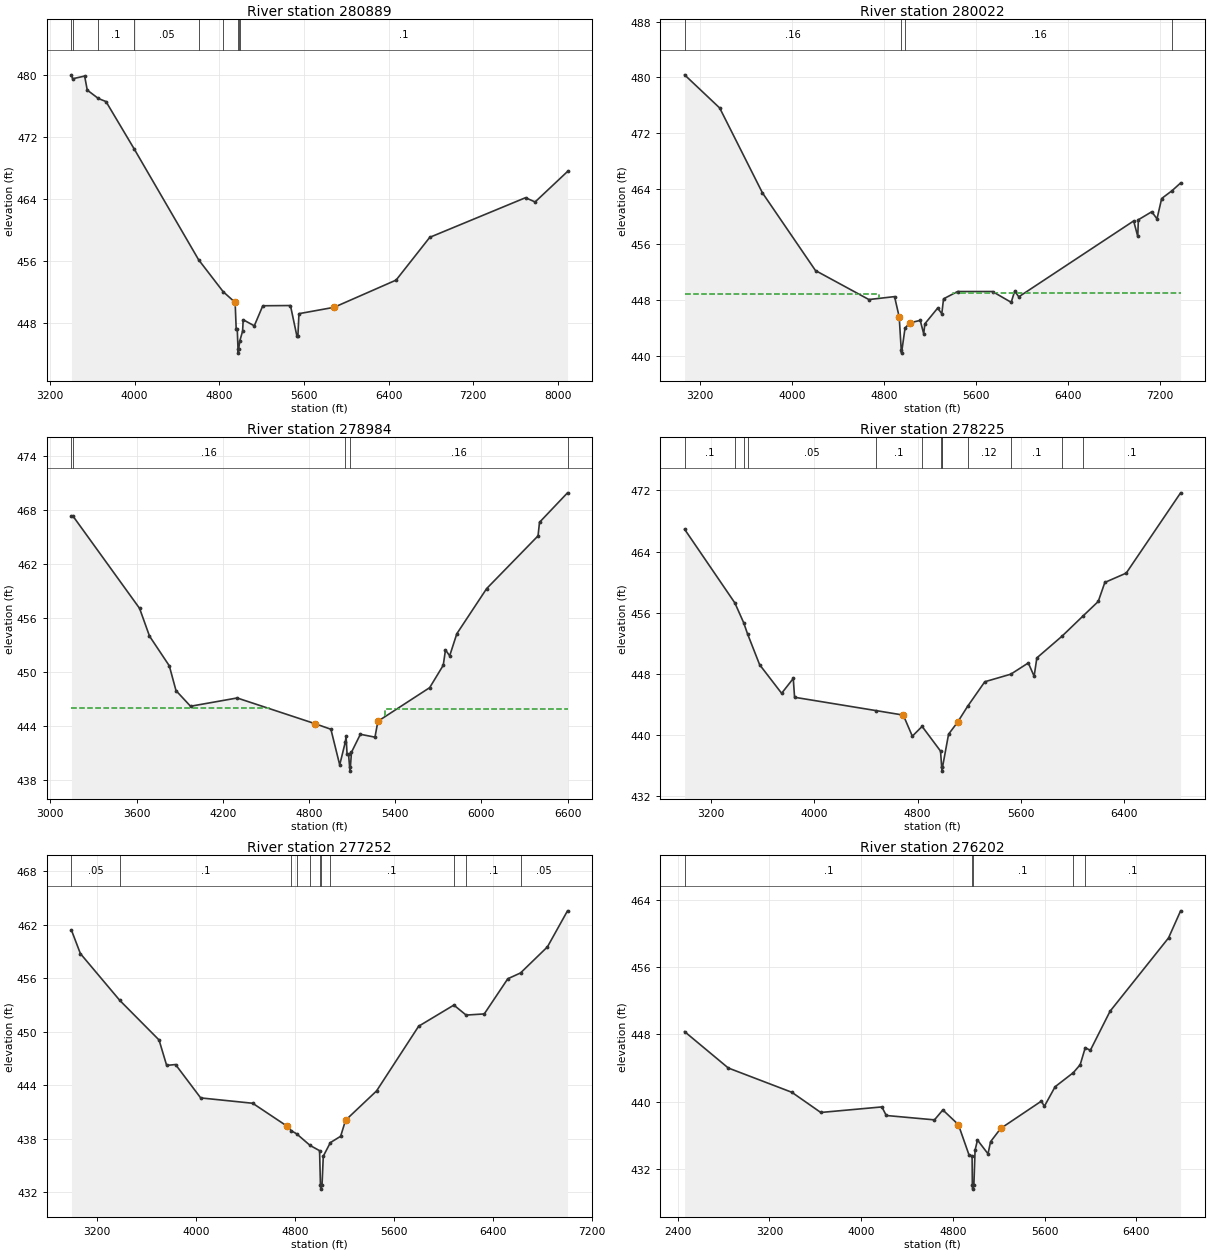
Type RM Length L Ch R = 1 ,280889  ,867,867,867
BEGIN DESCRIPTION:
LAGARTO CREEK 269.0
END DESCRIPTION:
XS GIS Cut Line= 3
      2159951.85     13221080.06      2160129.63     13219823.73
      2159774.06     13216422.11
#Sta/Elev= 30
  3402.5  480.02  3412.9  479.51  3526.9  479.86  3551.8  478.05  3656.5  476.97
  3728.9  476.57  3994.9  470.47  4604.1  456.17  4836.8  452.04  4949.7  450.66
  4959.8  447.18  4969.8  447.18  4976.9  444.62  4979.6  444.12  4982.9  444.62
  4993.2  445.67  5020.1  446.95  5025.8  448.43  5130.7  447.64  5211.1  450.23
  5472.6  450.26  5532.9  446.36  5542.9  446.36    5553  449.21  5884.8  450.03
  6471.1  453.54  6789.7  459.06  7694.6  464.17  7785.1  463.62  8091.5  467.55
#Mann= 9 ,-1 , 0
  3402.5      .1       0  3412.9     .05       0  3656.5      .1       0
  3994.9     .05       0  4604.1      .1       0  4836.8     .12       0
  4976.9     .07       0  4982.9     .12       0  4993.2      .1       0
Bank Sta=4949.7,5884.8
XS Rating Curve= 0 ,0
Exp/Cntr=0.3,0.1

Type RM Length L Ch R = 1 ,280022  ,1038,1038,1038
BEGIN DESCRIPTION:
LAGARTO CREEK 268.0
END DESCRIPTION:
XS GIS Cut Line= 3
      2161054.11      13221151.2      2160947.44     13219800.03
       2160461.5     13216884.42
#Sta/Elev= 30
  3068.6  480.35  3373.9  475.59    3745  463.42  4206.5  452.26  4670.5   448.1
  4893.5  448.52  4934.1   445.6  4951.4  440.91  4954.1  440.41  4984.6  443.99
  5025.3  444.75  5116.6  445.11    5147  443.18  5157.1  444.62  5268.6  446.88
  5304.2  446.06  5319.3   448.2    5441  449.25  5745.1  449.25  5907.3   447.7
  5937.7  449.31  5973.3  448.49  6971.8  459.38  7007.4  457.15  7012.4  459.55
    7129   460.7  7174.6  459.68  7215.1   462.6  7305.1  463.72  7379.8  464.83
#Mann= 4 ,-1 , 0
  3068.6     .16       0  4951.4     .07       0  4984.6     .16       0
  7305.1     .05       0
#XS Ineff= 2 , 0
         4757.35  448.84 5400.08          449.06
Permanent Ineff=
       F       F
Bank Sta=4934.1,5025.3
XS Rating Curve= 0 ,0
Exp/Cntr=0.3,0.1

Type RM Length L Ch R = 1 ,278984  ,759,759,759
BEGIN DESCRIPTION:
LAGARTO CREEK 266.0
END DESCRIPTION:
XS GIS Cut Line= 3
      2162014.14     13220605.99       2161824.5     13219349.64
      2161374.12     13217216.25
#Sta/Elev= 30
  3147.5  467.29  3159.4  467.29  3621.4  457.05  3690.3  453.97  3828.1  450.66
  3874.8   447.9  3975.9  446.16  4300.3  447.08    4840  444.23  4952.4   443.6
  5013.7  439.63  5052.8  442.19  5057.9  442.82  5064.8  440.85    5075  440.85
    5085  438.94  5088.3  439.44  5095.5  441.04  5157.4  443.04    5259  442.72
  5279.4  444.49  5639.6  448.23    5734  450.72  5749.6  452.43  5778.7  451.77
  5828.5  454.23  6035.8  459.25  6393.5  465.12  6403.7  466.63  6598.5  469.91
#Mann= 5 ,-1 , 0
  3147.5      .1       0  3159.4     .16       0  5052.8     .07       0
  5088.3     .16       0  6598.5      .1       0
#XS Ineff= 2 , 0
         4525.19  445.91 5331.82          445.82
Permanent Ineff=
       F       F
Bank Sta=4840,5279.4
XS Rating Curve= 0 ,0
Exp/Cntr=0.3,0.1

Type RM Length L Ch R = 1 ,278225  ,973,973,973
BEGIN DESCRIPTION:
LAGARTO CREEK 264.0
END DESCRIPTION:
XS GIS Cut Line= 3
      2162440.82     13220546.76      2162298.59     13218105.16
      2161528.21     13216943.66
#Sta/Elev= 30
  2996.7  466.93  3385.9  457.29  3454.5  454.69  3483.9  453.25  3577.6  449.21
  3747.9  445.47    3838  447.41  3848.1  444.95  4477.6  443.21  4689.5  442.62
  4759.6  439.86  4835.3  441.14  4977.9  437.91    4987  435.79  4989.7  435.29
    4993  435.79  5040.1  440.12  5110.2   441.7  5186.9  443.75  5320.5  446.98
  5521.7  447.97  5657.2  449.44  5702.4   447.7  5723.4   450.1  5918.9  452.95
  6078.8  455.55  6198.6  457.48  6249.7  459.97  6415.2  461.19  6836.2  471.69
#Mann= 13 ,-1 , 0
  2996.7      .1       0  3385.9     .05       0  3454.5      .1       0
  3483.9     .05       0  4477.6      .1       0  4835.3     .12       0
  4977.9      .1       0    4987     .07       0    4993      .1       0
  5186.9     .12       0  5521.7      .1       0  5918.9     .08       0
  6078.8      .1       0
Bank Sta=4689.5,5110.2
XS Rating Curve= 0 ,0
Exp/Cntr=0.3,0.1

Type RM Length L Ch R = 1 ,277252  ,1050,1050,1050
BEGIN DESCRIPTION:
LAGARTO CREEK 263.0
END DESCRIPTION:
XS GIS Cut Line= 3
      2163021.58     13220677.07      2163234.91     13219728.91
      2163151.95      13216694.7
#Sta/Elev= 30
  2995.7  461.38  3067.7  458.76  3386.3  453.51  3703.2  449.08  3764.7  446.23
  3836.4  446.33  4039.6  442.59  4459.8  441.99  4739.9   439.4  4771.3  438.92
  4815.2  438.56  4923.9  437.26    5000  436.68    5007  432.87  5009.8  432.37
    5013  432.87    5020  432.87    5030  436.06    5087  437.58  5170.1  438.29
  5210.1  440.09  5460.2  443.37  5800.3  450.62  6084.9  452.99  6183.8  451.87
  6330.5     452  6520.6  455.94  6623.4  456.59  6840.7  459.51  7002.9  463.55
#Mann= 11 ,-1 , 0
  2995.7     .05       0  3386.3      .1       0  4771.3     .05       0
  4815.2      .1       0  4923.9     .12       0    5007     .07       0
    5013     .12       0    5087      .1       0  6084.9     .08       0
  6183.8      .1       0  6623.4     .05       0
Bank Sta=4739.9,5210.1
XS Rating Curve= 0 ,0
Exp/Cntr=0.3,0.1

Type RM Length L Ch R = 1 ,276202  ,948,948,948
BEGIN DESCRIPTION:
LAGARTO CREEK 262.0
END DESCRIPTION:
XS GIS Cut Line= 3
      2164210.54     13220835.15        2164395.     13219413.73
      2163581.19     13216635.93
#Sta/Elev= 30
  2459.2  448.33  2840.7     444  3395.3  441.11  3647.4  438.71  4180.5  439.37
  4219.1  438.35  4639.5  437.83  4712.5  439.01    4848  437.27  4941.7  433.63
  4967.7  433.56    4970  430.09  4972.7  429.59    4976  430.09  4983.4  430.09
  4993.8  434.22  5014.7  435.43  5106.6  433.79  5129.3  435.24  5217.3  436.81
  5572.3  440.06  5598.2  439.44    5692  441.77  5851.3  443.45  5910.8  444.39
  5955.2  446.42  5999.3   446.1  6171.3  450.75  6681.9  459.48  6787.1   462.7
#Mann= 5 ,-1 , 0
  2459.2      .1       0    4970     .07       0    4976      .1       0
  5851.3     .08       0  5955.2      .1       0
Bank Sta=4848,5217.3
XS Rating Curve= 0 ,0
Exp/Cntr=0.3,0.1

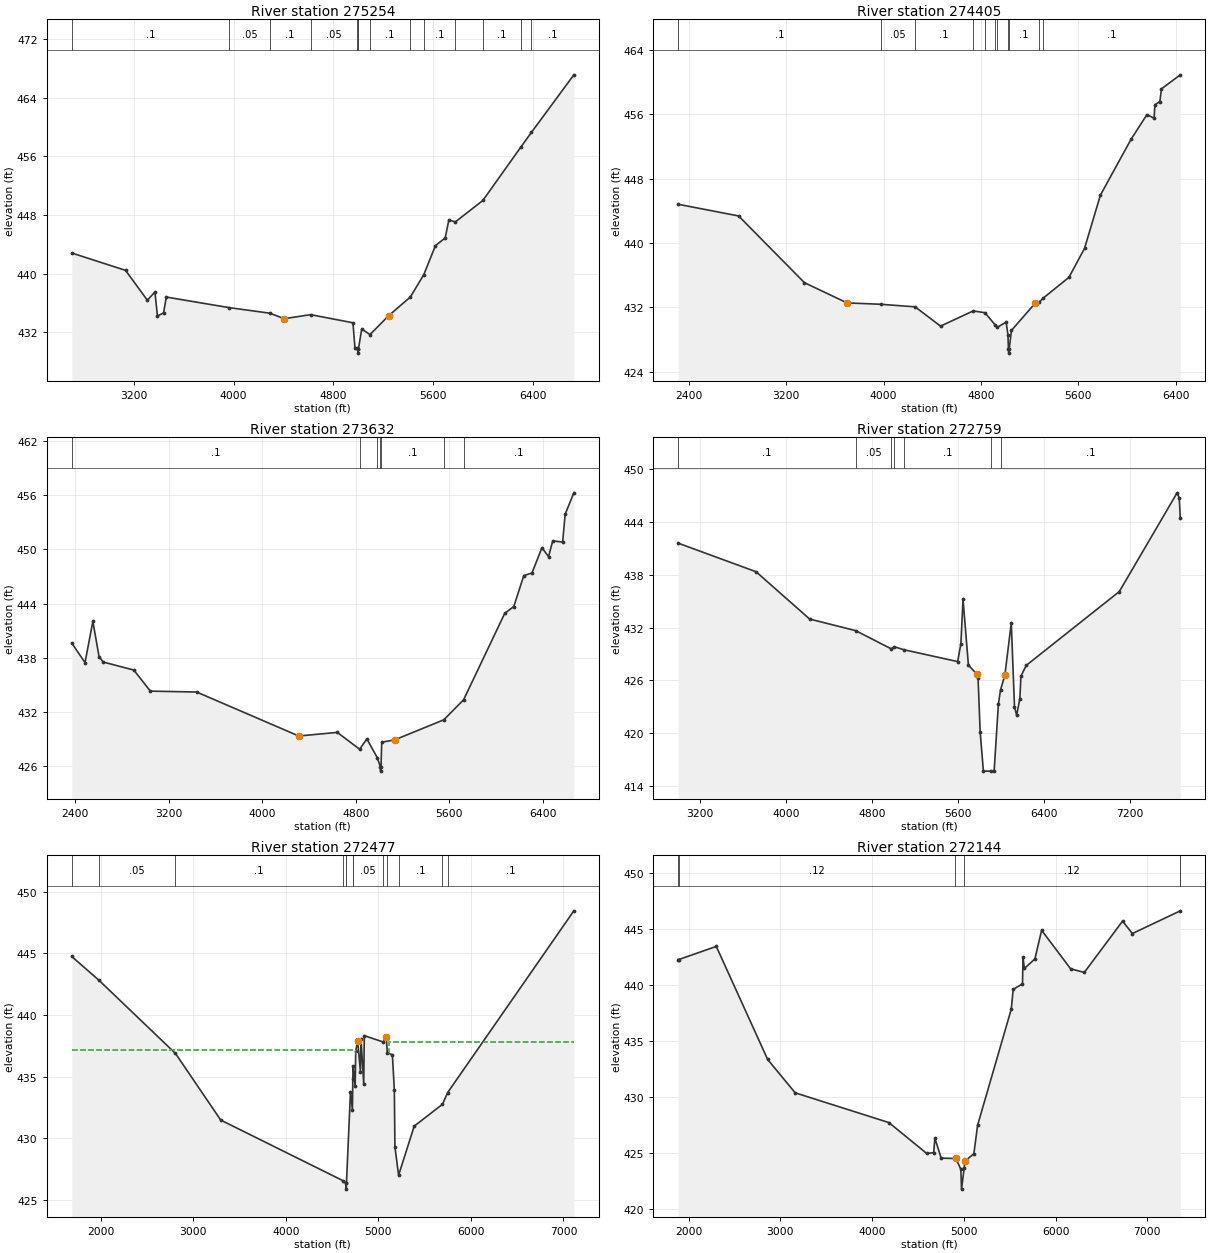
Type RM Length L Ch R = 1 ,275254  ,849,849,849
BEGIN DESCRIPTION:
LAGARTO CREEK 260.0
END DESCRIPTION:
XS GIS Cut Line= 3
      2165404.11     13220053.91       2165187.1     13218751.84
        2164178.     13216245.37
#Sta/Elev= 30
  2704.4  442.82  3135.5  440.45  3309.7  436.38  3370.5   437.5  3390.8  434.22
  3439.6  434.65  3461.8  436.81  3964.1  435.37  4290.4  434.61  4406.4  433.86
  4617.9  434.41  4956.9   433.3  4973.2  429.86  4985.3  429.86  4994.3  429.66
  4997.1  429.16  5000.3  429.66  5026.9  432.45  5093.2  431.69  5241.8  434.25
  5416.7  436.82  5524.5  439.87  5617.9  443.83  5695.8  444.88  5725.3  447.34
  5776.8  447.06  5997.6  449.99  6303.3  457.31  6386.8  459.28  6726.4  467.13
#Mann= 14 ,-1 , 0
  2704.4      .1       0  3964.1     .05       0  4290.4      .1       0
  4617.9     .05       0  4985.3     .12       0  4994.3     .07       0
  5000.3     .12       0  5093.2      .1       0  5416.7     .08       0
  5524.5      .1       0  5776.8     .05       0  5997.6      .1       0
  6303.3     .05       0  6386.8      .1       0
Bank Sta=4406.4,5241.8
XS Rating Curve= 0 ,0
Exp/Cntr=0.3,0.1

Type RM Length L Ch R = 1 ,274405  ,773,773,773
BEGIN DESCRIPTION:
LAGARTO CREEK 258.0
END DESCRIPTION:
XS GIS Cut Line= 3
      2165990.05     13220032.24      2165914.09     13218382.92
      2164926.68     13216115.12
#Sta/Elev= 30
  2313.7  444.82  2809.6  443.37  3350.2  435.07  3700.6  432.55  3975.6  432.38
  4259.6  432.06  4468.4  429.66  4736.9  431.55  4833.3  431.33  4914.8  429.86
  4935.9  429.53  5007.5  430.15  5022.1  428.61  5026.3   426.8  5029.1   426.3
  5032.3   426.8  5051.2  429.13  5243.9  432.48    5278  432.62    5310  433.12
  5523.4  435.73  5651.5  439.34  5781.9  445.96  6032.8  452.89  6163.6  455.97
  6223.2  455.54  6229.1  457.19    6270  457.61  6283.6  459.19  6438.2  460.93
#Mann= 11 ,-1 , 0
  2313.7      .1       0  3975.6     .05       0  4259.6      .1       0
  4736.9     .05       0  4833.3     .12       0  4914.8     .05       0
  4935.9      .1       0  5026.3     .07       0  5032.3      .1       0
    5278     .08       0    5310      .1       0
Bank Sta=3700.6,5243.9
XS Rating Curve= 0 ,0
Exp/Cntr=0.3,0.1

Type RM Length L Ch R = 1 ,273632  ,873,873,873
BEGIN DESCRIPTION:
LAGARTO CREEK 257.0
END DESCRIPTION:
XS GIS Cut Line= 3
      2167368.07     13219598.16      2165903.24     13216657.66
       2165165.4     13215974.06
#Sta/Elev= 30
  2373.1  439.63  2486.3  437.47  2553.3  442.03  2606.5  438.12  2642.7  437.53
  2903.1  436.65  3044.9  434.32  3440.3  434.22  4313.4  429.36  4642.5  429.76
  4833.3   427.9  4895.4  429.04  4984.6  426.95  5009.9  425.98  5012.7  425.48
  5015.9  425.98  5022.3  428.67  5134.1  428.94  5552.5  431.15  5722.1  433.37
  6073.4  442.91    6151  443.67  6236.1  447.08  6306.5  447.38  6391.4  450.16
  6448.1  449.18  6483.7  450.92  6568.3  450.79  6589.9  453.87  6664.1  456.23
#Mann= 7 ,-1 , 0
  2373.1      .1       0  4833.3     .12       0  4984.6      .1       0
  5009.9     .07       0  5015.9      .1       0  5552.5     .08       0
  5722.1      .1       0
Bank Sta=4313.4,5134.1
XS Rating Curve= 0 ,0
Exp/Cntr=0.3,0.1

Type RM Length L Ch R = 1 ,272759  ,282,282,282
BEGIN DESCRIPTION:
LAGARTO CREEK 256.0
END DESCRIPTION:
XS GIS Cut Line= 5
     2167437.561    13219749.394     2167290.972    13218855.545
     2166946.405    13217081.664     2166725.051    13216651.976
      2165462.03     13215935.83
#Sta/Elev= 30
    3000441.5771 3723.95438.3361 4221.78432.9724 4650.88431.6506 4980.18429.5932
 5010.12429.8228 5099.93429.4838 5598.88428.1424 5628.82430.1829 5648.77435.2225
 5698.67427.7447 5778.46 426.703 5788.43426.2892 5808.37420.1067 5838.28415.7152
 5908.07415.7152 5937.98415.7152 5977.86423.3632  5997.8424.9486 6037.68426.5929
  6097.5432.5319 6127.41423.0346 6147.35422.0505 6177.26423.9377 6187.23426.4856
 6237.05427.7162 7102.53436.0909 7639.72447.2887 7659.61446.7198 7669.56444.3866
#Mann= 7 ,-1 , 0
    3000      .1       0 4650.88     .05       0 4980.18    .033       0
 5010.12     .05       0 5099.93      .1       0 5908.07     .08       0
  5997.8      .1       0
Bank Sta=5778.46,6037.68
XS Rating Curve= 0 ,0
Exp/Cntr=0.3,0.1

Type RM Length L Ch R = 1 ,272477  ,333,333,333
BEGIN DESCRIPTION:
LAGARTO CREEK 255.0
END DESCRIPTION:
XS GIS Cut Line= 4
      2167545.36     13219959.24       2167258.9     13217003.54
      2166933.38     13216534.79      2165397.53     13215441.47
#Sta/Elev= 30
  1687.1  444.75  1980.9  442.82    2808  436.87    3297  431.46  4614.4  426.55
  4649.5  426.35  4652.2  425.85  4655.5  426.35  4698.9  433.76  4719.8  432.28
  4724.1   434.8  4727.5  435.86  4749.5  434.19  4755.6  437.07  4776.6  437.89
  4806.3   435.4  4812.4  438.06  4842.1  434.38  4848.1  438.32  5053.9   437.8
  5086.5  438.19  5096.2  436.95  5151.8  436.75    5173  433.89  5179.1   429.3
  5218.8  426.98  5387.7  430.97    5693  432.74  5749.4   433.7  7112.6  448.46
#Mann= 13 ,-1 , 0
  1687.1      .1       0  1980.9     .05       0    2808      .1       0
  4614.4     .05       0  4649.5     .03       0  4655.5     .05       0
  4724.1      .1       0  4727.5     .05       0  5053.9      .1       0
  5096.2     .05       0  5218.8      .1       0    5693     .08       0
  5749.4      .1       0
#XS Ineff= 2 , 0
       0 4754.55  437.14 5120.45       0  437.83
Permanent Ineff=
       T       T
Bank Sta=4776.6,5086.5
XS Rating Curve= 0 ,0
Exp/Cntr=0.3,0.1

Type RM Length L Ch R = 1 ,272144  ,786,786,786
BEGIN DESCRIPTION:
LAGARTO CREEK 254.0
END DESCRIPTION:
XS GIS Cut Line= 4
      2167727.65     13219581.64      2167701.61     13217420.21
      2167154.74     13216157.18      2165567.27     13215051.16
#Sta/Elev= 30
  1886.7  442.26  1891.6  442.26  2301.5  443.44  2861.6  433.33  3161.6  430.35
  4182.7  427.69  4595.3  424.93  4671.2     425    4684  426.31  4752.5  424.51
  4898.8  424.48  4912.8  424.48  4967.3  423.52  4974.5  421.74  5003.7  423.62
  5010.9  424.25    5109   424.9    5150  427.46  5516.9  437.83  5537.8   439.6
  5639.1  440.09  5645.2  442.45    5660  441.47  5774.4  442.32  5847.6  444.88
  6163.5  441.44  6312.7  441.11  6729.8   445.7  6837.1  444.59  7359.4  446.62
#Mann= 6 ,-1 , 0
  1886.7     .05       0  1891.6     .12       0  4898.8     .07       0
  5003.7     .12       0  7359.4      .1       0  7359.4      .1       0
Bank Sta=4912.8,5010.9
XS Rating Curve= 0 ,0
Exp/Cntr=0.3,0.1

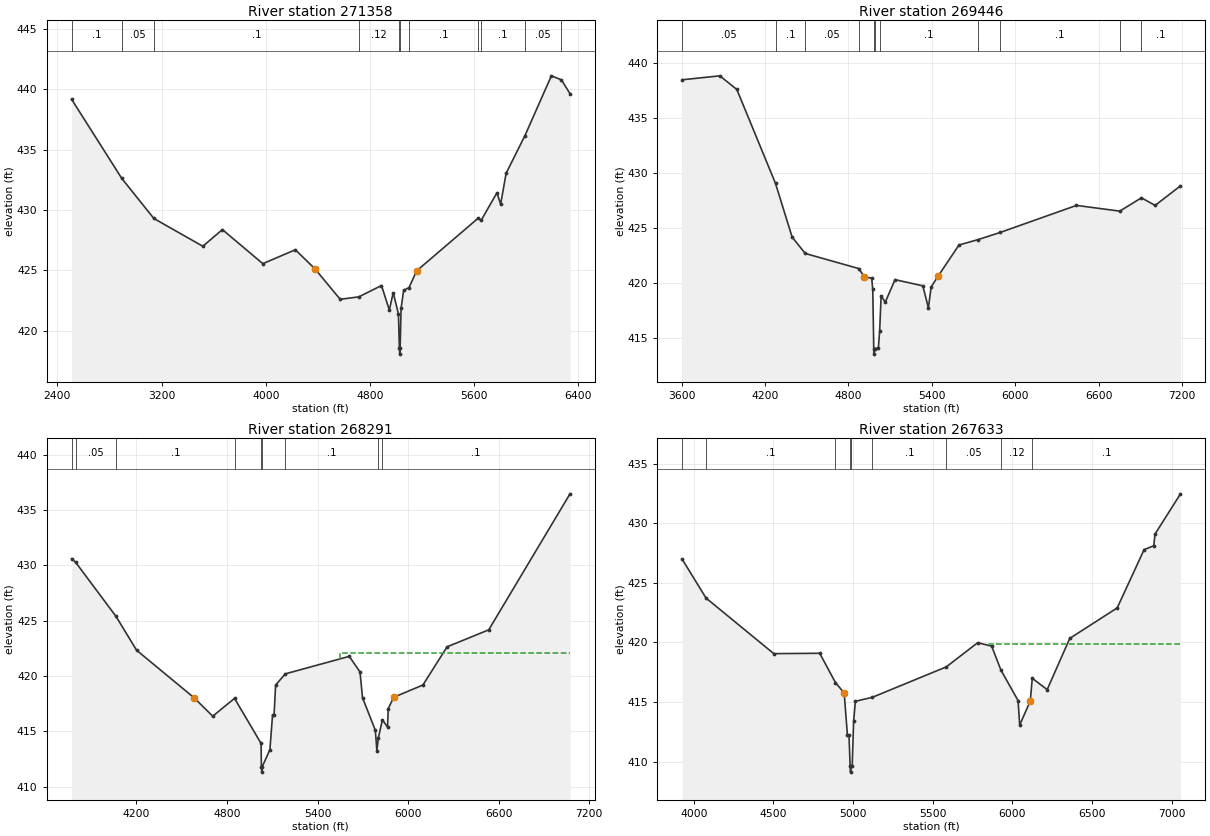
Type RM Length L Ch R = 1 ,271358  ,1912,1912,1912
BEGIN DESCRIPTION:
Mapping XS 5cea5f6b
END DESCRIPTION:
XS GIS Cut Line= 4
      2167997.43     13219033.96      2167943.17      13217330.4
      2168008.28     13216147.67      2167313.86     13215518.35
#Sta/Elev= 30
  2509.5  439.17  2895.1  432.61  3141.2   429.3  3517.1     427  3667.2  428.38
  3977.4  425.56  4227.5  426.71  4377.7  425.13  4571.3  422.61  4714.1  422.81
  4888.5  423.75  4948.6  421.72  4978.6  423.16  5018.7  421.39  5025.7  418.57
  5028.5  418.07  5031.7  418.57  5038.7  421.85  5058.7  423.36  5099.3  423.57
  5158.9  424.97    5628   429.3  5654.7  429.17  5774.9  431.43  5803.2  430.48
  5845.1  433.04  5989.7  436.16  6192.5  441.11  6269.4  440.78  6335.6  439.63
#Mann= 11 ,-1 , 0
  2509.5      .1       0  2895.1     .05       0  3141.2      .1       0
  4714.1     .12       0  5025.7     .07       0  5031.7     .12       0
  5099.3      .1       0    5628     .08       0  5654.7      .1       0
  5989.7     .05       0  6269.4      .1       0
Bank Sta=4377.7,5158.9
XS Rating Curve= 0 ,0
Exp/Cntr=0.3,0.1

Type RM Length L Ch R = 1 ,269446  ,1155,1155,1155
BEGIN DESCRIPTION:
LAGARTO CREEK 253.0
END DESCRIPTION:
XS GIS Cut Line= 3
      2169136.75     13218708.45      2169115.05      13216603.4
      2168031.33     13215595.54
#Sta/Elev= 30
  3603.7  438.45  3875.3  438.81  3997.5  437.57  4275.7  429.03  4395.3  424.15
  4489.8  422.66  4874.1  421.29  4915.4  420.54  4967.5  420.41  4975.4  419.39
  4982.4  414.01  4985.1  413.51  4988.4  414.01  5015.4  414.07  5024.9   415.6
  5035.4   418.8  5065.4  418.24  5135.4  420.28  5335.4  419.72  5375.4  417.72
  5395.4  419.62  5445.4   420.6  5595.4  423.43  5732.5  423.92  5893.6  424.58
  6440.6  427.03  6751.9  426.51  6907.9  427.72  7006.3  427.03  7188.8  428.81
#Mann= 11 ,-1 , 0
  3603.7     .05       0  4275.7      .1       0  4489.8     .05       0
  4874.1     .12       0  4982.4     .07       0  4988.4     .12       0
  5024.9      .1       0  5732.5     .05       0  5893.6      .1       0
  6751.9     .08       0  6907.9      .1       0
Bank Sta=4915.4,5445.4
XS Rating Curve= 0 ,0
Exp/Cntr=0.3,0.1

Type RM Length L Ch R = 1 ,268291  ,658,658,658
BEGIN DESCRIPTION:
LAGARTO CREEK 252.0
END DESCRIPTION:
XS GIS Cut Line= 4
      2169489.78     13218379.61      2169867.36     13217637.46
      2170192.88     13215840.58      2170271.01     13215202.56
#Sta/Elev= 30
  3770.7  430.61  3797.4  430.29  4065.2  425.39    4201  422.34  4581.6  418.04
  4705.6  416.37    4850  417.98  5025.9  413.91    5028  411.81  5030.8  411.31
    5034  411.81  5084.5  413.35    5102   416.5  5112.1   416.5  5122.3  419.19
  5186.9   420.2  5610.1  421.78  5681.3  420.37  5697.9  418.04  5782.9  415.09
    5793  413.25  5803.2  414.44  5829.7  416.04  5863.4  415.39  5868.4  417.06
  5904.8  418.08  6097.9  419.19  6257.9  422.64    6534  424.18  7072.3  436.48
#Mann= 9 ,-1 , 0
  3770.7      .1       0  3797.4     .05       0  4065.2      .1       0
    4850     .12       0    5028     .07       0    5034     .12       0
  5186.9      .1       0  5803.2     .12       0  5829.7      .1       0
#XS Ineff= 2 , 0
                         5547.73          422.05
Permanent Ineff=
       F       F
Bank Sta=4581.6,5904.8
XS Rating Curve= 0 ,0
Exp/Cntr=0.3,0.1

Type RM Length L Ch R = 1 ,267633  ,672,672,672
BEGIN DESCRIPTION:
LAGARTO CREEK 251.0
END DESCRIPTION:
XS GIS Cut Line= 3
      2170362.16     13218640.03      2170492.36     13217246.83
      2170778.76     13215541.48
#Sta/Elev= 30
  3926.5     427  4076.7  423.73  4502.2  419.06  4790.3  419.09  4889.3  416.63
  4944.1  415.75  4964.2  412.24  4974.2  412.24  4981.3  409.61    4984  409.11
  4987.3  409.61  4994.3  409.61  5003.3  413.39  5014.4  415.06  5120.3  415.39
  5585.3  417.95    5782  419.98  5869.8  419.69  5927.8  417.68  6035.5  415.12
  6045.7  413.06  6112.2  415.09  6124.7  416.99  6218.1  416.04    6360  420.34
  6657.7   422.9  6826.5  427.79  6887.3  428.12  6895.1   429.1    7055  432.48
#Mann= 9 ,-1 , 0
  3926.5     .05       0  4076.7      .1       0  4889.3     .12       0
  4981.3     .07       0  4987.3     .12       0  5120.3      .1       0
  5585.3     .05       0  5927.8     .12       0  6124.7      .1       0
#XS Ineff= 2 , 0
                            5850          419.91
Permanent Ineff=
       F       F
Bank Sta=4944.1,6112.2
XS Rating Curve= 0 ,0
Exp/Cntr=0.3,0.1