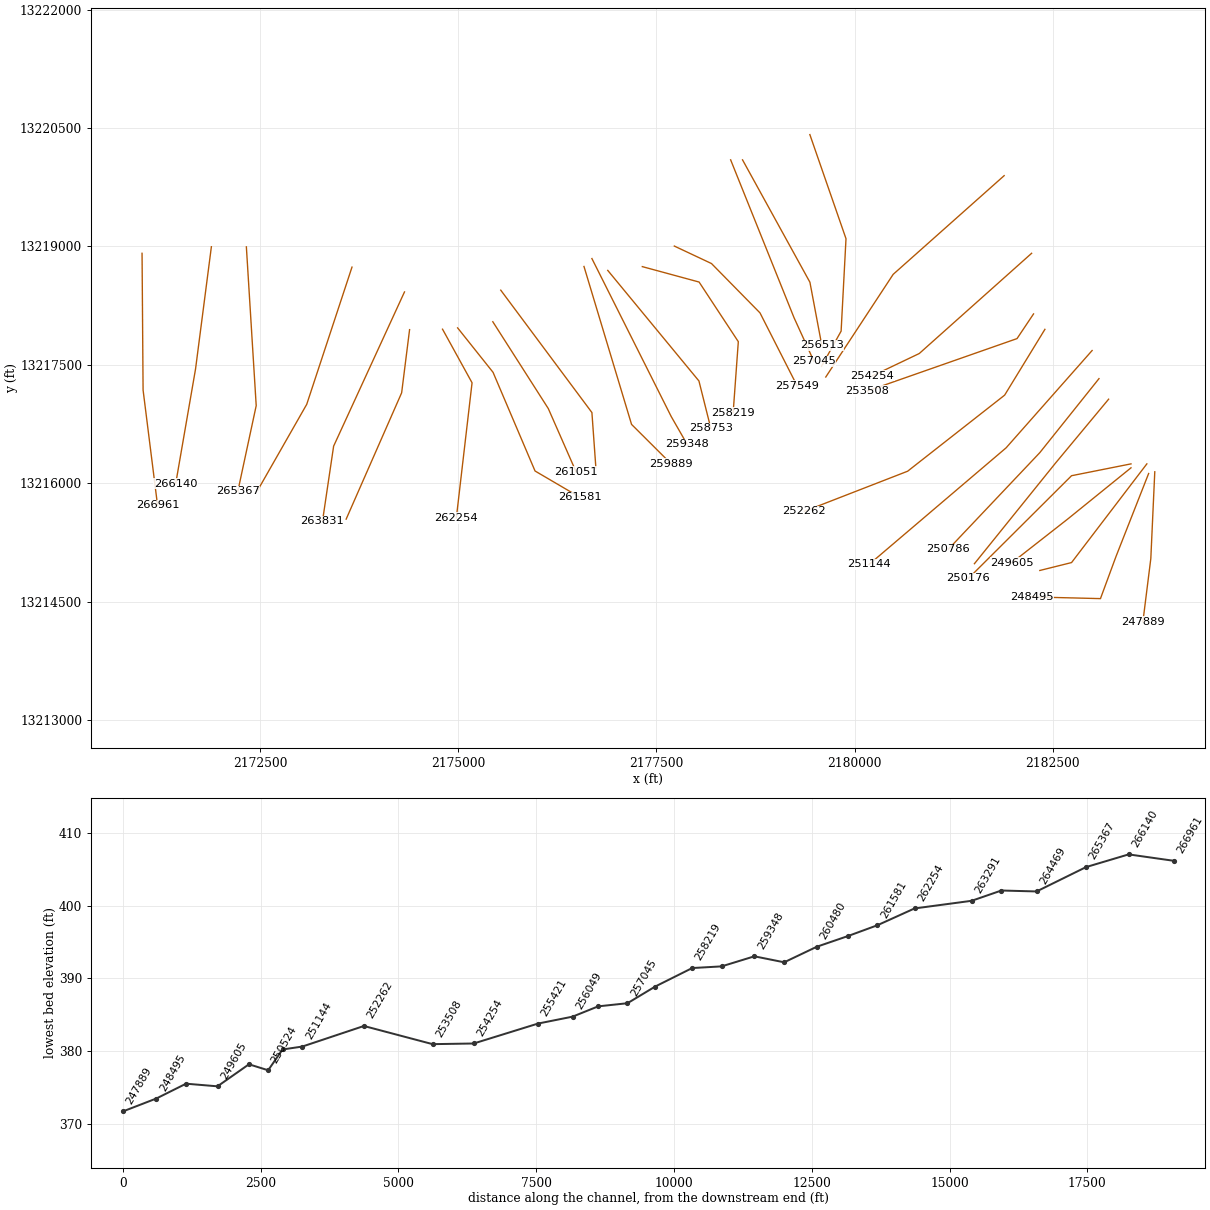
HEC-RAS study LAGARTO CREEK.prj: LAGARTO CREEK Base Level Engineering

--- LAGARTO CREEK.g01 (geometry) --- (continued)

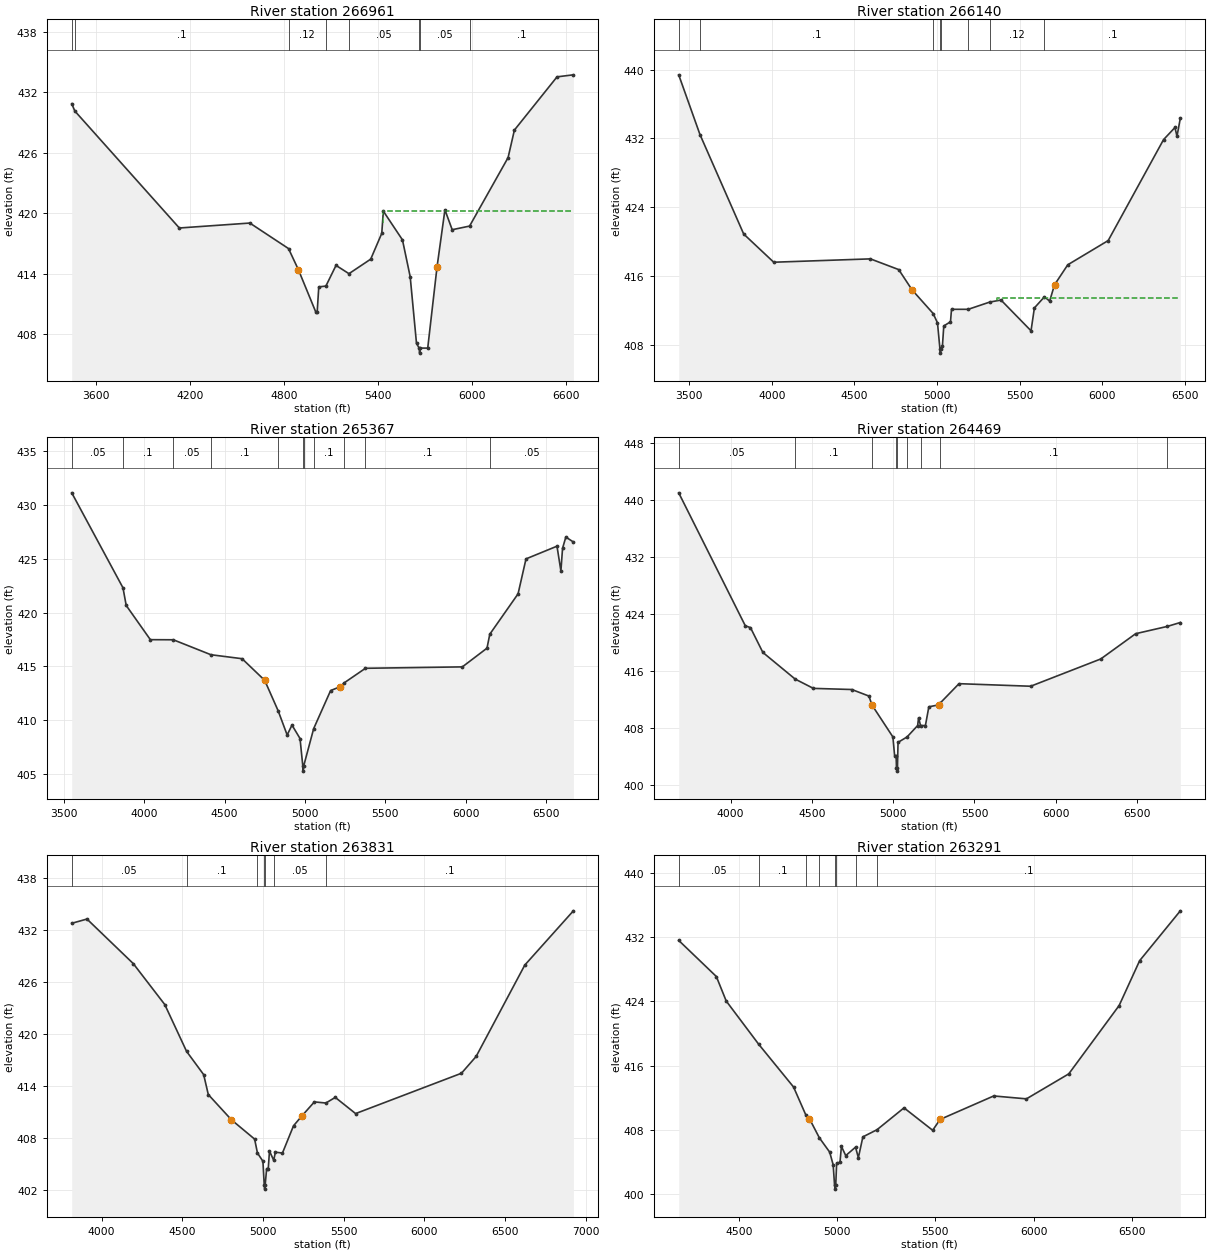
Type RM Length L Ch R = 1 ,266961  ,821,821,821
BEGIN DESCRIPTION:
LAGARTO CREEK 250.0
END DESCRIPTION:
XS GIS Cut Line= 3
       2171013.2     13218913.45      2171026.22     13217181.73
      2171208.51     13215723.35
#Sta/Elev= 30
  3446.2  430.87  3465.8  430.14  4132.8  418.54  4582.8  419.03  4829.6   416.5
  4892.8   414.4  5002.8  410.24  5012.8  410.24  5022.8   412.7  5068.2  412.78
  5132.8  414.83  5215.5  414.01  5354.2  415.45  5424.8  418.01  5434.8  420.21
  5556.9  417.36  5606.2  413.71  5646.5  407.09  5663.6  406.63  5666.4  406.13
  5669.6  406.63  5718.1  406.63  5777.5  414.67  5827.9  420.34  5874.3  418.37
  5985.3  418.73    6231  425.52  6271.3  428.25  6543.4  433.53  6647.7  433.73
#Mann= 8 ,-1 , 0
  3446.2     .05       0  3465.8      .1       0  4829.6     .12       0
  5068.2      .1       0  5215.5     .05       0  5663.6     .07       0
  5669.6     .05       0  5985.3      .1       0
#XS Ineff= 2 , 0
                         5429.55          420.21
Permanent Ineff=
       F       F
Bank Sta=4892.8,5777.5
XS Rating Curve= 0 ,0
Exp/Cntr=0.3,0.1

Type RM Length L Ch R = 1 ,266140  ,773,773,773
BEGIN DESCRIPTION:
LAGARTO CREEK 249.0
END DESCRIPTION:
XS GIS Cut Line= 3
      2171887.71     13218996.81      2171687.72     13217446.85
      2171437.72     13215996.85
#Sta/Elev= 30
  3437.2   439.4    3566  432.44  3830.4  420.87  4011.9  417.59  4596.7  417.98
  4768.1  416.73  4848.8  414.37  4976.3  411.62  5002.5  410.53  5017.3  407.51
    5020  407.01  5023.3  407.51  5032.5  407.87  5040.6  410.17  5081.2  410.66
  5087.3  412.11  5188.6  412.11  5318.2  412.95  5386.6  413.19  5568.3  409.61
  5588.6  412.27  5649.7  413.57  5680.9  413.06  5710.3  414.96  5790.5  417.29
    6035  420.11  6369.9  431.86  6438.9  433.27  6451.1  432.25  6471.4  434.35
#Mann= 8 ,-1 , 0
  3437.2     .05       0    3566      .1       0  4976.3     .12       0
  5017.3     .07       0  5023.3     .12       0  5188.6      .1       0
  5318.2     .12       0  5649.7      .1       0
#XS Ineff= 2 , 0
                         5364.49          413.37
Permanent Ineff=
       F       F
Bank Sta=4848.8,5710.3
XS Rating Curve= 0 ,0
Exp/Cntr=0.3,0.1

Type RM Length L Ch R = 1 ,265367  ,898,898,898
BEGIN DESCRIPTION:
LAGARTO CREEK 248.0
END DESCRIPTION:
XS GIS Cut Line= 3
      2172329.01      13218995.2      2172453.15     13216984.19
      2172221.63     13215900.99
#Sta/Elev= 30
  3548.9  431.14  3867.8  422.31  3887.9  420.67  4038.2  417.49  4181.2  417.48
  4415.2  416.09  4609.3  415.72  4749.9  413.71  4833.4  410.89  4889.8  408.63
  4919.8  409.55  4969.9   408.3    4987  405.77  4989.7  405.27    4993  405.77
  5054.8  409.22  5160.3  412.76  5220.4  413.12  5245.2  413.48  5377.1  414.83
  5980.3  414.96  6133.7   416.7  6151.2     418  6327.1  421.75  6376.5     425
  6569.4  426.18  6593.8  423.88    6604  425.98  6624.5  427.03  6671.4  426.57
#Mann= 11 ,-1 , 0
  3548.9     .05       0  3867.8      .1       0  4181.2     .05       0
  4415.2      .1       0  4833.4     .12       0    4987     .07       0
    4993     .12       0  5054.8      .1       0  5245.2     .05       0
  5377.1      .1       0  6151.2     .05       0
Bank Sta=4749.9,5220.4
XS Rating Curve= 0 ,0
Exp/Cntr=0.3,0.1

Type RM Length L Ch R = 1 ,264469  ,638,638,638
BEGIN DESCRIPTION:
LAGARTO CREEK 246.0
END DESCRIPTION:
XS GIS Cut Line= 3
       2173661.4     13218738.63      2173090.38     13217000.74
       2172469.7     13215908.35
#Sta/Elev= 30
  3680.5  441.01  4090.2  422.34    4122  422.08  4198.1   418.6  4396.6  414.86
  4508.9  413.55  4745.5  413.39  4850.7  412.47  4869.2  411.22  4998.1  406.73
  5008.6   404.1  5017.8   404.1  5020.1  402.43  5022.8  401.93  5026.1  402.43
  5029.7  405.97  5085.2  406.73  5150.3  408.33    5156  409.42  5168.1  408.33
  5198.1  408.33  5219.2  410.96  5282.8  411.25  5288.2  411.47  5404.8  414.21
  5845.6  413.85  6276.7  417.68  6491.5  421.23  6685.8  422.25  6766.2   422.8
#Mann= 9 ,-1 , 0
  3680.5     .05       0  4396.6      .1       0  4869.2     .12       0
  5020.1     .07       0  5026.1     .12       0  5085.2      .1       0
  5168.1     .05       0  5288.2      .1       0  6685.8     .05       0
Bank Sta=4869.2,5282.8
XS Rating Curve= 0 ,0
Exp/Cntr=0.3,0.1

Type RM Length L Ch R = 1 ,263831  ,540,540,540
BEGIN DESCRIPTION:
LAGARTO CREEK 245.0
END DESCRIPTION:
XS GIS Cut Line= 3
      2174323.48      13218424.2      2173429.69     13216471.09
      2173289.18     13215520.63
#Sta/Elev= 30
  3815.2  432.78  3909.5  433.27  4196.6  428.12  4391.7  423.39  4526.8  417.98
  4632.8  415.29  4661.4  412.99  4804.9  410.07  4948.5  407.84  4966.1  406.23
    5000  405.28    5008  402.56  5010.7  402.06    5014  402.56    5023  404.43
    5033  404.43  5040.6  406.46  5066.9  405.39    5077  406.33    5121  406.23
  5189.6  409.38  5241.9  410.53  5318.9  412.14  5389.9  412.01  5448.3  412.66
  5574.3  410.79  6230.2  415.45  6321.2  417.39  6622.8  427.95  6923.9  434.22
#Mann= 7 ,-1 , 0
  3815.2     .05       0  4526.8      .1       0  4966.1     .12       0
    5008     .07       0    5014     .12       0  5066.9     .05       0
  5389.9      .1       0
Bank Sta=4804.9,5241.9
XS Rating Curve= 0 ,0
Exp/Cntr=0.3,0.1

Type RM Length L Ch R = 1 ,263291  ,1037,1037,1037
BEGIN DESCRIPTION:
LAGARTO CREEK 244.0
END DESCRIPTION:
XS GIS Cut Line= 3
      2174387.72     13217946.83      2174287.72     13217146.85
      2173587.73     13215546.88
#Sta/Elev= 30
  4193.8  431.59  4385.3   427.1  4435.6  424.05  4601.2  418.66  4778.3  413.35
  4840.6  409.88  4858.9  409.42  4909.6  407.03  4962.2  405.25  4979.8  403.67
  4986.9  401.15  4989.7  400.65  4992.9  401.15  4997.5   403.9  5014.4  403.97
  5021.8  405.97  5043.7  404.82  5093.6  405.87    5108  404.56    5131  407.15
  5202.9  408.04  5340.3  410.76  5486.1  407.97  5523.9  409.32  5796.8  412.24
  5963.3  411.88  6178.8  414.99    6435  423.49  6539.4  429.07  6746.4  435.27
#Mann= 8 ,-1 , 0
  4193.8     .05       0  4601.2      .1       0  4840.6     .05       0
  4909.6      .1       0  4986.9     .07       0  4992.9      .1       0
  5093.6     .05       0  5202.9      .1       0
Bank Sta=4858.9,5523.9
XS Rating Curve= 0 ,0
Exp/Cntr=0.3,0.1

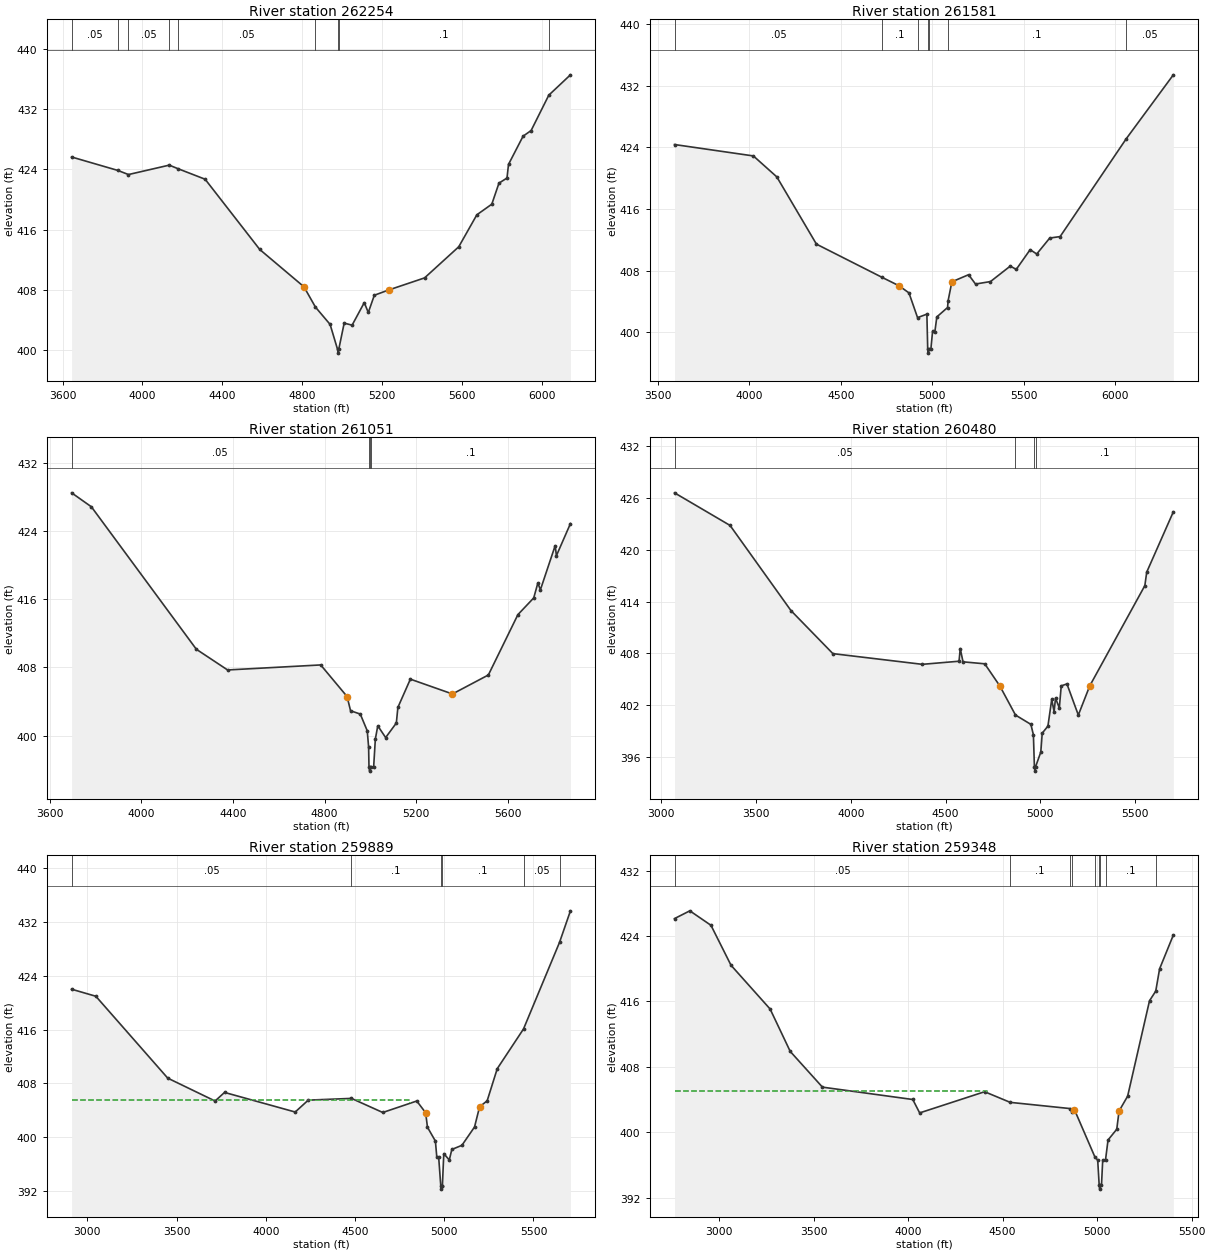
Type RM Length L Ch R = 1 ,262254  ,673,673,673
BEGIN DESCRIPTION:
LAGARTO CREEK 243.0
END DESCRIPTION:
XS GIS Cut Line= 3
      2174803.47     13217952.42      2175175.87     13217273.84
      2174977.31     13215561.26
#Sta/Elev= 30
  3645.1  425.62  3877.4  423.83  3929.8  423.29  4134.1  424.54  4175.7  424.09
  4313.7  422.67  4587.3  413.35  4808.7   408.4  4866.1  405.71  4939.6  403.41
  4976.9   400.1  4979.6   399.6  4982.9   400.1  5010.1  403.58  5049.8  403.31
  5110.7   406.3  5130.9  404.99  5161.1  407.28  5232.2  407.97  5412.7  409.58
  5583.9  413.71  5674.5  417.95  5749.4  419.36  5785.2  422.15  5825.5  422.83
  5833.1  424.64    5906  428.38  5946.3  429.13  6034.8  433.82  6143.2  436.52
#Mann= 9 ,-1 , 0
  3645.1     .05       0  3877.4      .1       0  3929.8     .05       0
  4134.1      .1       0  4175.7     .05       0  4866.1      .1       0
  4976.9     .07       0  4982.9      .1       0  6034.8     .05       0
Bank Sta=4808.7,5232.2
XS Rating Curve= 0 ,0
Exp/Cntr=0.3,0.1

Type RM Length L Ch R = 1 ,261581  ,530,530,530
BEGIN DESCRIPTION:
LAGARTO CREEK 242.0
END DESCRIPTION:
XS GIS Cut Line= 4
      2174993.82     13217968.97      2175440.69     13217406.25
      2175970.34     13216156.61       2176532.9     13215825.69
#Sta/Elev= 30
    3590  424.38  4021.4   422.9  4149.6  420.18  4366.3  411.45  4726.8  407.12
  4818.4  406.04  4872.4  405.12  4919.4  401.91  4970.4  402.36    4975   397.8
  4977.7   397.3    4981   397.8  4992.2   397.8  5001.6  400.13  5013.9  400.03
  5024.8     402  5083.5  403.22  5086.7  404.12  5107.2  406.56  5198.5  407.48
  5236.4  406.27  5318.3  406.59  5426.6   408.6  5459.2  408.17  5535.2  410.73
  5571.3  410.17  5642.4  412.24  5699.2  412.43  6060.2  425.11  6318.5  433.43
#Mann= 7 ,-1 , 0
    3590     .05       0  4726.8      .1       0  4919.4     .12       0
    4975     .07       0    4981     .12       0  5086.7      .1       0
  6060.2     .05       0
Bank Sta=4818.4,5107.2
XS Rating Curve= 0 ,0
Exp/Cntr=0.3,0.1

Type RM Length L Ch R = 1 ,261051  ,571,571,571
BEGIN DESCRIPTION:
LAGARTO CREEK 241.0
END DESCRIPTION:
XS GIS Cut Line= 3
      2175437.74     13218046.82      2176137.72     13216946.85
      2176487.72     13216146.87
#Sta/Elev= 30
  3696.2  428.51  3782.5  426.87  4240.6  410.14  4376.9  407.71  4783.3   408.3
  4898.4  404.59  4913.6  402.92    4956  402.53  4986.5  400.56  4992.4  398.65
    4994  396.33  4996.8  395.83    5000  396.33  5001.9  396.33  5014.4  396.33
  5021.8  399.61  5032.4  401.15  5066.7  399.77  5113.4  401.48  5120.1  403.31
  5174.6  406.63  5358.3  404.89    5515  407.12    5644  414.21    5713  416.17
  5730.9  417.91  5742.2  417.13  5806.6  422.31    5812  421.13  5873.2   424.9
#Mann= 4 ,-1 , 0
  3696.2     .05       0    4994     .03       0    5000     .05       0
  5001.9      .1       0
Bank Sta=4898.4,5358.3
XS Rating Curve= 0 ,0
Exp/Cntr=0.3,0.1

Type RM Length L Ch R = 1 ,260480  ,591,591,591
BEGIN DESCRIPTION:
LAGARTO CREEK 240.0
END DESCRIPTION:
XS GIS Cut Line= 3
      2175537.74     13218446.83      2176687.72     13216896.85
      2176737.72     13216196.84
#Sta/Elev= 30
    3070  426.61  3363.1  422.83  3684.4  412.96  3905.6  407.97  4377.4  406.73
  4571.2  407.09  4577.5  408.56  4592.1  407.02  4706.8  406.79  4786.2  404.23
    4869  400.85  4950.2  399.77  4963.5  398.56  4968.8  394.85  4971.6  394.35
  4974.8  394.85  5002.5  396.56    5010  398.75  5040.1  399.57  5060.2  402.66
  5072.7  401.25  5080.2  402.82  5100.3  401.67  5110.3  404.23  5140.4  404.46
  5200.5  400.85  5260.7  404.23  5551.4  415.85  5561.4  417.42  5701.8  424.41
#Mann= 4 ,-1 , 0
    3070     .05       0    4869      .1       0  4968.8     .07       0
  4974.8      .1       0
Bank Sta=4786.2,5260.7
XS Rating Curve= 0 ,0
Exp/Cntr=0.3,0.1

Type RM Length L Ch R = 1 ,259889  ,541,541,541
BEGIN DESCRIPTION:
LAGARTO CREEK 239.0
END DESCRIPTION:
XS GIS Cut Line= 3
      2176587.71     13218746.89      2177187.72     13216746.86
      2177687.72     13216246.86
#Sta/Elev= 30
  2911.9  422.01  3047.7  420.96  3450.5  408.76  3715.8  405.35  3768.9  406.63
  4164.8  403.71  4237.9  405.48  4480.1  405.74  4655.5  403.64    4846  405.35
  4895.6  403.61    4906  401.44  4950.4  399.38  4958.2  397.01  4968.7  397.01
  4980.5  392.72  4983.2  392.22  4986.5  392.72  4989.6  392.72  4997.4  397.51
  5028.3  396.56  5042.4  398.13    5099  398.75  5169.7  401.48    5198  404.49
  5240.4  405.38    5297  410.17  5444.2  416.09  5645.8  428.98  5707.1  433.69
#Mann= 6 ,-1 , 0
  2911.9     .05       0  4480.1      .1       0  4980.5     .07       0
  4986.5      .1       0  5444.2     .05       0  5645.8     .08       0
#XS Ineff= 2 , 0
          4810.8  405.46
Permanent Ineff=
       F       F
Bank Sta=4895.6,5198
XS Rating Curve= 0 ,0
Exp/Cntr=0.3,0.1

Type RM Length L Ch R = 1 ,259348  ,595,595,595
BEGIN DESCRIPTION:
LAGARTO CREEK 238.0
END DESCRIPTION:
XS GIS Cut Line= 3
      2176687.71     13218846.88      2177687.72     13216846.85
      2177887.71     13216496.87
#Sta/Elev= 30
  2763.9  426.12    2845  427.07  2956.8   425.3    3063  420.41  3269.8  415.06
  3376.1  409.88  3546.6  405.51  4024.5     404  4060.9  402.36  4404.6  404.95
  4539.9  403.65    4857  402.89  4866.3  402.49  4879.8  402.76  4988.5  396.95
  5002.9  396.59  5010.7  393.54  5013.4  393.04  5016.7  393.54    5023  393.54
  5029.5  396.62  5044.3  396.62  5057.6  399.05  5103.7  400.36  5115.9  402.59
  5161.2   404.4  5277.1  416.08    5310  417.25  5330.4  419.98  5403.1  424.11
#Mann= 9 ,-1 , 0
  2763.9     .05       0  4539.9      .1       0    4857     .05       0
  4866.3      .1       0  4988.5     .12       0  5010.7     .07       0
  5016.7     .12       0  5044.3      .1       0    5310     .08       0
#XS Ineff= 2 , 0
         4417.61  405.02
Permanent Ineff=
       F       F
Bank Sta=4879.8,5115.9
XS Rating Curve= 0 ,0
Exp/Cntr=0.3,0.1

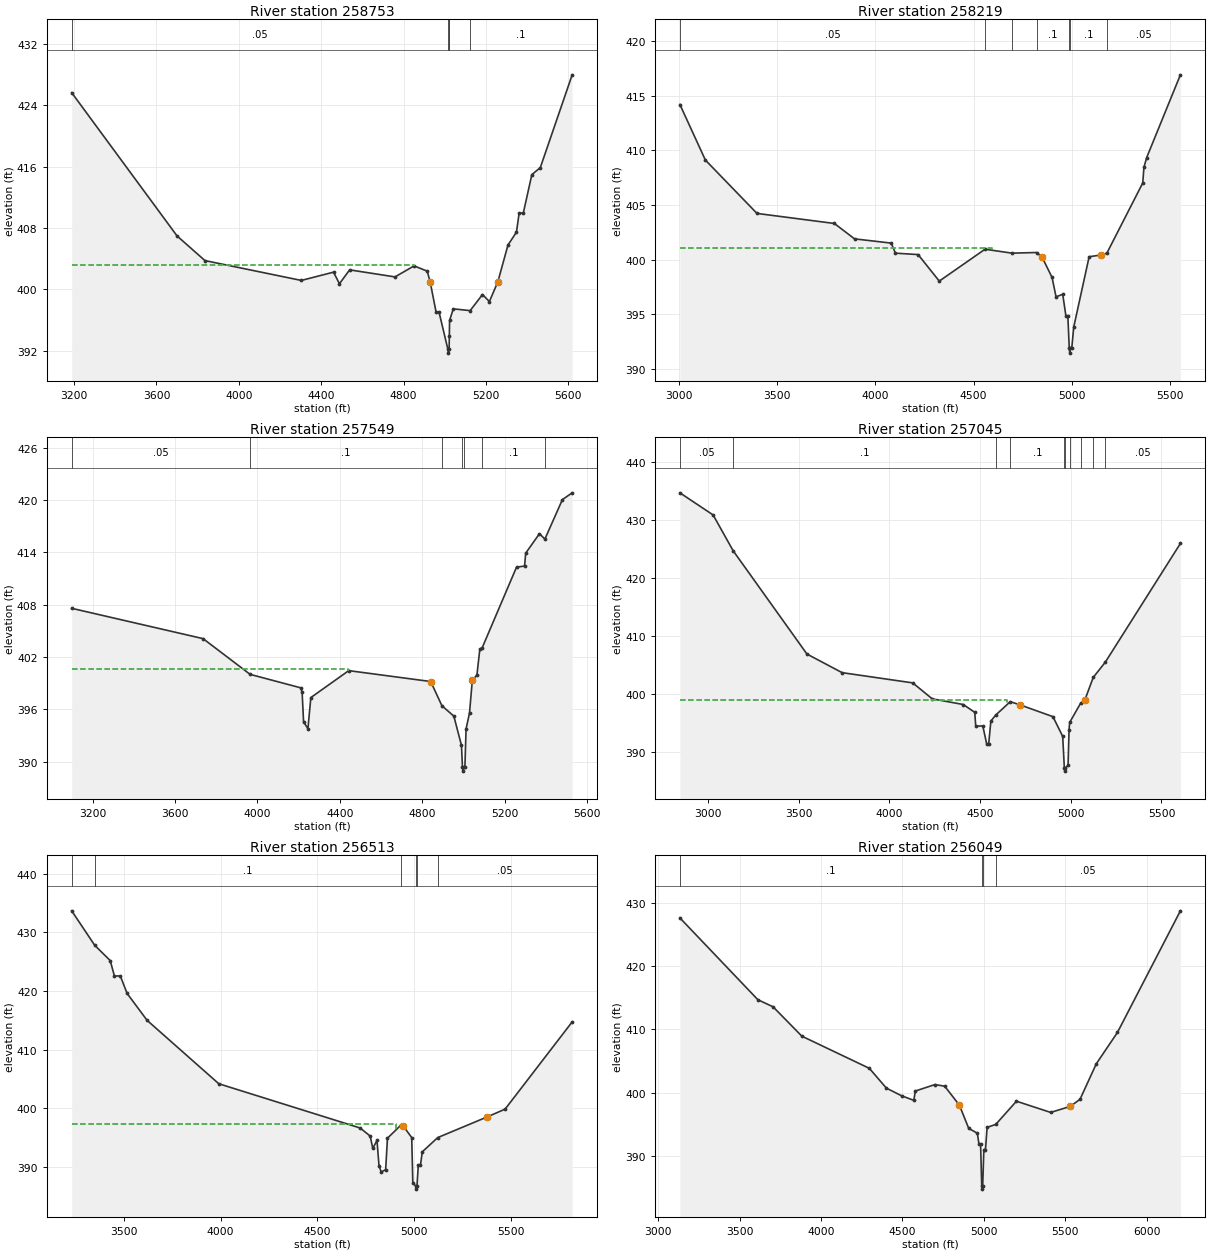
Type RM Length L Ch R = 1 ,258753  ,534,534,534
BEGIN DESCRIPTION:
LAGARTO CREEK 237.0
END DESCRIPTION:
XS GIS Cut Line= 3
       2176887.7     13218696.88      2178037.72     13217296.85
      2178187.73     13216696.82
#Sta/Elev= 30
  3188.2  425.66  3699.8  406.96  3835.3  403.74  4303.3  401.15  4459.7  402.23
  4488.4  400.72  4537.9  402.53  4758.2  401.61  4850.8  403.05  4914.6  402.36
    4929  400.95  4957.7  397.01    4972  397.01    5015  392.16  5017.8  391.66
    5021  392.16    5022  393.87  5023.2  395.93  5041.2  397.44  5123.1  397.21
    5183  399.31  5216.5  398.39  5257.7  400.98  5306.7  405.77  5347.9  407.45
  5360.8  409.91  5381.4  409.97  5422.6  414.96  5463.8  415.88  5618.5  427.99
#Mann= 5 ,-1 , 0
  3188.2     .05       0    5015     .03       0    5021     .05       0
    5022     .12       0  5123.1      .1       0
#XS Ineff= 2 , 0
         4849.43  403.17
Permanent Ineff=
       F       F
Bank Sta=4929,5257.7
XS Rating Curve= 0 ,0
Exp/Cntr=0.3,0.1

Type RM Length L Ch R = 1 ,258219  ,670,670,670
BEGIN DESCRIPTION:
LAGARTO CREEK 236.0
END DESCRIPTION:
XS GIS Cut Line= 4
       2177323.6     13218744.83       2178039.7     13218549.53
      2178534.49     13217794.32      2178469.39      13216895.9
#Sta/Elev= 30
  3006.5  414.21  3136.1  409.12  3398.7  404.23  3792.3  403.31  3894.8   401.9
  4081.7  401.51  4102.8  400.59  4218.2  400.46  4325.9  398.03  4558.6  400.95
  4696.1  400.59  4820.7  400.65  4849.6   400.2  4899.7  398.36  4919.8  396.59
  4953.9  396.82  4969.9  394.85  4979.9  394.85    4987  391.93  4989.7  391.43
    4993  391.93    5000  391.93    5010  393.83  5088.2  400.26  5150.4  400.43
  5178.4  400.59  5360.9  407.02    5367  408.46    5381  409.35  5552.4  416.93
#Mann= 7 ,-1 , 0
  3006.5     .05       0  4558.6      .1       0  4696.1     .05       0
  4820.7      .1       0    4987     .07       0    4993      .1       0
  5178.4     .05       0
#XS Ineff= 2 , 0
         4592.05  401.08
Permanent Ineff=
       F       F
Bank Sta=4849.6,5150.4
XS Rating Curve= 0 ,0
Exp/Cntr=0.3,0.1

Type RM Length L Ch R = 1 ,257549  ,504,504,504
BEGIN DESCRIPTION:
LAGARTO CREEK 235.0
END DESCRIPTION:
XS GIS Cut Line= 4
      2177727.23     13219005.24      2178195.95      13218783.9
      2178807.93      13218158.9      2179276.68     13217234.43
#Sta/Elev= 30
  3098.8  407.58  3736.6   404.1  3965.2     400  4210.3  398.46  4217.3     398
  4224.5  394.55  4245.6  393.77  4259.8  397.34  4443.7  400.43  4841.7  399.18
  4896.1   396.4  4953.9  395.21    4991  391.86  4995.7   389.4  4998.5   388.9
  5001.7   389.4  5007.7   389.4  5013.3  393.73    5030  395.57  5043.6  399.31
    5066  399.93  5080.1  402.89  5091.7  403.06  5258.2   412.3  5297.2  412.43
  5302.8  413.91  5369.6  416.14  5395.9  415.52  5480.9  420.05  5528.4  420.83
#Mann= 7 ,-1 , 0
  3098.8     .05       0  3965.2      .1       0  4896.1     .12       0
  4995.7     .07       0  5001.7     .12       0  5091.7      .1       0
  5395.9     .05       0
#XS Ineff= 2 , 0
         4442.05  400.57
Permanent Ineff=
       F       F
Bank Sta=4841.7,5043.6
XS Rating Curve= 0 ,0
Exp/Cntr=0.3,0.1

Type RM Length L Ch R = 1 ,257045  ,532,532,532
BEGIN DESCRIPTION:
LAGARTO CREEK 234.0
END DESCRIPTION:
XS GIS Cut Line= 3
      2178437.71     13220096.89      2179237.72     13218096.85
      2179487.74     13217546.81
#Sta/Elev= 30
  2845.9  434.74    3029  430.91  3139.4  424.72    3546  406.86  3739.9  403.64
    4129  401.87  4236.7  399.11  4407.6  398.13  4470.9  396.78  4476.3  394.39
  4515.3  394.42  4536.9  391.27  4547.6  391.27  4559.8  395.28  4585.9  396.29
  4666.6  398.62  4721.3  398.06  4901.7  396.03  4955.6  392.62  4964.7  387.11
  4967.4  386.61  4970.7  387.11  4985.2  387.66  4990.6  393.77  4994.2  395.04
  5053.9  398.33  5076.9  398.85  5123.9  402.82  5190.5  405.46  5604.2  425.98
#Mann= 10 ,-1 , 0
  2845.9     .05       0  3139.4      .1       0  4585.9     .12       0
  4666.6      .1       0  4964.7     .07       0  4970.7      .1       0
  4994.2     .12       0  5053.9     .05       0  5123.9      .1       0
  5190.5     .05       0
#XS Ineff= 2 , 0
         4647.73  398.92
Permanent Ineff=
       F       F
Bank Sta=4721.3,5076.9
XS Rating Curve= 0 ,0
Exp/Cntr=0.3,0.1

Type RM Length L Ch R = 1 ,256513  ,464,464,464
BEGIN DESCRIPTION:
LAGARTO CREEK 233.0
END DESCRIPTION:
XS GIS Cut Line= 3
       2178587.7     13220096.88      2179437.72     13218546.86
      2179587.71      13217746.9
#Sta/Elev= 30
  3232.2  433.69  3350.9  427.81  3430.8   425.2  3452.6  422.57  3483.1  422.57
    3518  419.59  3621.3  414.99    3991  404.17  4719.9  396.62  4771.9  395.24
  4785.3  393.14  4807.1  394.49  4817.5  390.16  4828.9  389.11  4851.7   389.5
  4861.1  394.88  4928.8  397.05  4942.6  396.95  4986.2  394.98  4991.9   387.3
  5007.2  386.68  5009.9  386.18  5013.2  386.68  5020.3  390.32  5031.4  390.32
  5040.7  392.55  5120.4  394.98  5376.4  398.52    5468  399.84  5813.9  414.73
#Mann= 6 ,-1 , 0
  3232.2     .05       0  3350.9      .1       0  4928.8     .12       0
  5007.2     .07       0  5013.2     .12       0  5120.4     .05       0
#XS Ineff= 2 , 0
         4907.39  397.27
Permanent Ineff=
       F       F
Bank Sta=4942.6,5376.4
XS Rating Curve= 0 ,0
Exp/Cntr=0.3,0.1

Type RM Length L Ch R = 1 ,256049  ,628,628,628
BEGIN DESCRIPTION:
LAGARTO CREEK 232.0
END DESCRIPTION:
XS GIS Cut Line= 4
      2179436.86     13220416.95      2179892.78     13219098.46
      2179831.17      13217927.8      2179584.69     13217484.15
#Sta/Elev= 30
  3132.9  427.59  3612.1  414.67  3705.6  413.55  3882.1  408.92  4296.9  403.84
  4401.4  400.72  4494.9  399.51  4569.7  398.79  4579.7  400.26  4699.8  401.28
  4759.9  401.02    4850  398.03  4907.4  394.36  4960.2   393.6  4970.2   391.9
  4980.2   391.9  4987.2  385.27    4990  384.77  4993.2  385.27  5000.3  391.01
  5010.3  391.01  5020.3  394.52  5073.1  394.98  5200.5  398.65  5410.8  396.88
    5531  397.83  5591.1  398.95  5691.2  404.56  5821.1  409.51  6207.8  428.71
#Mann= 4 ,-1 , 0
  3132.9      .1       0  4987.2     .07       0  4993.2      .1       0
  5073.1     .05       0
Bank Sta=4850,5531
XS Rating Curve= 0 ,0
Exp/Cntr=0.3,0.1

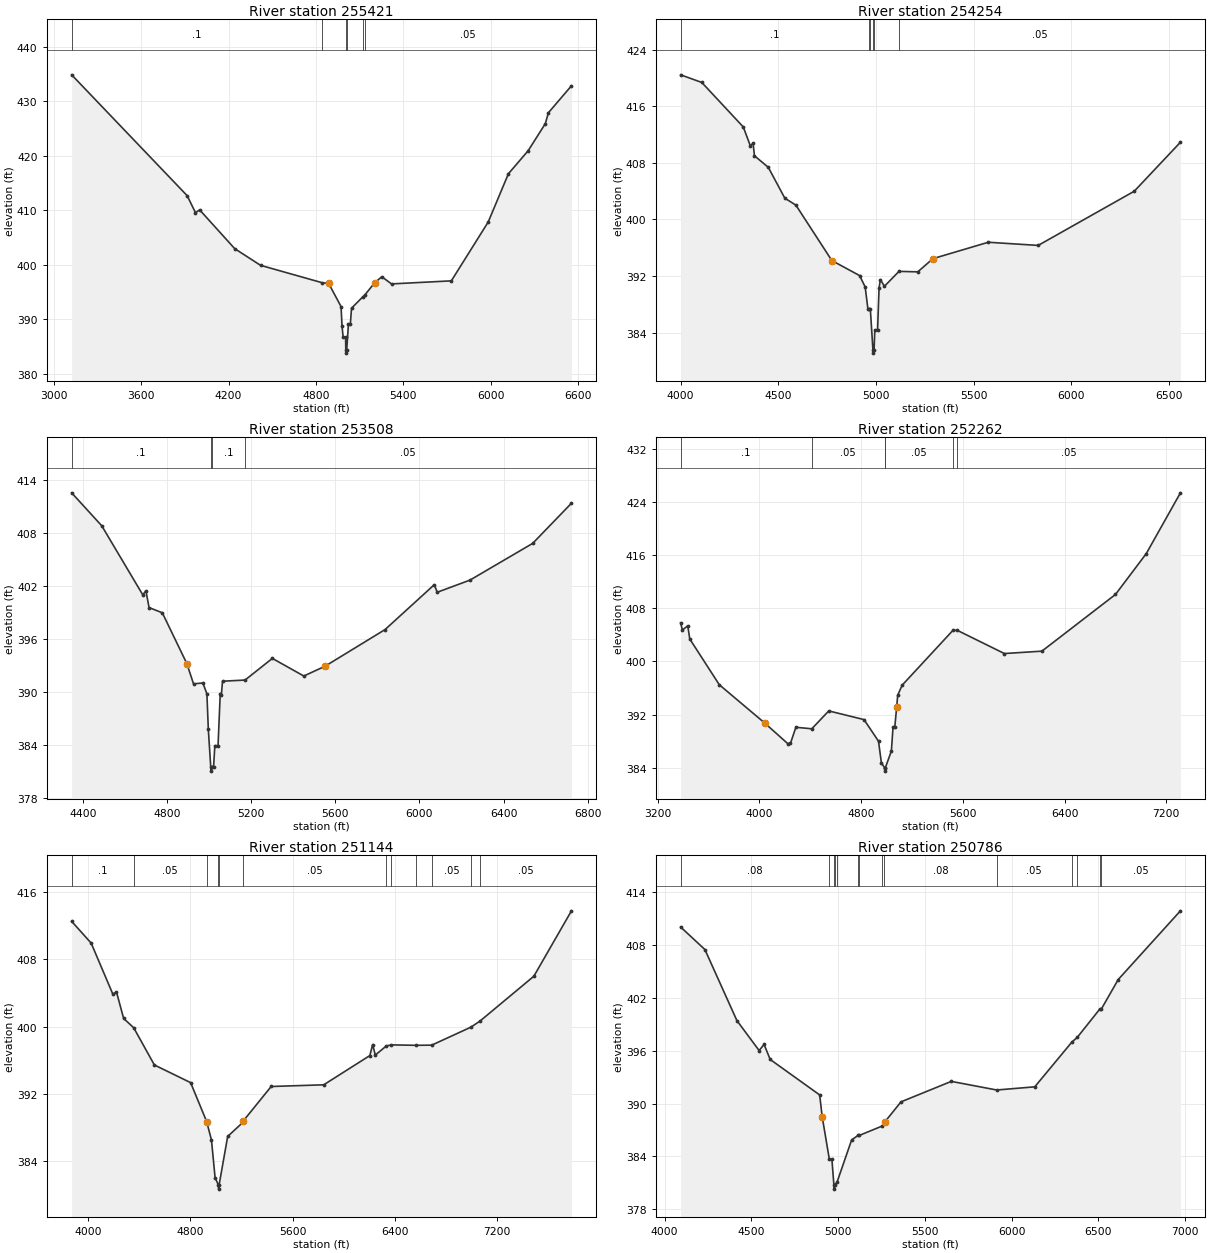
Type RM Length L Ch R = 1 ,255421  ,1167,1167,1167
BEGIN DESCRIPTION:
LAGARTO CREEK 231.0
END DESCRIPTION:
XS GIS Cut Line= 3
       2181887.7     13219896.83      2180487.72     13218646.85
      2179637.73     13217346.87
#Sta/Elev= 30
  3123.2  434.88  3916.1   412.7    3973  409.58  4001.4  410.11  4242.2  402.99
  4419.4  399.93  4844.6  396.72  4886.7  396.62    4972  392.36  4978.7  388.75
  4986.2  386.81    5003  386.81  5004.6  384.32  5007.3  383.82  5010.6  384.32
  5022.7  389.14  5035.8  389.14  5043.8  392.06    5123  394.19  5133.2  394.42
  5203.1  396.75  5251.8  397.83  5318.2  396.52  5728.8  397.08  5981.7  407.87
  6120.5  416.73  6256.1  420.96  6373.8  425.92  6394.9  427.92  6553.2  432.87
#Mann= 6 ,-1 , 0
  3123.2      .1       0  4844.6     .12       0  5004.6     .07       0
  5010.6     .12       0    5123      .1       0  5133.2     .05       0
Bank Sta=4886.7,5203.1
XS Rating Curve= 0 ,0
Exp/Cntr=0.3,0.1

Type RM Length L Ch R = 1 ,254254  ,746,746,746
BEGIN DESCRIPTION:
LAGARTO CREEK 229.0
END DESCRIPTION:
XS GIS Cut Line= 3
      2182234.11     13218913.63      2180816.99     13217644.38
      2180226.41      13217361.4
#Sta/Elev= 30
  4000.6  420.47    4109  419.39  4321.3  413.09  4357.2  410.43  4371.5  410.79
  4378.2  409.02  4449.2  407.38  4533.7  403.02  4590.5  402.03  4774.4  394.19
  4916.5  392.06  4944.9  390.45  4959.1   387.3  4966.4   387.3  4971.4   387.3
  4984.5  381.59  4987.2  381.09  4990.5  381.59  4994.2  384.35  5008.4  384.35
  5015.9  390.29  5022.6   391.5  5043.5  390.55  5117.9  392.66    5214  392.59
  5291.8  394.46  5575.1  396.78    5830  396.33  6321.7     404  6557.9  410.93
#Mann= 6 ,-1 , 0
  4000.6      .1       0  4966.4     .12       0  4971.4      .1       0
  4984.5     .07       0  4990.5      .1       0  5117.9     .05       0
Bank Sta=4774.4,5291.8
XS Rating Curve= 0 ,0
Exp/Cntr=0.3,0.1

Type RM Length L Ch R = 1 ,253508  ,1246,1246,1246
BEGIN DESCRIPTION:
LAGARTO CREEK 228.0
END DESCRIPTION:
XS GIS Cut Line= 3
      2182258.43     13218145.85      2182050.12     13217833.38
      2180162.42     13217169.43
#Sta/Elev= 30
  4346.3   412.6  4489.3  408.86  4684.4  401.02  4699.4  401.48  4714.4  399.57
  4777.4  398.98    4894  393.21  4925.8  390.91  4970.5  391.01  4989.4  389.76
  4996.2  385.73  5007.6   381.5  5010.4     381  5013.6   381.5  5021.2   381.5
  5027.2  383.89  5042.4  383.89  5052.8   389.8  5058.1   389.6  5063.6  391.21
  5170.8  391.34  5300.6   393.8  5450.2   391.8  5551.2  392.91  5836.9  397.08
  6070.7  402.17  6084.6  401.31  6240.3  402.69  6538.6  406.86  6722.9  411.42
#Mann= 4 ,-1 , 0
  4346.3      .1       0  5007.6     .07       0  5013.6      .1       0
  5170.8     .05       0
Bank Sta=4894,5551.2
XS Rating Curve= 0 ,0
Exp/Cntr=0.3,0.1

Type RM Length L Ch R = 1 ,252262  ,1118,1118,1118
BEGIN DESCRIPTION:
LAGARTO CREEK 227.0
END DESCRIPTION:
XS GIS Cut Line= 4
      2182401.66     13217950.54      2181893.87     13217117.24
      2180669.91      13216153.7      2179367.78     13215645.87
#Sta/Elev= 30
    3380  405.81  3393.7  404.72  3436.3  405.35  3451.8  403.38  3684.2  396.49
  4040.1  390.75  4222.6  387.63  4243.9  387.66  4286.5  390.09  4411.7  389.86
  4545.3  392.55  4822.7  391.24  4936.5  387.99  4959.1  384.74  4984.3  383.99
    4987  383.49  4990.3  383.99  5037.7  386.52  5050.9  390.16  5064.8  390.16
  5079.3  393.11  5087.4  394.91  5122.6  396.42    5521  404.65  5554.2  404.69
  5926.6  401.18  6221.6  401.54  6800.4  410.07  7042.3  416.21  7311.2  425.36
#Mann= 6 ,-1 , 0
    3380      .1       0  4411.7     .05       0  4984.3     .03       0
  4990.3     .05       0    5521     .08       0  5554.2     .05       0
Bank Sta=4040.1,5079.3
XS Rating Curve= 0 ,0
Exp/Cntr=0.3,0.1

Type RM Length L Ch R = 1 ,251144  ,358,358,358
BEGIN DESCRIPTION:
LAGARTO CREEK 226.0
END DESCRIPTION:
XS GIS Cut Line= 3
      2182997.19     13217682.36       2181912.1      13216449.7
      2180184.71     13214974.04
#Sta/Elev= 30
  3869.9  412.53  4022.6  409.94  4192.4  403.87  4220.9  404.13  4276.9  400.98
  4355.7  399.87  4517.8  395.44  4801.5  393.34    4927  388.71  4964.7  386.52
  4993.1  382.05  5018.6  381.17  5021.3  380.67  5024.6  381.17  5091.8  386.94
  5210.1   388.6  5212.3  388.75  5432.4  392.88  5843.8  393.08    6205  396.56
    6227  397.87  6247.8  396.62  6333.9   397.7  6371.9  397.83  6566.4  397.78
  6689.5   397.8  6996.7  399.94    7069  400.68  7489.5     406    7784  413.78
#Mann= 12 ,-1 , 0
  3869.9      .1       0  4355.7     .05       0    4927      .1       0
  5018.6     .07       0  5024.6      .1       0  5210.1     .05       0
  6333.9     .08       0  6371.9     .05       0  6566.4      .1       0
  6689.5     .05       0  6996.7      .1       0    7069     .05       0
Bank Sta=4927,5212.3
XS Rating Curve= 0 ,0
Exp/Cntr=0.3,0.1

Type RM Length L Ch R = 1 ,250786  ,262,262,262
BEGIN DESCRIPTION:
LAGARTO CREEK 225.0
END DESCRIPTION:
XS GIS Cut Line= 3
      2183083.95     13217326.41      2182337.45     13216388.94
      2181182.96     13215165.01
#Sta/Elev= 30
  4092.1  410.07  4232.1  407.51  4416.3  399.44  4544.5  396.03  4573.3  396.72
  4608.5  395.01  4893.6  390.98    4908  388.52  4948.7  383.74  4964.1  383.66
  4975.5  380.77  4978.2  380.27  4981.5  380.77  4993.3  381.04  5077.8  385.86
  5115.1  386.38  5122.8  386.38  5252.2  387.43  5266.9  387.78    5270  387.93
  5362.3  390.19  5652.4  392.52  5913.9  391.54  6133.4   391.9  6347.4  396.99
  6377.9  397.51  6507.8  400.73  6516.5  400.72  6614.5   404.1    6973  411.91
#Mann= 14 ,-1 , 0
  4092.1     .08       0  4948.7     .05       0  4975.5     .07       0
  4981.5     .05       0  4993.3     .08       0  5115.1      .1       0
  5122.8     .08       0  5252.2      .1       0  5266.9     .08       0
  5913.9     .05       0  6347.4      .1       0  6377.9     .05       0
  6507.8     .08       0  6516.5     .05       0
Bank Sta=4908,5270
XS Rating Curve= 0 ,0
Exp/Cntr=0.3,0.1

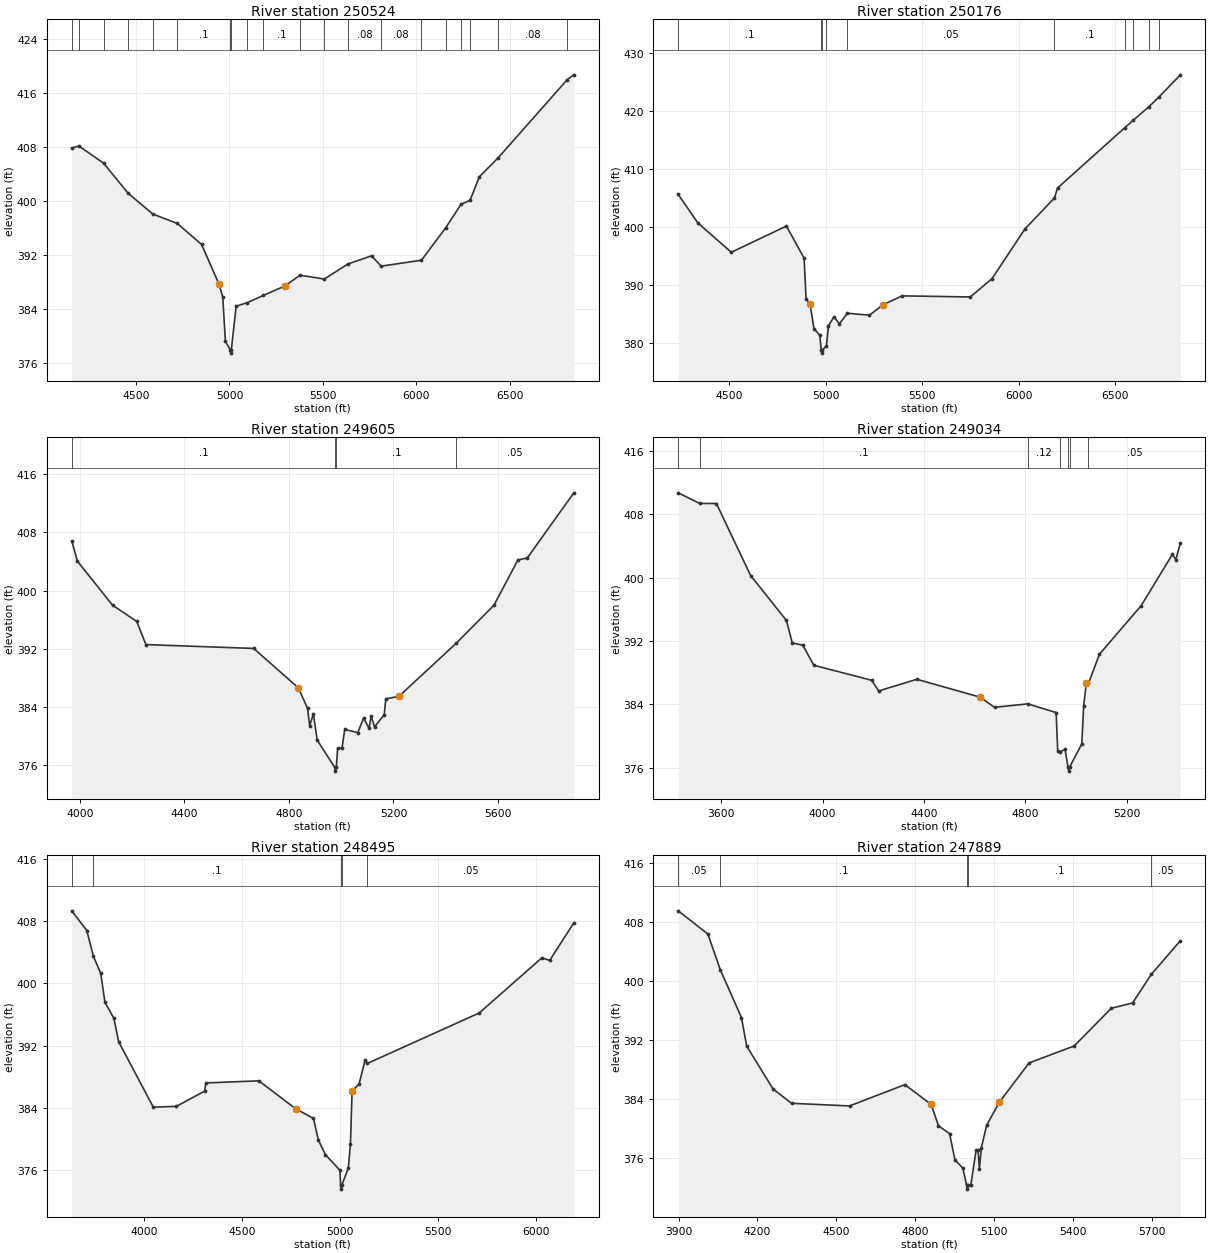
Type RM Length L Ch R = 1 ,250524  ,348,348,348
BEGIN DESCRIPTION:
Mapping XS 5643da13
END DESCRIPTION:
XS GIS Cut Line= 3
       2183205.5     13217066.02       2182537.1     13216258.73
      2181512.78     13214982.67
#Sta/Elev= 30
    4157  407.84  4195.1  408.14  4326.7  405.61  4458.3  401.13  4589.9  398.06
  4721.5  396.65  4850.9  393.54  4943.4   387.7  4964.2  385.76  4978.5  379.17
  5004.2  377.92  5006.9  377.42  5010.2  377.92  5035.9  384.38  5096.5  384.92
  5181.4  385.98  5297.8   387.4  5377.2  388.98  5507.1  388.41  5634.1  390.65
  5760.3  391.86  5810.9  390.32  6026.6   391.2  6156.5  396.02  6238.6  399.51
  6286.3  400.07  6336.3  403.58  6433.8   406.3  6805.9  417.98  6841.4   418.7
#Mann= 20 ,-1 , 0
    4157     .08       0  4195.1      .1       0  4326.7      .1       0
  4458.3     .08       0  4589.9     .08       0  4721.5      .1       0
  5004.2     .07       0  5010.2      .1       0  5096.5     .08       0
  5181.4      .1       0  5377.2      .1       0  5507.1      .1       0
  5634.1     .08       0  5810.9     .08       0  6026.6      .1       0
  6156.5     .05       0  6238.6     .08       0  6286.3      .1       0
  6433.8     .08       0  6805.9      .1       0
Bank Sta=4943.4,5297.8
XS Rating Curve= 0 ,0
Exp/Cntr=0.3,0.1

Type RM Length L Ch R = 1 ,250176  ,571,571,571
BEGIN DESCRIPTION:
LAGARTO CREEK 224.0
END DESCRIPTION:
XS GIS Cut Line= 3
      2183487.77     13216246.86      2182737.72     13216096.86
       2181437.7     13214796.84
#Sta/Elev= 30
  4235.1  405.61  4337.1  400.69  4510.5  395.64    4796  400.16  4887.8  394.62
    4898   387.6  4918.4  386.75  4938.8  382.48  4969.4  381.33  4976.6  378.74
  4979.4  378.24  4982.6  378.74  5003.6  379.52  5014.1  382.94  5042.4  384.51
  5070.7   383.3  5112.3  385.12  5226.3  384.78    5297  386.58    5396  388.12
  5749.5  387.93  5862.7  391.11  6032.4  399.64  6186.1  405.02  6202.1  406.73
    6550  417.11  6594.5  418.42  6675.5  420.74  6729.3  422.47  6838.5  426.25
#Mann= 10 ,-1 , 0
  4235.1      .1       0  4976.6     .07       0  4982.6      .1       0
  5003.6     .12       0  5112.3     .05       0  6186.1      .1       0
    6550     .05       0  6594.5      .1       0  6675.5     .05       0
  6729.3      .1       0
Bank Sta=4918.4,5297
XS Rating Curve= 0 ,0
Exp/Cntr=0.3,0.1

Type RM Length L Ch R = 1 ,249605  ,571,571,571
BEGIN DESCRIPTION:
LAGARTO CREEK 223.0
END DESCRIPTION:
XS GIS Cut Line= 3
      2183487.74     13216196.87      2182687.72     13215546.85
      2181987.74     13214996.87
#Sta/Elev= 30
  3969.2  406.82  3990.8  404.04  4125.1     398  4217.7  395.77  4252.9  392.59
  4665.2  392.06  4836.2  386.65  4871.4  383.83  4879.3  381.46  4893.7  383.07
  4908.1  379.49  4975.4  375.72  4978.2  375.22  4981.4  375.72  4986.4  378.38
  5003.2  378.38  5013.6  380.94  5063.6  380.51  5085.8  382.51  5106.7   381.1
  5114.5  382.78  5127.5   381.3  5164.5  382.94  5170.8  385.14  5220.5  385.47
  5440.9   392.8  5584.7     398  5676.1   404.2  5712.2  404.49  5890.2  413.42
#Mann= 4 ,-1 , 0
  3969.2      .1       0  4975.4     .07       0  4981.4      .1       0
  5440.9     .05       0
Bank Sta=4836.2,5220.5
XS Rating Curve= 0 ,0
Exp/Cntr=0.3,0.1

Type RM Length L Ch R = 1 ,249034  ,539,539,539
BEGIN DESCRIPTION:
LAGARTO CREEK 222.0
END DESCRIPTION:
XS GIS Cut Line= 3
       2183687.7     13216246.83      2182737.72     13214996.85
      2182337.73     13214896.86
#Sta/Elev= 30
    3430   410.7  3514.6  409.36  3580.7  409.35  3715.9  400.26  3857.3  394.59
  3880.2  391.77  3921.8  391.47  3965.4  388.94  4194.2  387.04  4221.3   385.7
    4372  387.17  4622.5  384.91  4678.7  383.63    4810  384.07    4922  382.97
  4928.3  378.18  4935.5  378.01  4957.4  378.31  4968.9  376.08  4971.7  375.58
  4974.9  376.08  5023.2     379  5030.9  383.86  5041.2  386.65  5049.8  386.65
  5092.8  390.32  5257.7  396.46  5381.4  402.95  5394.3  402.26  5412.3  404.33
#Mann= 7 ,-1 , 0
    3430     .05       0  3514.6      .1       0    4810     .12       0
  4935.5      .1       0  4968.9     .07       0  4974.9      .1       0
  5049.8     .05       0
Bank Sta=4622.5,5041.2
XS Rating Curve= 0 ,0
Exp/Cntr=0.3,0.1

Type RM Length L Ch R = 1 ,248495  ,606,606,606
BEGIN DESCRIPTION:
LAGARTO CREEK 221.0
END DESCRIPTION:
XS GIS Cut Line= 4
      2183710.22     13216124.65      2183297.89     13215072.12
      2183102.58     13214540.44      2182234.49     13214562.14
#Sta/Elev= 30
  3629.6  409.32  3706.4  406.79  3740.6  403.45  3777.6  401.28  3799.1  397.57
  3844.7  395.51  3869.2  392.49  4046.1  384.09  4164.2  384.19  4308.7  386.15
  4314.6   387.2  4585.4  387.47    4773  383.89  4864.4  382.64  4889.6  379.86
  4925.4  377.99    5000  375.95  5003.2  374.05  5005.9  373.55  5009.2  374.05
  5042.6  376.28  5053.3  379.33  5061.8  386.15  5097.6  387.07  5128.1  390.12
  5139.3   389.7  5711.4  396.19  6031.5  403.28  6071.5  402.95  6194.8  407.78
#Mann= 5 ,-1 , 0
  3629.6     .05       0  3740.6      .1       0  5003.2     .07       0
  5009.2      .1       0  5139.3     .05       0
Bank Sta=4773,5061.8
XS Rating Curve= 0 ,0
Exp/Cntr=0.3,0.1

Type RM Length L Ch R = 1 ,247889  ,583,583,583
BEGIN DESCRIPTION:
LAGARTO CREEK 220.0
END DESCRIPTION:
XS GIS Cut Line= 3
      2183787.72     13216146.82      2183737.72     13215046.85
      2183637.72     13214246.88
#Sta/Elev= 30
  3898.9  409.55  4011.5   406.4  4058.5  401.57  4139.1  395.05  4159.1  391.17
  4259.2  385.37  4329.3  383.43  4549.5  383.07  4759.8  385.96  4859.9  383.27
  4887.4  380.38  4929.9   379.3  4949.9  375.75    4980  374.64  4994.5  372.28
  4997.2  371.78  5000.5  372.28  5010.1  372.28  5030.2  377.03  5037.8  377.03
  5042.8  374.57  5050.4   377.4  5070.5  380.45  5118.4  383.56  5231.8  388.91
  5403.1  391.21  5544.2  396.33  5624.8  397.05  5695.8  400.92  5806.2  405.48
#Mann= 5 ,-1 , 0
  3898.9     .05       0  4058.5      .1       0  4994.5     .07       0
  5000.5      .1       0  5695.8     .05       0
Bank Sta=4859.9,5118.4
XS Rating Curve= 0 ,0
Exp/Cntr=0.3,0.1