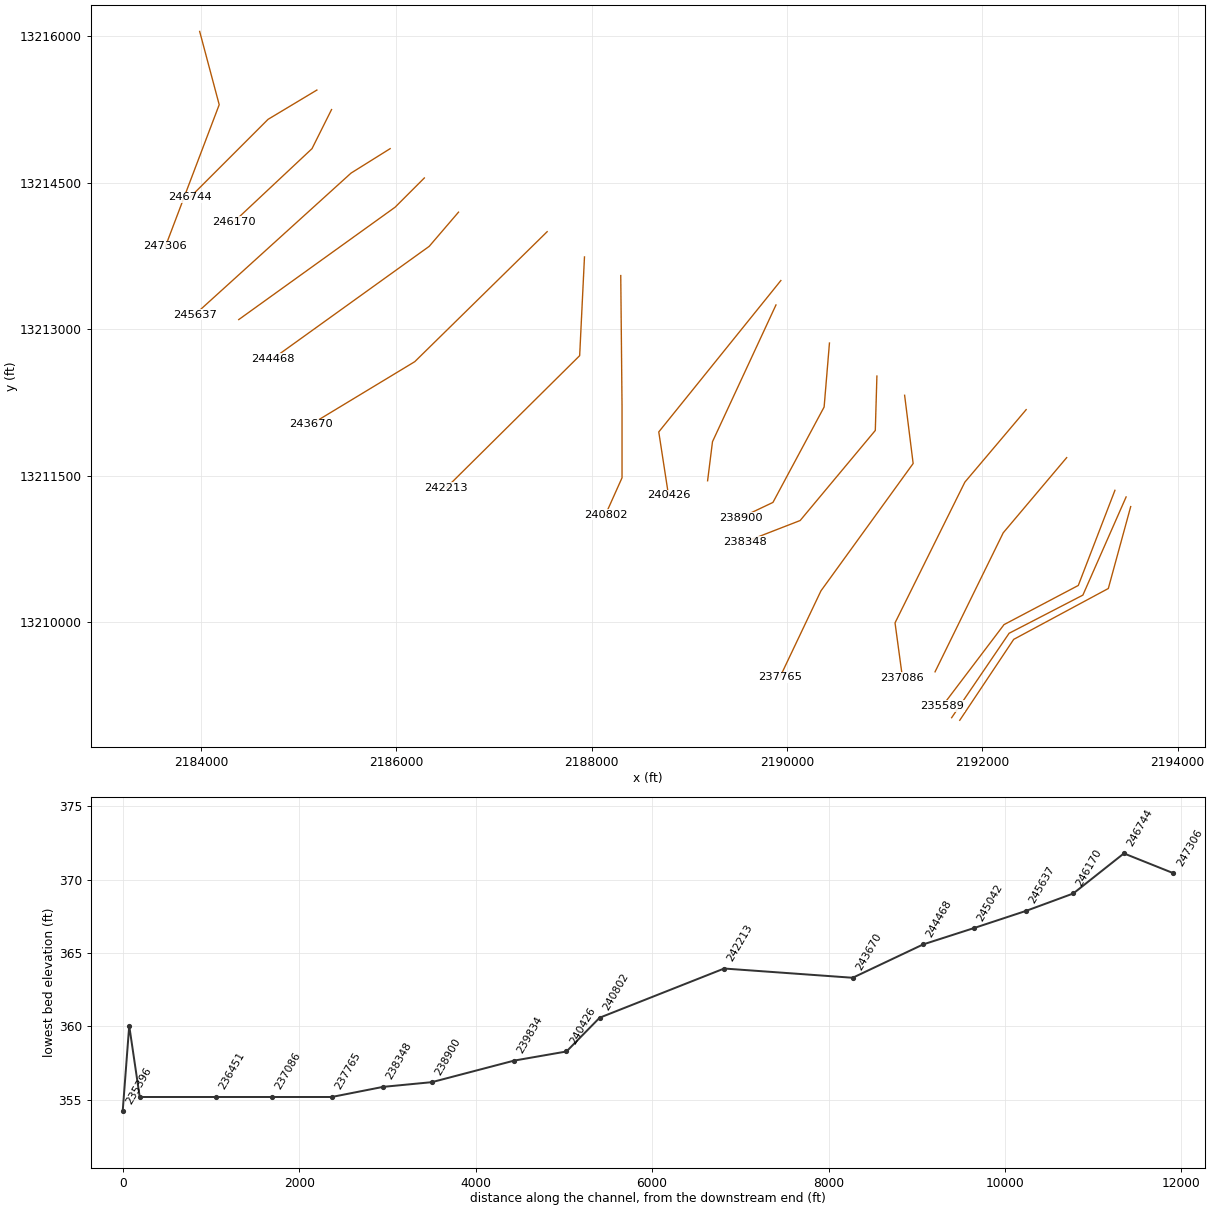
HEC-RAS study LAGARTO CREEK.prj: LAGARTO CREEK Base Level Engineering

--- LAGARTO CREEK.g01 (geometry) --- (continued)

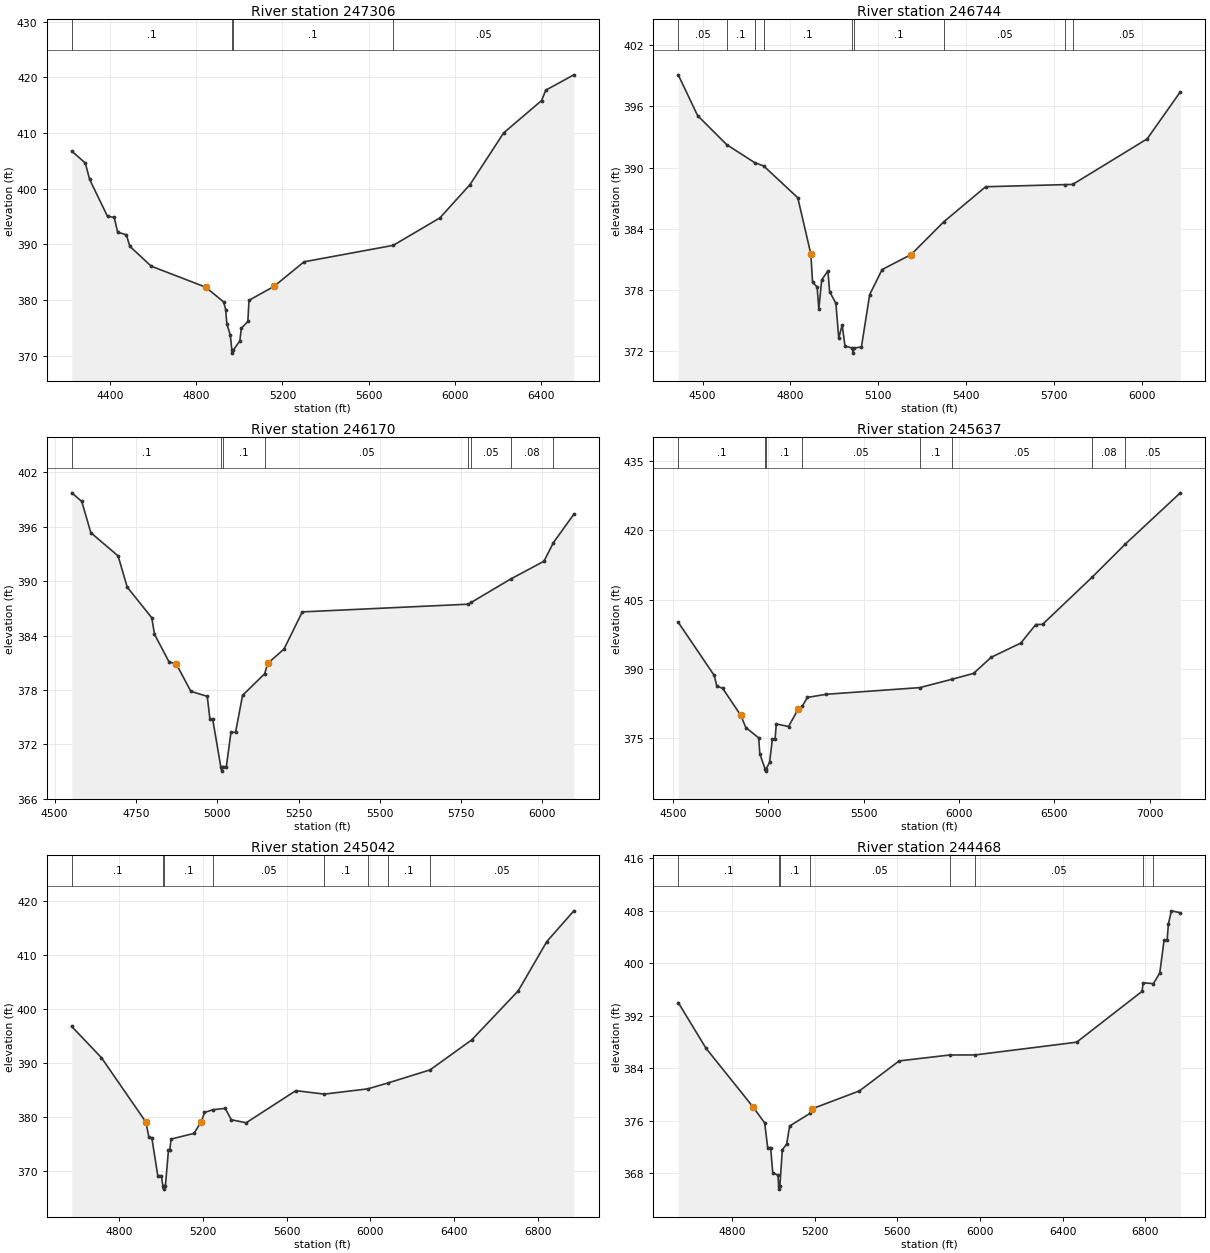
Type RM Length L Ch R = 1 ,247306  ,562,562,562
BEGIN DESCRIPTION:
LAGARTO CREEK 219.0
END DESCRIPTION:
XS GIS Cut Line= 3
      2183987.72     13216046.85      2184187.72     13215296.86
      2183637.72     13213846.86
#Sta/Elev= 30
  4223.8  406.73  4286.5  404.59  4306.6  401.64  4389.4  395.01  4420.4  394.82
  4436.6  392.16  4476.7   391.7  4492.9  389.63  4591.8  386.06  4844.8  382.28
  4927.6  379.63  4937.3  378.25  4942.4  375.69  4958.6  373.69    4966  370.93
  4968.7  370.43    4972  370.93  5002.7  372.64  5009.7   374.9  5039.9  376.12
  5045.2  379.92  5160.4  382.41  5300.4  386.84  5713.9   389.8  5930.5  394.75
  6069.5  400.72  6225.6  410.01  6401.1  415.81  6420.5  417.68  6550.8  420.44
#Mann= 4 ,-1 , 0
  4223.8      .1       0    4966     .07       0    4972      .1       0
  5713.9     .05       0
Bank Sta=4844.8,5160.4
XS Rating Curve= 0 ,0
Exp/Cntr=0.3,0.1

Type RM Length L Ch R = 1 ,246744  ,574,574,574
BEGIN DESCRIPTION:
LAGARTO CREEK 218.0
END DESCRIPTION:
XS GIS Cut Line= 3
      2185187.72     13215446.86      2184687.72     13215146.85
       2183887.7     13214346.83
#Sta/Elev= 30
  4416.9  399.11    4483  395.11  4582.6  392.25  4678.4  390.48  4708.7  390.16
  4825.1  387.04  4869.8   381.5  4875.6  378.74  4891.2  378.28    4897  376.08
  4906.7  378.97  4928.1  379.86  4933.9  377.82  4955.3  376.67    4965  373.26
  4976.7  374.54  4986.4  372.47  5011.1  372.28  5013.9  371.78  5017.1  372.28
  5042.4  372.38  5070.7  377.53  5113.1  379.99  5212.1  381.46  5323.8  384.68
  5466.7  388.12    5738  388.33    5764  388.35  6018.2  392.82  6131.4  397.44
#Mann= 9 ,-1 , 0
  4416.9     .05       0  4582.6      .1       0  4678.4     .05       0
  4708.7      .1       0  5011.1     .07       0  5017.1      .1       0
  5323.8     .05       0    5738      .1       0    5764     .05       0
Bank Sta=4869.8,5212.1
XS Rating Curve= 0 ,0
Exp/Cntr=0.3,0.1

Type RM Length L Ch R = 1 ,246170  ,533,533,533
BEGIN DESCRIPTION:
LAGARTO CREEK 217.0
END DESCRIPTION:
XS GIS Cut Line= 3
      2185337.71     13215246.84      2185137.72     13214846.85
      2184337.71     13214096.85
#Sta/Elev= 30
  4552.8  399.74  4583.5  398.79  4611.5  395.34  4695.3  392.78  4723.3  389.34
  4798.8  385.96  4807.1  384.15  4851.9   381.1  4874.2  380.87  4918.9  377.85
  4969.3   377.3  4977.6   374.8    4986   374.8  5010.9  369.55  5013.7  369.05
  5016.9  369.55  5028.1  369.55  5042.3  373.33  5056.4  373.33  5077.9   377.4
  5145.8  379.79  5155.6  380.94  5205.4  382.51  5261.6  386.61  5772.3  387.46
  5781.8  387.67  5903.1  390.25  6004.5  392.19    6034  394.26  6096.6  397.38
#Mann= 8 ,-1 , 0
  4552.8      .1       0  5010.9     .07       0  5016.9      .1       0
  5145.8     .05       0  5772.3     .08       0  5781.8     .05       0
  5903.1     .08       0    6034     .05       0
Bank Sta=4874.2,5155.6
XS Rating Curve= 0 ,0
Exp/Cntr=0.3,0.1

Type RM Length L Ch R = 1 ,245637  ,595,595,595
BEGIN DESCRIPTION:
LAGARTO CREEK 216.0
END DESCRIPTION:
XS GIS Cut Line= 3
      2185937.72     13214846.86      2185537.72     13214596.85
      2183937.71     13213146.84
#Sta/Elev= 30
  4528.3   400.1    4717  388.58  4730.5  386.32  4761.2  385.79  4855.5  379.99
  4882.7   377.3  4949.9  375.07  4955.8  371.59  4983.4  368.37  4986.2  367.87
  4989.4  368.37  5007.1  369.78  5021.3  374.74  5035.5  374.74  5042.2  378.08
  5106.5  377.53  5155.8  381.23  5179.1  381.99  5205.1  383.83  5304.5  384.51
  5793.7  385.95  5962.9  387.76  6076.3  389.04  6168.2  392.52  6323.6   395.6
    6402  399.61  6437.2  399.64  6697.8  409.88  6871.1  417.03  7159.3  428.12
#Mann= 8 ,-1 , 0
  4528.3      .1       0  4983.4     .07       0  4989.4      .1       0
  5179.1     .05       0  5793.7      .1       0  5962.9     .05       0
  6697.8     .08       0  6871.1     .05       0
Bank Sta=4855.5,5155.8
XS Rating Curve= 0 ,0
Exp/Cntr=0.3,0.1

Type RM Length L Ch R = 1 ,245042  ,574,574,574
BEGIN DESCRIPTION:
LAGARTO CREEK 215.0
END DESCRIPTION:
XS GIS Cut Line= 3
      2186287.75     13214546.88      2185987.72     13214246.85
      2184387.73     13213096.86
#Sta/Elev= 30
  4575.7  396.78  4717.2  391.01  4929.3   379.1  4943.4  376.35  4957.6  376.18
  4985.9  369.19  5003.1  369.19  5010.5  367.19  5013.3  366.69  5016.5  367.19
  5022.1  367.19  5036.8  373.85    5043  373.85  5049.3  375.95  5158.4     377
    5194   379.2  5208.7  380.87  5249.5  381.39  5307.9  381.63  5336.4  379.53
  5407.6  378.97  5644.5  384.91  5780.3  384.27  5987.3  385.24  6085.5  386.35
  6284.5  388.75    6483  394.29  6705.2  403.38  6841.5   412.5  6970.4  418.18
#Mann= 8 ,-1 , 0
  4575.7      .1       0  5010.5     .07       0  5016.5      .1       0
  5249.5     .05       0  5780.3      .1       0  5987.3     .05       0
  6085.5      .1       0  6284.5     .05       0
Bank Sta=4929.3,5194
XS Rating Curve= 0 ,0
Exp/Cntr=0.3,0.1

Type RM Length L Ch R = 1 ,244468  ,798,798,798
BEGIN DESCRIPTION:
LAGARTO CREEK 214.0
END DESCRIPTION:
XS GIS Cut Line= 3
      2186637.74     13214196.87      2186337.72     13213846.85
      2184737.73     13212696.86
#Sta/Elev= 30
    4539     394  4673.5  387.04  4900.7  378.12  4957.7  375.66    4972  371.92
  4986.3  371.92  4996.7  368.11  5022.1  367.68  5025.2  366.08    5028  365.58
  5031.2  366.08    5043  371.56  5063.9  372.44  5078.6   375.2    5179  377.15
  5185.4  377.79  5416.2  380.54  5608.9  385.11  5853.5  386.01  5976.2  386.02
  6468.3  387.96    6785   395.7  6790.6  397.01    6840  396.88  6870.9  398.49
  6891.8  403.51  6906.6  403.51  6912.7  405.97  6927.4  407.97  6970.4  407.68
#Mann= 8 ,-1 , 0
    4539      .1       0  5025.2     .07       0  5031.2      .1       0
    5179     .05       0  5853.5      .1       0  5976.2     .05       0
  6790.6      .1       0    6840     .05       0
Bank Sta=4900.7,5185.4
XS Rating Curve= 0 ,0
Exp/Cntr=0.3,0.1

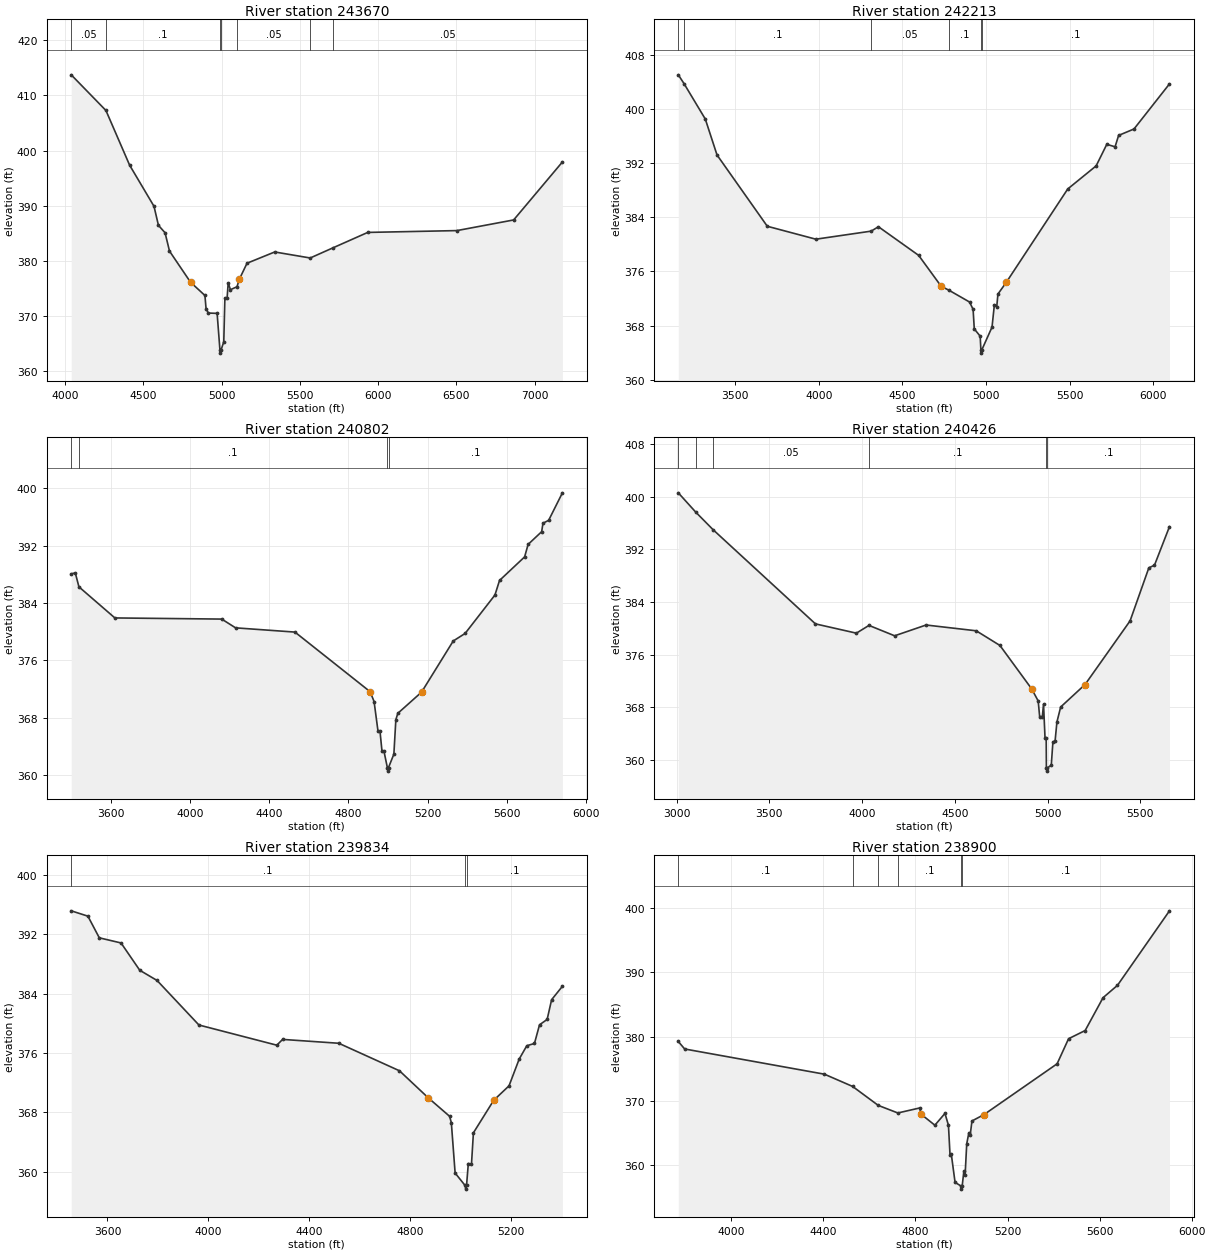
Type RM Length L Ch R = 1 ,243670  ,1457,1457,1457
BEGIN DESCRIPTION:
LAGARTO CREEK 213.0
END DESCRIPTION:
XS GIS Cut Line= 3
      2187545.19     13213996.83      2186189.71     13212665.99
      2185131.34     13212026.05
#Sta/Elev= 30
  4040.1  413.71  4261.8  407.25  4413.1  397.34  4568.7   389.9    4597  386.45
  4639.3  385.11  4667.6  381.79    4802  376.15  4893.9  373.75    4901  371.39
  4915.2  370.57  4971.7  370.51  4989.9  363.81  4992.6  363.31  4995.9  363.81
  5014.2  365.35  5021.2  373.23  5035.3  373.23  5042.5  376.05  5056.6   374.8
  5098.7  375.33  5113.2  376.67  5162.6  379.59  5339.5  381.63    5566  380.54
    5714  382.41  5933.4  385.17  6502.6   385.5  6865.2  387.43  7176.5  397.93
#Mann= 7 ,-1 , 0
  4040.1     .05       0  4261.8      .1       0  4989.9     .07       0
  4995.9      .1       0  5098.7     .05       0    5566      .1       0
    5714     .05       0
Bank Sta=4802,5113.2
XS Rating Curve= 0 ,0
Exp/Cntr=0.3,0.1

Type RM Length L Ch R = 1 ,242213  ,1411,1411,1411
BEGIN DESCRIPTION:
LAGARTO CREEK 211.0
END DESCRIPTION:
XS GIS Cut Line= 3
      2187927.22     13213738.11      2187877.92      13212727.6
      2186511.38     13211373.37
#Sta/Elev= 30
  3160.3  405.05  3194.9  403.74  3321.7  398.52  3391.8  393.21  3692.2  382.68
  3982.5  380.77    4313  381.96  4356.5  382.61  4596.9  378.38  4731.3  373.82
  4780.2   373.2    4901  371.49  4922.2  370.41  4929.3  367.52  4964.6  366.44
  4968.7  364.44  4971.5  363.94  4974.7  364.44  5035.3  367.78  5049.5   371.1
  5063.6   370.8  5070.7  372.67  5120.2  374.38  5487.9  388.19  5657.6   391.6
  5721.2  394.78  5770.8  394.42  5791.9   396.1  5883.9  397.05  6095.9  403.71
#Mann= 6 ,-1 , 0
  3160.3     .05       0  3194.9      .1       0    4313     .05       0
  4780.2      .1       0  4968.7     .07       0  4974.7      .1       0
Bank Sta=4731.3,5120.2
XS Rating Curve= 0 ,0
Exp/Cntr=0.3,0.1

Type RM Length L Ch R = 1 ,240802  ,376,376,376
BEGIN DESCRIPTION:
LAGARTO CREEK 209.0
END DESCRIPTION:
XS GIS Cut Line= 4
      2188298.59     13213547.49      2188311.61     13212219.38
      2188311.61     13211477.19      2188143.02     13211101.11
#Sta/Elev= 30
  3399.3  388.06  3419.9  388.19  3438.2  386.25  3619.9  381.92    4160  381.76
    4230  380.54    4530  379.95    4910  371.65    4930  370.28    4950  366.11
    4960  366.11    4970  363.35    4980  363.35    4997  361.09  4999.8  360.59
    5003  361.09    5030  362.96    5040  367.75    5050  368.64    5170  371.59
    5330  378.71    5390  379.76  5540.8  385.11    5564  387.14  5690.8  390.42
  5708.5  392.16  5776.9  393.93  5783.6  395.11  5812.2  395.51  5881.8  399.34
#Mann= 4 ,-1 , 0
  3399.3     .05       0  3438.2      .1       0    4997     .07       0
    5003      .1       0
Bank Sta=4910,5170
XS Rating Curve= 0 ,0
Exp/Cntr=0.3,0.1

Type RM Length L Ch R = 1 ,240426  ,592,592,592
BEGIN DESCRIPTION:
LAGARTO CREEK 208.0
END DESCRIPTION:
XS GIS Cut Line= 3
       2189937.7     13213496.83      2188687.72     13211946.85
      2188787.71      13211296.9
#Sta/Elev= 30
  3008.8  400.61  3103.1  397.67  3196.2  395.01  3748.5  380.68  3969.2  379.27
  4037.1  380.45  4175.5  378.87  4345.1  380.51  4615.4  379.63  4743.3   377.4
  4914.4   370.8  4949.6  368.96  4957.6  366.57    4972  366.57  4978.4  368.47
  4986.4  363.39  4992.8  363.32  4993.8  358.79  4996.5  358.29  4999.8  358.79
  5020.2  359.19  5029.1  362.76  5040.5   362.8  5050.6  365.75  5070.8  368.04
  5202.4  371.46  5445.2  381.14  5546.4  389.21  5576.7   389.6  5657.6  395.47
#Mann= 6 ,-1 , 0
  3008.8     .05       0  3103.1      .1       0  3196.2     .05       0
  4037.1      .1       0  4993.8     .07       0  4999.8      .1       0
Bank Sta=4914.4,5202.4
XS Rating Curve= 0 ,0
Exp/Cntr=0.3,0.1

Type RM Length L Ch R = 1 ,239834  ,934,934,934
BEGIN DESCRIPTION:
LAGARTO CREEK 207.0
END DESCRIPTION:
XS GIS Cut Line= 3
      2189887.71     13213246.82      2189237.72     13211846.86
      2189187.72     13211446.87
#Sta/Elev= 30
  3456.5  395.18  3522.6  394.46  3567.8  391.54  3653.9  390.85  3728.1  387.17
  3796.8  385.79  3962.6  379.79  4271.3  377.07  4294.2  377.85  4516.8  377.33
  4757.4  373.62  4871.3  369.98  4955.9  367.49  4962.9  366.63  4977.9  359.84
  5017.2  358.17  5019.9  357.67  5023.2  358.17  5030.2  361.12  5042.8  361.06
  5050.4  365.26    5131  369.65  5191.5  371.59  5231.8   375.2    5262     377
  5292.3   377.3  5312.4  379.82  5342.6  380.54  5360.3   383.2  5403.1  385.01
#Mann= 3 ,-1 , 0
  3456.5      .1       0  5017.2     .07       0  5023.2      .1       0
Bank Sta=4871.3,5131
XS Rating Curve= 0 ,0
Exp/Cntr=0.3,0.1

Type RM Length L Ch R = 1 ,238900  ,552,552,552
BEGIN DESCRIPTION:
LAGARTO CREEK 206.0
END DESCRIPTION:
XS GIS Cut Line= 4
      2190435.23       13212857.      2190380.66     13212202.18
      2189856.77     13211225.35      2189523.91      13211067.1
#Sta/Elev= 30
  3769.5  379.23  3797.2  378.06  4404.3  374.13  4526.8  372.22  4638.3  369.26
  4723.4  368.08  4818.4  368.86  4824.2  367.89  4884.3  366.17  4928.1  368.01
  4943.3  366.16  4950.1  361.54  4955.7  361.65    4972  357.26    4997   356.7
  4999.7   356.2    5003   356.7  5010.2  358.98  5015.8  358.46  5022.7  363.27
  5032.1  365.01  5037.8  364.64  5045.4  366.83  5097.9  367.83  5415.4  375.75
  5465.2  379.66  5537.3  380.94    5615  386.06  5677.7  387.99  5903.6  399.61
#Mann= 6 ,-1 , 0
  3769.5      .1       0  4526.8     .08       0  4638.3     .05       0
  4723.4      .1       0    4997     .07       0    5003      .1       0
Bank Sta=4824.2,5097.9
XS Rating Curve= 0 ,0
Exp/Cntr=0.3,0.1

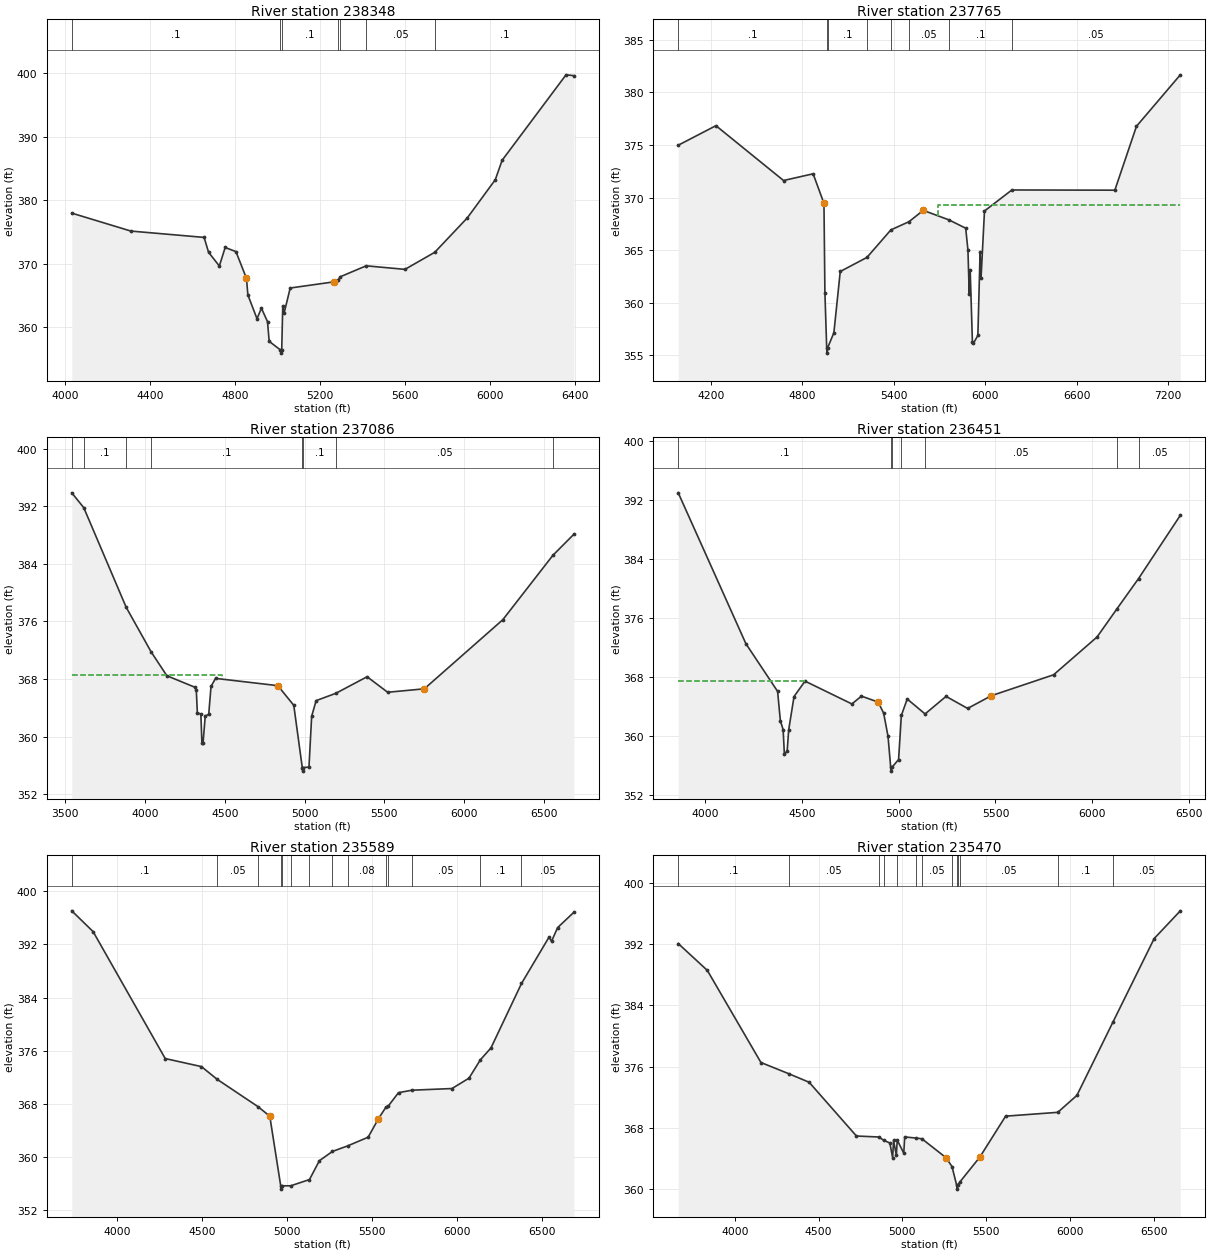
Type RM Length L Ch R = 1 ,238348  ,583,583,583
BEGIN DESCRIPTION:
LAGARTO CREEK 205.0
END DESCRIPTION:
XS GIS Cut Line= 4
      2190920.92     13212518.71      2190904.55     13211962.07
      2190135.09     13211039.81      2189573.44     13210821.69
#Sta/Elev= 30
  4032.6  377.96  4310.5  375.13  4654.8  374.13  4675.7  371.79  4726.4  369.62
  4753.8  372.54  4804.5  371.89    4854  367.66  4860.5  365.07  4903.4  361.31
  4924.3  362.96  4952.9  360.84  4960.7  357.74  5013.7  356.38  5016.4  355.88
  5019.7  356.38  5024.5  363.28    5031   362.2  5059.6  366.15  5265.3  367.12
  5284.9  367.41  5295.4  367.93  5416.9  369.65  5599.1  369.09  5739.1  371.78
  5892.5  377.22  6023.8  383.23  6055.9  386.29  6356.3  399.77  6393.1  399.64
#Mann= 7 ,-1 , 0
  4032.6      .1       0  5013.7     .07       0  5019.7      .1       0
  5284.9     .05       0  5295.4      .1       0  5416.9     .05       0
  5739.1      .1       0
Bank Sta=4854,5265.3
XS Rating Curve= 0 ,0
Exp/Cntr=0.3,0.1

Type RM Length L Ch R = 1 ,237765  ,679,679,679
BEGIN DESCRIPTION:
LAGARTO CREEK 204.0
END DESCRIPTION:
XS GIS Cut Line= 4
      2191204.69     13212322.23        2191292.     13211623.72
      2190347.92     13210319.46      2189927.71     13209435.38
#Sta/Elev= 30
  3987.3  374.98  4234.6  376.84    4678  371.62    4872  372.26  4943.1  369.44
  4949.3  360.92    4961  355.69  4963.8  355.19    4967  355.69  5008.1  357.13
  5049.9  362.96  5224.9   364.3    5382  366.92  5500.7   367.7  5594.3  368.78
  5763.2  367.87  5872.7  367.08  5887.4  364.99  5895.9  360.78  5902.1  363.08
  5916.8  356.22    5923  356.12  5952.4  356.87  5967.1   364.8  5973.3  362.33
  5995.9  368.72  6175.5  370.72  6850.8   370.7  6992.6  376.78  7280.2  381.68
#Mann= 8 ,-1 , 0
  3987.3      .1       0    4961     .07       0    4967      .1       0
  5224.9     .05       0    5382      .1       0  5500.7     .05       0
  5763.2      .1       0  6175.5     .05       0
#XS Ineff= 2 , 0
                         5693.18          369.27
Permanent Ineff=
       F       F
Bank Sta=4943.1,5594.3
XS Rating Curve= 0 ,0
Exp/Cntr=0.3,0.1

Type RM Length L Ch R = 1 ,237086  ,635,635,635
BEGIN DESCRIPTION:
LAGARTO CREEK 203.0
END DESCRIPTION:
XS GIS Cut Line= 4
      2192448.91     13212174.88      2191821.35     13211432.72
      2191106.46     13209992.03      2191182.66     13209431.42
#Sta/Elev= 30
  3541.5  393.87  3616.8   391.8  3882.5  377.96  4038.6  371.77  4137.2  368.45
    4314  366.84  4321.8  366.44  4328.3  363.32  4350.4  363.11  4356.9  359.15
    4364  359.09  4377.8  362.82  4399.8  363.11  4414.1  366.96  4442.5  368.08
  4832.5  367.07  4932.6  364.34  4985.8  355.69  4988.6  355.19  4991.8  355.69
  5027.8  355.75  5044.7  362.82  5072.7  364.99  5195.7     366    5392  368.31
  5520.9  366.15  5750.6  366.63  6242.7  376.24    6556  385.18  6687.5  388.11
#Mann= 8 ,-1 , 0
  3541.5     .05       0  3616.8      .1       0  3882.5     .05       0
  4038.6      .1       0  4985.8     .07       0  4991.8      .1       0
  5195.7     .05       0    6556     .08       0
#XS Ineff= 2 , 0
          4480.4  368.52
Permanent Ineff=
       F       F
Bank Sta=4832.5,5750.6
XS Rating Curve= 0 ,0
Exp/Cntr=0.3,0.1

Type RM Length L Ch R = 1 ,236451  ,862,862,862
BEGIN DESCRIPTION:
LAGARTO CREEK 202.0
END DESCRIPTION:
XS GIS Cut Line= 3
      2192863.69     13211683.77      2192214.27     13210914.29
      2191516.23     13209490.95
#Sta/Elev= 30
  3862.3  393.01  4211.6  372.51  4375.3  366.03  4389.6  362.03  4403.9  360.83
  4410.4  357.45  4424.7  357.91  4432.5  360.78  4460.2  365.33    4517  367.42
  4758.8  364.32  4808.3  365.38  4894.8  364.57  4922.9  363.06  4945.4  359.92
  4959.3  355.69    4962  355.19  4965.3  355.69    5000  356.77  5014.2  362.75
  5044.6  364.99  5136.7  362.96    5245  365.35  5356.4  363.71  5478.9  365.44
  5800.1  368.28  6024.7  373.42  6127.2  377.24  6238.9  381.36  6454.5  389.95
#Mann= 7 ,-1 , 0
  3862.3      .1       0  4959.3     .07       0  4965.3      .1       0
  5014.2      .1       0  5136.7     .05       0  6127.2     .08       0
  6238.9     .05       0
#XS Ineff= 2 , 0
         4515.91   367.4
Permanent Ineff=
       F       F
Bank Sta=4894.8,5478.9
XS Rating Curve= 0 ,0
Exp/Cntr=0.3,0.1

Type RM Length L Ch R = 1 ,235589  ,119,119,119
BEGIN DESCRIPTION:
LAGARTO CREEK 201.0
END DESCRIPTION:
XS GIS Cut Line= 4
      2193357.71     13211349.13      2192982.71     13210375.18
      2192222.29     13209974.14      2191590.99     13209140.81
#Sta/Elev= 30
  3735.9  397.05  3861.3  393.92  4284.8  374.83  4497.5  373.62  4590.1   371.7
    4830  367.59  4898.9  366.16  4963.1  355.69  4965.8  355.19  4969.1  355.69
  5021.8  355.69    5132  356.63  5190.3  359.47  5266.9  360.86  5356.8   361.7
  5476.6     363    5537  365.78  5581.6  367.54  5594.6  367.68  5654.9   369.7
  5733.6  370.07    5969  370.32  6068.9  371.88  6135.9  374.65  6197.8  376.42
  6377.2  386.12  6539.1   393.1  6553.6  392.46  6589.3  394.52  6684.7  396.83
#Mann= 14 ,-1 , 0
  3735.9      .1       0  4590.1     .05       0    4830     .08       0
  4963.1     .07       0  4969.1     .08       0  5021.8      .1       0
    5132     .08       0  5266.9     .05       0  5356.8     .08       0
  5581.6     .05       0  5594.6     .08       0  5733.6     .05       0
  6135.9      .1       0  6377.2     .05       0
Bank Sta=4898.9,5537
XS Rating Curve= 0 ,0
Exp/Cntr=0.3,0.1

Type RM Length L Ch R = 1 ,235470  ,74,74,74
BEGIN DESCRIPTION:
Mapping XS 1c437db8
END DESCRIPTION:
XS GIS Cut Line= 4
      2193472.28     13211281.39      2193029.59     13210276.22
      2192274.38     13209885.59       2191686.1     13209021.41
#Sta/Elev= 30
  3663.3  392.08  3836.7  388.58  4156.5  376.56  4326.7  375.06  4444.1  373.98
  4725.9  366.97  4860.5  366.84  4887.8  366.42  4925.2  366.06  4941.8  364.15
  4947.4   366.4  4963.9  364.45  4969.3  366.44  5008.2  364.73  5013.8  366.85
  5078.2  366.71  5116.3  366.61  5259.1  364.16  5295.8  362.99  5323.7  360.54
  5326.4  360.04  5329.7  360.54  5344.8  361.03  5461.8  364.22  5615.6  369.56
  5926.6  370.06  6040.6  372.27  6256.1  381.86  6501.4  392.73  6657.3  396.35
#Mann= 13 ,-1 , 0
  3663.3      .1       0  4326.7     .05       0  4860.5     .08       0
  4887.8     .05       0  4969.3      .1       0  5078.2     .08       0
  5116.3     .05       0  5295.8     .08       0  5323.7     .07       0
  5329.7     .08       0  5344.8     .05       0  5926.6      .1       0
  6256.1     .05       0
Bank Sta=5259.1,5461.8
XS Rating Curve= 0 ,0
Exp/Cntr=0.3,0.1

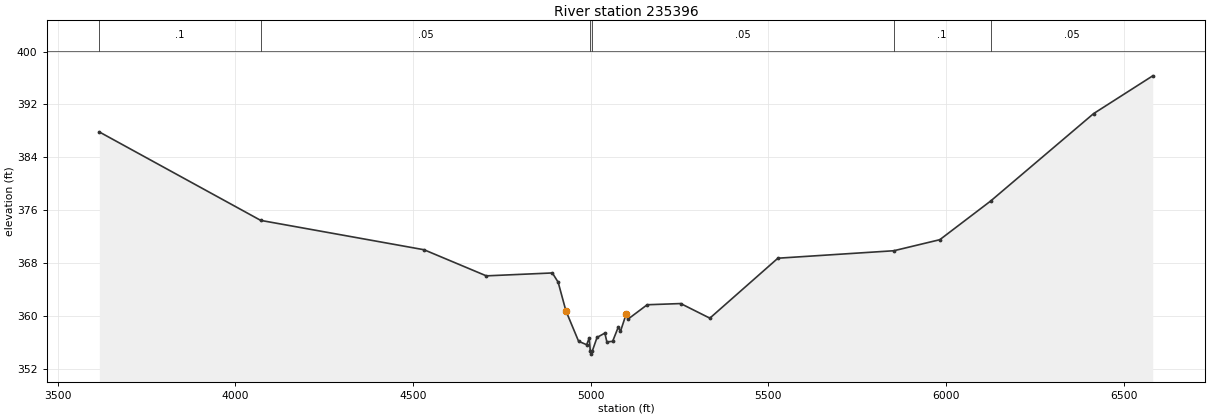
Type RM Length L Ch R = 1 ,235396  ,778,778,778
BEGIN DESCRIPTION:
LAGARTO CREEK 200.0
END DESCRIPTION:
XS GIS Cut Line= 4
      2193519.17     13211182.47        2193290.     13210343.93
      2192321.25     13209823.09      2191769.15     13208994.94
#Sta/Elev= 30
  3617.2  387.83  4071.4  374.45    4531  370.01  4706.3  366.06  4892.1   366.5
  4908.4   365.1  4930.3  360.76  4965.9  356.17  4988.6  355.64    4996  356.67
  4998.7  354.72  5001.4  354.22  5004.7  354.72  5017.9  356.75  5039.8   357.4
  5045.5  356.08  5061.7  356.15    5078  358.36  5083.7  357.65  5099.9   360.3
  5105.6  359.54    5159  361.69  5253.3  361.87  5335.3  359.66  5526.8  368.73
  5853.1  369.86  5982.4  371.53  6125.3  377.37  6415.1   390.6  6581.7  396.32
#Mann= 6 ,-1 , 0
  3617.2      .1       0  4071.4     .05       0  4998.7     .03       0
  5004.7     .05       0  5853.1      .1       0  6125.3     .05       0
Bank Sta=4930.3,5099.9
XS Rating Curve= 0 ,0
Exp/Cntr=0.3,0.1