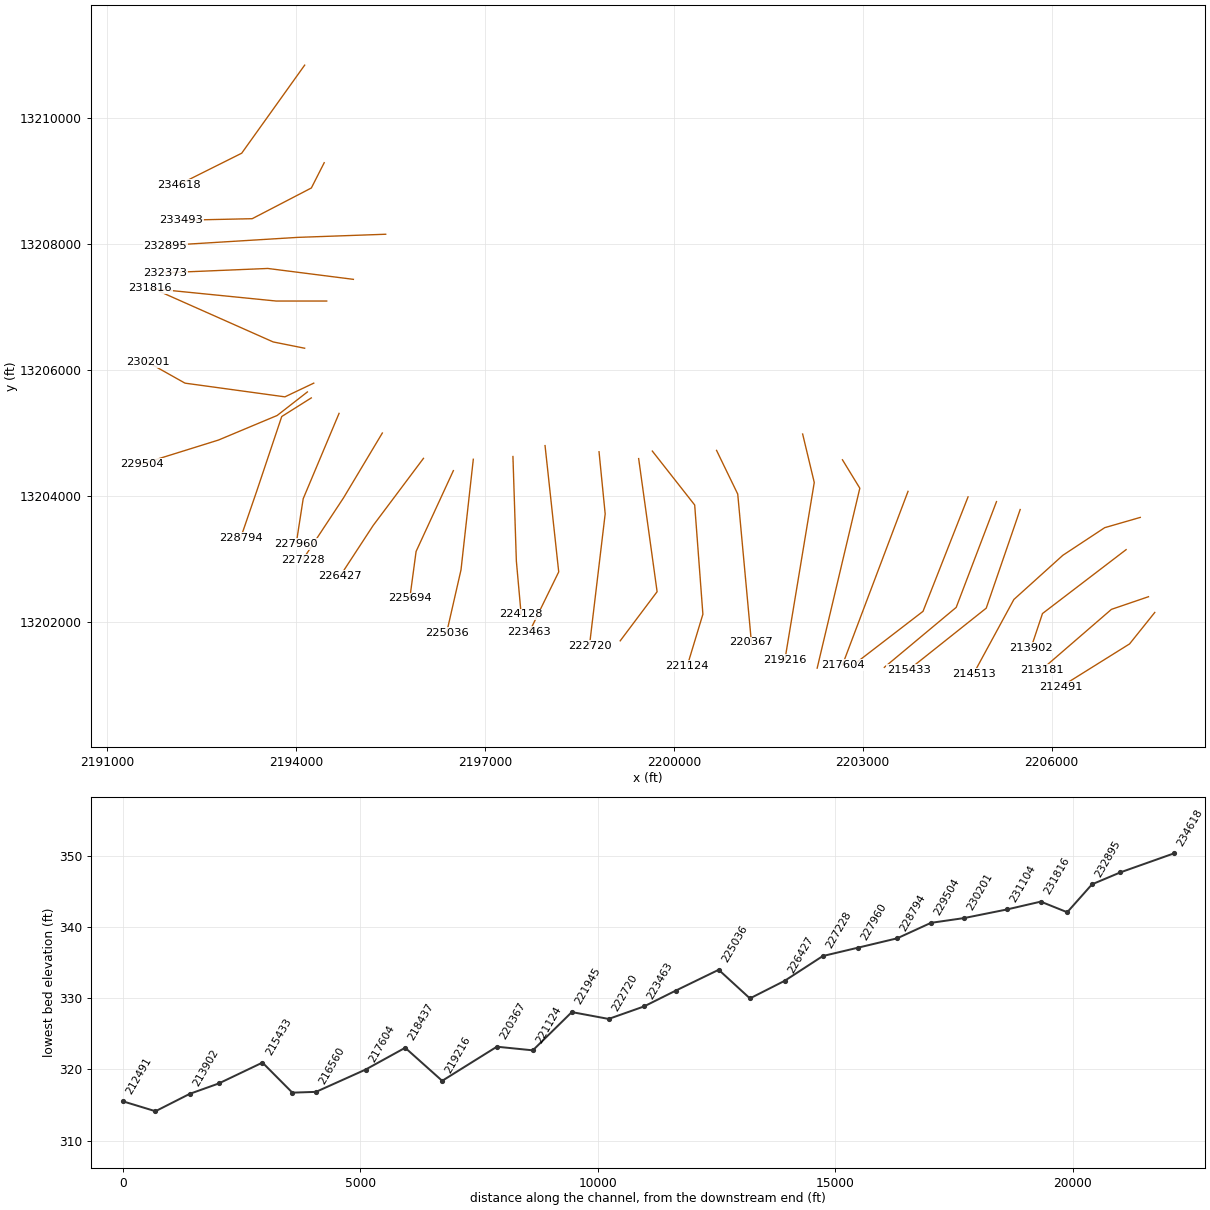
HEC-RAS study LAGARTO CREEK.prj: LAGARTO CREEK Base Level Engineering

--- LAGARTO CREEK.g01 (geometry) --- (continued)

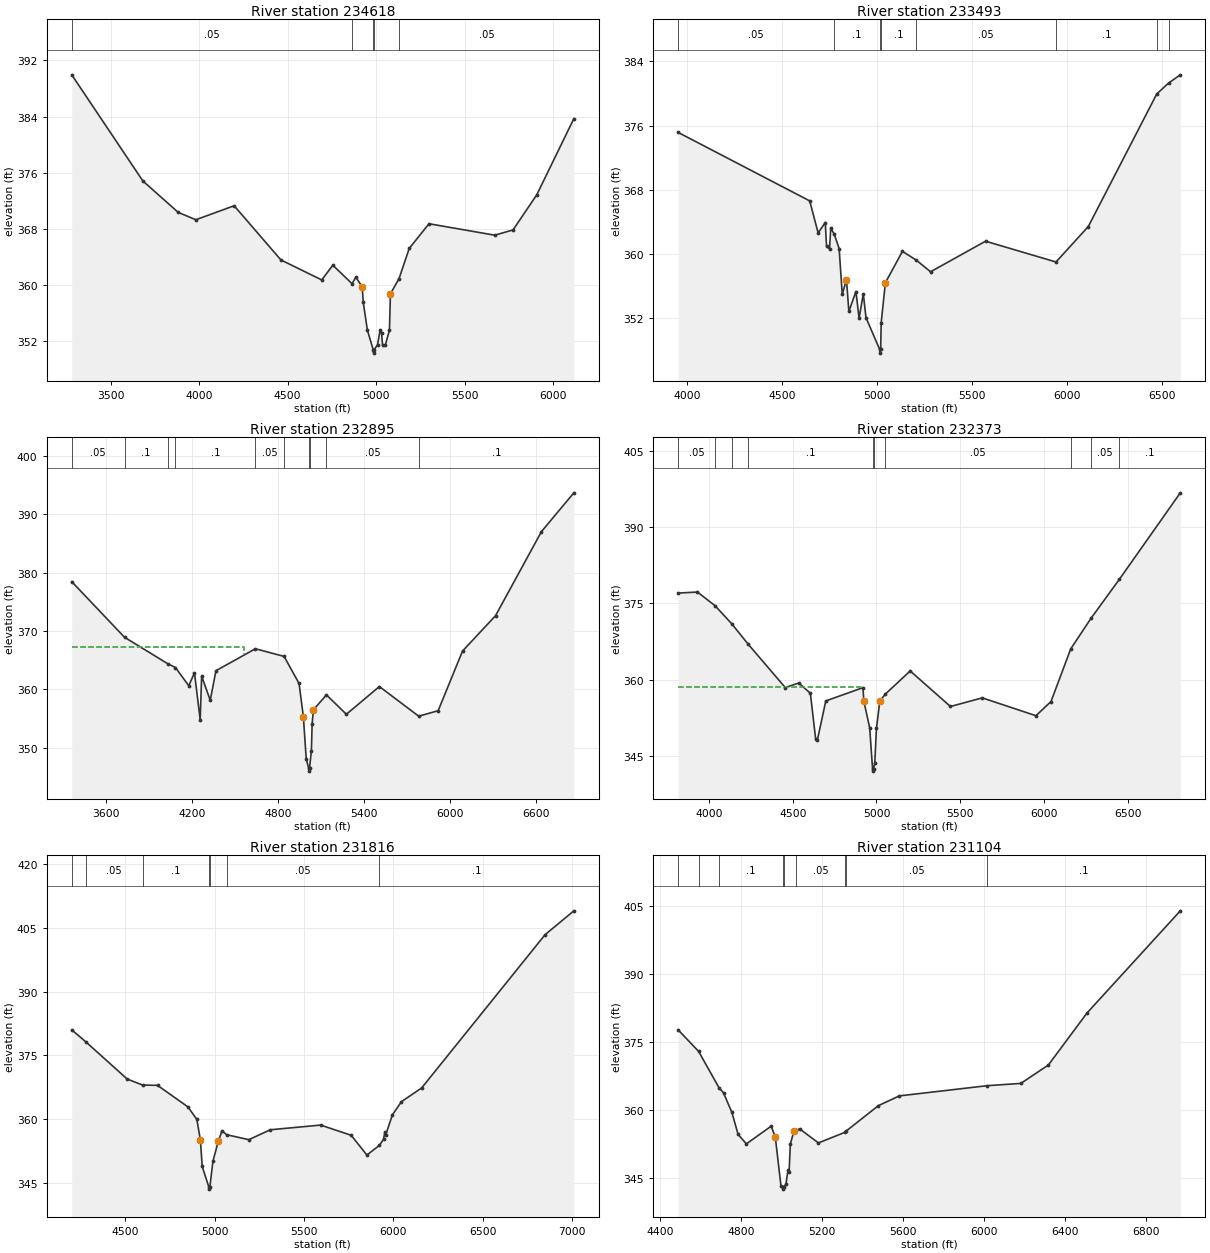
Type RM Length L Ch R = 1 ,234618  ,1125,1125,1125
BEGIN DESCRIPTION:
LAGARTO CREEK 199.0
END DESCRIPTION:
XS GIS Cut Line= 3
      2194137.74     13210846.88      2193137.72     13209446.85
      2192137.75     13208946.87
#Sta/Elev= 30
  3279.5  389.96  3681.4  374.85  3881.7  370.37  3981.2  369.33  4197.5  371.32
  4461.7  363.61  4692.8  360.76  4755.4  362.86  4864.2  360.22  4885.7  361.17
  4921.4  359.76  4927.5  357.57  4950.8  353.61  4983.5  350.84  4986.2  350.34
  4989.5  350.84  5008.4  351.55  5022.4  353.57  5030.7  353.27  5036.3   351.5
  5053.1  351.54  5075.5  353.63  5081.1  358.78  5129.8  360.96  5187.3  365.24
  5299.1  368.76  5670.8  367.13  5774.2  367.88  5908.4  372.88    6118  383.72
#Mann= 5 ,-1 , 0
  3279.5     .05       0  4864.2      .1       0  4983.5     .07       0
  4989.5      .1       0  5129.8     .05       0
Bank Sta=4921.4,5081.1
XS Rating Curve= 0 ,0
Exp/Cntr=0.3,0.1

Type RM Length L Ch R = 1 ,233493  ,598,598,598
BEGIN DESCRIPTION:
LAGARTO CREEK 198.0
END DESCRIPTION:
XS GIS Cut Line= 4
      2194448.05     13209295.85       2194244.1     13208894.12
      2193304.73      13208405.9       2192173.8     13208381.18
#Sta/Elev= 30
  3953.5  375.16  4644.9  366.64  4689.1  362.66  4726.8  363.94  4733.3  361.02
  4749.3  360.64  4755.4  363.22  4773.4  362.54  4799.7   360.7  4816.1  355.01
  4838.2  356.84  4850.8  352.88  4888.1  355.35  4904.6  352.02  4926.7  355.08
  4940.9   352.1  5012.1  348.18  5014.9  347.68  5018.1  348.18  5020.8  351.47
  5042.9  356.45  5132.5  360.35  5205.6  359.26  5280.5  357.81  5569.7  361.62
  5940.1  359.03  6110.1  363.45  6470.1  379.96  6531.9  381.31  6593.9  382.34
#Mann= 8 ,-1 , 0
  3953.5     .05       0  4773.4      .1       0  5012.1     .07       0
  5018.1      .1       0  5205.6     .05       0  5940.1      .1       0
  6470.1     .05       0  6531.9      .1       0
Bank Sta=4838.2,5042.9
XS Rating Curve= 0 ,0
Exp/Cntr=0.3,0.1

Type RM Length L Ch R = 1 ,232895  ,522,522,522
BEGIN DESCRIPTION:
LAGARTO CREEK 197.0
END DESCRIPTION:
XS GIS Cut Line= 3
      2195424.47     13208158.69      2194033.98     13208109.25
      2191921.53     13207979.54
#Sta/Elev= 30
    3359  378.45  3727.5  368.93  4028.7  364.41  4083.4  363.75  4176.3  360.63
  4216.3  362.84  4256.3  354.77  4266.3  362.28  4326.4  358.14  4366.4   363.2
  4641.8  366.96  4842.4  365.65    4947  361.01  4977.1  355.33  4997.1   348.1
  5014.1   346.5  5016.9     346  5020.1   346.5  5033.2  349.49  5038.2   354.1
  5047.2   356.5  5138.2  359.06  5277.6  355.74  5508.1  360.49  5782.9  355.41
  5918.8  356.35  6089.1  366.57  6319.6  372.62  6640.2  387.02  6866.8  393.67
#Mann= 10 ,-1 , 0
    3359     .05       0  3727.5      .1       0  4028.7     .05       0
  4083.4      .1       0  4641.8     .05       0  4842.4      .1       0
  5014.1     .07       0  5020.1      .1       0  5138.2     .05       0
  5782.9      .1       0
#XS Ineff= 2 , 0
         4561.36  367.18
Permanent Ineff=
       F       F
Bank Sta=4977.1,5047.2
XS Rating Curve= 0 ,0
Exp/Cntr=0.3,0.1

Type RM Length L Ch R = 1 ,232373  ,557,557,557
BEGIN DESCRIPTION:
LAGARTO CREEK 196.0
END DESCRIPTION:
XS GIS Cut Line= 3
      2194911.55      13207441.8      2193551.93     13207614.85
      2191926.54     13207546.86
#Sta/Elev= 30
  3816.7  377.04  3931.4  377.24  4036.8  374.55  4136.2  371.01  4235.5  366.95
  4455.7  358.49  4536.3  359.38  4605.5  357.37  4637.1  348.41  4647.2  348.15
  4697.6  355.86  4919.4  358.47  4925.2  355.76  4959.7  350.57  4976.8  342.58
  4979.6  342.08  4982.8  342.58  4989.9  343.59    5000  350.45  5020.2  355.86
    5054  357.23  5201.5  361.75  5441.7  354.77  5631.9  356.46  5952.2  352.96
  6042.2  355.75  6159.9  366.08  6281.3   372.1  6450.9  379.77  6814.1  396.72
#Mann= 10 ,-1 , 0
  3816.7     .05       0  4036.8     .08       0  4136.2     .05       0
  4235.5      .1       0  4976.8     .07       0  4982.8      .1       0
    5054     .05       0  6159.9      .1       0  6281.3     .05       0
  6450.9      .1       0
#XS Ineff= 2 , 0
         4909.42  358.51
Permanent Ineff=
       F       F
Bank Sta=4925.2,5020.2
XS Rating Curve= 0 ,0
Exp/Cntr=0.3,0.1

Type RM Length L Ch R = 1 ,231816  ,712,712,712
BEGIN DESCRIPTION:
LAGARTO CREEK 195.0
END DESCRIPTION:
XS GIS Cut Line= 3
      2194487.72     13207096.85      2193687.72     13207096.86
       2191687.7     13207296.86
#Sta/Elev= 30
    4200  381.01  4277.8  378.24    4510  369.46  4596.4  368.04    4680  367.97
    4850  362.91    4900  359.97    4920  355.07    4930  348.92    4967  344.07
  4969.7  343.57    4973  344.07    4990  350.13  5020.1  354.81  5040.2  357.24
  5067.3  356.36  5190.9   355.2  5311.5  357.53  5592.9  358.63  5763.8  356.23
  5851.7  351.59  5921.4  353.85  5944.7  355.29  5952.2  357.01  5957.3  356.38
  5994.9  361.06  6045.2  364.14  6158.2  367.36  6849.2  403.41    7010  409.01
#Mann= 7 ,-1 , 0
    4200     .08       0  4277.8     .05       0  4596.4      .1       0
    4967     .07       0    4973      .1       0  5067.3     .05       0
  5921.4      .1       0
Bank Sta=4920,5020.1
XS Rating Curve= 0 ,0
Exp/Cntr=0.3,0.1

Type RM Length L Ch R = 1 ,231104  ,903,903,903
BEGIN DESCRIPTION:
LAGARTO CREEK 194.0
END DESCRIPTION:
XS GIS Cut Line= 3
      2194137.72     13206346.86      2193637.72     13206446.85
      2191837.69     13207246.87
#Sta/Elev= 30
  4490.1  377.67  4590.5  372.95  4691.2  364.92  4714.5  363.69  4755.2  359.42
  4785.8  354.57  4826.6  352.48    4949  356.39  4969.4  354.02  4997.5  343.17
  5005.9  342.97  5008.6  342.47  5011.9  342.97  5021.9  343.53  5032.1  346.66
  5037.6  346.21  5043.8  352.42  5060.9  355.22  5072.7  355.46  5089.6   355.8
  5182.6  352.69  5312.1  355.01  5318.4  355.28  5478.1  360.92    5582  363.09
  6016.7  365.35  6181.9  365.85    6318  369.91  6509.5  381.45  6969.8  404.02
#Mann= 9 ,-1 , 0
  4490.1      .1       0  4590.5     .08       0  4691.2      .1       0
  5005.9     .07       0  5011.9      .1       0  5072.7     .05       0
  5312.1      .1       0  5318.4     .05       0  6016.7      .1       0
Bank Sta=4969.4,5060.9
XS Rating Curve= 0 ,0
Exp/Cntr=0.3,0.1

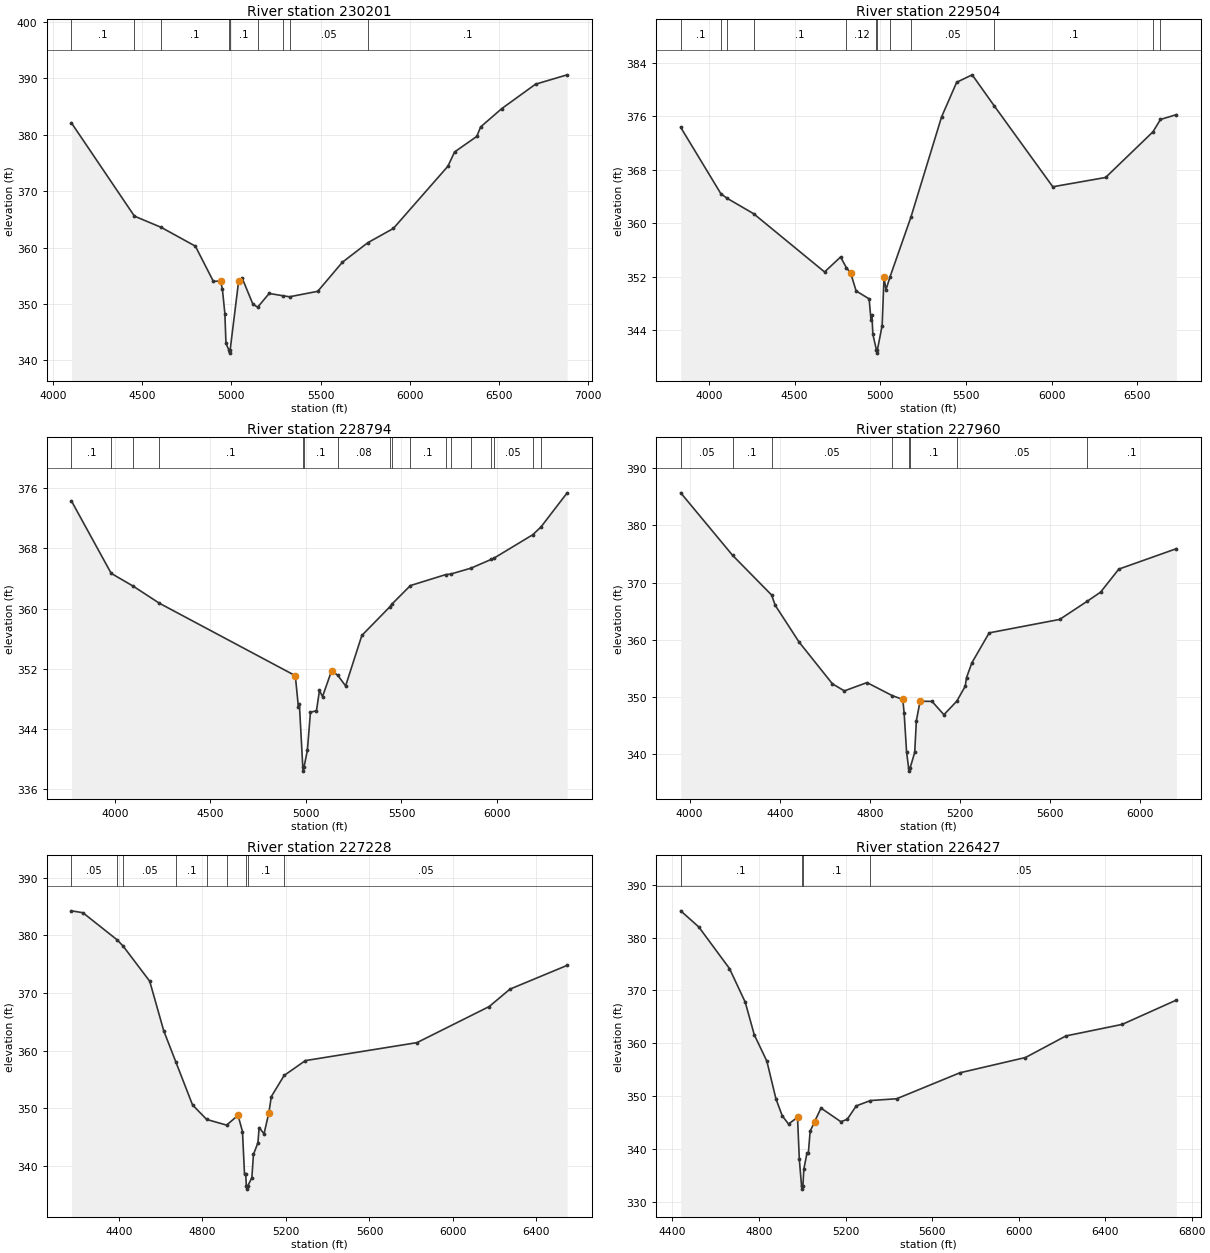
Type RM Length L Ch R = 1 ,230201  ,697,697,697
BEGIN DESCRIPTION:
LAGARTO CREEK 193.0
END DESCRIPTION:
XS GIS Cut Line= 4
      2194281.84     13205791.78      2193823.84     13205573.96
      2192237.56     13205791.79      2191651.91     13206120.87
#Sta/Elev= 30
  4103.1  382.11  4456.2  365.57  4606.8  363.57  4798.1  360.24  4899.1  353.99
  4939.4  354.06  4949.5  352.65  4963.5  348.29  4969.7  342.97  4986.9  341.76
  4989.7  341.26  4992.9  341.76  5040.6  354.02  5060.6  354.56  5121.1  349.92
  5147.6  349.42    5212  351.85  5287.1  351.45  5326.3  351.26  5484.5  352.23
  5622.3  357.38    5765  360.85  5908.4  363.38  6214.3  374.42  6251.9  376.96
  6376.2  379.71  6397.9   381.4  6516.5  384.65  6705.8  388.98  6883.2  390.64
#Mann= 9 ,-1 , 0
  4103.1      .1       0  4456.2     .08       0  4606.8      .1       0
  4986.9     .07       0  4992.9      .1       0  5147.6     .05       0
  5287.1      .1       0  5326.3     .05       0    5765      .1       0
Bank Sta=4939.4,5040.6
XS Rating Curve= 0 ,0
Exp/Cntr=0.3,0.1

Type RM Length L Ch R = 1 ,229504  ,710,710,710
BEGIN DESCRIPTION:
LAGARTO CREEK 192.0
END DESCRIPTION:
XS GIS Cut Line= 4
      2194181.29     13205652.14      2193700.96     13205277.93
      2192768.19     13204886.94       2191551.6     13204507.46
#Sta/Elev= 30
  3834.6  374.33  4069.4   364.4  4105.5  363.73  4260.2  361.43  4674.7  352.72
  4768.2  354.96  4801.9  353.36  4826.6  352.58    4859  349.88  4934.9   348.7
  4945.5   345.6    4951  346.34  4956.6  343.41  4977.2  341.09  4979.9  340.59
  4983.2  341.09  5010.8   344.7  5021.7  351.95  5033.1  350.06  5057.5  352.04
  5178.2  360.86  5357.8  375.89  5446.1  381.07  5536.6  382.18  5665.5  377.54
  6007.3  365.45  6315.6  366.84  6592.5  373.67    6636  375.51  6729.3  376.23
#Mann= 12 ,-1 , 0
  3834.6      .1       0  4069.4     .05       0  4105.5     .08       0
  4260.2      .1       0  4801.9     .12       0  4977.2     .07       0
  4983.2     .12       0  5057.5      .1       0  5178.2     .05       0
  5665.5      .1       0  6592.5     .08       0    6636      .1       0
Bank Sta=4826.6,5021.7
XS Rating Curve= 0 ,0
Exp/Cntr=0.3,0.1

Type RM Length L Ch R = 1 ,228794  ,834,834,834
BEGIN DESCRIPTION:
LAGARTO CREEK 191.0
END DESCRIPTION:
XS GIS Cut Line= 4
      2194242.75      13205557.2      2193773.57     13205261.17
        2193377.     13204077.05      2193120.64     13203330.25
#Sta/Elev= 30
  3773.6  374.28  3981.5  364.67  4095.4  362.99  4233.9   360.7  4944.6  351.09
  4960.6  346.98  4965.9  347.33  4983.8  338.92  4986.5  338.42  4989.8  338.92
  5007.8  341.18  5023.7  346.23  5055.3  346.44  5071.1  349.14  5086.9  348.31
  5134.4  351.74  5165.9  351.16  5207.8  349.73  5292.6  356.43  5439.5  360.24
  5449.9  360.59  5546.7  363.05  5730.4   364.5  5757.8  364.58  5863.4  365.36
    5969  366.52  5982.6  366.67  6186.8   369.8    6230  370.84  6366.7  375.36
#Mann= 17 ,-1 , 0
  3773.6      .1       0  3981.5     .05       0  4095.4     .08       0
  4233.9      .1       0  4983.8     .07       0  4989.8      .1       0
  5165.9     .08       0  5439.5     .05       0  5449.9     .08       0
  5546.7      .1       0  5730.4     .08       0  5757.8      .1       0
  5863.4     .05       0    5969      .1       0  5982.6     .05       0
  6186.8      .1       0    6230     .05       0
Bank Sta=4944.6,5134.4
XS Rating Curve= 0 ,0
Exp/Cntr=0.3,0.1

Type RM Length L Ch R = 1 ,227960  ,732,732,732
BEGIN DESCRIPTION:
LAGARTO CREEK 190.0
END DESCRIPTION:
XS GIS Cut Line= 3
      2194683.99      13205311.4      2194114.29     13203954.17
      2194002.65     13203234.12
#Sta/Elev= 30
  3960.5  385.68  4190.7  374.77  4363.9  367.84  4380.1  366.04    4486  359.62
    4634  352.33  4686.9   351.1  4787.4  352.55  4900.3  350.26  4946.3  349.61
  4952.3  347.24  4963.2  340.42  4972.4  337.59  4975.2  337.09  4978.4  337.59
  4999.2  340.35  5006.6  345.89    5023  349.29  5075.9  349.27  5128.9  346.94
  5186.2  349.31  5223.5  351.92  5229.3  353.42  5253.1  356.01  5329.8  361.23
  5642.9  363.58  5763.9  366.72  5824.4  368.34  5905.3  372.36  6161.1  375.93
#Mann= 8 ,-1 , 0
  3960.5     .05       0  4190.7      .1       0  4363.9     .05       0
  4900.3      .1       0  4972.4     .07       0  4978.4      .1       0
  5186.2     .05       0  5763.9      .1       0
Bank Sta=4946.3,5023
XS Rating Curve= 0 ,0
Exp/Cntr=0.3,0.1

Type RM Length L Ch R = 1 ,227228  ,801,801,801
BEGIN DESCRIPTION:
LAGARTO CREEK 188.0
END DESCRIPTION:
XS GIS Cut Line= 3
      2195371.04     13204998.68      2194756.62     13203970.92
      2194108.68     13202987.85
#Sta/Elev= 30
  4172.3  384.26  4227.2  383.93  4390.2  379.25  4419.6  378.15  4547.2  372.04
  4614.3  363.44  4672.6     358  4752.4  350.55  4820.2  348.03  4915.6  347.05
  4970.3  348.75  4991.7  345.92  5001.4  338.52  5007.2  338.53  5010.3  336.43
    5013  335.93  5016.3  336.43  5036.6  337.93  5044.2  341.96  5065.6  343.98
  5071.5  346.62  5094.8  345.53  5118.1   349.2  5129.8     352  5191.2  355.67
  5292.9  358.25  5827.4  361.37  6173.7  367.64    6273  370.66  6547.1  374.79
#Mann= 9 ,-1 , 0
  4172.3     .05       0  4390.2      .1       0  4419.6     .05       0
  4672.6      .1       0  4820.2     .05       0  4915.6      .1       0
  5010.3     .07       0  5016.3      .1       0  5191.2     .05       0
Bank Sta=4970.3,5118.1
XS Rating Curve= 0 ,0
Exp/Cntr=0.3,0.1

Type RM Length L Ch R = 1 ,226427  ,733,733,733
BEGIN DESCRIPTION:
LAGARTO CREEK 189.0
END DESCRIPTION:
XS GIS Cut Line= 3
      2196024.52      13204596.5       2195225.8     13203529.67
      2194701.75     13202726.87
#Sta/Elev= 30
  4438.3  385.05  4521.9     382  4663.6  374.15  4736.5  367.79  4778.2  361.64
  4836.6  356.63  4878.2  349.56  4907.4  346.33  4936.6  344.77  4978.2  346.02
  4986.6  338.08    4997  332.96  4999.8  332.46    5003  332.96  5007.4  336.25
    5022  339.27  5028.3   339.3  5036.6  343.41  5057.4  345.22  5086.6  347.78
  5178.3  345.21  5207.5  345.63  5249.8  348.19  5315.4   349.2  5436.7  349.54
  5728.4  354.44  6031.9  357.33  6218.9  361.41  6478.9  363.59  6729.7  368.19
#Mann= 4 ,-1 , 0
  4438.3      .1       0    4997     .07       0    5003      .1       0
  5315.4     .05       0
Bank Sta=4978.2,5057.4
XS Rating Curve= 0 ,0
Exp/Cntr=0.3,0.1

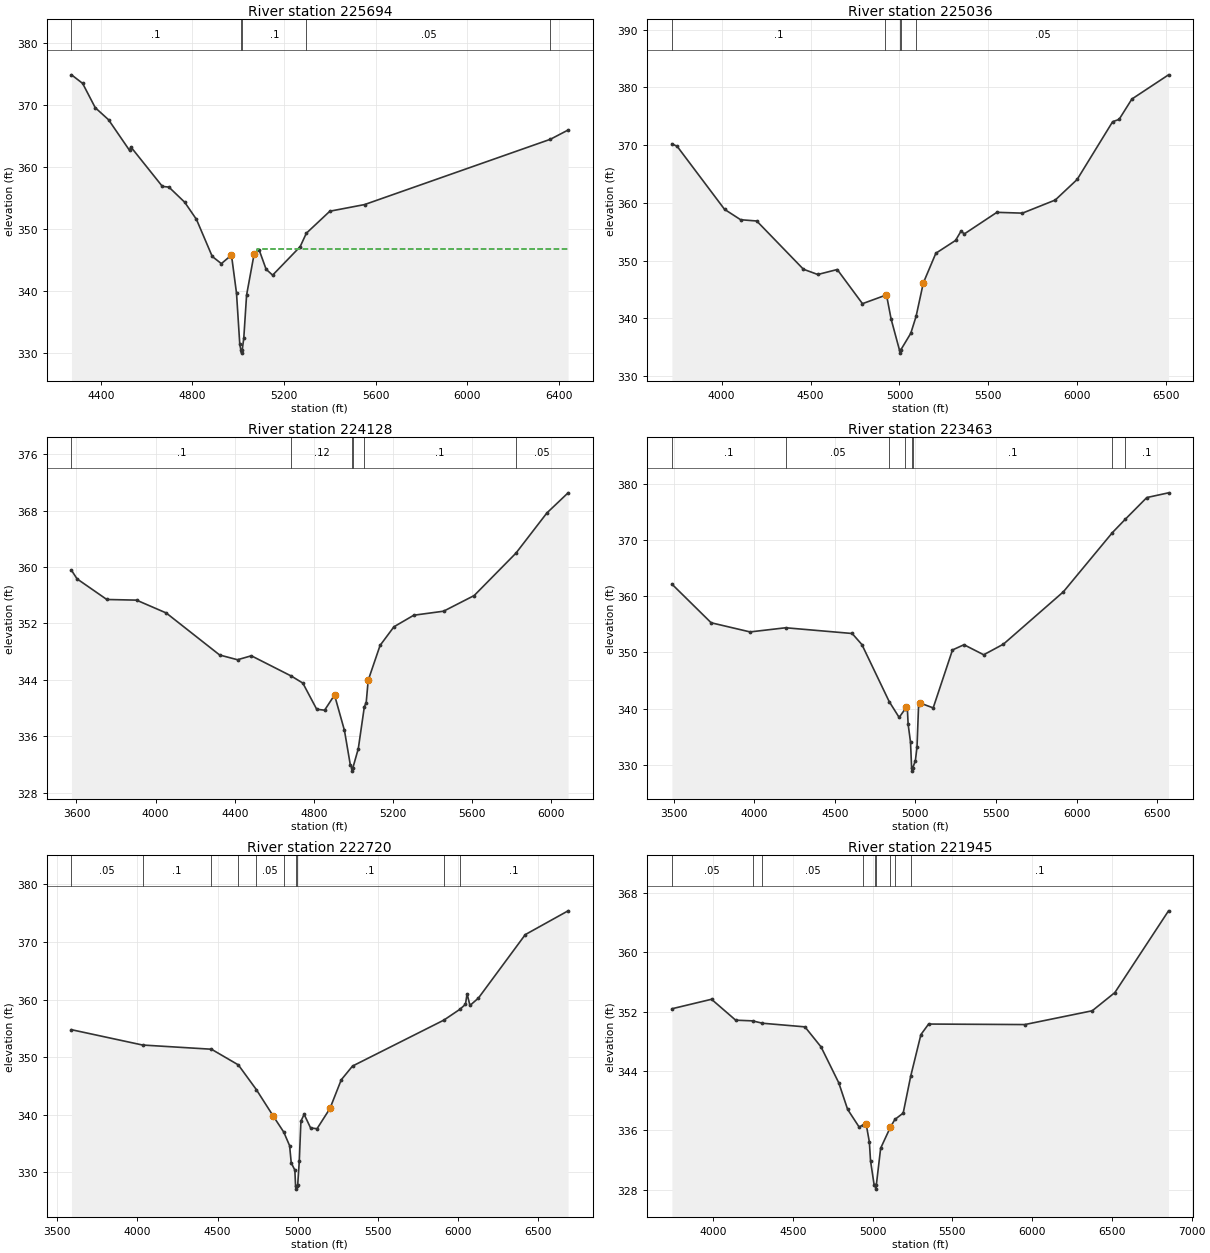
Type RM Length L Ch R = 1 ,225694  ,658,658,658
BEGIN DESCRIPTION:
LAGARTO CREEK 186.0
END DESCRIPTION:
XS GIS Cut Line= 3
      2196499.29     13204401.02      2195907.23     13203116.35
      2195806.96     13202369.89
#Sta/Elev= 30
  4272.1  374.85  4320.7  373.47  4375.8  369.55  4433.8  367.61  4525.6  362.66
  4531.1  363.23  4668.8  356.86  4697.3  356.75  4766.2  354.31  4817.6  351.54
  4886.4  345.57  4926.3  344.41  4970.4  345.79  4992.4  339.65  5006.7  331.41
  5011.4  330.48  5014.2  329.98  5017.4  330.48  5024.2  332.43  5036.4  339.34
  5069.5     346  5091.5  346.59  5121.5  343.51    5150  342.55  5270.3  347.15
  5297.2  349.31  5399.8  352.86  5551.3  353.93  6362.5  364.46  6439.8  365.95
#Mann= 5 ,-1 , 0
  4272.1      .1       0  5011.4     .07       0  5017.4      .1       0
  5297.2     .05       0  6362.5      .1       0
#XS Ineff= 2 , 0
                         5081.04          346.69
Permanent Ineff=
       F       F
Bank Sta=4970.4,5069.5
XS Rating Curve= 0 ,0
Exp/Cntr=0.3,0.1

Type RM Length L Ch R = 1 ,225036  ,908,908,908
BEGIN DESCRIPTION:
LAGARTO CREEK 185.0
END DESCRIPTION:
XS GIS Cut Line= 3
      2196815.81     13204581.74       2196620.5     13202823.97
      2196392.69     13201825.92
#Sta/Elev= 30
  3720.5  370.21  3749.5  369.81  4016.2  358.89  4106.7  357.09  4197.3  356.87
  4459.9  348.52  4540.4  347.61    4650  348.47  4791.9  342.56  4918.9  343.99
  4926.7  344.12  4952.9   339.9  5000.2   334.5    5003     334  5006.2   334.5
  5063.6  337.44  5093.4  340.37    5134  346.15  5204.5  351.29  5315.1   353.5
  5345.3  355.08  5365.4  354.65  5547.7  358.37  5691.3  358.23  5875.9   360.5
    5999  364.06  6198.6  374.06  6234.9  374.46  6306.7  377.98  6512.8  382.17
#Mann= 5 ,-1 , 0
  3720.5      .1       0  4918.9     .12       0  5000.2     .07       0
  5006.2     .12       0  5093.4     .05       0
Bank Sta=4926.7,5134
XS Rating Curve= 0 ,0
Exp/Cntr=0.3,0.1

Type RM Length L Ch R = 1 ,224128  ,665,665,665
BEGIN DESCRIPTION:
LAGARTO CREEK 184.0
END DESCRIPTION:
XS GIS Cut Line= 3
      2197445.16     13204625.18      2197499.41     13202965.02
      2197575.22     13202120.26
#Sta/Elev= 30
  3574.9  359.53  3603.2  358.31  3753.3  355.39  3903.4   355.3  4053.5  353.48
  4323.6  347.52  4413.7  346.85  4483.7  347.41    4686  344.53  4743.8  343.54
  4813.9  339.83  4853.9   339.7  4903.9  341.85    4954  336.84    4984   331.9
    4991  331.56  4993.7  331.06    4997  331.56    5024  334.24  5054.7   340.2
    5064  340.77    5074  343.93  5134.1  348.88  5204.1  351.52  5304.4  353.16
    5455  353.73  5609.6  355.95  5820.6  361.96  5977.1  367.66  6084.1  370.51
#Mann= 6 ,-1 , 0
  3574.9      .1       0    4686     .12       0    4991     .07       0
    4997     .12       0  5054.7      .1       0  5820.6     .05       0
Bank Sta=4903.9,5074
XS Rating Curve= 0 ,0
Exp/Cntr=0.3,0.1

Type RM Length L Ch R = 1 ,223463  ,743,743,743
BEGIN DESCRIPTION:
LAGARTO CREEK 183.0
END DESCRIPTION:
XS GIS Cut Line= 3
      2197955.14      13204798.8      2198172.15     13202791.41
      2197705.59     13201836.59
#Sta/Elev= 30
  3489.3  362.15  3732.7  355.27  3974.1  353.64  4195.2  354.38  4607.7  353.36
  4668.1  351.39  4837.5  341.24  4899.4  338.41  4936.6  339.92  4939.7  340.28
  4949.7   340.4  4955.1   337.2  4969.8  334.05  4976.9  329.35  4979.6  328.85
  4982.9  329.35    5000  330.72  5010.1   333.1  5020.1  340.65  5030.2  340.97
  5110.6  340.11  5230.4  350.43  5301.7  351.36  5424.1  349.57  5546.9  351.47
  5918.4  360.78  6223.2  371.34  6302.2  373.69  6436.3  377.57  6571.1  378.41
#Mann= 8 ,-1 , 0
  3489.3      .1       0  4195.2     .05       0  4837.5     .07       0
  4936.6      .1       0  4976.9     .07       0  4982.9      .1       0
  6223.2     .05       0  6302.2      .1       0
Bank Sta=4939.7,5030.2
XS Rating Curve= 0 ,0
Exp/Cntr=0.3,0.1

Type RM Length L Ch R = 1 ,222720  ,775,775,775
BEGIN DESCRIPTION:
LAGARTO CREEK 182.0
END DESCRIPTION:
XS GIS Cut Line= 3
      2198812.35     13204701.09        2198910.     13203713.72
      2198660.57     13201620.72
#Sta/Elev= 30
    3588  354.78  4031.6  352.12  4461.7  351.39  4629.5  348.67  4742.4  344.36
  4848.9  339.72  4913.3  336.99  4949.6  334.64  4959.7  331.66  4982.3   330.4
  4986.9   327.6  4989.7   327.1  4992.9   327.6    5000   327.8  5010.1  332.02
  5020.1   338.9  5040.3  340.08  5080.6  337.72  5120.8  337.59  5201.4   341.1
  5271.9  346.08  5342.4  348.47  5912.1  356.44    6012  358.31  6047.4  359.19
  6057.4  361.02  6075.4  358.99  6127.9  360.26  6420.7  371.29    6688  375.42
#Mann= 10 ,-1 , 0
    3588     .05       0  4031.6      .1       0  4461.7     .05       0
  4629.5      .1       0  4742.4     .05       0  4913.3      .1       0
  4986.9     .07       0  4992.9      .1       0  5912.1     .05       0
    6012      .1       0
Bank Sta=4848.9,5201.4
XS Rating Curve= 0 ,0
Exp/Cntr=0.3,0.1

Type RM Length L Ch R = 1 ,221945  ,821,821,821
BEGIN DESCRIPTION:
LAGARTO CREEK 181.0
END DESCRIPTION:
XS GIS Cut Line= 3
      2199441.68     13204592.67      2199734.65     13202476.74
       2199148.7     13201695.47
#Sta/Elev= 30
  3742.3  352.37  3990.5  353.65  4141.9  350.83  4247.3  350.74  4309.6  350.42
    4576  349.93  4676.9  347.23    4788  342.39  4843.5  338.81  4915.3  336.44
    4941  336.71  4959.6  336.84  4979.8  334.41  4987.1  331.88  5010.1  328.57
  5017.2  328.56  5019.9  328.06  5023.2  328.56  5050.5  333.57  5110.1  336.34
    5111  336.39  5139.7  337.45  5191.8  338.31  5239.1   343.3  5302.9  348.89
  5351.1  350.31  5953.9  350.24  6376.8   352.1  6518.5  354.55    6855  365.57
#Mann= 9 ,-1 , 0
  3742.3     .05       0  4247.3      .1       0  4309.6     .05       0
    4941      .1       0  5017.2     .07       0  5023.2      .1       0
  5110.1     .05       0  5139.7     .08       0  5239.1      .1       0
Bank Sta=4959.6,5111
XS Rating Curve= 0 ,0
Exp/Cntr=0.3,0.1

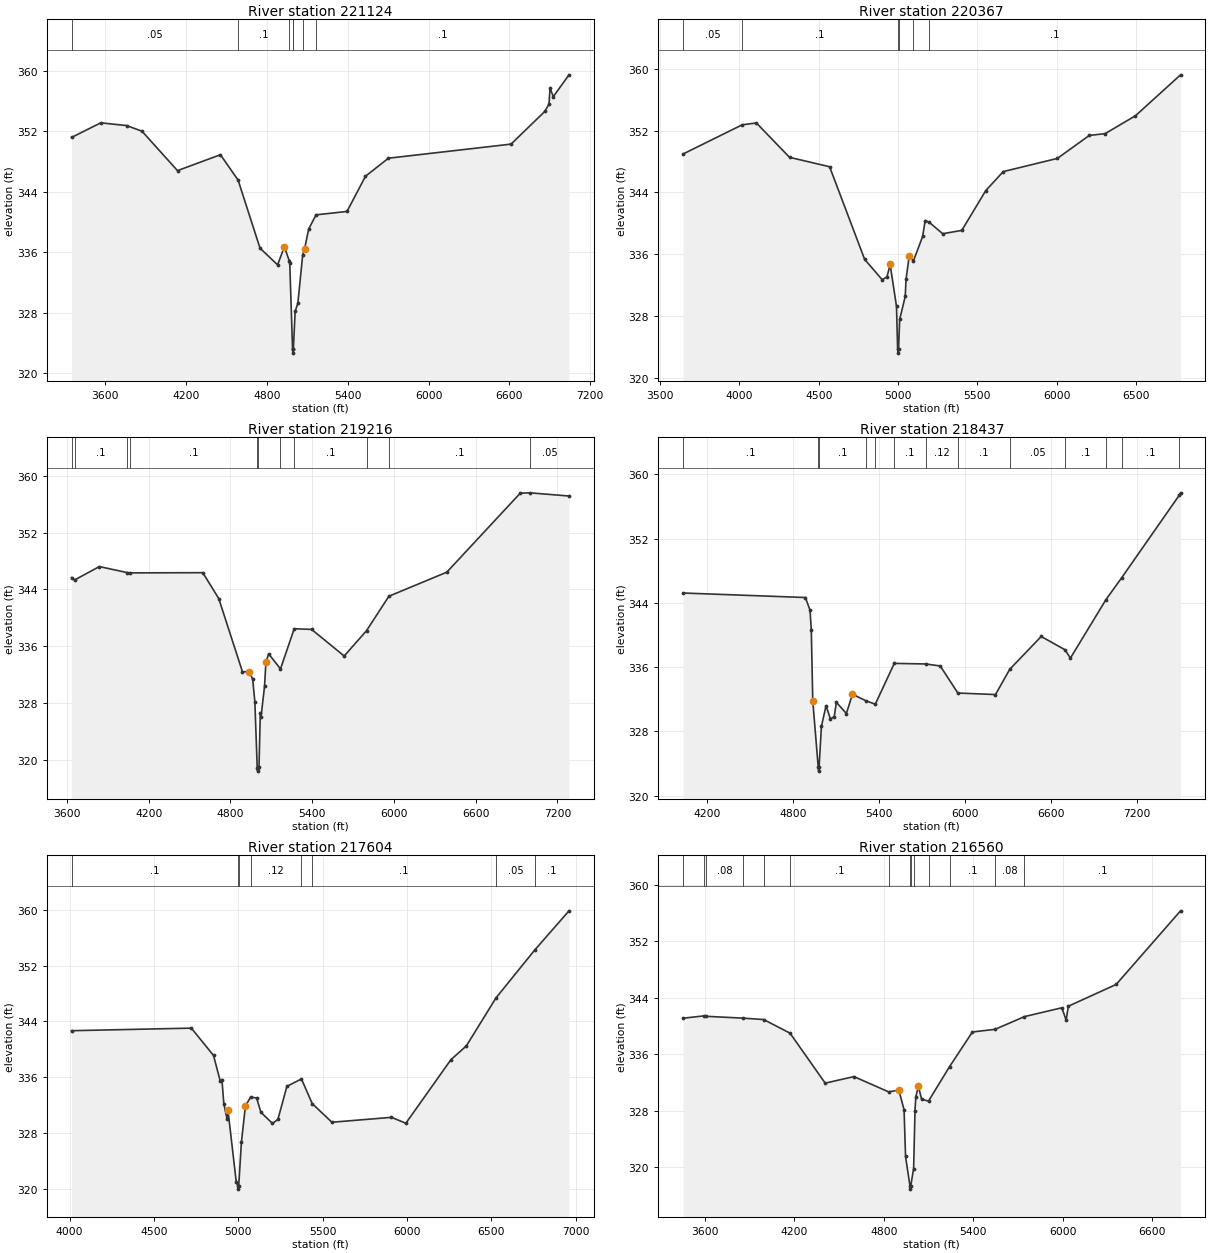
Type RM Length L Ch R = 1 ,221124  ,757,757,757
BEGIN DESCRIPTION:
LAGARTO CREEK 180.0
END DESCRIPTION:
XS GIS Cut Line= 4
      2199658.68     13204712.01      2200331.44     13203854.78
      2200461.65     13202118.67       2200212.4     13201295.05
#Sta/Elev= 30
  3350.8  351.17  3567.5   353.1    3760  352.74  3873.9  351.99    4137  346.79
  4455.5  348.89  4586.6  345.54  4749.3  336.55  4879.7  334.35  4929.8  336.72
  4967.1  334.85  4969.9  334.58  4990.7  323.19  4993.5  322.69  4996.7  323.19
    5010  328.22  5030.1  329.28    5066  335.69  5080.2  336.47  5110.3  339.07
  5164.9  340.95  5394.8   341.4  5531.9  346.05    5702  348.43  6611.8  350.29
  6862.5  354.61  6893.8   355.6  6900.9  357.71  6925.2  356.56    7042  359.44
#Mann= 7 ,-1 , 0
  3350.8     .05       0  4586.6      .1       0  4967.1     .12       0
  4990.7     .07       0  4996.7     .12       0    5066     .08       0
  5164.9      .1       0
Bank Sta=4929.8,5080.2
XS Rating Curve= 0 ,0
Exp/Cntr=0.3,0.1

Type RM Length L Ch R = 1 ,220367  ,1151,1151,1151
BEGIN DESCRIPTION:
LAGARTO CREEK 179.0
END DESCRIPTION:
XS GIS Cut Line= 3
      2200678.67     13204722.82      2201015.03     13204028.39
      2201232.05     13201673.77
#Sta/Elev= 30
  3644.4  348.98  4017.1  352.76  4106.6     353  4315.5  348.55  4568.2  347.33
  4789.1  335.34  4899.6  332.71  4929.7  333.06  4949.8  334.68    4990  329.25
    4997   323.7  4999.7   323.2    5003   323.7    5010  327.56  5044.9  330.54
  5050.2  332.77  5070.3  335.79  5096.2  335.11  5154.6   338.3  5170.7  340.36
  5195.2  340.16  5281.2  338.66  5401.7  339.09  5552.3  344.23  5662.8   346.7
  6004.2  348.41  6205.1  351.38  6305.5  351.62  6496.3  353.93  6780.6  359.23
#Mann= 6 ,-1 , 0
  3644.4     .05       0  4017.1      .1       0    4997     .07       0
    5003      .1       0  5096.2     .08       0  5195.2      .1       0
Bank Sta=4949.8,5070.3
XS Rating Curve= 0 ,0
Exp/Cntr=0.3,0.1

Type RM Length L Ch R = 1 ,219216  ,779,779,779
BEGIN DESCRIPTION:
LAGARTO CREEK 177.0
END DESCRIPTION:
XS GIS Cut Line= 3
      2202045.84     13204983.29      2202230.31     13204212.85
      2201763.75     13201391.79
#Sta/Elev= 30
  3634.1  345.67  3656.3  345.34  3838.3  347.23  4040.7  346.39  4059.8  346.34
  4597.5  346.37  4714.6  342.73  4888.5  332.42  4939.2  332.39  4963.8  331.35
  4979.7  328.19    4997  318.91  4999.8  318.41    5003  318.91  5010.1  319.03
  5019.8  326.64  5024.9  326.02  5050.7  330.36  5060.8  333.74  5080.9  334.94
  5167.9  332.81  5268.6  338.47  5396.2  338.38  5635.4  334.63  5799.4   338.2
  5963.5  343.05  6388.6  346.44  6927.6  357.57  6998.5  357.62  7285.7  357.17
#Mann= 11 ,-1 , 0
  3634.1     .08       0  3656.3      .1       0  4040.7     .08       0
  4059.8      .1       0    4997     .07       0    5003      .1       0
  5167.9     .08       0  5268.6      .1       0  5799.4     .12       0
  5963.5      .1       0  6998.5     .05       0
Bank Sta=4939.2,5060.8
XS Rating Curve= 0 ,0
Exp/Cntr=0.3,0.1

Type RM Length L Ch R = 1 ,218437  ,833,833,833
BEGIN DESCRIPTION:
LAGARTO CREEK 176.0
END DESCRIPTION:
XS GIS Cut Line= 3
      2202677.87     13204573.44      2202953.89     13204121.77
      2202276.49     13201261.62
#Sta/Elev= 30
    4034  345.22    4887  344.66  4919.2  343.08  4928.1  340.64  4938.3  331.81
  4976.4  323.55  4979.2  323.05  4982.4  323.55  4998.6  328.61  5030.8  331.18
  5061.7  329.55  5088.2  329.84  5102.8  331.62  5172.7  330.22    5215  332.62
  5307.8  331.82  5374.2  331.38  5506.8  336.46  5725.2  336.39    5827  336.14
    5950  332.77  6212.4  332.58  6311.9  335.73  6531.2  339.81  6696.5  338.16
  6734.8  337.12  6982.9  344.41  7091.8  347.11  7492.4  357.36  7502.6  357.69
#Mann= 13 ,-1 , 0
    4034      .1       0  4976.4     .07       0  4982.4      .1       0
  5307.8     .12       0  5374.2     .05       0  5506.8      .1       0
  5725.2     .12       0    5950      .1       0  6311.9     .05       0
  6696.5      .1       0  6982.9     .05       0  7091.8      .1       0
  7492.4     .05       0
Bank Sta=4938.3,5215
XS Rating Curve= 0 ,0
Exp/Cntr=0.3,0.1

Type RM Length L Ch R = 1 ,217604  ,1044,1044,1044
BEGIN DESCRIPTION:
LAGARTO CREEK 175.0
END DESCRIPTION:
XS GIS Cut Line= 2
      2203719.18     13204071.63      2202677.93     13201311.71
#Sta/Elev= 30
  4011.6  342.68  4722.1  343.05  4853.6  339.13  4893.1  335.48  4903.3  335.69
  4914.5  332.24  4933.5  330.08  4938.8  331.35  4988.5  320.97    4997  320.49
  4999.8  319.99    5003  320.49  5018.7  326.67  5042.8  331.93    5074  333.18
  5109.3  333.04  5134.2     331  5203.1   329.4  5235.1  329.97  5288.6  334.71
  5374.8  335.77  5438.7  332.24  5555.1  329.57  5908.5  330.27    5994  329.43
  6261.2  338.53  6352.5   340.5  6528.7  347.39  6758.2  354.24  6961.4  359.85
#Mann= 8 ,-1 , 0
  4011.6      .1       0    4997     .07       0    5003      .1       0
    5074     .12       0  5374.8     .05       0  5438.7      .1       0
  6528.7     .05       0  6758.2      .1       0
Bank Sta=4938.8,5042.8
XS Rating Curve= 0 ,0
Exp/Cntr=0.3,0.1

Type RM Length L Ch R = 1 ,216560  ,498,498,498
BEGIN DESCRIPTION:
LAGARTO CREEK 174.0
END DESCRIPTION:
XS GIS Cut Line= 3
      2204672.62     13203983.81      2203957.52      13202164.7
      2202866.09     13201324.17
#Sta/Elev= 30
    3456   341.1  3595.7  341.43  3609.4  341.37  3858.6  341.11  3996.1  340.91
  4172.6  338.98    4408  331.89  4600.4  332.82  4833.4  330.65  4901.2  330.91
  4936.3  328.12  4946.3  321.49  4975.5  317.36  4978.3  316.86  4981.5  317.36
  5000.3  319.78  5009.6  328.01  5014.9  329.94  5032.2  331.46  5053.7  329.61
  5100.2  329.35  5241.2  334.24  5394.3  339.15  5545.6  339.52    5743  341.33
  5993.1  342.58  6022.1  340.82  6036.6   342.8    6357  345.89  6788.2  356.33
#Mann= 14 ,-1 , 0
    3456     .08       0  3595.7     .05       0  3609.4     .08       0
  3858.6      .1       0  3996.1     .05       0  4172.6      .1       0
  4833.4     .12       0  4975.5     .07       0  4981.5     .12       0
  5000.3      .1       0  5100.2     .08       0  5241.2      .1       0
  5545.6     .08       0    5743      .1       0
Bank Sta=4901.2,5032.2
XS Rating Curve= 0 ,0
Exp/Cntr=0.3,0.1

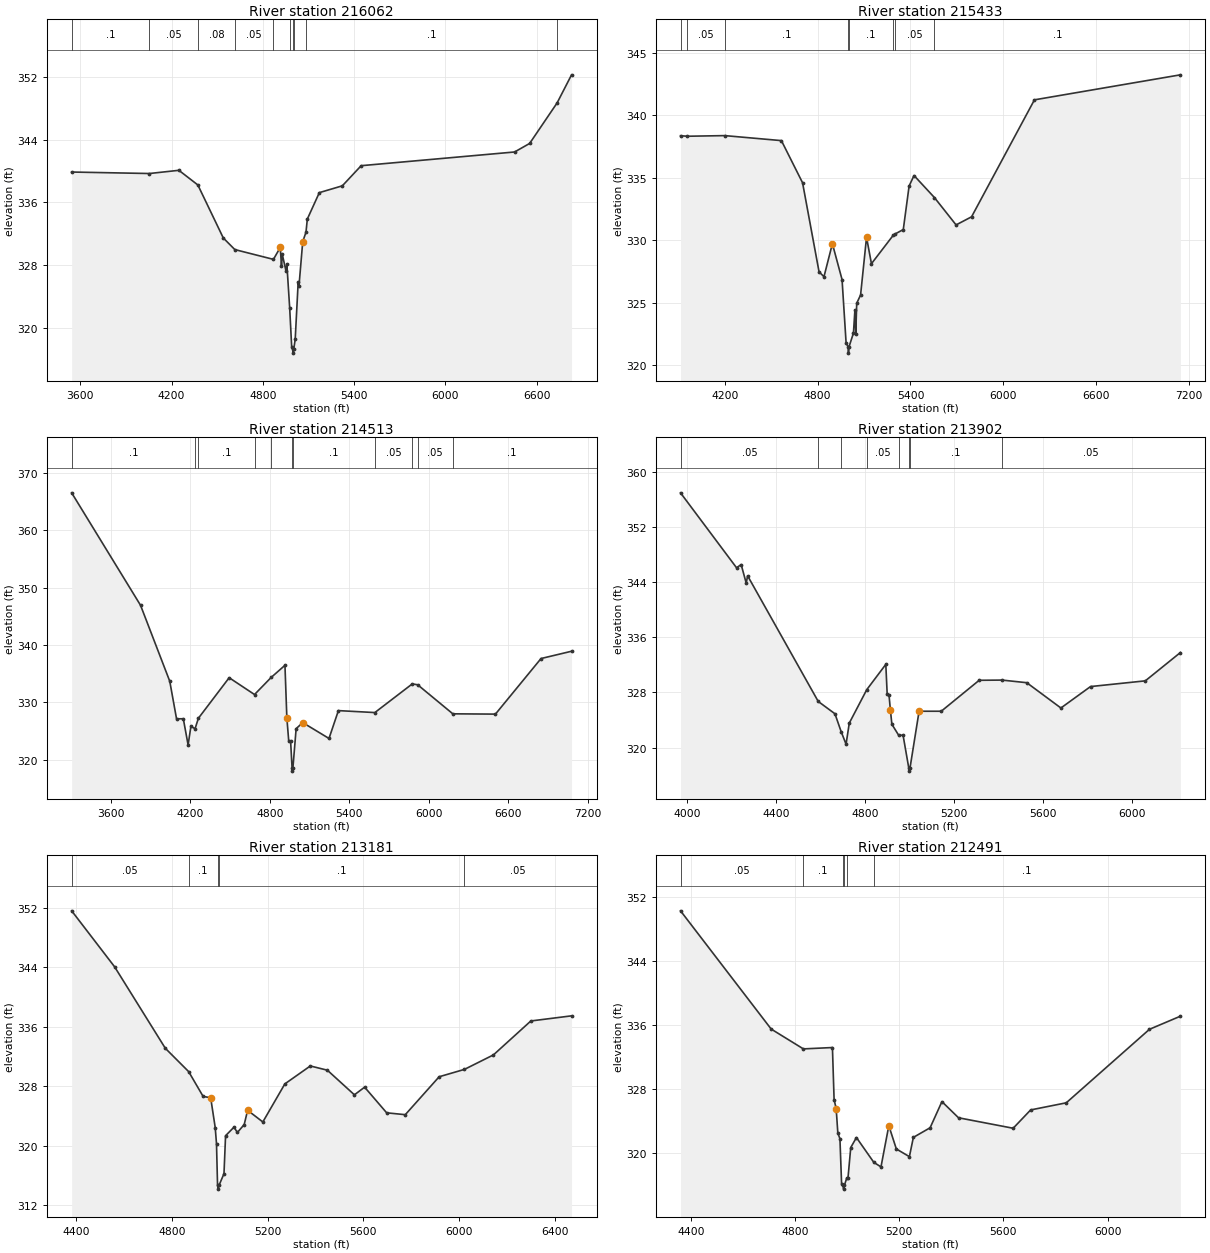
Type RM Length L Ch R = 1 ,216062  ,629,629,629
BEGIN DESCRIPTION:
LAGARTO CREEK 173.0
END DESCRIPTION:
XS GIS Cut Line= 3
      2205124.23     13203908.47      2204484.42     13202227.42
      2203342.79     13201273.97
#Sta/Elev= 30
  3543.1  339.87  4053.8  339.68  4247.9  340.09  4372.6  338.22  4539.9  331.45
  4615.7  329.97  4869.5  328.72  4914.4  330.25  4922.3  327.93  4927.7  329.35
  4952.4  327.21  4957.8  328.09  4976.4  322.48  4989.3  317.59    4997  317.25
  4999.7  316.75    5003  317.25  5012.6  318.51    5032  325.77  5037.4  325.31
  5062.1  330.99  5083.4  332.18  5092.3  333.87  5171.2  337.24  5322.4  338.11
  5446.2  340.68  6454.8  342.43  6553.7  343.52  6734.1  348.69  6829.2  352.28
#Mann= 10 ,-1 , 0
  3543.1      .1       0  4053.8     .05       0  4372.6     .08       0
  4615.7     .05       0  4869.5     .12       0  4976.4     .08       0
    4997     .07       0    5003     .08       0  5083.4      .1       0
  6734.1     .08       0
Bank Sta=4914.4,5062.1
XS Rating Curve= 0 ,0
Exp/Cntr=0.3,0.1

Type RM Length L Ch R = 1 ,215433  ,920,920,920
BEGIN DESCRIPTION:
LAGARTO CREEK 172.0
END DESCRIPTION:
XS GIS Cut Line= 3
      2205500.59     13203783.02      2204961.15     13202214.88
      2203732.22     13201236.75
#Sta/Elev= 30
  3914.6  338.35  3959.6  338.31  4200.7  338.36  4566.2  337.96  4702.9  334.59
  4809.4  327.47  4841.2  327.08  4895.5  329.72    4958  326.85    4984  321.81
  4996.8  321.47  4999.5  320.97  5002.8  321.47  5031.5  322.57  5041.1  324.43
  5046.4  322.47  5052.7  324.96  5077.7  325.62  5116.1  330.23  5147.8  328.12
    5289   330.4  5299.6  330.49  5353.5  330.85  5391.1  334.33  5422.8  335.17
  5554.5  333.41  5694.5  331.22  5794.6  331.87  6200.6  341.22  7143.6  343.22
#Mann= 8 ,-1 , 0
  3914.6      .1       0  3959.6     .05       0  4200.7      .1       0
  4996.8     .07       0  5002.8      .1       0    5289     .08       0
  5299.6     .05       0  5554.5      .1       0
Bank Sta=4895.5,5116.1
XS Rating Curve= 0 ,0
Exp/Cntr=0.3,0.1

Type RM Length L Ch R = 1 ,214513  ,611,611,611
BEGIN DESCRIPTION:
LAGARTO CREEK 171.0
END DESCRIPTION:
XS GIS Cut Line= 5
      2207407.51      13203657.6      2206842.95      13203494.5
      2206178.04     13203055.42      2205400.23     13202352.88
      2204760.43     13201173.63
#Sta/Elev= 30
  3304.4  366.51  3824.5  346.92  4045.1  333.69  4096.3  327.15  4147.4  327.16
  4183.6   322.6  4204.6  325.83  4236.1  325.43  4261.3  327.25  4493.6  334.31
    4685  331.38  4811.2  334.37  4914.8  336.47    4929  327.37  4943.2   323.3
  4957.4  323.29  4968.6  318.54  4971.3  318.04  4974.6  318.54  4999.2  325.44
  5049.3  326.49  5247.3  323.73  5318.3  328.58  5593.5  328.24  5875.9  333.23
  5916.8  333.08  6182.2  328.02    6504  327.97  6848.1  337.65  7078.6  338.92
#Mann= 11 ,-1 , 0
  3304.4      .1       0  4236.1     .12       0  4261.3      .1       0
    4685     .05       0  4811.2      .1       0  4968.6     .07       0
  4974.6      .1       0  5593.5     .05       0  5875.9     .08       0
  5916.8     .05       0  6182.2      .1       0
Bank Sta=4929,5049.3
XS Rating Curve= 0 ,0
Exp/Cntr=0.3,0.1

Type RM Length L Ch R = 1 ,213902  ,721,721,721
BEGIN DESCRIPTION:
LAGARTO CREEK 170.0
END DESCRIPTION:
XS GIS Cut Line= 3
      2207182.48     13203144.98      2205854.39     13202129.38
       2205672.4     13201583.42
#Sta/Elev= 30
  3970.7  356.96  4222.5  346.09  4243.3  346.55    4266  343.86  4272.3  344.92
  4589.8  326.69    4665   324.9  4692.8  322.31  4714.9  320.49  4729.4  323.55
    4808   328.4  4893.6  332.07  4899.8  327.72  4908.1  327.58  4914.4  325.38
  4920.9  323.38  4951.5  321.78  4971.2  321.79  4996.6  317.08  4999.3  316.58
  5002.6  317.08  5043.2  325.27  5142.9  325.27  5313.3  329.76  5416.3  329.79
  5527.3  329.41  5680.8  325.74  5813.9  328.85  6060.3  329.68  6218.1  333.79
#Mann= 8 ,-1 , 0
  3970.7     .05       0  4589.8      .1       0  4692.8     .12       0
    4808     .05       0  4951.5      .1       0  4996.6     .07       0
  5002.6      .1       0  5416.3     .05       0
Bank Sta=4914.4,5043.2
XS Rating Curve= 0 ,0
Exp/Cntr=0.3,0.1

Type RM Length L Ch R = 1 ,213181  ,690,690,690
BEGIN DESCRIPTION:
LAGARTO CREEK 169.0
END DESCRIPTION:
XS GIS Cut Line= 3
      2207537.69     13202396.84      2206949.57     13202195.99
      2205838.99     13201235.47
#Sta/Elev= 30
  4381.2  351.56  4560.8  344.03  4772.7  333.08  4870.3  329.94  4930.7  326.61
  4962.4  326.42  4981.4  322.41  4986.7  320.23  4991.1  314.64  4993.8  314.14
  4997.1  314.64    5018  316.22  5024.6  321.32  5059.7  322.47    5074  321.76
  5102.5  322.82  5116.8  324.74  5180.4  323.17  5272.5  328.29  5378.9   330.7
  5450.2  330.13  5563.2  326.82  5605.9  327.85  5698.1   324.4  5775.9  324.15
  5917.5  329.25  6023.2  330.24  6144.5  332.19  6300.8  336.75    6471  337.44
#Mann= 5 ,-1 , 0
  4381.2     .05       0  4870.3      .1       0  4991.1     .07       0
  4997.1      .1       0  6023.2     .05       0
Bank Sta=4962.4,5116.8
XS Rating Curve= 0 ,0
Exp/Cntr=0.3,0.1

Type RM Length L Ch R = 1 ,212491  ,896,896,896
BEGIN DESCRIPTION:
LAGARTO CREEK 168.0
END DESCRIPTION:
XS GIS Cut Line= 3
      2207637.71     13202146.85      2207237.72     13201646.86
      2206152.37     13200968.51
#Sta/Elev= 30
  4359.7  350.33  4707.9  335.55  4831.6  333.07  4943.2  333.24  4949.6  326.73
  4957.6   325.6    4964  322.53    4972  321.85  4978.4   316.2  4983.4  316.04
  4986.1  315.54  4989.4  316.04  4998.3  316.92  5002.9  316.92  5013.6  320.74
  5035.4  321.99  5102.3  318.88  5129.7  318.32  5159.8  323.47  5188.7  320.56
  5238.8   319.6  5254.1  322.01  5318.4  323.21  5363.8  326.48  5427.5  324.46
  5637.4  323.15  5704.6  325.44  5841.4  326.33    6161  335.52  6279.9  337.16
#Mann= 6 ,-1 , 0
  4359.7     .05       0  4831.6      .1       0  4983.4     .07       0
  4989.4      .1       0  4998.3     .12       0  5102.3      .1       0
Bank Sta=4957.6,5159.8
XS Rating Curve= 0 ,0
Exp/Cntr=0.3,0.1