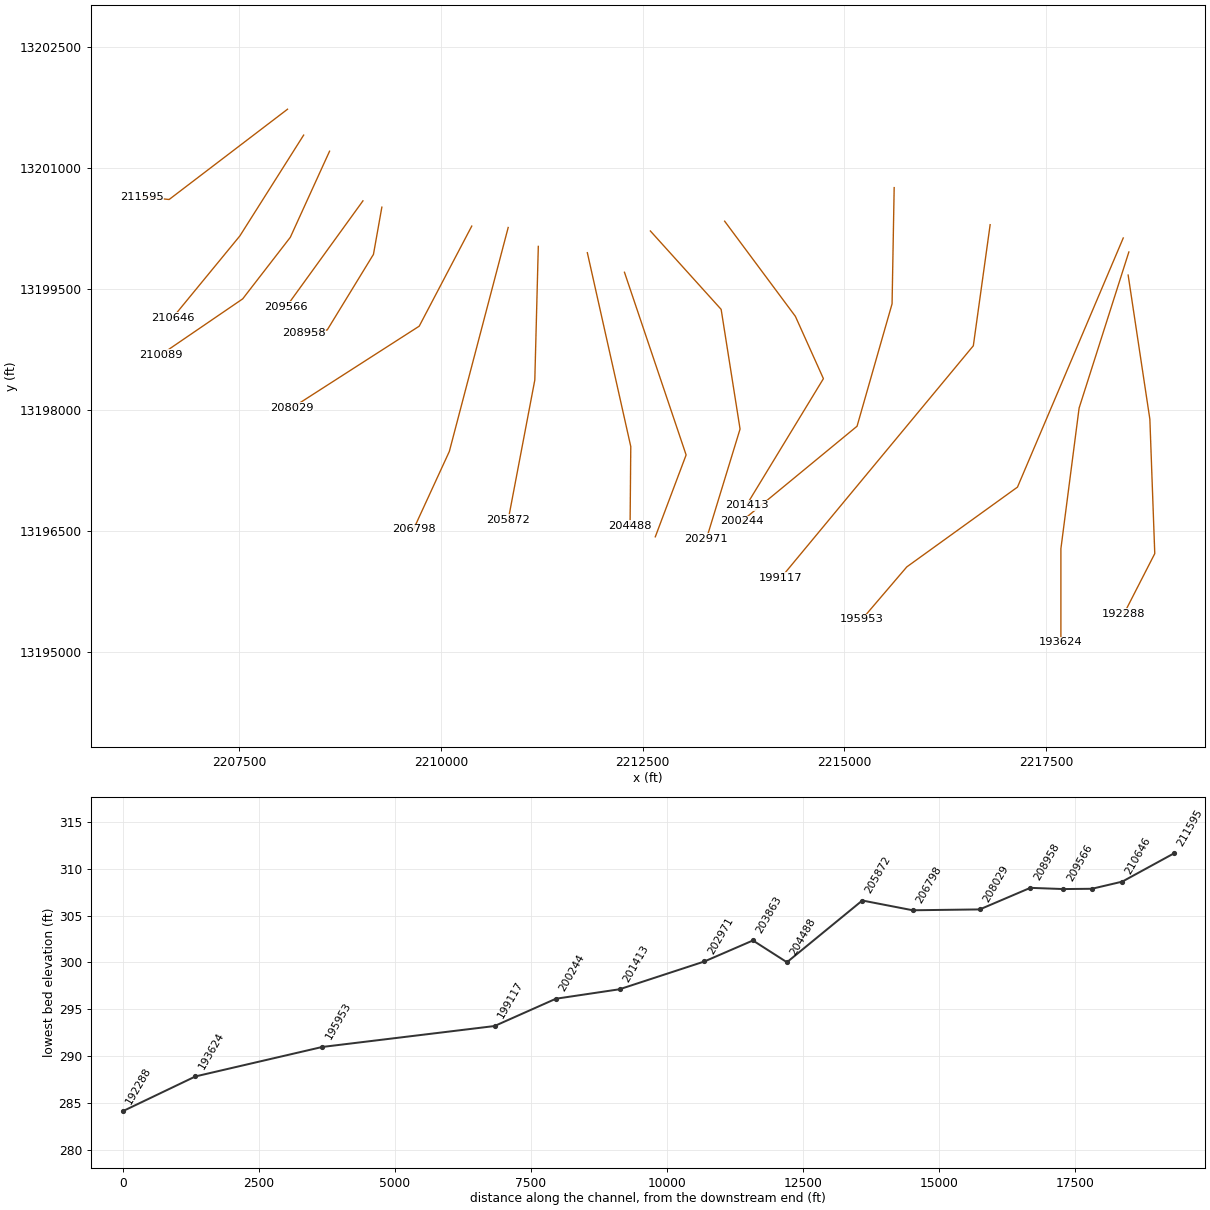
HEC-RAS study LAGARTO CREEK.prj: LAGARTO CREEK Base Level Engineering

--- LAGARTO CREEK.g01 (geometry) --- (continued)

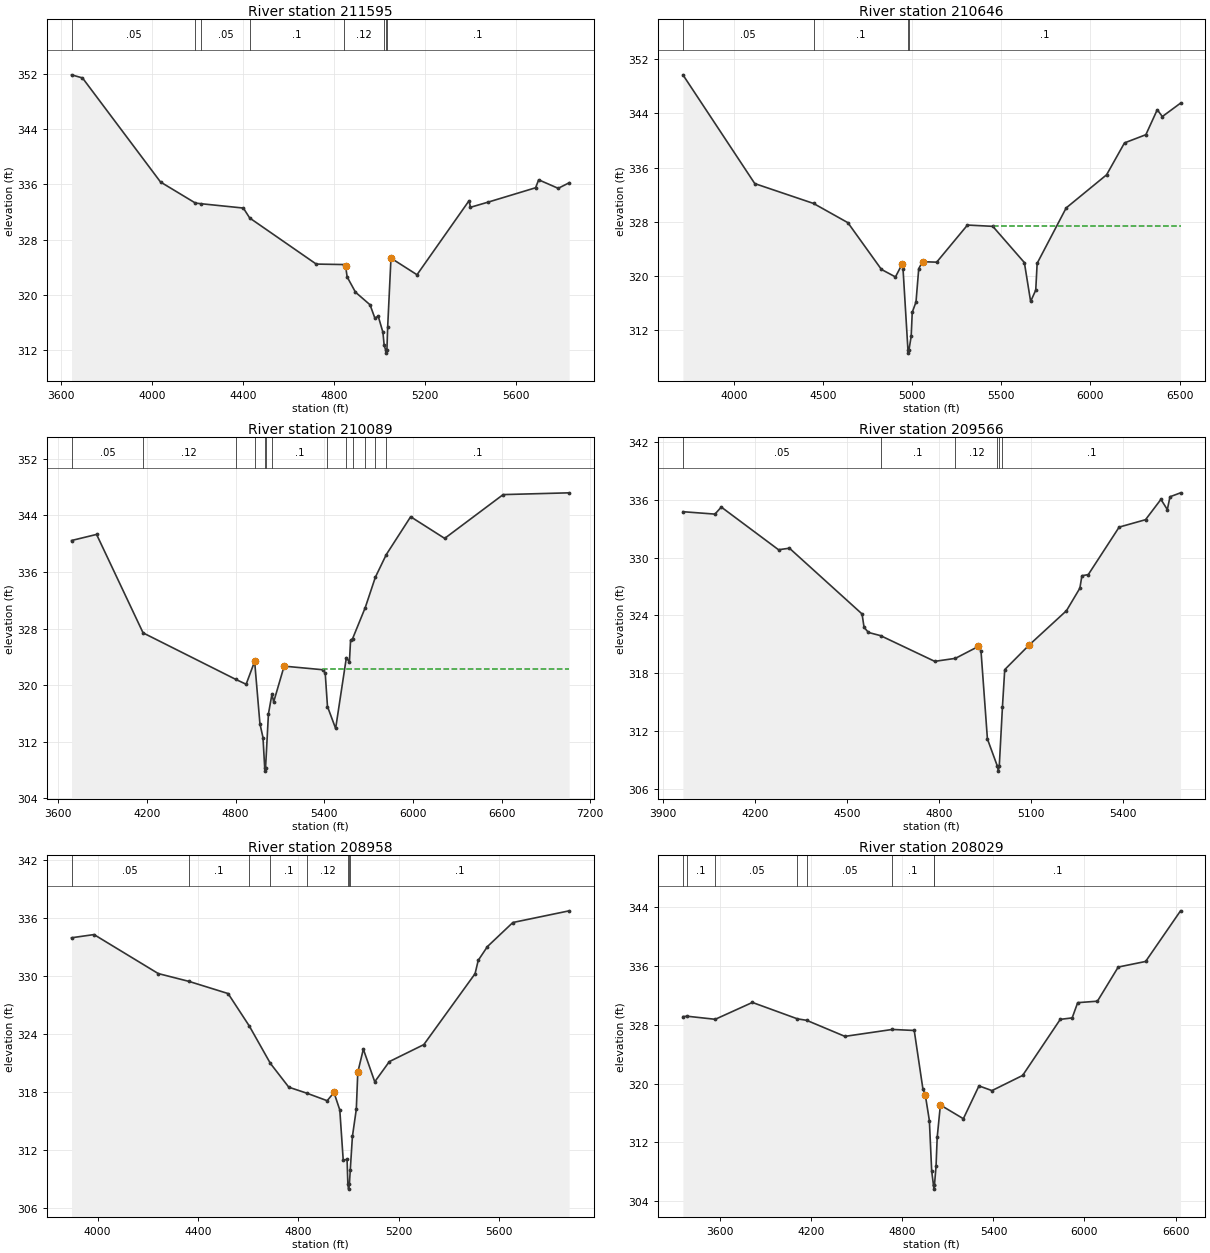
Type RM Length L Ch R = 1 ,211595  ,949,949,949
BEGIN DESCRIPTION:
LAGARTO CREEK 167.0
END DESCRIPTION:
XS GIS Cut Line= 3
      2208099.91     13201731.79      2206632.92     13200612.02
      2206294.42     13200646.73
#Sta/Elev= 30
  3646.5  351.81  3694.6  351.36  4037.4  336.33  4190.7  333.29  4217.2  333.19
  4401.2  332.57  4429.2  331.13  4721.3  324.48  4844.8  324.41  4850.1  324.22
    4857  322.63  4893.7  320.42  4957.6   318.6  4978.9  316.67  4993.5  316.96
  5014.3  314.62  5019.7  312.73  5025.8  312.12  5028.6  311.62  5031.8  312.12
  5035.1  315.41  5049.6  325.34  5163.9  322.94  5392.5  333.63  5398.8  332.68
  5477.7  333.44  5684.8   335.5  5698.3  336.65  5784.1  335.42  5832.3  336.22
#Mann= 8 ,-1 , 0
  3646.5     .05       0  4190.7      .1       0  4217.2     .05       0
  4429.2      .1       0  4844.8     .12       0  5019.7      .1       0
  5025.8     .07       0  5031.8      .1       0
Bank Sta=4850.1,5049.6
XS Rating Curve= 0 ,0
Exp/Cntr=0.3,0.1

Type RM Length L Ch R = 1 ,210646  ,557,557,557
BEGIN DESCRIPTION:
LAGARTO CREEK 166.0
END DESCRIPTION:
XS GIS Cut Line= 3
      2208299.59     13201410.62      2207509.66     13200160.63
      2206676.34     13199145.02
#Sta/Elev= 30
  3712.9   349.7  4116.2  333.64  4445.8  330.71  4638.6  327.87  4826.8  320.97
  4905.6  319.86  4942.1  321.71    4948  321.09  4975.6  309.11  4978.3  308.61
  4981.6  309.11  4993.8  311.09  4999.8  314.64  5020.9  316.16  5036.2  321.08
  5057.4  322.11  5136.9  322.04  5309.6  327.52  5451.7  327.33    5629  321.98
  5664.1  316.24  5692.8  317.91  5700.7  321.87  5863.6  330.05  6090.4  334.94
  6190.9  339.65  6310.7  340.86  6374.6  344.54  6403.3  343.54  6505.3  345.52
#Mann= 4 ,-1 , 0
  3712.9     .05       0  4445.8      .1       0  4975.6     .07       0
  4981.6      .1       0
#XS Ineff= 2 , 0
                         5451.76          327.37
Permanent Ineff=
       F       F
Bank Sta=4942.1,5057.4
XS Rating Curve= 0 ,0
Exp/Cntr=0.3,0.1

Type RM Length L Ch R = 1 ,210089  ,523,523,523
BEGIN DESCRIPTION:
LAGARTO CREEK 165.0
END DESCRIPTION:
XS GIS Cut Line= 4
      2208620.77     13201210.98      2208134.66     13200143.27
      2207544.38     13199379.38      2206528.74     13198684.92
#Sta/Elev= 30
    3689  340.45  3858.5  341.31  4173.4  327.39  4799.6  320.83    4871  320.13
  4928.5  323.36  4964.3  314.56  4985.1  312.59  4996.6  308.35  4999.3  307.85
  5002.6  308.35  5021.9  315.93  5045.8  318.73  5057.5  317.64  5128.2  322.69
 5390.49  322.18  5406.2  321.72  5421.7  316.98  5476.9  313.88  5549.6   323.9
  5570.1  323.26    5578  326.34  5591.2  326.55  5677.4  330.97  5745.8  335.26
  5819.5  338.45  5984.8  343.81  6215.1  340.75  6610.9  346.94  7057.9  347.19
#Mann= 13 ,-1 , 0
    3689     .05       0  4173.4     .12       0  4799.6      .1       0
  4928.5     .12       0  4996.6     .07       0  5002.6     .12       0
  5045.8      .1       0  5421.7     .12       0  5549.6      .1       0
  5591.2     .05       0  5677.4      .1       0  5745.8     .05       0
  5819.5      .1       0
#XS Ineff= 2 , 0
                         5389.94          322.28
Permanent Ineff=
       F       F
Bank Sta=4928.5,5128.2
XS Rating Curve= 0 ,0
Exp/Cntr=0.3,0.1

Type RM Length L Ch R = 1 ,209566  ,608,608,608
BEGIN DESCRIPTION:
LAGARTO CREEK 164.0
END DESCRIPTION:
XS GIS Cut Line= 2
      2209034.57     13200595.26      2208084.67     13199281.01
#Sta/Elev= 30
  3964.9  334.76  4069.2  334.51    4090  335.24  4276.5  330.81    4312  330.97
  4548.7  324.14  4555.2  322.75  4569.6  322.22  4608.9  321.89  4785.5  319.22
  4852.8  319.53  4927.8  320.77  4936.3  320.29  4957.2  311.16  4989.8  308.32
  4992.5  307.82  4995.8  308.32  5006.2  314.51  5013.6  318.36  5093.3  320.92
  5214.8  324.48  5258.5  326.82  5265.1  328.11  5285.9  328.23  5386.5  333.16
  5472.4  333.93  5522.6  336.04  5543.5  334.98  5552.1  336.31  5586.5  336.72
#Mann= 6 ,-1 , 0
  3964.9     .05       0  4608.9      .1       0  4852.8     .12       0
  4989.8     .07       0  4995.8     .12       0  5006.2      .1       0
Bank Sta=4927.8,5093.3
XS Rating Curve= 0 ,0
Exp/Cntr=0.3,0.1

Type RM Length L Ch R = 1 ,208958  ,929,929,929
BEGIN DESCRIPTION:
LAGARTO CREEK 163.0
END DESCRIPTION:
XS GIS Cut Line= 4
      2209268.93     13200517.09      2209164.77     13199931.18
      2208591.85     13198993.68      2208305.39     13198954.62
#Sta/Elev= 30
  3895.9  333.99  3985.5  334.32  4241.5  330.28  4363.8  329.47  4519.7  328.21
  4604.4  324.84  4688.1  320.98  4761.6  318.51  4834.4  317.88  4914.5  317.11
  4941.6  317.96  4964.8  316.15  4978.4  310.97  4993.8  311.02    4997  308.45
  4999.8  307.95    5003  308.45  5006.6  309.95  5015.1  313.41  5030.6  316.22
  5036.5  320.05  5058.6  322.45  5104.1  319.07  5162.2  321.16  5299.6  322.92
  5503.9  330.27  5516.4  331.65  5553.2  333.08  5654.4  335.57  5878.8  336.78
#Mann= 8 ,-1 , 0
  3895.9     .05       0  4363.8      .1       0  4604.4     .05       0
  4688.1      .1       0  4834.4     .12       0    4997     .07       0
    5003     .12       0  5006.6      .1       0
Bank Sta=4941.6,5036.5
XS Rating Curve= 0 ,0
Exp/Cntr=0.3,0.1

Type RM Length L Ch R = 1 ,208029  ,1231,1231,1231
BEGIN DESCRIPTION:
LAGARTO CREEK 162.0
END DESCRIPTION:
XS GIS Cut Line= 3
      2210382.93     13200282.18      2209731.88     13199040.84
      2208152.41     13198025.46
#Sta/Elev= 30
  3353.6  329.09  3380.2  329.15  3566.5  328.73  3811.6  331.02  4108.3  328.79
  4169.1  328.59  4421.1  326.41    4734  327.35    4878  327.21  4935.5  319.22
  4950.5   318.5  4977.8  314.97    4993  308.12  5005.1  306.15  5007.9  305.65
  5011.1  306.15  5021.8  308.76  5029.3  312.67  5050.4  317.08  5201.7  315.22
  5304.7  319.68  5390.3  319.04  5592.4   321.1  5840.3  328.72  5918.9  328.92
  5955.2  330.99  6085.3  331.19  6222.5  335.83    6403  336.59    6633  343.47
#Mann= 8 ,-1 , 0
  3353.6     .05       0  3380.2      .1       0  3566.5     .05       0
  4108.3      .1       0  4169.1     .05       0    4734      .1       0
  5005.1     .07       0  5011.1      .1       0
Bank Sta=4950.5,5050.4
XS Rating Curve= 0 ,0
Exp/Cntr=0.3,0.1

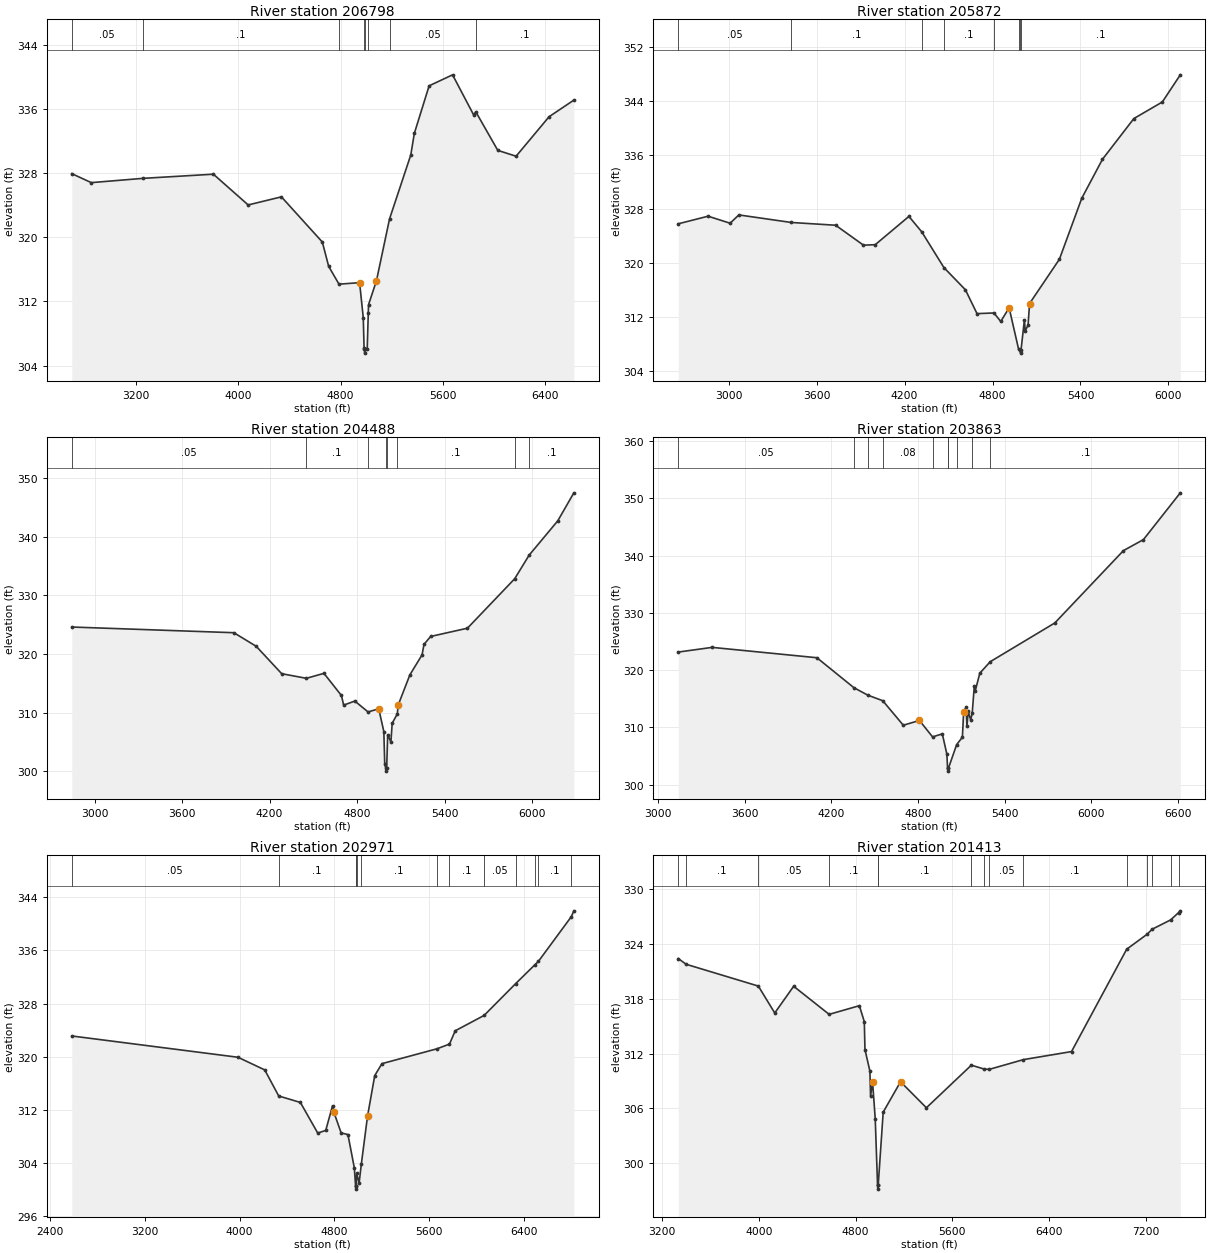
Type RM Length L Ch R = 1 ,206798  ,926,926,926
BEGIN DESCRIPTION:
LAGARTO CREEK 161.0
END DESCRIPTION:
XS GIS Cut Line= 3
      2210834.32     13200264.83      2210105.14     13197487.02
      2209662.56     13196523.75
#Sta/Elev= 30
  2695.1  327.92  2848.1   326.8  3250.1  327.33  3804.3  327.85  4076.6  324.02
  4336.9  325.03  4657.4   319.4    4707  316.37  4787.9  314.15  4949.2  314.34
  4977.9  309.98  4984.4  306.16  4986.6  306.06  4989.3  305.56  4992.6  306.06
  5008.9  306.08  5017.2  310.52  5019.2  311.59  5081.3  314.58  5183.7  322.28
  5350.1  330.25  5377.8  332.93  5493.7  338.86  5677.3  340.23  5842.3  335.24
    5859  335.63  6031.4  330.82  6174.8  330.09  6433.1  335.01  6627.1  337.08
#Mann= 8 ,-1 , 0
  2695.1     .05       0  3250.1      .1       0  4787.9     .12       0
  4986.6     .07       0  4992.6     .12       0  5017.2      .1       0
  5183.7     .05       0    5859      .1       0
Bank Sta=4949.2,5081.3
XS Rating Curve= 0 ,0
Exp/Cntr=0.3,0.1

Type RM Length L Ch R = 1 ,205872  ,1384,1384,1384
BEGIN DESCRIPTION:
LAGARTO CREEK 160.0
END DESCRIPTION:
XS GIS Cut Line= 3
      2211207.57     13200030.43      2211164.17     13198372.43
      2210834.32     13196636.36
#Sta/Elev= 30
  2655.4  325.79    2859  326.92  3009.1  325.88  3069.1  327.11  3426.5  325.99
  3729.3  325.58  3919.4  322.62  3999.4  322.69  4229.5  326.89  4317.1  324.59
    4468   319.3  4614.8     316    4694  312.46  4809.6  312.56  4855.8   311.3
  4913.1  313.32  4977.9  307.17  4988.5   307.1  4991.2   306.6  4994.5   307.1
  5017.5  311.55  5022.6  309.91  5042.3  310.73  5052.5  313.96  5256.1  320.53
  5408.8  329.59  5550.1  335.37  5764.1  341.41  5958.4  343.87  6081.1   347.9
#Mann= 8 ,-1 , 0
  2655.4     .05       0  3426.5      .1       0  4317.1     .05       0
    4468      .1       0  4809.6     .12       0  4977.9      .1       0
  4988.5     .07       0  4994.5      .1       0
Bank Sta=4913.1,5052.5
XS Rating Curve= 0 ,0
Exp/Cntr=0.3,0.1

Type RM Length L Ch R = 1 ,204488  ,625,625,625
BEGIN DESCRIPTION:
LAGARTO CREEK 158.0
END DESCRIPTION:
XS GIS Cut Line= 3
      2211815.22     13199952.26      2212353.41     13197547.78
      2212344.73     13196566.89
#Sta/Elev= 30
  2842.5   324.6  3954.8  323.63  4108.2  321.31  4282.7  316.64  4452.4  315.85
  4572.8   316.7  4692.6  312.92  4708.1  311.28  4784.8  311.97  4875.2  310.12
  4948.8  310.64  4983.7  306.77  4989.8  301.25    4997  300.52  4999.7  300.02
    5003  300.52  5010.2  306.23  5032.2  304.99    5041  308.19  5076.2  309.78
    5082  311.28  5162.4  316.44  5245.9  319.85  5259.4  321.65  5304.9  322.99
  5557.4   324.4  5881.7  332.84  5980.6  336.86  6177.4  342.72  6287.4  347.49
#Mann= 8 ,-1 , 0
  2842.5     .05       0  4452.4      .1       0  4875.2     .12       0
    4997     .07       0    5003     .12       0  5076.2      .1       0
  5881.7     .08       0  5980.6      .1       0
Bank Sta=4948.8,5082
XS Rating Curve= 0 ,0
Exp/Cntr=0.3,0.1

Type RM Length L Ch R = 1 ,203863  ,892,892,892
BEGIN DESCRIPTION:
LAGARTO CREEK 157.0
END DESCRIPTION:
XS GIS Cut Line= 3
      2212275.27     13199709.27      2213039.17     13197443.61
      2212657.24     13196428.03
#Sta/Elev= 30
  3140.1  323.14  3374.8  323.96  4100.1  322.15  4356.1  316.92  4452.8  315.61
    4556  314.64  4698.2  310.36    4810  311.19  4900.9  308.32  4968.3  308.85
    5000  305.29  5004.7  302.84  5007.4  302.34  5010.7  302.84  5067.5  306.96
  5107.4  308.27  5116.1  312.71  5133.6  313.48  5138.9   310.2  5147.7  312.77
  5165.1  311.28  5175.5  312.52    5190  317.23  5196.6  316.38    5228  319.45
  5300.3  321.46  5747.4  328.23  6222.1  340.86  6360.9  342.79  6616.1  350.96
#Mann= 10 ,-1 , 0
  3140.1     .05       0  4356.1      .1       0  4452.8     .05       0
    4556     .08       0  4900.9     .12       0  5004.7     .07       0
  5010.7     .12       0  5067.5      .1       0  5175.5     .08       0
  5300.3      .1       0
Bank Sta=4810,5116.1
XS Rating Curve= 0 ,0
Exp/Cntr=0.3,0.1

Type RM Length L Ch R = 1 ,202971  ,1558,1558,1558
BEGIN DESCRIPTION:
LAGARTO CREEK 156.0
END DESCRIPTION:
XS GIS Cut Line= 4
      2212596.46      13200221.4       2213473.2     13199249.17
      2213707.57     13197764.79      2213290.92     13196401.99
#Sta/Elev= 30
  2583.2  323.12  3985.8  319.92  4211.7  318.02  4329.6   314.1  4512.3  313.13
  4658.9  308.53  4726.4  308.92  4783.7  312.63  4795.7  311.63  4856.5  308.55
  4913.7   308.3  4967.8  303.29  4978.2   300.6  4980.9   300.1  4984.2   300.6
  4987.7  302.46  5008.3  301.05    5027  303.89  5079.2  311.07  5139.9  317.16
  5200.7  318.96  5666.4   321.2  5770.7   321.9  5819.3   323.9    6063  326.21
  6328.7  330.98  6492.4  333.84  6520.7  334.32  6799.6  341.07  6820.2  341.93
#Mann= 13 ,-1 , 0
  2583.2     .05       0  4329.6      .1       0  4978.2     .07       0
  4984.2      .1       0  4987.7     .12       0    5027      .1       0
  5666.4     .05       0  5770.7      .1       0    6063     .05       0
  6328.7      .1       0  6492.4     .05       0  6520.7      .1       0
  6799.6     .05       0
Bank Sta=4795.7,5079.2
XS Rating Curve= 0 ,0
Exp/Cntr=0.3,0.1

Type RM Length L Ch R = 1 ,201413  ,1169,1169,1169
BEGIN DESCRIPTION:
Mapping XS 2f375b45
END DESCRIPTION:
XS GIS Cut Line= 4
      2213516.59     13200342.93      2214393.34     13199162.36
      2214740.56     13198389.79      2213786.69     13196820.24
#Sta/Elev= 30
  3332.9  322.42  3398.4  321.79  3995.6   319.4  4131.5  316.45  4287.9  319.38
  4581.5   316.3  4831.6  317.25  4872.4   315.5  4877.9  312.44  4918.7  310.08
  4924.2  307.37    4941  308.86  4962.9  304.85  4981.9  297.64  4984.6  297.14
  4987.9  297.64  5028.7  305.58  5172.3  308.91  5386.2  306.06  5758.2  310.73
  5862.1  310.31  5906.3  310.27  6189.4  311.34    6587  312.22  7043.4  323.44
  7212.1  325.08  7253.7  325.63  7407.6  326.66  7472.8  327.46  7487.1  327.65
#Mann= 15 ,-1 , 0
  3332.9     .05       0  3398.4      .1       0  3995.6     .05       0
  4581.5      .1       0  4981.9     .07       0  4987.9      .1       0
  5758.2     .05       0  5862.1      .1       0  5906.3     .05       0
  6189.4      .1       0  7043.4     .08       0  7212.1      .1       0
  7253.7     .05       0  7407.6      .1       0  7472.8     .05       0
Bank Sta=4941,5172.3
XS Rating Curve= 0 ,0
Exp/Cntr=0.3,0.1

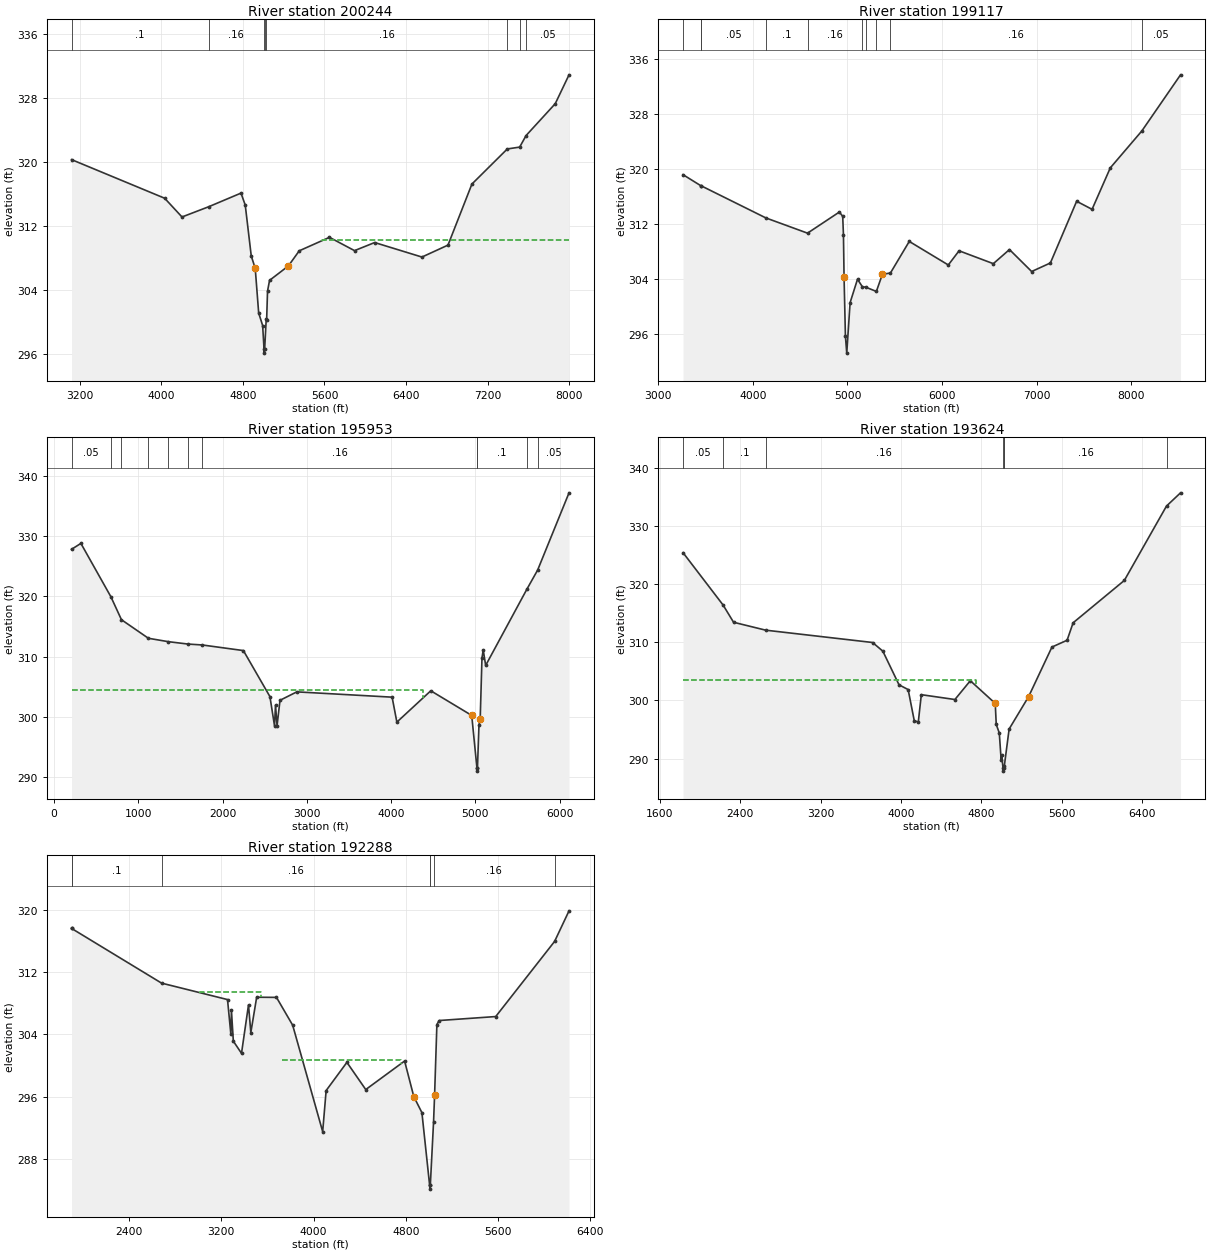
Type RM Length L Ch R = 1 ,200244  ,1127,1127,1127
BEGIN DESCRIPTION:
LAGARTO CREEK 155.0
END DESCRIPTION:
XS GIS Cut Line= 4
       2215617.3     13200759.54      2215591.25     13199318.61
      2215157.23     13197799.52      2213724.91     13196618.94
#Sta/Elev= 30
  3120.2  320.28    4033  315.46  4203.1  313.12  4463.1  314.39  4781.6   316.1
  4823.2   314.6    4882  308.26    4921  306.71  4954.8  301.14  4993.8  299.57
  5007.4  296.63  5010.2  296.13  5013.4  296.63  5028.7  300.34  5032.8  300.24
  5041.6  303.86  5061.4  305.21    5246  307.01  5352.6   308.9    5649  310.58
  5894.4  308.92    6092  309.93  6555.3  308.12  6810.8  309.61  7045.4  317.23
  7392.3  321.61  7513.6  321.84  7576.1  323.28  7862.4  327.26  7997.4  330.86
#Mann= 8 ,-1 , 0
  3120.2      .1       0  4463.1     .16       0  5007.4     .07       0
  5013.4     .12       0  5028.7     .16       0  7392.3     .08       0
  7513.6      .1       0  7576.1     .05       0
#XS Ineff= 2 , 0
       0 4738.64   315.6  5576.7       0  310.21
Permanent Ineff=
       F       T
Bank Sta=4921,5246
XS Rating Curve= 0 ,0
Exp/Cntr=0.3,0.1

Type RM Length L Ch R = 1 ,199117  ,3164,3164,3164
BEGIN DESCRIPTION:
LAGARTO CREEK 154.0
END DESCRIPTION:
XS GIS Cut Line= 3
      2216806.53     13200299.53       2216598.2     13198797.78
       2214211.9     13195916.87
#Sta/Elev= 30
  3262.7  319.13    3448  317.55  3456.3   317.5  4138.3  312.85  4577.9  310.64
  4914.6  313.71  4949.8  313.08  4957.6  310.39  4964.1  304.28  4978.4  295.68
  4992.5  293.22  5027.9  300.55  5106.1  303.95    5157  302.87    5196  302.78
  5305.5  302.18  5369.2  304.67    5454  304.85  5653.1  309.44  6065.6  306.02
  6179.3  308.08  6541.3  306.21    6712  308.26  6946.4  305.07  7144.3  306.31
  7421.8  315.27  7584.8   314.1  7777.4  320.12  8110.8  325.48  8519.7  333.63
#Mann= 10 ,-1 , 0
  3262.7     .05       0    3448      .1       0  3456.3     .05       0
  4138.3      .1       0  4577.9     .16       0    5157     .12       0
    5196     .16       0  5305.5     .12       0    5454     .16       0
  8110.8     .05       0
#XS Ineff= 2 , 0
       0 4892.05  313.24 5684.43       0  309.14
Permanent Ineff=
       F       T
Bank Sta=4964.1,5369.2
XS Rating Curve= 0 ,0
Exp/Cntr=0.3,0.1

Type RM Length L Ch R = 1 ,195953  ,2329,2329,2329
BEGIN DESCRIPTION:
LAGARTO CREEK 153.0
END DESCRIPTION:
XS GIS Cut Line= 5
      2218455.83     13200134.57      2217683.27     13198311.67
      2217145.07     13197044.31      2215773.55     13196054.72
      2215217.98     13195403.67
#Sta/Elev= 30
   207.2  327.79   318.2  328.77   674.1  319.92   799.5  316.11  1119.3  313.03
  1354.2  312.47  1589.1  312.07    1758  311.92  2246.6  310.99  2561.7  303.35
    2616  298.51  2627.8  301.94  2646.1  298.53  2681.2  302.74  2880.7  304.14
  4011.6  303.26  4068.1  299.12  4470.5  304.32  4956.4  300.23  5018.4  291.49
  5021.2  290.99  5024.4  291.49  5042.3  298.62    5057  299.64  5077.9  309.74
  5092.6  311.09    5122  308.53  5610.5  321.16  5738.4  324.34  6111.1  337.16
#Mann= 11 ,-1 , 0
   207.2     .05       0   674.1     .08       0   799.5      .1       0
  1119.3     .05       0  1354.2      .1       0  1589.1      .1       0
    1758     .16       0  5018.4     .07       0  5024.4      .1       0
  5610.5     .08       0  5738.4     .05       0
#XS Ineff= 2 , 0
       0 4383.53  304.37               0
Permanent Ineff=
       T       F
Bank Sta=4956.4,5057
XS Rating Curve= 0 ,0
Exp/Cntr=0.3,0.1

Type RM Length L Ch R = 1 ,193624  ,1336,1336,1336
BEGIN DESCRIPTION:
LAGARTO CREEK 152.0
END DESCRIPTION:
XS GIS Cut Line= 4
      2218525.29     13199961.01      2217908.96     13198025.21
      2217683.27     13196280.42      2217683.27     13195117.19
#Sta/Elev= 30
  1830.7   325.4  2229.5   316.4  2333.6  313.44  2653.6  312.08  3718.4  309.96
  3820.3  308.47  3981.6  302.68  4072.3  301.87  4132.8  296.55  4173.2  296.27
  4203.4  300.99  4537.9  300.16  4691.4  303.39  4939.5  299.49  4949.6  295.87
  4979.8  294.41  4998.6  289.74  5003.6  290.64  5017.2  288.35  5019.9  287.85
  5023.2  288.35  5030.3  288.78  5077.9  295.09  5272.2  300.67  5504.2  309.18
  5655.1  310.35  5715.1  313.35  6225.1  320.63  6645.1  333.42  6784.8  335.69
#Mann= 7 ,-1 , 0
  1830.7     .05       0  2229.5      .1       0  2653.6     .16       0
  5017.2     .07       0  5023.2      .1       0  5030.3     .16       0
  6645.1     .05       0
#XS Ineff= 2 , 0
       0 4748.16  303.43               0
Permanent Ineff=
       T       F
Bank Sta=4939.5,5272.2
XS Rating Curve= 0 ,0
Exp/Cntr=0.3,0.1

Type RM Length L Ch R = 1 ,192288  ,757,757,757
BEGIN DESCRIPTION:
LAGARTO CREEK 150.0
END DESCRIPTION:
XS GIS Cut Line= 4
      2218516.59     13199674.56       2218785.7     13197886.32
      2218846.46     13196219.66      2218464.52     13195473.14
#Sta/Elev= 30
  1901.3   317.6  1901.6   317.6  2682.2  310.58  3254.1  308.47  3282.9  304.06
    3288  307.08  3304.6  303.13  3375.4  301.57  3436.1  307.79  3456.3  304.24
  3506.9  308.77  3678.8  308.75  3819.2  305.18  4079.4  291.52  4109.4  296.79
  4289.5  300.41    4453  296.92  4789.9  300.58  4869.9  296.01    4940  293.96
    5007  284.64  5009.8  284.14    5013  284.64    5041  292.74    5050  296.19
    5070  305.27  5090.1  305.78  5580.2  306.29  6091.1  315.94    6216  319.86
#Mann= 7 ,-1 , 0
  1901.3     .05       0  1901.6      .1       0  2682.2     .16       0
    5007     .07       0    5013     .12       0    5041     .16       0
  6091.1     .05       0
#XS Ineff= 2 ,-1
 3016.07 3546.28  309.43 3723.86 4760.23  300.68
Permanent Ineff=
       T       T
Bank Sta=4869.9,5050
XS Rating Curve= 0 ,0
Exp/Cntr=0.3,0.1