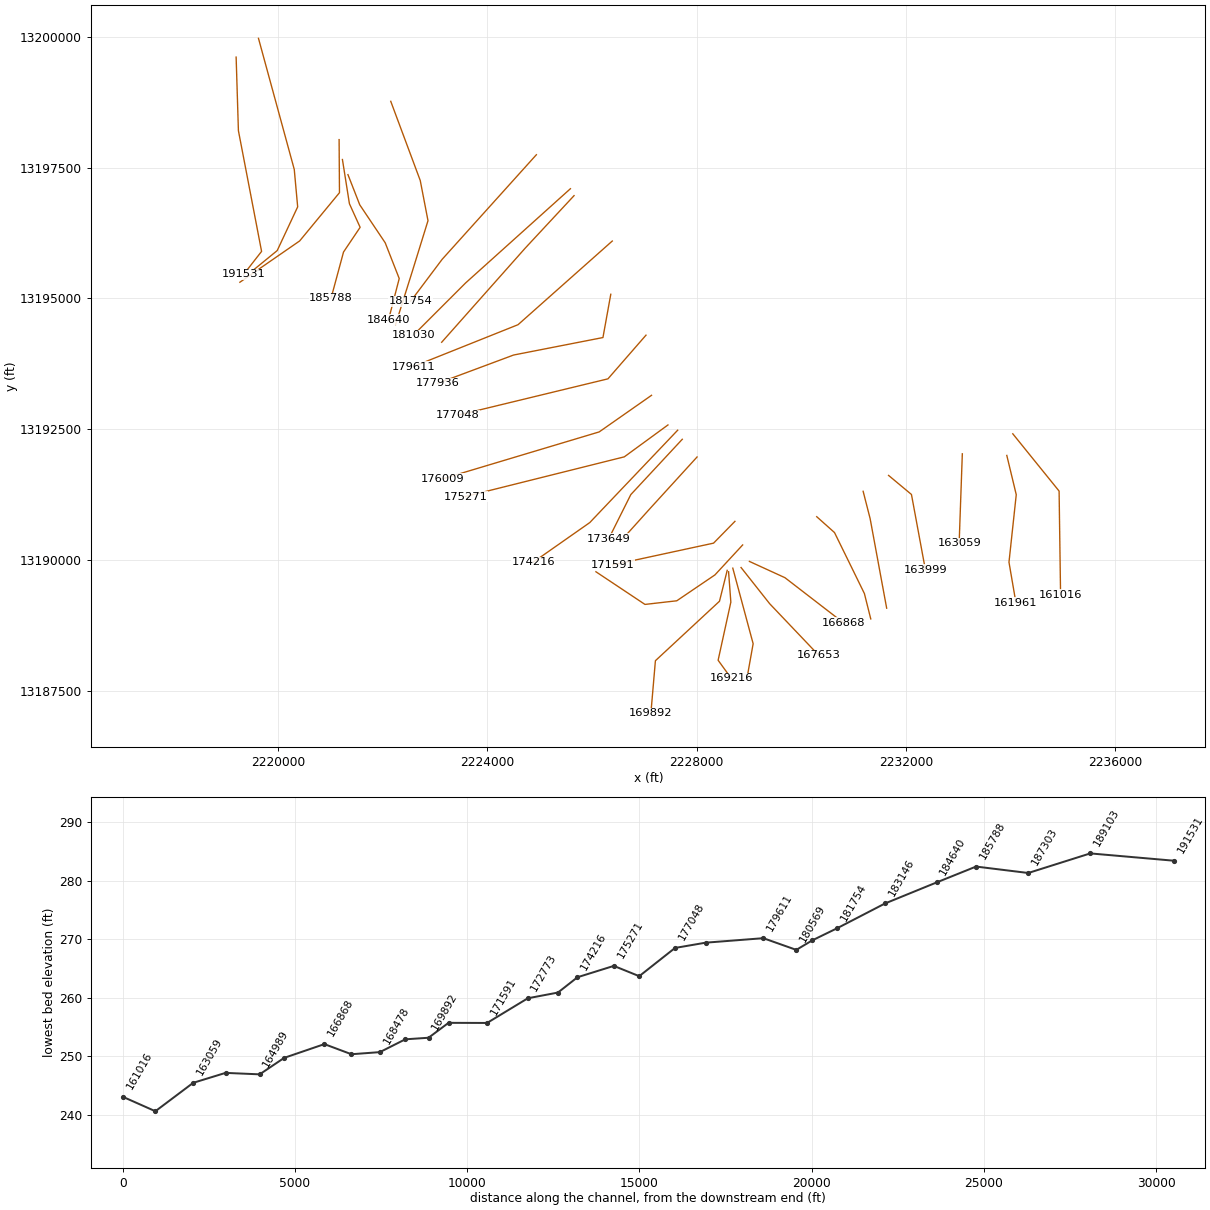
HEC-RAS study LAGARTO CREEK.prj: LAGARTO CREEK Base Level Engineering

--- LAGARTO CREEK.g01 (geometry) --- (continued)

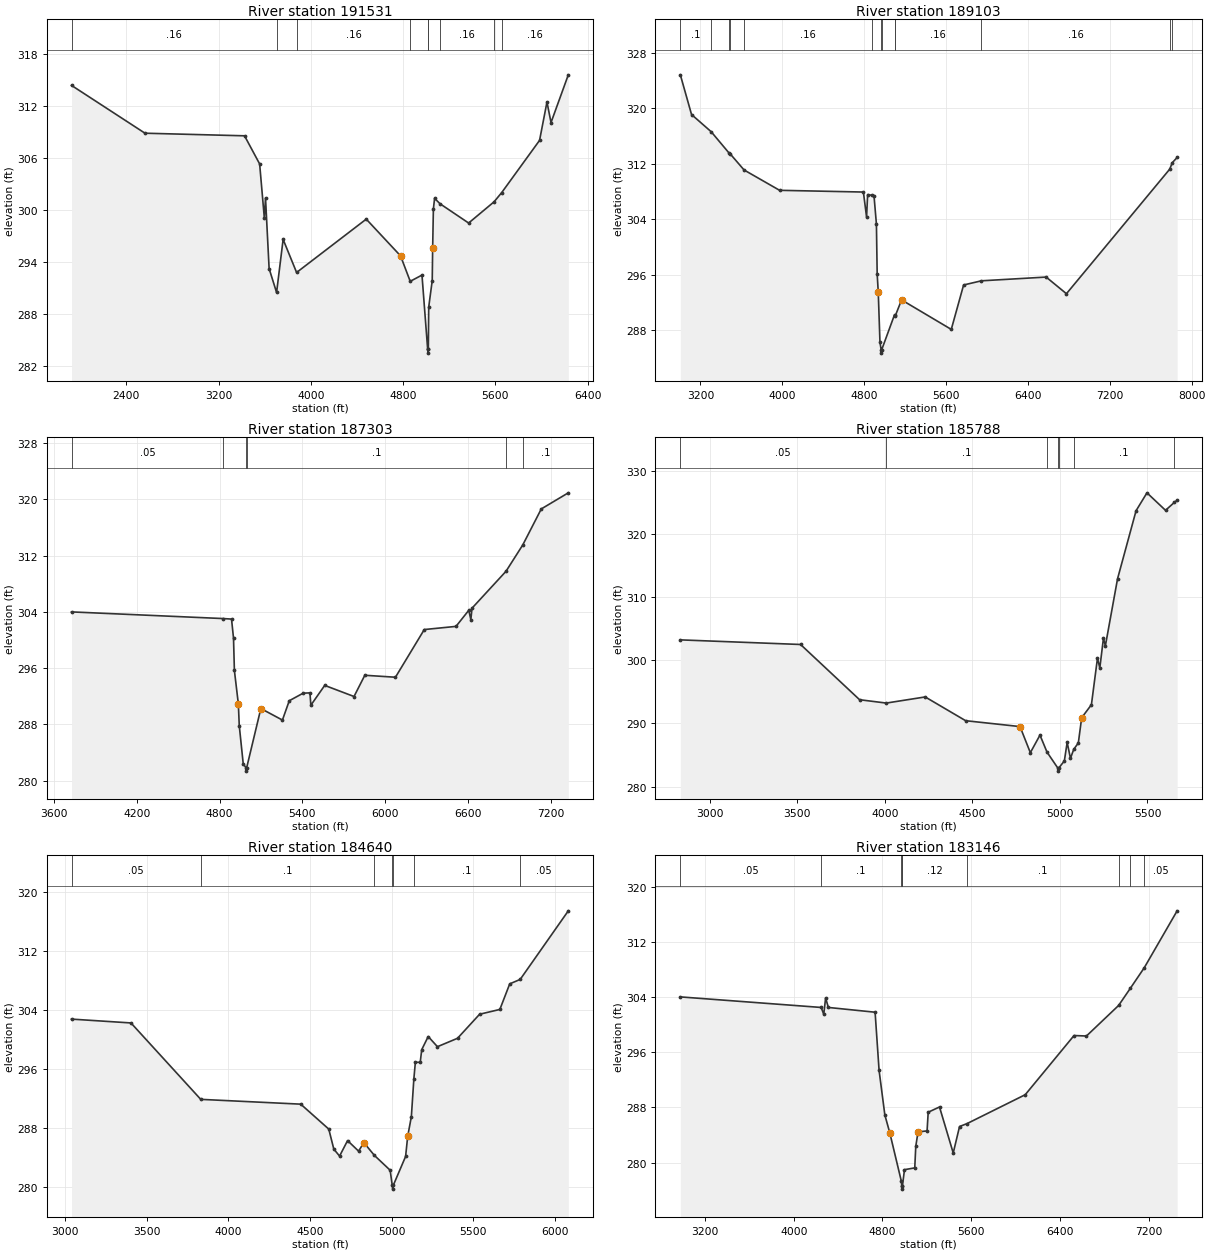
Type RM Length L Ch R = 1 ,191531  ,2428,2428,2428
BEGIN DESCRIPTION:
LAGARTO CREEK 149.0
END DESCRIPTION:
XS GIS Cut Line= 4
      2219202.37     13199613.73      2219245.77      13198207.5
      2219688.48     13195898.47      2219349.95     13195464.47
#Sta/Elev= 30
  1924.8  314.36    2562  308.84  3425.4  308.54  3556.4  305.29  3597.1  299.04
  3607.3  301.36  3638.5  293.21  3703.3  290.45    3760  296.58  3876.8  292.76
  4480.9  298.92  4778.2  294.68  4862.2  291.74  4964.2  292.46  5013.2  283.95
    5016  283.45  5019.2  283.95  5022.6  288.76  5053.1  291.83 5056.82  295.59
  5063.1  300.09  5073.5  301.32  5121.1  300.69  5368.8  298.47  5589.4  300.92
  5655.9  301.99  5983.8  308.01  6048.1  312.44  6083.3  310.07  6233.2  315.58
#Mann= 9 ,-1 , 0
  1924.8     .16       0  3703.3     .12       0  3876.8     .16       0
  4862.2     .12       0  5013.2     .07       0  5019.2     .12       0
  5121.1     .16       0  5589.4     .05       0  5655.9     .16       0
#XS Ineff= 2 , 0
       0  4477.8  298.88 5094.32       0  300.93
Permanent Ineff=
       T       F
Bank Sta=4778.2,5056.82
XS Rating Curve= 0 ,0
Exp/Cntr=0.3,0.1

Type RM Length L Ch R = 1 ,189103  ,1800,1800,1800
BEGIN DESCRIPTION:
Mapping XS 345d1f48
END DESCRIPTION:
XS GIS Cut Line= 5
      2219629.17     13199972.52      2220312.75     13197466.04
      2220377.86     13196749.89      2219987.23     13195914.39
      2219511.28     13195524.97
#Sta/Elev= 30
    3004   324.8  3113.5  319.08  3305.5   316.6  3476.7  313.59  3492.3  313.39
  3626.8  311.09  3973.8  308.16  4792.7  307.91  4823.8   304.3  4834.2  307.54
    4876  307.44  4896.3  307.39    4920  303.29  4927.4  296.08  4937.8  293.53
  4954.6  286.27  4965.9   285.2  4968.7   284.7  4971.9   285.2  5097.4  290.25
  5102.9  290.02  5165.8  292.37  5651.4  288.12  5771.9  294.52  5946.2  295.12
  6578.4  295.66  6776.7  293.26    7786  311.21  7810.9  312.14  7858.4  312.89
#Mann= 13 ,-1 , 0
    3004      .1       0  3305.5     .16       0  3476.7      .1       0
  3492.3     .16       0  3626.8     .16       0    4876     .12       0
  4965.9     .07       0  4971.9     .12       0  5097.4      .1       0
  5102.9     .16       0  5946.2     .16       0    7786     .05       0
  7810.9      .1       0
Bank Sta=4937.8,5165.8
XS Rating Curve= 0 ,0
Exp/Cntr=0.3,0.1

Type RM Length L Ch R = 1 ,187303  ,1515,1515,1515
BEGIN DESCRIPTION:
LAGARTO CREEK 148.0
END DESCRIPTION:
XS GIS Cut Line= 4
      2221169.39     13198035.73      2221176.44     13197021.09
      2220415.48     13196098.08      2219274.03     13195308.92
#Sta/Elev= 30
  3727.5  303.99  4828.4  303.04  4886.6  302.97    4901  300.26  4907.4  295.66
  4936.1  290.89  4942.6  287.82  4971.3   282.4  4990.5  281.85  4993.2  281.35
  4996.5  281.85    5099  290.25  5255.3  288.61  5304.9  291.36  5405.2  292.43
  5454.7  292.48  5461.2  290.72  5561.6  293.54  5773.9  291.96  5852.1  294.98
    6074   294.7  6282.8  301.48  6512.6  301.93  6605.2  304.22  6620.1  302.89
  6628.7  304.52    6875  309.77  6996.5  313.52  7130.3  318.63  7326.1  320.92
#Mann= 6 ,-1 , 0
  3727.5     .05       0  4828.4      .1       0  4990.5     .07       0
  4996.5      .1       0    6875     .05       0  6996.5      .1       0
Bank Sta=4936.1,5099
XS Rating Curve= 0 ,0
Exp/Cntr=0.3,0.1

Type RM Length L Ch R = 1 ,185788  ,1148,1148,1148
BEGIN DESCRIPTION:
LAGARTO CREEK 147.0
END DESCRIPTION:
XS GIS Cut Line= 5
      2221232.81     13197655.21      2221366.68     13196809.71
      2221571.01     13196358.77      2221253.95      13195886.7
      2221014.78     13195000.38
#Sta/Elev= 30
  2831.8  303.22  3518.6  302.49  3855.7  293.75  4008.1  293.22  4230.5  294.19
  4461.5  290.43  4772.1   289.5  4831.1  285.37  4886.1  288.15  4926.3  285.46
  4987.7  282.95  4990.5  282.45  4993.7  282.95  5025.4  284.07  5041.4     287
  5060.2  284.47  5079.1  285.91  5105.2  286.91  5124.3   290.9  5179.9  292.96
  5214.6  300.34  5227.9  298.77  5248.6  303.48  5259.7  302.28  5329.2  312.89
    5435  323.66  5497.2  326.49  5603.3  323.72    5653  324.96  5669.6  325.32
#Mann= 7 ,-1 , 0
  2831.8     .05       0  4008.1      .1       0  4926.3     .12       0
  4987.7     .07       0  4993.7     .12       0  5079.1      .1       0
    5653     .08       0
Bank Sta=4772.1,5124.3
XS Rating Curve= 0 ,0
Exp/Cntr=0.3,0.1

Type RM Length L Ch R = 1 ,184640  ,1494,1494,1494
BEGIN DESCRIPTION:
LAGARTO CREEK 145.0
END DESCRIPTION:
XS GIS Cut Line= 5
      2221338.49     13197366.34      2221563.97     13196788.57
      2222050.13     13196062.85      2222317.88     13195379.39
      2222113.75     13194591.04
#Sta/Elev= 30
  3040.5  302.78  3404.6  302.26  3831.9   291.9  4444.1  291.25  4615.8  287.87
  4646.8  285.15    4682  284.21  4730.9  286.31  4798.4  284.88  4830.6  286.04
  4894.9  284.31  4991.7  282.29  5004.6  280.23  5007.4  279.73  5010.6  280.23
  5086.3  284.16  5099.1  286.89  5121.5  289.55    5137  294.72    5146  296.92
  5175.8  296.93  5185.1  298.64  5224.7  300.42  5281.2  299.04  5404.3  300.18
  5539.4  303.44  5663.4  304.09  5723.9  307.56  5787.9  308.16  6082.6  317.46
#Mann= 7 ,-1 , 0
  3040.5     .05       0  3831.9      .1       0  4894.9     .12       0
  5004.6     .07       0  5010.6     .12       0    5137      .1       0
  5787.9     .05       0
Bank Sta=4830.6,5099.1
XS Rating Curve= 0 ,0
Exp/Cntr=0.3,0.1

Type RM Length L Ch R = 1 ,183146  ,1392,1392,1392
BEGIN DESCRIPTION:
LAGARTO CREEK 144.0
END DESCRIPTION:
XS GIS Cut Line= 5
      2222155.83     13198768.46      2222719.49      13197253.6
      2222867.46      13196485.6      2222564.48     13195506.22
      2222247.93     13194500.28
#Sta/Elev= 30
  2978.1  304.01  4247.5  302.48  4270.9  301.49  4287.6  303.85  4312.6  302.48
  4733.7  301.79  4769.7  293.34  4821.6  286.89  4866.1   284.3  4969.5  277.34
  4974.3  276.64    4977  276.14  4980.3  276.64  4998.5  278.96  5091.2  279.22
  5100.3  282.34  5120.7  284.44  5202.2  284.58  5212.3  287.29  5314.2  288.05
    5438  281.38  5494.9  285.22  5561.1  285.63    6087  289.83  6526.9  298.41
  6638.9  298.34  6928.7  302.77  7033.3  305.23  7159.6  308.23  7456.3  316.49
#Mann= 9 ,-1 , 0
  2978.1     .05       0  4247.5      .1       0  4969.5     .12       0
  4974.3     .07       0  4980.3     .12       0  5561.1      .1       0
  6928.7     .05       0  7033.3      .1       0  7159.6     .05       0
#XS Ineff= 2 , 0
                            5300          287.52
Permanent Ineff=
       F       F
Bank Sta=4866.1,5120.7
XS Rating Curve= 0 ,0
Exp/Cntr=0.3,0.1

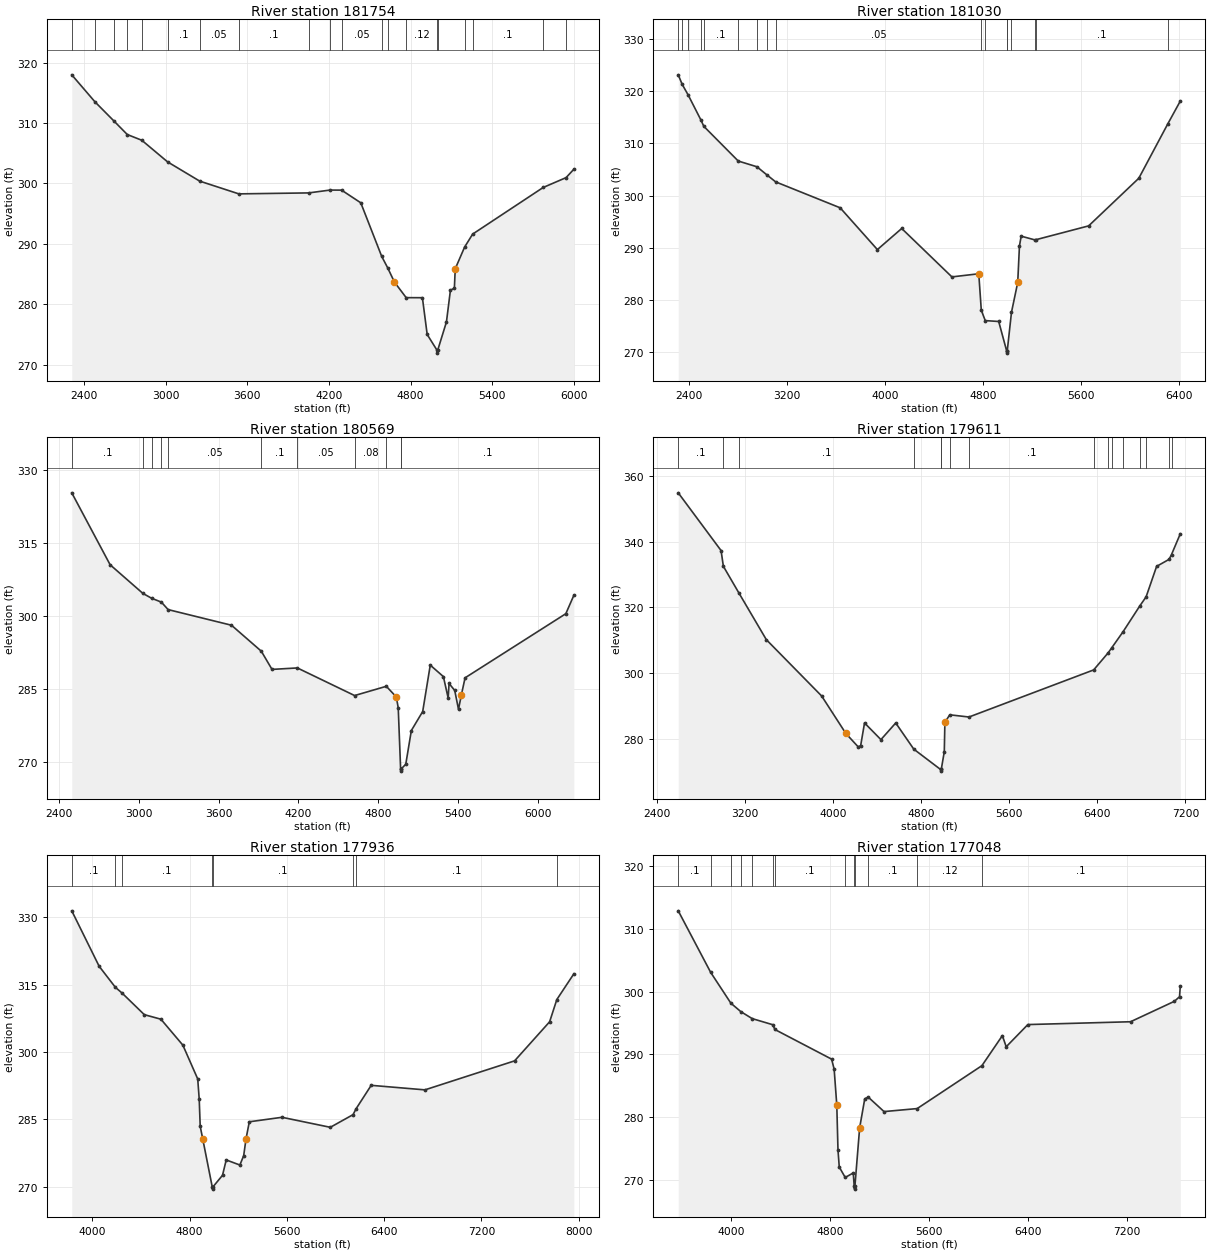
Type RM Length L Ch R = 1 ,181754  ,724,724,724
BEGIN DESCRIPTION:
LAGARTO CREEK 143.0
END DESCRIPTION:
XS GIS Cut Line= 3
       2224937.7     13197746.84      2223137.72     13195746.86
      2222537.72     13194946.86
#Sta/Elev= 30
  2309.3     318    2480  313.52    2622  310.29  2717.4  308.11  2824.2  307.16
  3013.6  303.58    3250  300.39  3537.4  298.28  4051.3  298.44  4207.3  298.91
  4292.6   298.9  4433.8   296.8  4587.7  287.92  4630.8  286.06  4681.2  283.67
  4767.4  281.09  4886.8  281.08  4921.9  274.99  4993.6   272.4  4996.4   271.9
  4999.6   272.4  5063.5  277.07  5092.7  282.32  5121.9  282.66  5128.1  285.87
  5197.1  289.47  5256.3  291.62  5774.6  299.34  5942.8  300.97    6000  302.36
#Mann= 20 ,-1 , 0
  2309.3     .05       0    2480     .08       0    2622      .1       0
  2717.4     .08       0  2824.2     .08       0  3013.6      .1       0
    3250     .05       0  3537.4      .1       0  4051.3     .05       0
  4207.3      .1       0  4292.6     .05       0  4587.7     .08       0
  4630.8      .1       0  4767.4     .12       0  4993.6     .07       0
  4999.6     .12       0  5197.1     .08       0  5256.3      .1       0
  5774.6     .05       0  5942.8      .1       0
Bank Sta=4681.2,5128.1
XS Rating Curve= 0 ,0
Exp/Cntr=0.3,0.1

Type RM Length L Ch R = 1 ,181030  ,461,461,461
BEGIN DESCRIPTION:
LAGARTO CREEK 142.0
END DESCRIPTION:
XS GIS Cut Line= 3
       2225587.7     13197096.84      2223587.72     13195296.85
      2222587.73     13194296.86
#Sta/Elev= 30
  2309.3  323.12  2341.5   321.3    2390  319.28  2494.3  314.49  2518.6  313.25
    2800  306.61  2952.9  305.51  3032.9  303.98  3105.7  302.62  3633.3  297.65
  3937.5  289.65  4136.4  293.69  4546.7  284.42  4766.4  285.02  4787.1  278.03
  4819.4  276.05  4929.4  275.88  4993.6  270.32  4996.4  269.82  4999.6  270.32
    5034  277.66  5084.9  283.35    5099  290.33  5113.1  292.22  5229.3  291.48
  5231.6  291.53  5664.7  294.19  6074.8  303.31  6312.6  313.76  6414.2   318.1
#Mann= 17 ,-1 , 0
  2309.3      .1       0  2341.5     .08       0    2390      .1       0
  2494.3     .08       0  2518.6      .1       0    2800     .08       0
  2952.9     .05       0  3032.9      .1       0  3105.7     .05       0
  4787.1      .1       0  4819.4     .12       0  4993.6     .07       0
  4999.6     .12       0    5034      .1       0  5229.3     .08       0
  5231.6      .1       0  6312.6     .05       0
Bank Sta=4766.4,5084.9
XS Rating Curve= 0 ,0
Exp/Cntr=0.3,0.1

Type RM Length L Ch R = 1 ,180569  ,958,958,958
BEGIN DESCRIPTION:
LAGARTO CREEK 141.0
END DESCRIPTION:
XS GIS Cut Line= 3
      2225657.61     13196964.69      2224727.58      13195964.2
      2223128.77     13194161.15
#Sta/Elev= 30
  2495.5  325.35  2783.9  310.58  3030.2   304.7    3096   303.7  3169.1  302.91
  3220.2  301.37  3696.6  298.16  3920.8  292.83  4001.4  289.09  4191.9  289.39
  4622.5  283.72    4861  285.62  4936.4  283.42  4950.6  281.19  4968.5   268.7
  4971.3   268.2  4974.5   268.7  5007.3  269.61  5049.3  276.54  5134.6  280.44
  5191.5  289.97  5290.2  287.61  5326.1  283.22  5332.8   286.2  5375.5  284.77
  5403.9  280.89  5424.8  283.78  5453.3  287.36    6211  300.53  6271.3   304.3
#Mann= 11 ,-1 , 0
  2495.5      .1       0  3030.2     .08       0    3096     .05       0
  3169.1      .1       0  3220.2     .05       0  3920.8      .1       0
  4191.9     .05       0  4622.5     .08       0    4861      .1       0
  4968.5     .07       0  4974.5      .1       0
Bank Sta=4936.4,5424.8
XS Rating Curve= 0 ,0
Exp/Cntr=0.3,0.1

Type RM Length L Ch R = 1 ,179611  ,1675,1675,1675
BEGIN DESCRIPTION:
LAGARTO CREEK 140.0
END DESCRIPTION:
XS GIS Cut Line= 3
      2226387.71     13196096.84      2224587.72     13194496.85
      2222587.69     13193696.84
#Sta/Elev= 30
  2591.7   354.8  2980.9  337.25  3001.9  332.46  3143.2  324.34  3392.4  310.16
  3894.9  293.04  4114.9  281.65  4227.7  277.55  4249.5  277.96  4284.6  284.85
  4433.5  279.78  4568.1  284.84  4732.2  276.88  4975.7   270.7  4978.4   270.2
  4981.7   270.7  5009.4   276.1  5014.8  285.07  5059.5  287.32  5233.6  286.65
  6366.9  300.97  6498.6  306.17  6529.9  307.64  6634.4   312.6  6786.4  320.44
  6843.3  323.18  6938.7  332.44  7052.2  334.58  7074.2  336.04  7154.1  342.36
#Mann= 16 ,-1 , 0
  2591.7      .1       0  3001.9     .08       0  3143.2      .1       0
  4732.2     .12       0  4975.7     .07       0  4981.7     .12       0
  5059.5     .05       0  5233.6      .1       0  6366.9     .05       0
  6498.6      .1       0  6529.9     .05       0  6634.4      .1       0
  6786.4     .05       0  6843.3      .1       0  7052.2     .08       0
  7074.2     .05       0
Bank Sta=4114.9,5014.8
XS Rating Curve= 0 ,0
Exp/Cntr=0.3,0.1

Type RM Length L Ch R = 1 ,177936  ,888,888,888
BEGIN DESCRIPTION:
LAGARTO CREEK 139.0
END DESCRIPTION:
XS GIS Cut Line= 4
      2226359.12      13195078.2      2226209.41     13194251.14
      2224503.66     13193917.22      2223051.21     13193375.26
#Sta/Elev= 30
  3831.7  331.42  4056.6  319.08  4190.1  314.39  4245.4   313.1  4428.3  308.29
  4564.8  307.28  4745.3   301.5  4867.5  293.97  4879.8  289.45  4887.9  283.41
  4908.3  280.68  4986.8  269.93  4989.6  269.43  4992.8  269.93  5071.3  272.51
  5101.9  275.93    5214   274.8  5245.4  276.87  5264.9  280.66  5291.8  284.43
  5560.4  285.43  5957.8   283.2  6144.9  286.02  6170.5  287.36  6294.1  292.55
  6735.9  291.54  7473.3     298  7761.5  306.71  7820.7  311.66  7960.6  317.39
#Mann= 8 ,-1 , 0
  3831.7      .1       0  4190.1     .05       0  4245.4      .1       0
  4986.8     .07       0  4992.8      .1       0  6144.9     .05       0
  6170.5      .1       0  7820.7     .05       0
Bank Sta=4908.3,5264.9
XS Rating Curve= 0 ,0
Exp/Cntr=0.3,0.1

Type RM Length L Ch R = 1 ,177048  ,1039,1039,1039
BEGIN DESCRIPTION:
LAGARTO CREEK 138.0
END DESCRIPTION:
XS GIS Cut Line= 3
      2227031.86     13194296.98      2226304.88     13193461.49
      2223441.52     13192767.34
#Sta/Elev= 30
  3576.3  312.89  3838.5  303.07  4001.3  298.17  4081.1  296.83  4173.4  295.71
  4340.7  294.73  4356.1  293.98  4814.7  289.25  4835.2  287.65  4856.5  281.92
  4866.1   274.8  4876.4  272.05  4924.6  270.39  4989.6  271.11  4996.9  269.03
  4999.6  268.53  5002.9  269.03    5041   278.3  5082.2  282.92  5110.2   283.2
  5237.9  280.89  5505.7  281.37  6028.2  288.21  6193.5     293  6224.3  291.22
  6399.2  294.76  7228.3  295.21  7582.6  298.47  7623.7   299.2  7630.1  300.91
#Mann= 13 ,-1 , 0
  3576.3      .1       0  3838.5     .05       0  4001.3      .1       0
  4081.1     .05       0  4173.4      .1       0  4340.7     .05       0
  4356.1      .1       0  4924.6     .12       0  4996.9     .07       0
  5002.9     .12       0  5110.2      .1       0  5505.7     .12       0
  6028.2      .1       0
Bank Sta=4856.5,5041
XS Rating Curve= 0 ,0
Exp/Cntr=0.3,0.1

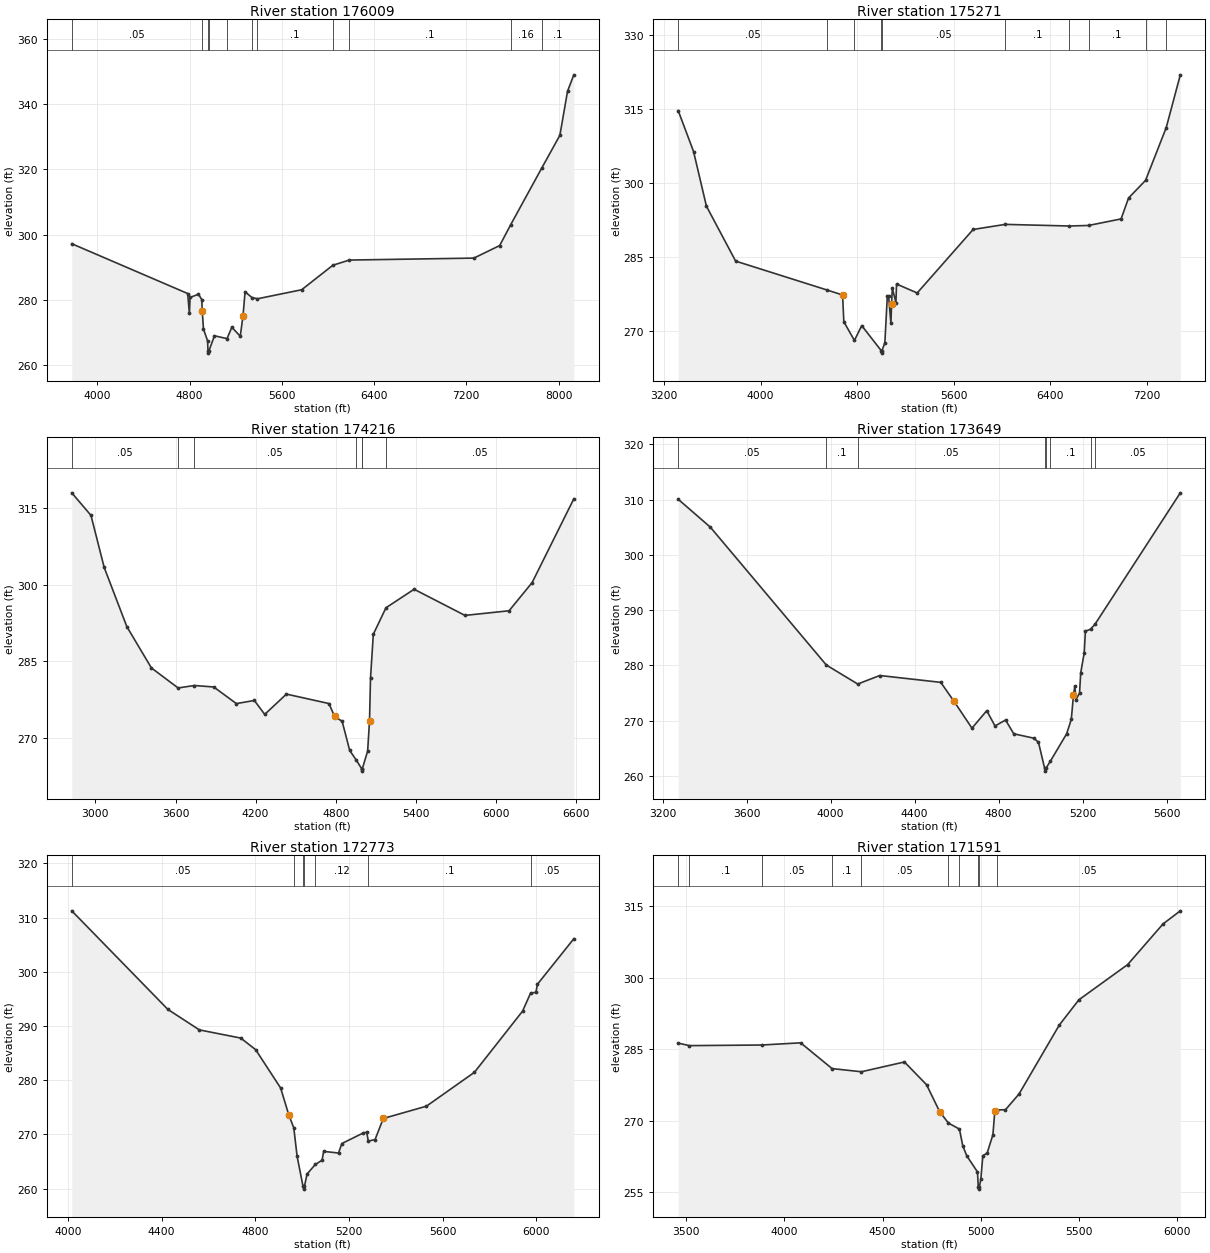
Type RM Length L Ch R = 1 ,176009  ,738,738,738
BEGIN DESCRIPTION:
LAGARTO CREEK 137.0
END DESCRIPTION:
XS GIS Cut Line= 3
      2227137.76     13193146.88      2226137.72     13192446.85
      2223137.71     13191546.85
#Sta/Elev= 30
  3779.3   297.2  4784.2  281.95    4799  275.84  4805.1  280.75  4877.9  281.74
  4906.3  280.09  4910.8  276.55  4921.1  271.08  4956.8  267.46  4960.4   264.2
  4963.1   263.7  4966.4   264.2  5016.5  269.01  5125.4  268.14    5167  271.61
  5240.1  268.87  5263.6  275.06  5281.9  282.48  5340.7  280.73    5389  280.34
  5772.6  283.11  6043.1  290.62  6186.5   292.2  7265.5   292.8  7489.1  296.64
  7583.2  302.93  7856.4  320.54  8011.2  330.41  8077.3  343.89  8132.1  348.92
#Mann= 11 ,-1 , 0
  3779.3     .05       0  4910.8     .12       0  4960.4     .07       0
  4966.4     .12       0  5125.4      .1       0  5340.7     .05       0
    5389      .1       0  6043.1     .05       0  6186.5      .1       0
  7583.2     .16       0  7856.4      .1       0
Bank Sta=4910.8,5263.6
XS Rating Curve= 0 ,0
Exp/Cntr=0.3,0.1

Type RM Length L Ch R = 1 ,175271  ,1055,1055,1055
BEGIN DESCRIPTION:
LAGARTO CREEK 136.0
END DESCRIPTION:
XS GIS Cut Line= 3
      2227451.14      13192579.8      2226617.27     13191969.95
      2223581.57     13191211.03
#Sta/Elev= 30
    3318  314.62    3445  306.35  3551.6  295.27    3794  284.12  4551.9  278.26
  4680.5  277.25  4690.8  271.82  4778.6  268.03  4839.1  271.04    5001  265.96
  5003.8  265.46    5007  265.96  5030.9  267.57  5051.5  277.09  5061.8  277.08
  5081.3   271.5  5086.5  275.39  5092.8  278.61  5122.6  275.71  5127.7  279.48
  5298.9  277.66  5762.8  290.54  6029.4  291.57    6561  291.24  6719.6  291.35
  6989.4  292.68  7051.2  296.92    7192  300.49  7363.4  311.19  7480.2   321.9
#Mann= 10 ,-1 , 0
    3318     .05       0  4551.9      .1       0  4778.6     .05       0
    5001     .03       0    5007     .05       0  6029.4      .1       0
    6561     .16       0  6719.6      .1       0    7192     .16       0
  7363.4      .1       0
Bank Sta=4680.5,5086.5
XS Rating Curve= 0 ,0
Exp/Cntr=0.3,0.1

Type RM Length L Ch R = 1 ,174216  ,567,567,567
BEGIN DESCRIPTION:
LAGARTO CREEK 135.0
END DESCRIPTION:
XS GIS Cut Line= 4
      2227637.85     13192480.26      2226430.59     13191210.76
      2225957.65     13190712.94      2224874.84     13189953.72
#Sta/Elev= 30
  2822.9  317.96  2966.7  313.55  3065.8  303.36  3235.7  291.77  3419.7   283.7
  3619.6  279.79  3741.2  280.27  3886.5  279.98    4056  276.73  4190.6  277.34
  4268.3  274.62  4430.9  278.59  4749.3  276.74  4791.7  274.22  4848.3  273.26
    4905  267.56  4951.8  265.77  4993.8  264.02  4996.6  263.52  4999.8  264.02
  5039.3  267.45  5053.4  273.41  5060.7  281.68  5081.7  290.29  5176.4  295.47
  5387.4   299.1  5768.3  293.98  6098.7  294.89  6271.3   300.4  6583.9   316.8
#Mann= 7 ,-1 , 0
  2822.9     .05       0  3619.6      .1       0  3741.2     .05       0
  4951.8      .1       0  4993.8     .07       0  4999.8      .1       0
  5176.4     .05       0
Bank Sta=4791.7,5053.4
XS Rating Curve= 0 ,0
Exp/Cntr=0.3,0.1

Type RM Length L Ch R = 1 ,173649  ,876,876,876
BEGIN DESCRIPTION:
LAGARTO CREEK 134.0
END DESCRIPTION:
XS GIS Cut Line= 3
      2227724.91     13192305.96      2226741.73      13191248.1
      2226318.57     13190401.79
#Sta/Elev= 30
  3274.9  310.05  3427.8  305.01  3980.1  280.08  4129.5  276.65  4234.5  278.19
  4524.8  276.95  4588.3   273.5  4673.3  268.67  4743.8  271.83    4783  269.07
  4833.3  270.14  4872.4  267.65  4967.4  266.86  4989.8  266.15  5019.4   261.4
  5022.1   260.9  5025.4   261.4  5046.1  262.67    5124  267.64  5146.3  270.26
  5156.5  274.58  5163.1  276.28  5168.7  273.85  5185.5     275  5191.1  278.65
  5207.8  282.28  5213.4   286.2  5237.9  286.56  5259.3  287.47  5665.3  311.22
#Mann= 8 ,-1 , 0
  3274.9     .05       0  3980.1      .1       0  4129.5     .05       0
  5019.4     .03       0  5025.4     .05       0  5046.1      .1       0
  5237.9     .12       0  5259.3     .05       0
Bank Sta=4588.3,5156.5
XS Rating Curve= 0 ,0
Exp/Cntr=0.3,0.1

Type RM Length L Ch R = 1 ,172773  ,1182,1182,1182
BEGIN DESCRIPTION:
LAGARTO CREEK 133.0
END DESCRIPTION:
XS GIS Cut Line= 3
      2228007.31     13191967.37      2227113.23     13190986.49
      2226566.36     13190378.85
#Sta/Elev= 30
    4016  311.25  4426.5  293.07    4561  289.29    4738  287.78  4801.5  285.64
  4908.2  278.57  4943.4  273.56  4964.4  271.22  4978.5     266  5003.9  260.42
  5006.6  259.92  5009.9  260.42  5021.1  262.71  5056.6  264.48  5085.2  265.24
    5092  266.88  5155.5  266.58  5169.7  268.33  5261.6  270.29  5275.8   270.4
  5282.8  268.79  5311.6  269.06  5346.7  272.95  5531.1  275.22  5736.1  281.47
  5941.7  292.75  5976.1  296.09  5998.5  296.21  6005.2  297.71  6160.7  306.11
#Mann= 7 ,-1 , 0
    4016     .05       0  4964.4      .1       0  5003.9     .07       0
  5009.9      .1       0  5056.6     .12       0  5282.8      .1       0
  5976.1     .05       0
Bank Sta=4943.4,5346.7
XS Rating Curve= 0 ,0
Exp/Cntr=0.3,0.1

Type RM Length L Ch R = 1 ,171591  ,1119,1119,1119
BEGIN DESCRIPTION:
Mapping XS 797eacd3
END DESCRIPTION:
XS GIS Cut Line= 3
      2228730.76     13190736.66       2228322.8     13190320.01
      2226395.74     13189903.35
#Sta/Elev= 30
  3460.2  286.28  3516.4  285.75    3885  285.88  4083.1  286.34    4243  280.94
  4392.5  280.28  4611.2  282.33  4723.8  277.56    4791  271.87    4835  269.54
    4891  268.27  4907.9  264.79  4928.4  262.67  4982.8  259.31  4986.8   256.2
  4989.5   255.7  4992.8   256.2    5000  257.85  5010.2  262.71  5032.1  263.25
  5061.4   267.1  5071.1  272.12  5084.6  272.29  5125.4  272.33  5194.4  275.63
    5399  290.05  5498.8  295.35  5746.9  302.72  5926.6  311.22  6014.9  313.98
#Mann= 10 ,-1 , 0
  3460.2     .05       0  3516.4      .1       0    3885     .05       0
    4243      .1       0  4392.5     .05       0    4835      .1       0
    4891     .12       0  4986.8     .07       0  4992.8     .12       0
  5084.6     .05       0
Bank Sta=4791,5071.1
XS Rating Curve= 0 ,0
Exp/Cntr=0.3,0.1

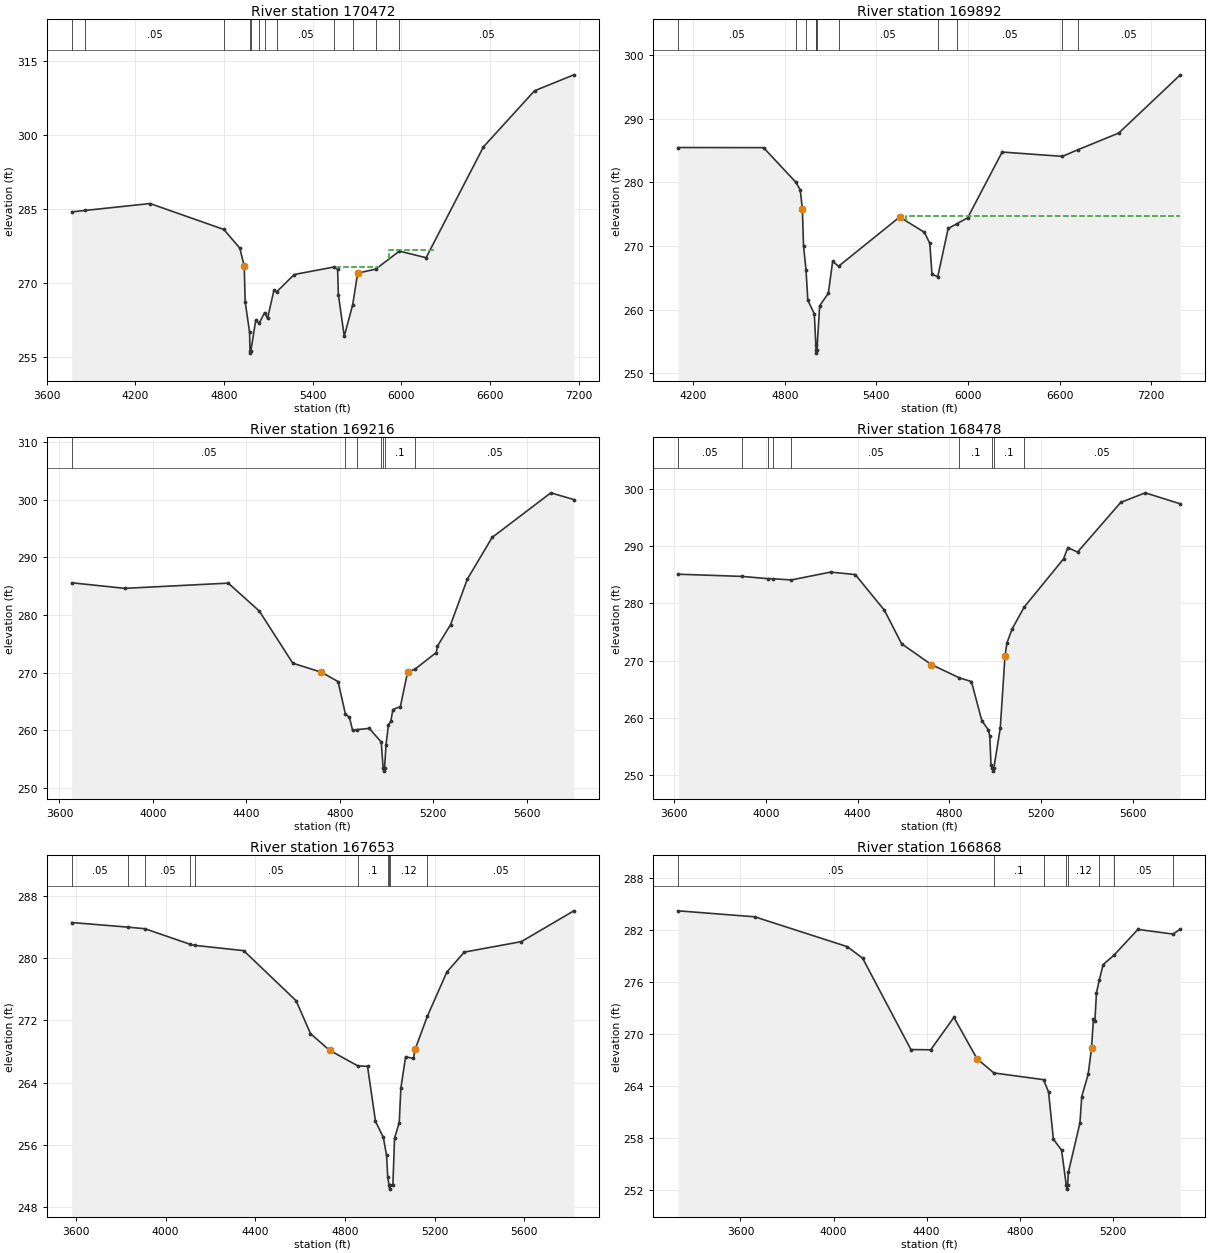
Type RM Length L Ch R = 1 ,170472  ,580,580,580
BEGIN DESCRIPTION:
Mapping XS cf9fee41
END DESCRIPTION:
XS GIS Cut Line= 5
      2228878.36      13190285.3      2228348.84     13189712.38
      2227619.67     13189217.58      2227012.03     13189148.14
      2226075.51     13189772.49
#Sta/Elev= 30
  3768.7   284.4  3857.2  284.68  4298.6  286.09  4797.8  280.83  4906.3  277.03
  4936.2  273.34  4942.3  266.18  4972.2     260  4975.2  256.22    4978  255.72
  4981.2  256.22  5014.1  262.42  5036.4  261.74  5074.1  263.95    5094  262.78
  5136.9  268.45  5155.8  268.17  5274.6  271.68    5544  273.21  5568.2   272.7
  5573.3  267.59  5613.2  259.15  5670.2  265.54  5703.8  271.96    5825  272.76
  5986.5  276.43    6167  275.09  6555.4   297.6  6900.9  308.98  7167.2  312.22
#Mann= 12 ,-1 , 0
  3768.7      .1       0  3857.2     .05       0  4797.8      .1       0
  4975.2     .07       0  4981.2      .1       0  5036.4     .16       0
  5074.1     .12       0  5155.8     .05       0    5544      .1       0
  5670.2     .05       0    5825      .1       0  5986.5     .05       0
#XS Ineff= 2 ,-1
 5562.71 5850.91  273.21 5914.36 6220.14  276.59
Permanent Ineff=
       F       F
Bank Sta=4936.2,5703.8
XS Rating Curve= 0 ,0
Exp/Cntr=0.3,0.1

Type RM Length L Ch R = 1 ,169892  ,676,676,676
BEGIN DESCRIPTION:
LAGARTO CREEK 132.0
END DESCRIPTION:
XS GIS Cut Line= 4
       2228583.2     13189799.15      2228435.64      13189208.9
      2227211.68     13188071.75      2227124.88     13187064.78
#Sta/Elev= 30
  4101.5  285.47  4660.5  285.45  4872.8     280  4900.8  278.82    4915  275.81
  4922.3  270.06  4938.9  266.19  4950.6  261.48  4993.2  259.34  5003.2  254.41
  5004.3  253.67  5007.1  253.17  5010.3  253.67  5028.3   260.6    5085  262.59
  5113.3  267.58  5152.2  266.82  5552.1  274.55  5714.8  272.15    5750  270.42
  5764.2  265.55  5801.9  265.18  5870.2  272.75  5926.6  273.49  5997.7  274.43
  6223.9  284.76  6618.6  284.08  6718.1   285.1  6987.7  287.74  7391.3  296.89
#Mann= 11 ,-1 , 0
  4101.5     .05       0  4872.8      .1       0  4938.9     .16       0
  5003.2      .1       0  5004.3     .07       0  5010.3      .1       0
  5152.2     .05       0  5801.9     .12       0  5926.6     .05       0
  6618.6      .1       0  6718.1     .05       0
#XS Ineff= 2 , 0
                          5592.9          274.66
Permanent Ineff=
       F       F
Bank Sta=4915,5552.1
XS Rating Curve= 0 ,0
Exp/Cntr=0.3,0.1

Type RM Length L Ch R = 1 ,169216  ,738,738,738
BEGIN DESCRIPTION:
Mapping XS 1cb21580
END DESCRIPTION:
XS GIS Cut Line= 4
      2228609.26     13189773.12      2228652.66     13189191.54
       2228409.6     13188080.43      2228661.36     13187733.17
#Sta/Elev= 30
  3652.8  285.59  3879.7  284.62  4322.7  285.53  4455.8  280.68  4599.1  271.63
  4721.9  270.06  4792.8  268.44  4824.4  262.81  4841.8  262.22    4855  259.97
  4875.9  260.12  4926.6  260.31  4977.8  257.95  4985.8   253.4  4988.5   252.9
  4991.8   253.4  4998.3  257.51  5008.5  260.94  5018.8  261.56  5027.5  263.58
  5059.7  264.11  5090.4  270.08  5121.8  270.59  5213.3  273.48  5218.4  274.61
  5274.7  278.33  5346.3  286.22  5452.5  293.46  5703.8   301.2  5802.3  300.03
#Mann= 7 ,-1 , 0
  3652.8     .05       0  4824.4      .1       0  4875.9     .12       0
  4977.8      .1       0  4985.8     .07       0  4991.8      .1       0
  5121.8     .05       0
Bank Sta=4721.9,5090.4
XS Rating Curve= 0 ,0
Exp/Cntr=0.3,0.1

Type RM Length L Ch R = 1 ,168478  ,825,825,825
BEGIN DESCRIPTION:
LAGARTO CREEK 131.0
END DESCRIPTION:
XS GIS Cut Line= 3
      2228689.94     13189841.69      2229078.59     13188396.41
      2228957.14     13187716.29
#Sta/Elev= 30
  3618.7  285.09  3896.4  284.71  4008.2  284.32  4029.5   284.3  4111.2  284.09
  4282.7  285.46    4390  285.03  4517.3  278.78    4592  272.94  4721.4  269.32
    4844  266.99  4896.2  266.35  4941.3  259.53  4969.9   257.9  4976.1  256.86
  4981.3  251.86  4987.6  251.21  4990.3  250.71  4993.6  251.21  5021.7  258.19
  5042.4  270.83  5050.9  273.11  5073.4  275.53  5125.4  279.32  5297.7  287.78
  5316.1  289.73  5358.7  288.96  5546.7  297.63  5653.3   299.3  5806.2  297.38
#Mann= 9 ,-1 , 0
  3618.7     .05       0  3896.4      .1       0  4008.2     .05       0
  4029.5      .1       0  4111.2     .05       0    4844      .1       0
  4987.6     .07       0  4993.6      .1       0  5125.4     .05       0
Bank Sta=4721.4,5042.4
XS Rating Curve= 0 ,0
Exp/Cntr=0.3,0.1

Type RM Length L Ch R = 1 ,167653  ,785,785,785
BEGIN DESCRIPTION:
LAGARTO CREEK 130.0
END DESCRIPTION:
XS GIS Cut Line= 3
      2228847.79     13189853.92      2229394.37     13189161.58
      2230329.61     13188177.76
#Sta/Elev= 30
  3581.7  284.57  3830.8  283.98  3908.4  283.77    4111  281.76  4129.9  281.64
  4348.5  280.96  4582.5  274.53  4646.4  270.32  4731.4  268.17  4857.1  266.18
  4900.9  266.11  4936.4  259.06  4971.6  256.98  4985.8  254.68  4991.2  251.88
    4997  250.85  4999.7  250.35    5003  250.85  5014.1  250.88  5021.4  256.88
  5042.4  258.89  5049.7  263.33  5070.7  267.32  5105.9  267.14  5113.2  268.28
  5167.3  272.51  5254.8  278.22  5332.4  280.77  5587.2  282.12  5821.2  286.07
#Mann= 10 ,-1 , 0
  3581.7     .05       0  3830.8      .1       0  3908.4     .05       0
    4111      .1       0  4129.9     .05       0  4857.1      .1       0
  4991.2     .12       0    4997     .07       0    5003     .12       0
  5167.3     .05       0
Bank Sta=4731.4,5113.2
XS Rating Curve= 0 ,0
Exp/Cntr=0.3,0.1

Type RM Length L Ch R = 1 ,166868  ,1167,1167,1167
BEGIN DESCRIPTION:
LAGARTO CREEK 129.0
END DESCRIPTION:
XS GIS Cut Line= 3
      2229007.27     13189970.37      2229685.86     13189659.55
      2230802.99     13188797.42
#Sta/Elev= 30
  3332.6  284.16  3661.4  283.47    4059  280.03  4124.9   278.7  4332.4  268.17
  4417.5  268.14  4517.1  271.88  4616.8   267.1  4689.1  265.47  4902.2   264.7
  4923.8  263.29  4944.7  257.84    4980  256.56  4999.7  252.58  5002.4  252.08
  5005.7  252.58    5009  254.01  5058.8  259.71  5066.6  262.75  5094.1  265.31
  5108.6  268.32  5116.8  271.73  5123.1   271.5  5129.8  274.71  5141.7  276.15
  5158.4  277.96  5204.8  279.04  5307.9  282.02  5458.6  281.48  5490.1  282.05
#Mann= 8 ,-1 , 0
  3332.6     .05       0  4689.1      .1       0  4902.2     .12       0
  4999.7     .07       0  5005.7     .12       0  5141.7      .1       0
  5204.8     .05       0  5458.6      .1       0
Bank Sta=4616.8,5108.6
XS Rating Curve= 0 ,0
Exp/Cntr=0.3,0.1

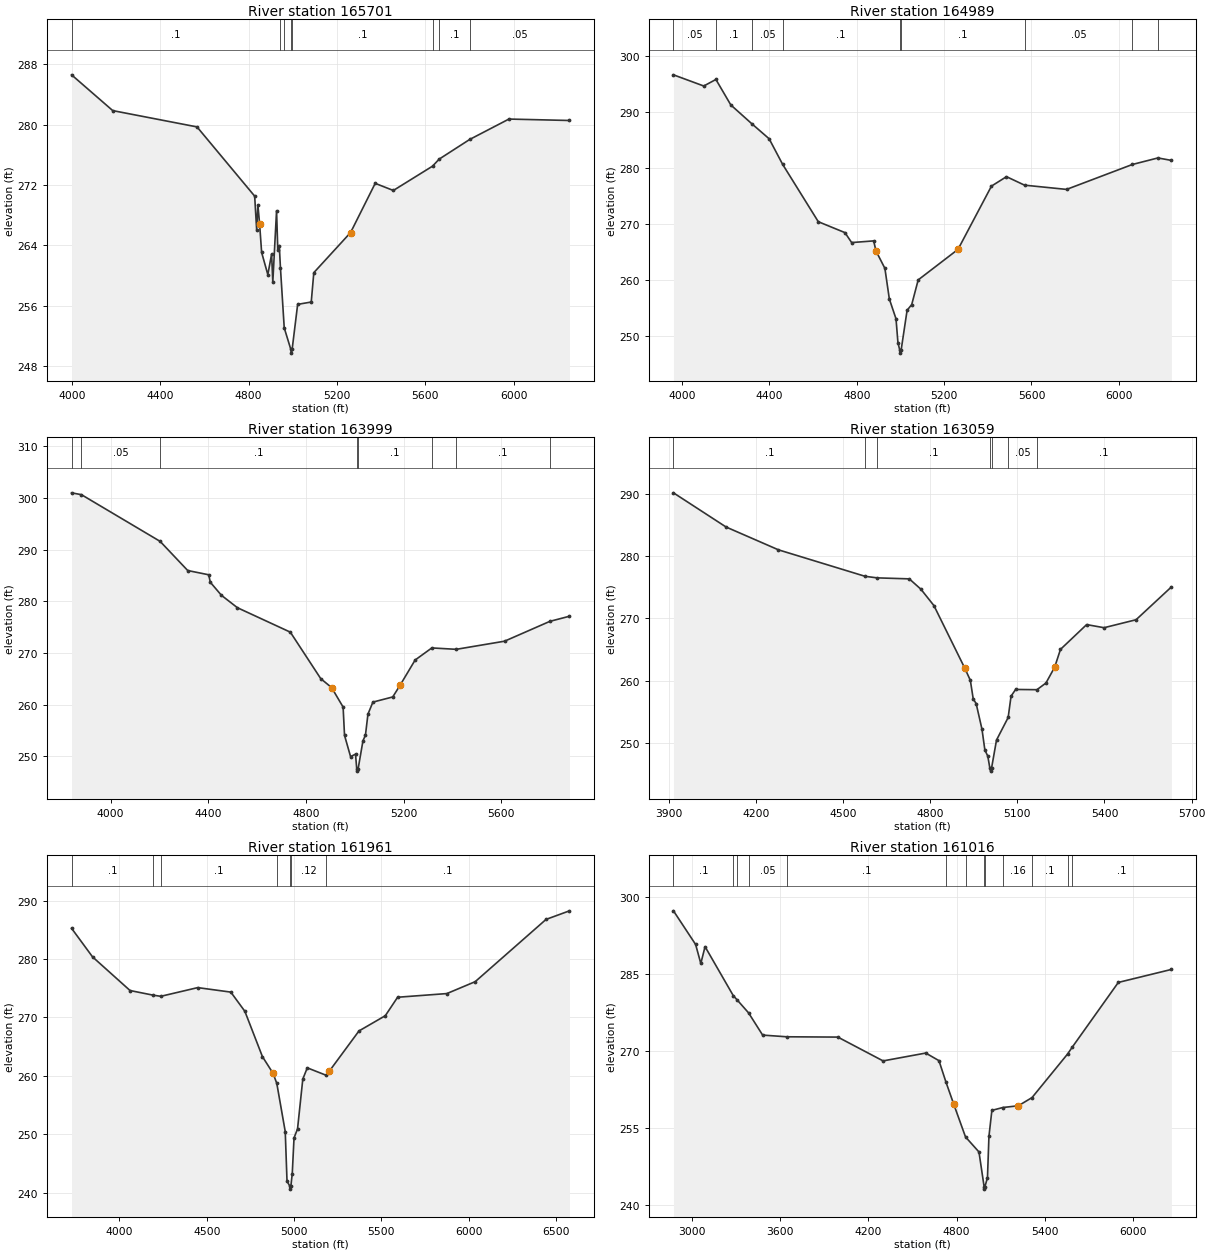
Type RM Length L Ch R = 1 ,165701  ,712,712,712
BEGIN DESCRIPTION:
LAGARTO CREEK 128.0
END DESCRIPTION:
XS GIS Cut Line= 4
      2230293.15     13190825.52      2230633.22     13190521.89
      2231204.06     13189355.91       2231325.3     13188870.95
#Sta/Elev= 30
  3998.8   286.6  4185.2  281.86  4566.7   279.7  4827.7  270.53  4836.7  266.08
  4842.3  269.35    4850  266.87  4859.2  263.07  4887.3  260.13  4904.3  262.85
  4909.8  259.14  4926.8   268.6  4932.3  263.44  4939.1  263.98  4944.4  261.02
  4961.5  253.08  4991.3  250.23    4994  249.73  4997.3  250.23  5022.3  256.19
  5083.8   256.5  5095.4  260.39    5262  265.71  5373.3  272.22  5455.5  271.28
  5632.9   274.5  5662.8  275.43  5801.2  278.04  5978.7  280.74  6252.8  280.55
#Mann= 8 ,-1 , 0
  3998.8      .1       0  4944.4     .05       0  4961.5      .1       0
  4991.3     .07       0  4997.3      .1       0  5632.9     .05       0
  5662.8      .1       0  5801.2     .05       0
Bank Sta=4850,5262
XS Rating Curve= 0 ,0
Exp/Cntr=0.3,0.1

Type RM Length L Ch R = 1 ,164989  ,990,990,990
BEGIN DESCRIPTION:
LAGARTO CREEK 127.0
END DESCRIPTION:
XS GIS Cut Line= 3
      2231179.77     13191311.34      2231313.37     13190789.09
      2231629.16     13189076.53
#Sta/Elev= 30
  3960.4   296.7  4099.2   294.7  4154.8  295.87  4223.1  291.31  4320.1  287.92
  4398.6  285.26  4460.5  280.68  4623.8  270.42  4745.8  268.47  4776.5  266.69
  4877.4  266.99  4888.1  265.18  4928.8  262.07  4949.2  256.59  4979.7  253.05
  4988.5  248.81    4997  247.41  4999.7  246.91    5003  247.41  5030.5  254.58
  5051.6  255.59  5081.3  260.01  5263.6  265.47  5416.9  276.79  5485.7  278.48
  5568.4  276.96  5760.9   276.2  6062.2  280.66  6179.3  281.83  6240.9  281.39
#Mann= 9 ,-1 , 0
  3960.4     .05       0  4154.8      .1       0  4320.1     .05       0
  4460.5      .1       0    4997     .07       0    5003      .1       0
  5568.4     .05       0  6062.2      .1       0  6179.3     .05       0
Bank Sta=4888.1,5263.6
XS Rating Curve= 0 ,0
Exp/Cntr=0.3,0.1

Type RM Length L Ch R = 1 ,163999  ,940,940,940
BEGIN DESCRIPTION:
LAGARTO CREEK 126.0
END DESCRIPTION:
XS GIS Cut Line= 3
       2231665.6     13191614.98      2232102.84     13191250.62
      2232370.04     13189805.26
#Sta/Elev= 30
  3839.8  300.99  3880.4  300.63  4202.5   291.6  4315.5  285.96  4401.4  285.14
  4407.9   283.7  4453.5  281.17  4518.9  278.77  4735.7  274.04  4860.2  265.05
  4904.7  263.32  4951.8  259.55  4957.6  254.08  4982.3  249.97  5002.6  250.44
  5007.5  247.66  5010.3  247.16  5013.5  247.66  5033.1  253.03  5043.3  254.12
  5053.5  258.18  5073.8  260.51  5155.1  261.51  5185.7  263.82  5246.7  268.65
  5315.1  270.99  5415.1  270.72  5612.8  272.29  5798.5  276.13  5878.8  277.12
#Mann= 8 ,-1 , 0
  3839.8      .1       0  3880.4     .05       0  4202.5      .1       0
  5007.5     .07       0  5013.5      .1       0  5315.1     .05       0
  5415.1      .1       0  5798.5     .16       0
Bank Sta=4904.7,5185.7
XS Rating Curve= 0 ,0
Exp/Cntr=0.3,0.1

Type RM Length L Ch R = 1 ,163059  ,1098,1098,1098
BEGIN DESCRIPTION:
LAGARTO CREEK 125.0
END DESCRIPTION:
XS GIS Cut Line= 2
      2233074.48     13192027.94      2233013.75     13190315.42
#Sta/Elev= 30
  3916.6  290.13  4097.8  284.64  4277.9  280.98  4576.1  276.73  4617.6  276.48
  4728.2  276.32  4768.2  274.66    4813  272.03  4918.3  262.07  4938.3  260.04
  4948.3  257.04  4958.3  256.31  4978.4  252.18  4988.4  248.83  4998.4  247.87
  5005.4  245.96  5008.1  245.46  5011.4  245.96  5028.4  250.45  5068.5  254.07
  5078.4  257.49  5094.2  258.57  5167.5  258.53  5198.5   259.6  5228.5  262.14
  5248.5     265  5338.6  268.98  5398.6  268.48  5508.7  269.76  5630.2  275.02
#Mann= 7 ,-1 , 0
  3916.6      .1       0  4576.1     .08       0  4617.6      .1       0
  5005.4     .07       0  5011.4      .1       0  5068.5     .05       0
  5167.5      .1       0
Bank Sta=4918.3,5228.5
XS Rating Curve= 0 ,0
Exp/Cntr=0.3,0.1

Type RM Length L Ch R = 1 ,161961  ,945,945,945
BEGIN DESCRIPTION:
LAGARTO CREEK 124.0
END DESCRIPTION:
XS GIS Cut Line= 4
      2233924.13     13191997.04      2234104.69     13191247.03
       2233965.8     13189955.36      2234097.74     13189184.53
#Sta/Elev= 30
  3725.5  285.27  3845.8  280.37  4060.6  274.61  4192.3  273.82  4236.6  273.62
  4448.3  275.11  4637.9  274.34  4718.4  271.05    4819  263.29  4879.3  260.46
  4901.2  258.72  4949.7  250.45  4959.8  241.98  4975.9   241.1  4978.7   240.6
  4981.9   241.1  4989.9  243.27    5000  249.37  5020.1  250.91  5050.3  259.45
    5076  261.37  5183.1  260.11  5201.2  260.76  5372.1  267.69    5523   270.3
  5593.4  273.46  5875.7  274.09    6038  276.13  6443.8  286.79  6578.1  288.26
#Mann= 7 ,-1 , 0
  3725.5      .1       0  4192.3     .05       0  4236.6      .1       0
  4901.2     .12       0  4975.9     .07       0  4981.9     .12       0
  5183.1      .1       0
Bank Sta=4879.3,5201.2
XS Rating Curve= 0 ,0
Exp/Cntr=0.3,0.1

Type RM Length L Ch R = 1 ,161016  ,1049,1049,1049
BEGIN DESCRIPTION:
LAGARTO CREEK 123.0
END DESCRIPTION:
XS GIS Cut Line= 3
      2234038.81     13192410.42      2234923.24      13191315.4
      2234951.32     13189335.88
#Sta/Elev= 30
  2873.8  297.29  3024.7  290.73  3059.9  287.03  3088.7  290.31  3280.5  280.78
  3308.7  279.88  3384.5  277.42  3480.5  273.08  3644.2  272.75  3992.2  272.69
  4299.9  268.05    4590  269.58    4680   268.1  4727.9   263.9    4780  259.66
  4860.6  253.24  4952.2  250.31    4987  243.57  4989.7  243.07    4993  243.57
    5010  245.32    5020  253.34    5040  258.41  5114.3  258.97    5220  259.31
  5313.3  260.91  5554.6  269.38  5585.8  270.69  5900.1  283.34  6261.1  285.87
#Mann= 13 ,-1 , 0
  2873.8      .1       0  3280.5     .05       0  3308.7      .1       0
  3384.5     .05       0  3644.2      .1       0  4727.9     .05       0
  4860.6      .1       0    4987     .07       0    4993      .1       0
  5114.3     .16       0  5313.3      .1       0  5554.6     .16       0
  5585.8      .1       0
Bank Sta=4780,5220
XS Rating Curve= 0 ,0
Exp/Cntr=0.3,0.1