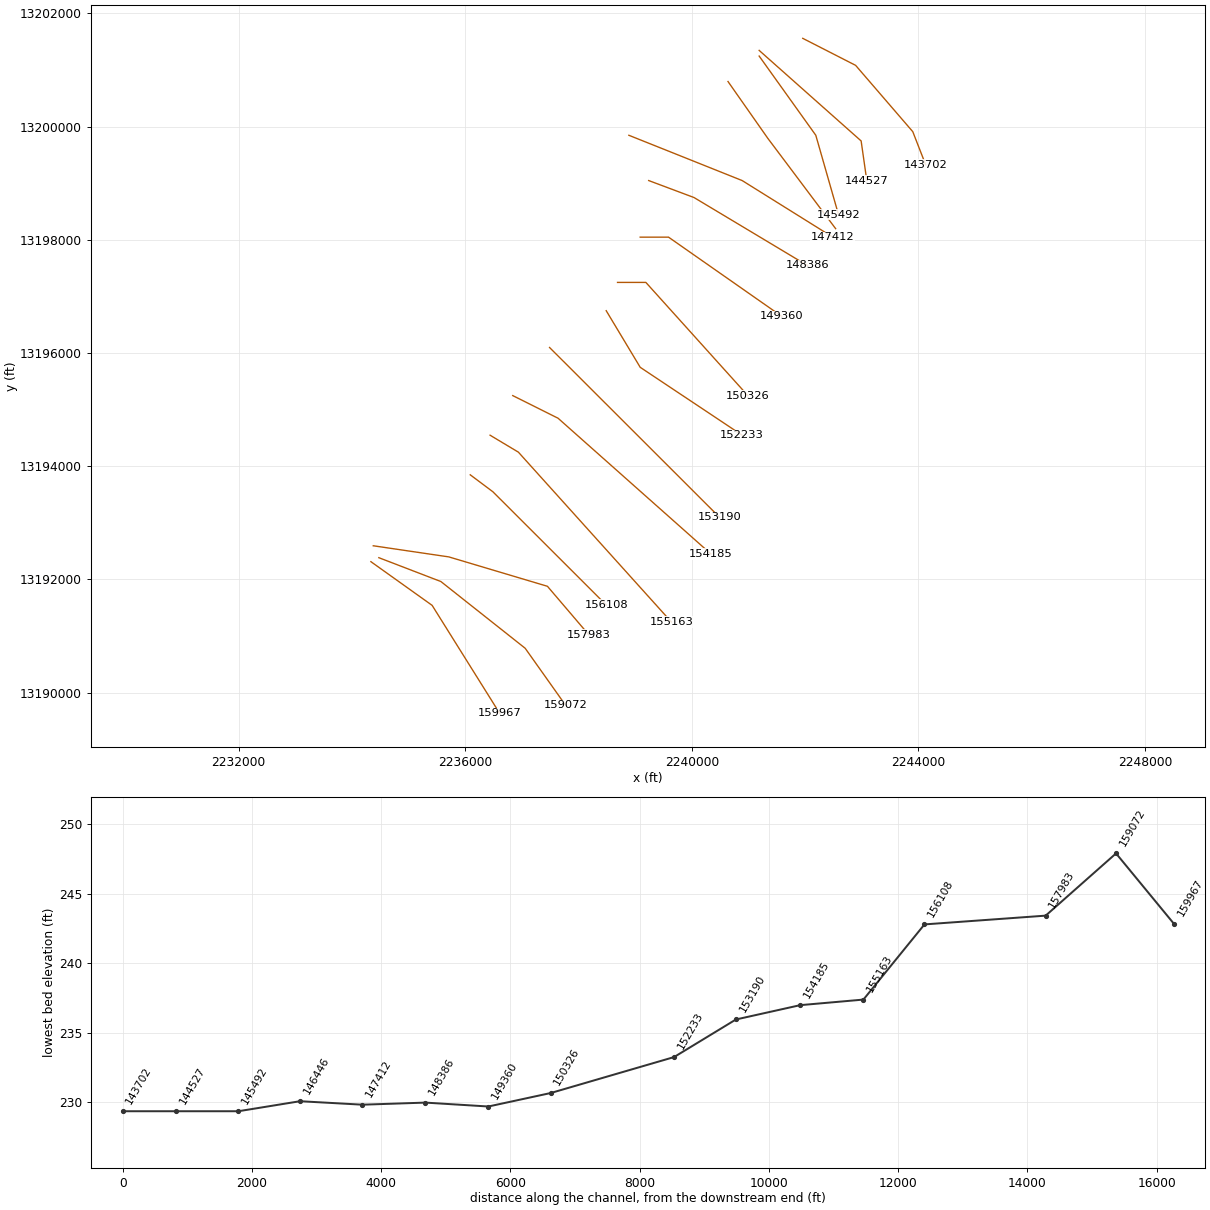
HEC-RAS study LAGARTO CREEK.prj: LAGARTO CREEK Base Level Engineering

--- LAGARTO CREEK.g01 (geometry) --- (continued)

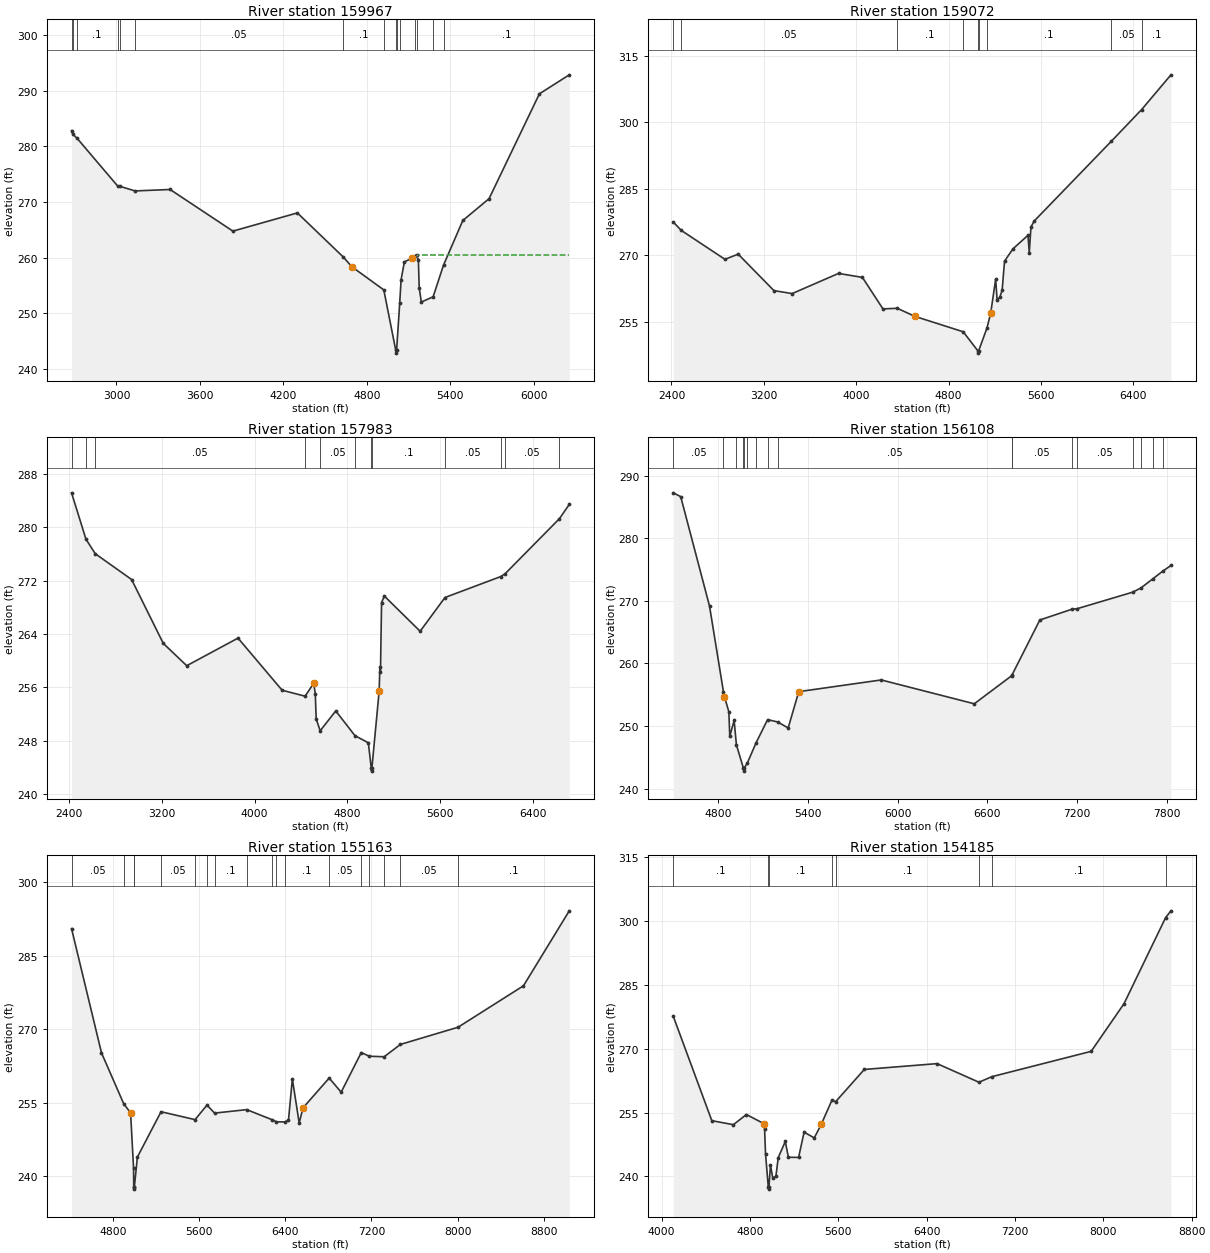
Type RM Length L Ch R = 1 ,159967  ,895,895,895
BEGIN DESCRIPTION:
LAGARTO CREEK 122.0
END DESCRIPTION:
XS GIS Cut Line= 3
      2234333.57      13192312.2      2235414.61     13191540.02
      2236607.59     13189631.26
#Sta/Elev= 30
  2677.2   282.8  2686.2  282.16  2715.9  281.46  3007.8  272.88  3024.4   272.8
  3134.1  271.97    3386  272.23  3837.5  264.75  4301.2  268.02  4632.5  260.07
  4693.4  258.34  4922.8  254.19  5008.8  243.33  5011.5  242.83  5014.8  243.33
  5037.1  251.77  5047.2  256.05  5070.8  259.22    5129  259.93    5148  260.32
    5158  260.49  5171.5   259.5  5177.4  254.55  5192.7  252.01  5277.5  252.95
  5352.2  258.64    5491  266.66  5679.7  270.58  6041.8  289.42  6256.6  292.83
#Mann= 15 ,-1 , 0
  2677.2      .1       0  2686.2     .05       0  2715.9      .1       0
  3007.8     .05       0  3024.4      .1       0  3134.1     .05       0
  4632.5      .1       0  4922.8     .12       0  5008.8     .07       0
  5014.8     .12       0  5037.1      .1       0    5148     .12       0
    5158      .1       0  5277.5     .12       0  5352.2      .1       0
#XS Ineff= 2 , 0
                         5164.69          260.48
Permanent Ineff=
       F       F
Bank Sta=4693.4,5129
XS Rating Curve= 0 ,0
Exp/Cntr=0.3,0.1

Type RM Length L Ch R = 1 ,159072  ,1089,1089,1089
BEGIN DESCRIPTION:
LAGARTO CREEK 121.0
END DESCRIPTION:
XS GIS Cut Line= 4
      2234474.01     13192382.36      2235569.04     13191961.19
      2237057.17     13190781.92      2237772.66     13189771.82
#Sta/Elev= 30
  2415.2  277.48  2484.2  275.59  2863.1  269.05  2977.7  270.22    3287  261.99
  3444.8  261.32  3846.6  265.87  4053.4  264.97  4231.2  257.86  4354.8     258
  4508.4  256.17  4926.1   252.7  5053.5  248.38  5056.2  247.88  5059.5  248.38
  5131.4  253.51  5163.9  256.85  5207.2  264.59  5219.9  259.83  5242.4  260.45
  5263.2  262.06    5284  268.64  5356.2   271.4  5487.2  274.48  5498.1  270.57
  5512.9  276.38  5542.4  277.74  6208.9   295.7  6471.5  302.86    6725  310.69
#Mann= 9 ,-1 , 0
  2415.2      .1       0  2484.2     .05       0  4354.8      .1       0
  4926.1     .12       0  5053.5     .07       0  5059.5     .12       0
  5131.4      .1       0  6208.9     .05       0  6471.5      .1       0
Bank Sta=4508.4,5163.9
XS Rating Curve= 0 ,0
Exp/Cntr=0.3,0.1

Type RM Length L Ch R = 1 ,157983  ,1875,1875,1875
BEGIN DESCRIPTION:
LAGARTO CREEK 120.0
END DESCRIPTION:
XS GIS Cut Line= 4
      2234375.76     13192592.94      2235709.43      13192396.4
      2237450.27     13191876.96      2238179.73     13191021.24
#Sta/Elev= 30
  2422.3  285.15  2546.3   278.2  2626.5  276.02  2939.8  272.15  3212.7  262.57
  3414.9  259.22  3856.8  263.36    4237  255.54  4435.1  254.65  4509.5   256.6
  4522.9  254.96  4530.4  251.24  4564.8  249.46  4699.1  252.44  4864.6  248.73
  4979.9  247.66  5004.8  243.91  5007.5  243.41  5010.8  243.91    5073  255.39
  5079.3  259.05  5084.5  258.28  5093.9  268.68  5117.6  269.67  5426.3  264.39
  5640.3  269.45  6120.7  272.59  6158.9  273.02  6626.4  281.27  6711.5  283.41
#Mann= 12 ,-1 , 0
  2422.3     .05       0  2546.3      .1       0  2626.5     .05       0
  4435.1      .1       0  4564.8     .05       0  4864.6      .1       0
  5004.8     .07       0  5010.8      .1       0  5640.3     .05       0
  6120.7      .1       0  6158.9     .05       0  6626.4      .1       0
Bank Sta=4509.5,5073
XS Rating Curve= 0 ,0
Exp/Cntr=0.3,0.1

Type RM Length L Ch R = 1 ,156108  ,945,945,945
BEGIN DESCRIPTION:
LAGARTO CREEK 119.0
END DESCRIPTION:
XS GIS Cut Line= 3
      2236087.72     13193846.85      2236487.72     13193546.85
       2238487.7     13191546.87
#Sta/Elev= 30
    4500  287.25    4550  286.64  4742.7  269.15  4836.1  255.41  4842.7  254.64
  4871.9  252.27  4878.1  248.37  4907.3  250.87  4922.5  246.98  4968.9  243.28
  4971.6  242.78  4974.9  243.28  4994.5  244.02  5054.7  247.34    5131  251.01
  5197.8  250.64  5268.7  249.68  5339.4  255.48    5891  257.35  6513.2  253.54
  6764.1  258.04  6766.3  258.18  6951.6  266.93  7166.1  268.65  7200.4  268.73
  7573.2  271.38  7629.5  272.08  7708.9  273.54  7772.6  274.72  7828.4  275.64
#Mann= 17 ,-1 , 0
    4500     .05       0  4836.1      .1       0  4922.5     .05       0
  4968.9     .07       0  4974.9     .05       0  4994.5      .1       0
  5054.7     .05       0    5131      .1       0  5197.8     .05       0
  6764.1      .1       0  6766.3     .05       0  7166.1      .1       0
  7200.4     .05       0  7573.2      .1       0  7629.5     .05       0
  7708.9      .1       0  7772.6     .05       0
Bank Sta=4842.7,5339.4
XS Rating Curve= 0 ,0
Exp/Cntr=0.3,0.1

Type RM Length L Ch R = 1 ,155163  ,978,978,978
BEGIN DESCRIPTION:
LAGARTO CREEK 118.0
END DESCRIPTION:
XS GIS Cut Line= 3
      2236437.72     13194546.86      2236937.72     13194246.85
      2239637.73     13191246.85
#Sta/Elev= 30
  4416.9  290.53  4694.8  265.18  4900.2  254.84    4965  252.92  4992.2  241.73
  4994.1  237.88  4996.8  237.38  5000.1  237.88    5028  243.93  5247.4  253.17
  5563.2  251.56    5674  254.53  5744.5  252.89  6042.3   253.6  6280.7  251.52
  6318.9  251.12  6400.5  251.09  6430.2   251.5  6466.1  259.85  6529.6  250.86
  6564.7  253.95  6807.8  260.04    6919  257.16  7105.8  265.25    7180  264.49
  7318.6  264.39  7468.6   266.9  8003.8  270.41  8611.2  278.87  9036.1  294.16
#Mann= 18 ,-1 , 0
  4416.9     .05       0  4900.2      .1       0  4994.1     .07       0
  5000.1      .1       0  5247.4     .05       0  5563.2      .1       0
    5674     .05       0  5744.5      .1       0  6042.3     .05       0
  6280.7      .1       0  6318.9     .05       0  6400.5      .1       0
  6807.8     .05       0  7105.8      .1       0    7180     .05       0
  7318.6      .1       0  7468.6     .05       0  8003.8      .1       0
Bank Sta=4965,6564.7
XS Rating Curve= 0 ,0
Exp/Cntr=0.3,0.1

Type RM Length L Ch R = 1 ,154185  ,995,995,995
BEGIN DESCRIPTION:
LAGARTO CREEK 117.0
END DESCRIPTION:
XS GIS Cut Line= 3
      2236837.74     13195246.84      2237637.72     13194846.85
      2240337.74     13192446.84
#Sta/Elev= 30
  4105.6  277.66    4455  253.08  4650.6  252.14    4768  254.53  4924.5  252.41
  4932.9   251.2  4941.3  245.31  4966.3  237.48    4969  236.98  4972.3  237.48
    4986  242.68  5007.1  239.52  5035.5  240.02  5056.4  244.39  5120.4  248.19
  5148.4  244.47  5240.8  244.44  5290.6  250.38  5382.6  249.03  5446.1  252.23
  5542.3  257.88  5575.9  257.54  5835.8  265.13  6494.7   266.5  6874.1  262.12
  6989.4  263.42    7890  269.39  8187.3  280.59  8563.9  300.83  8612.5  302.44
#Mann= 8 ,-1 , 0
  4105.6      .1       0  4966.3     .07       0  4972.3      .1       0
  5542.3     .08       0  5575.9      .1       0  6874.1     .16       0
  6989.4      .1       0  8563.9     .05       0
Bank Sta=4924.5,5446.1
XS Rating Curve= 0 ,0
Exp/Cntr=0.3,0.1

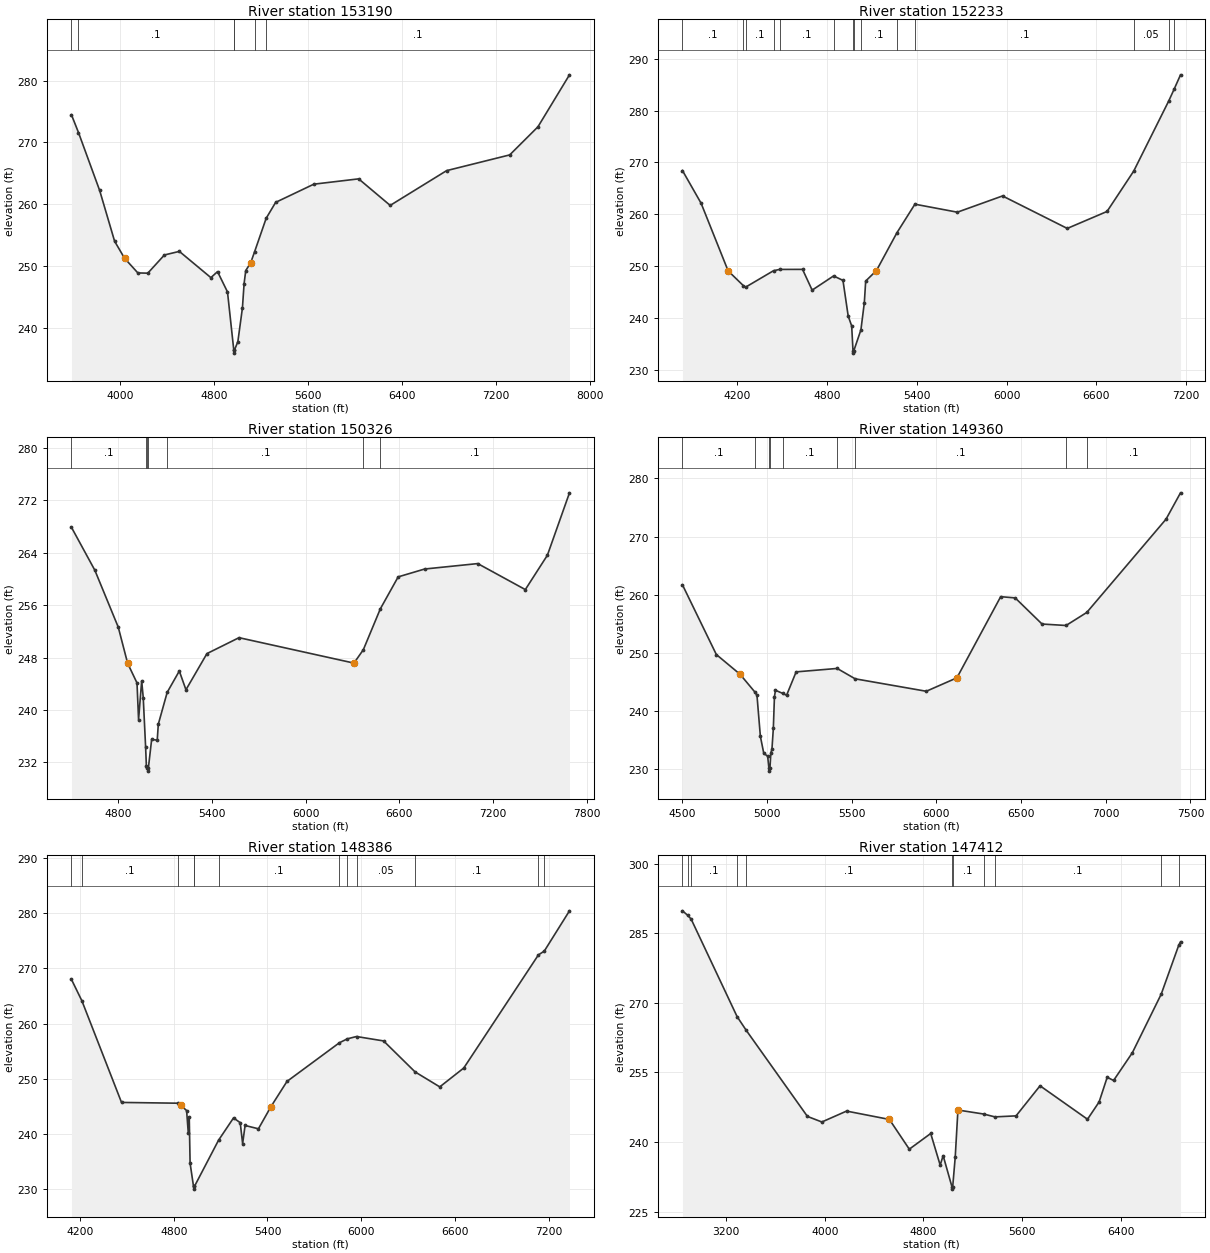
Type RM Length L Ch R = 1 ,153190  ,957,957,957
BEGIN DESCRIPTION:
LAGARTO CREEK 116.0
END DESCRIPTION:
XS GIS Cut Line= 3
      2237487.73     13196096.85      2238487.72     13195096.86
       2240487.7     13193096.87
#Sta/Elev= 30
  3585.8  274.47  3645.7   271.6  3826.2  262.23  3953.5  254.03  4038.3  251.28
  4151.5  248.91  4236.3  248.87  4377.7  251.81    4505  252.39  4773.7  248.15
  4830.3  249.12  4915.1  245.84  4968.7  236.45  4971.5  235.95  4974.7  236.45
  5003.5  237.81  5042.4  243.26  5056.6  247.19  5070.7  249.29  5113.1  250.57
    5146  252.33  5244.6  257.74  5325.3  260.31  5650.5  263.25  6032.4  264.11
  6301.1  259.82  6781.9  265.44  7319.3  267.98  7559.7  272.52  7828.4  280.92
#Mann= 6 ,-1 , 0
  3585.8     .05       0  3645.7      .1       0  4968.7     .07       0
  4974.7      .1       0    5146     .05       0  5244.6      .1       0
Bank Sta=4038.3,5113.1
XS Rating Curve= 0 ,0
Exp/Cntr=0.3,0.1

Type RM Length L Ch R = 1 ,152233  ,1907,1907,1907
BEGIN DESCRIPTION:
LAGARTO CREEK 115.0
END DESCRIPTION:
XS GIS Cut Line= 3
      2238487.72     13196746.86      2239087.72     13195746.86
      2240887.69     13194546.87
#Sta/Elev= 30
  3833.8  268.43  3958.2  262.14    4139   249.1  4241.7  246.23  4256.8  245.98
  4442.4  249.13  4483.2  249.38  4636.5  249.39  4700.7  245.39  4843.8  248.12
  4906.7  247.27  4941.7  240.39    4965  238.49  4973.7  233.75  4976.4  233.25
  4979.7  233.75  5026.7  237.73  5049.6  242.98  5058.6  247.14  5130.7  249.17
  5267.3  256.44  5387.7  261.95  5671.5  260.41  5973.5  263.54  6406.2  257.28
  6672.1  260.55  6850.7  268.34  7084.8  281.86  7119.8  284.06  7163.3  286.88
#Mann= 14 ,-1 , 0
  3833.8      .1       0  4241.7     .08       0  4256.8      .1       0
  4442.4     .08       0  4483.2      .1       0  4843.8     .12       0
  4973.7     .07       0  4979.7     .12       0  5026.7      .1       0
  5267.3     .08       0  5387.7      .1       0  6850.7     .05       0
  7084.8      .1       0  7119.8     .05       0
Bank Sta=4139,5130.7
XS Rating Curve= 0 ,0
Exp/Cntr=0.3,0.1

Type RM Length L Ch R = 1 ,150326  ,966,966,966
BEGIN DESCRIPTION:
LAGARTO CREEK 114.0
END DESCRIPTION:
XS GIS Cut Line= 3
      2238687.72     13197246.85      2239187.72     13197246.86
       2240987.7     13195246.87
#Sta/Elev= 30
    4500  267.89    4650  261.33    4800  252.64    4860  247.13    4920  244.13
    4930  238.54    4950  244.45    4960  241.88  4975.2  234.33    4980  231.51
    4987  231.17  4989.7  230.67    4993  231.17  5013.8   235.5  5049.7   235.4
  5056.4  237.82  5113.5   242.7    5191  245.95  5233.6  243.09  5368.1  248.61
  5573.6  251.04  6309.9  247.16    6370   249.2  6478.9  255.44  6593.1  260.32
  6762.8  261.52  7102.9  262.35  7407.8  258.38  7549.1  263.62  7690.7  273.15
#Mann= 7 ,-1 , 0
    4500      .1       0  4975.2     .12       0    4987     .07       0
    4993     .12       0  5113.5      .1       0    6370     .08       0
  6478.9      .1       0
Bank Sta=4860,6309.9
XS Rating Curve= 0 ,0
Exp/Cntr=0.3,0.1

Type RM Length L Ch R = 1 ,149360  ,974,974,974
BEGIN DESCRIPTION:
LAGARTO CREEK 113.0
END DESCRIPTION:
XS GIS Cut Line= 3
      2239087.72     13198046.85      2239587.72     13198046.86
      2241587.71     13196646.86
#Sta/Elev= 30
    4500   261.7    4700  249.73    4840  246.34  4928.1  243.27    4940  242.71
    4960  235.68    4980  232.78  5003.1  232.25  5010.5   230.2  5013.3   229.7
  5016.5   230.2  5022.2   232.9  5028.3  233.42  5036.6  237.04  5043.2  242.51
  5049.3  243.59  5092.2  243.05  5114.7  242.73  5171.3  246.75  5413.6  247.34
  5519.7  245.56  5939.9  243.42  6120.8  245.73  6379.3  259.67  6464.8  259.46
  6623.5  254.97  6765.3  254.72  6887.7  256.96  7355.9  272.99  7441.3  277.51
#Mann= 9 ,-1 , 0
    4500      .1       0  4928.1     .12       0  5010.5     .07       0
  5016.5     .12       0  5092.2      .1       0  5413.6     .05       0
  5519.7      .1       0  6765.3     .08       0  6887.7      .1       0
Bank Sta=4840,6120.8
XS Rating Curve= 0 ,0
Exp/Cntr=0.3,0.1

Type RM Length L Ch R = 1 ,148386  ,974,974,974
BEGIN DESCRIPTION:
LAGARTO CREEK 112.0
END DESCRIPTION:
XS GIS Cut Line= 3
      2239237.72     13199046.85      2240037.72     13198746.85
      2242037.74     13197546.84
#Sta/Elev= 30
  4145.6  268.01  4212.8   264.1    4466   245.7  4826.4  245.56  4844.2   245.2
  4882.5  244.23  4893.2  240.15  4899.4  243.03  4904.8  234.69  4926.7  230.48
  4929.4  229.98  4932.7  230.48  5086.7  238.84  5182.7  242.89  5225.5  242.03
    5241  238.22  5256.6  241.52  5342.1  240.92  5421.8  244.92  5524.8  249.51
  5860.2  256.52  5911.1  257.23  5969.6  257.65  6142.9  256.85  6344.2  251.24
  6502.4  248.52    6656  251.94  7133.6  272.45  7171.2  273.14  7332.4  280.44
#Mann= 12 ,-1 , 0
  4145.6     .08       0  4212.8      .1       0  4826.4     .12       0
  4926.7     .07       0  4932.7     .12       0  5086.7      .1       0
  5860.2     .05       0  5911.1      .1       0  5969.6     .05       0
  6344.2      .1       0  7133.6     .08       0  7171.2      .1       0
Bank Sta=4844.2,5421.8
XS Rating Curve= 0 ,0
Exp/Cntr=0.3,0.1

Type RM Length L Ch R = 1 ,147412  ,966,966,966
BEGIN DESCRIPTION:
LAGARTO CREEK 111.0
END DESCRIPTION:
XS GIS Cut Line= 3
      2238887.69     13199846.87      2240887.72     13199046.86
      2242487.72     13198046.85
#Sta/Elev= 30
  2845.9  289.81  2886.8  288.88  2916.2  288.03  3289.3     267  3363.1  264.06
  3859.7   245.5  3976.8   244.3  4177.4  246.65  4524.8  244.85  4686.3  238.44
    4860  241.82  4936.7  235.01    4961  237.04  5032.4  230.33  5035.1  229.83
  5038.4  230.33    5059  236.77  5080.8  246.88  5288.5  246.02  5381.1   245.4
  5552.5  245.62  5747.1   252.1  6132.1  244.89  6226.4  248.62  6291.9  253.93
  6343.8  253.25  6495.9  259.22  6730.2  271.85  6872.6  282.41  6886.8  283.12
#Mann= 11 ,-1 , 0
  2845.9      .1       0  2886.8     .05       0  2916.2      .1       0
  3289.3     .08       0  3363.1      .1       0  5032.4     .07       0
  5038.4      .1       0  5288.5     .05       0  5381.1      .1       0
  6730.2     .08       0  6872.6      .1       0
Bank Sta=4524.8,5080.8
XS Rating Curve= 0 ,0
Exp/Cntr=0.3,0.1

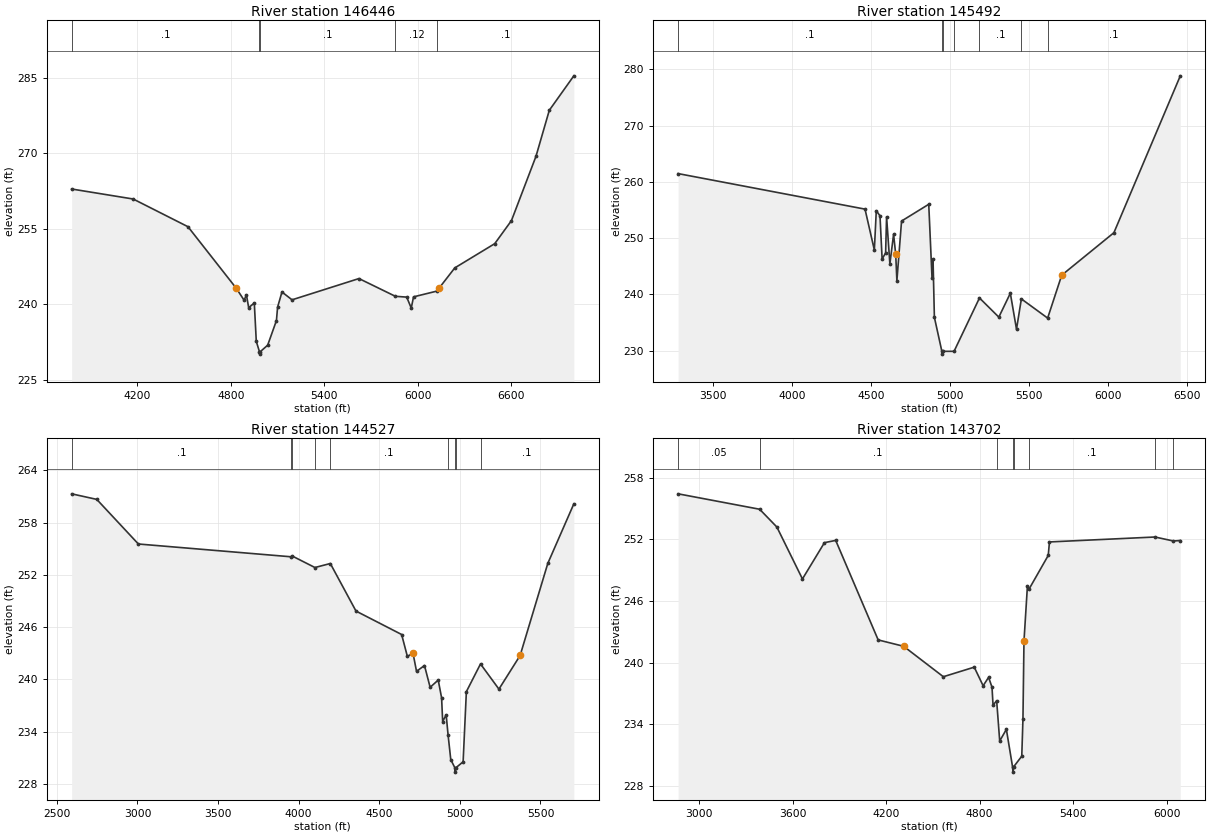
Type RM Length L Ch R = 1 ,146446  ,954,954,954
BEGIN DESCRIPTION:
LAGARTO CREEK 110.0
END DESCRIPTION:
XS GIS Cut Line= 3
       2240637.7     13200796.89      2241337.72     13199796.85
      2242537.72     13198196.85
#Sta/Elev= 30
  3779.3  262.92  4173.9  260.93  4525.3  255.42  4834.8  243.19  4885.3   240.8
  4900.2  241.87  4914.6  239.32  4950.7  240.25  4963.4  232.63  4983.5  230.58
  4986.2  230.08  4989.5  230.58  5036.5  231.86  5092.7  236.76    5100  239.41
  5128.1  242.44  5192.7  240.88  5621.9  245.11  5855.5  241.58  5928.1  241.42
  5957.3  239.24  5971.9  241.47  6124.8  242.64  6136.5  243.23  6236.5  247.23
  6492.7  252.05    6600  256.64  6757.3  269.43  6842.7  278.58    7000  285.43
#Mann= 5 ,-1 , 0
  3779.3      .1       0  4983.5     .07       0  4989.5      .1       0
  5855.5     .12       0  6124.8      .1       0
Bank Sta=4834.8,6136.5
XS Rating Curve= 0 ,0
Exp/Cntr=0.3,0.1

Type RM Length L Ch R = 1 ,145492  ,965,965,965
BEGIN DESCRIPTION:
LAGARTO CREEK 109.0
END DESCRIPTION:
XS GIS Cut Line= 3
       2241187.7     13201246.88      2242187.72     13199846.86
      2242587.71     13198446.88
#Sta/Elev= 30
  3279.5  261.47  4461.7  255.15  4520.7  247.88    4533  254.86  4556.4  253.96
  4569.9  246.26    4592  247.37  4598.1  253.79    4619  245.41  4642.4  250.68
  4655.9  247.09  4663.3  242.41  4692.8  253.03  4864.8  256.01  4885.7  242.82
  4891.9  246.23  4900.5   235.9  4947.8  229.86  4950.6  229.36  4953.8  229.86
  5024.9  229.86  5185.7  239.35  5308.1  235.94  5380.9  240.19  5419.9  233.79
  5450.7  239.18  5616.9  235.77  5705.9   243.4  6036.1  250.96    6456  278.86
#Mann= 7 ,-1 , 0
  3279.5      .1       0  4947.8     .07       0  4953.8      .1       0
  5024.9     .05       0  5185.7      .1       0  5450.7     .12       0
  5616.9      .1       0
Bank Sta=4655.9,5705.9
XS Rating Curve= 0 ,0
Exp/Cntr=0.3,0.1

Type RM Length L Ch R = 1 ,144527  ,825,825,825
BEGIN DESCRIPTION:
LAGARTO CREEK 108.0
END DESCRIPTION:
XS GIS Cut Line= 3
      2241187.73     13201346.84      2242987.72     13199746.85
      2243087.72     13199046.86
#Sta/Elev= 30
  2591.7  261.31  2747.6  260.67  3005.6  255.55  3953.9  254.08    3960  254.17
  4100.9  252.85  4196.4  253.31  4355.7  247.85  4638.8  245.16  4674.3  242.65
  4709.4  243.01  4731.2  240.93  4780.5   241.6  4815.6   239.1  4865.8  239.93
  4886.7  237.89  4893.4  235.17  4915.1  235.94  4926.7  233.67  4943.6   230.8
    4969  229.86  4971.7  229.36    4975  229.86  5020.2  230.54  5040.4   238.6
  5128.1  241.78  5242.4  238.89  5373.8  242.75  5545.5  253.32  5707.1  260.16
#Mann= 9 ,-1 , 0
  2591.7      .1       0  3953.9     .05       0    3960      .1       0
  4100.9     .05       0  4196.4      .1       0  4926.7     .12       0
    4969     .07       0    4975     .12       0  5128.1      .1       0
Bank Sta=4709.4,5373.8
XS Rating Curve= 0 ,0
Exp/Cntr=0.3,0.1

Type RM Length L Ch R = 1 ,143702  ,1109,1109,1109
BEGIN DESCRIPTION:
Mapping XS e3e68a4c
END DESCRIPTION:
XS GIS Cut Line= 4
      2241957.33     13201560.03      2242890.52     13201082.58
      2243899.64     13199910.71       2244127.5     13199324.78
#Sta/Elev= 30
  2864.8  256.43  3388.1  254.93  3498.7   253.2  3662.8  248.15    3804  251.68
  3876.3   251.9  4148.9  242.22  4312.4   241.6  4567.2  238.64  4765.5  239.57
  4822.6  237.76  4857.7  238.58  4879.6  237.62  4886.2  235.87  4909.4  236.31
    4929  232.39  4971.8  233.52  5011.6  229.86  5014.3  229.36  5017.6  229.86
  5070.6  230.91  5078.2  234.51  5084.8   242.1  5106.7  247.42    5116  247.13
  5240.6  250.44  5248.3  251.75  5925.8  252.23  6044.1  251.84  6088.2  251.89
#Mann= 8 ,-1 , 0
  2864.8     .05       0  3388.1      .1       0  4909.4     .12       0
  5011.6     .07       0  5017.6     .12       0    5116      .1       0
  5925.8     .08       0  6044.1     .05       0
Bank Sta=4312.4,5084.8
XS Rating Curve= 0 ,0
Exp/Cntr=0.3,0.1