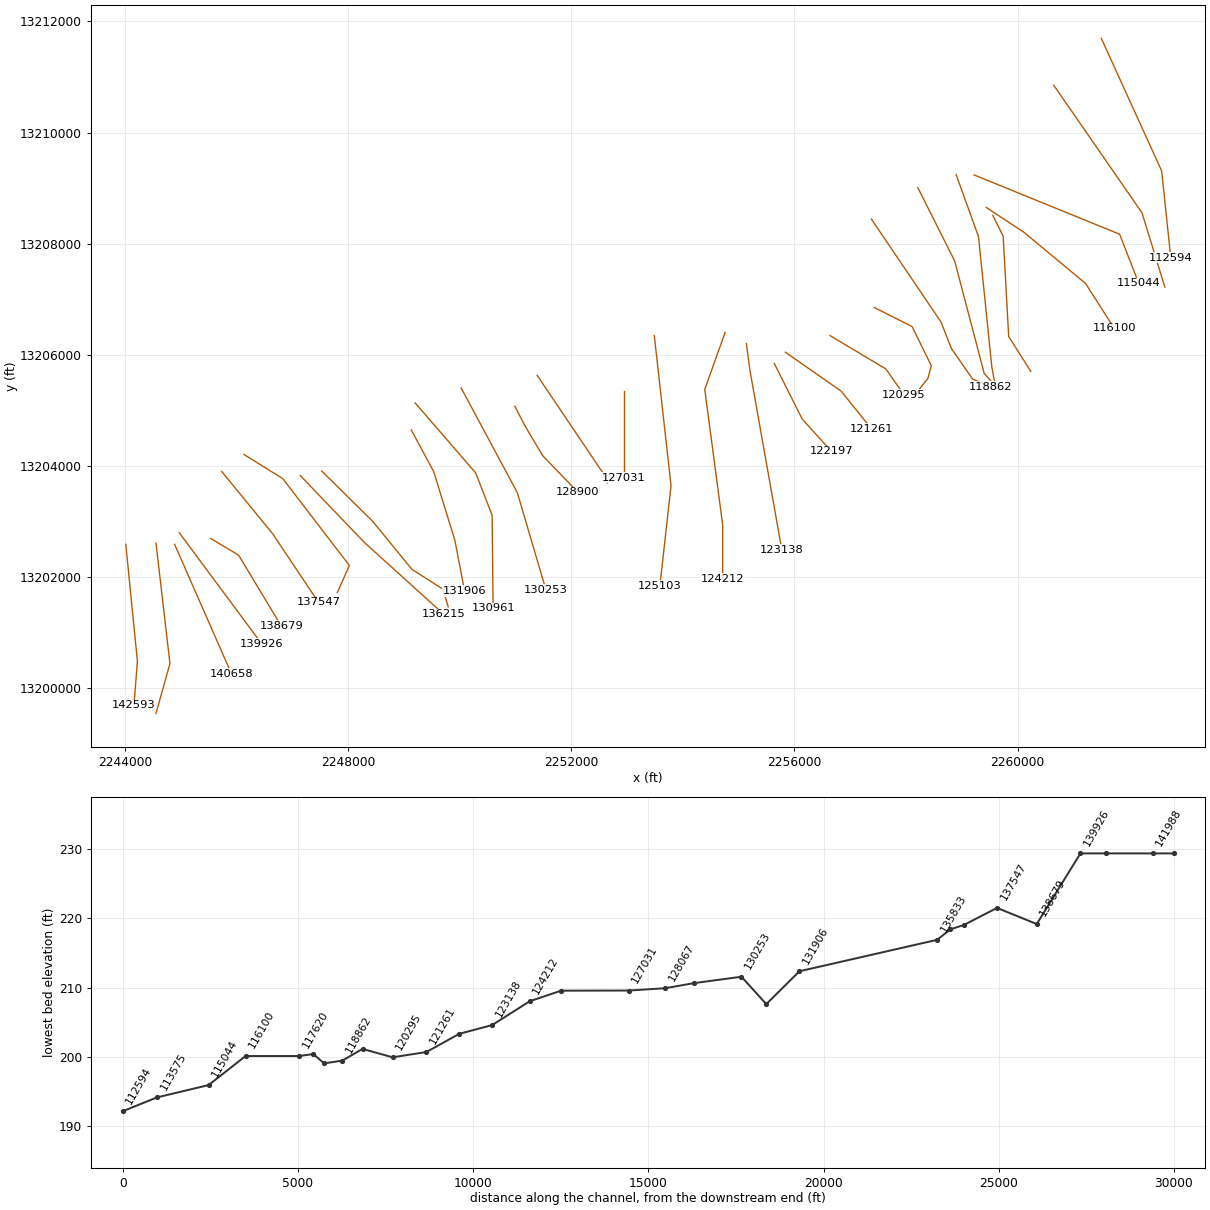
HEC-RAS study LAGARTO CREEK.prj: LAGARTO CREEK Base Level Engineering

--- LAGARTO CREEK.g01 (geometry) --- (continued)

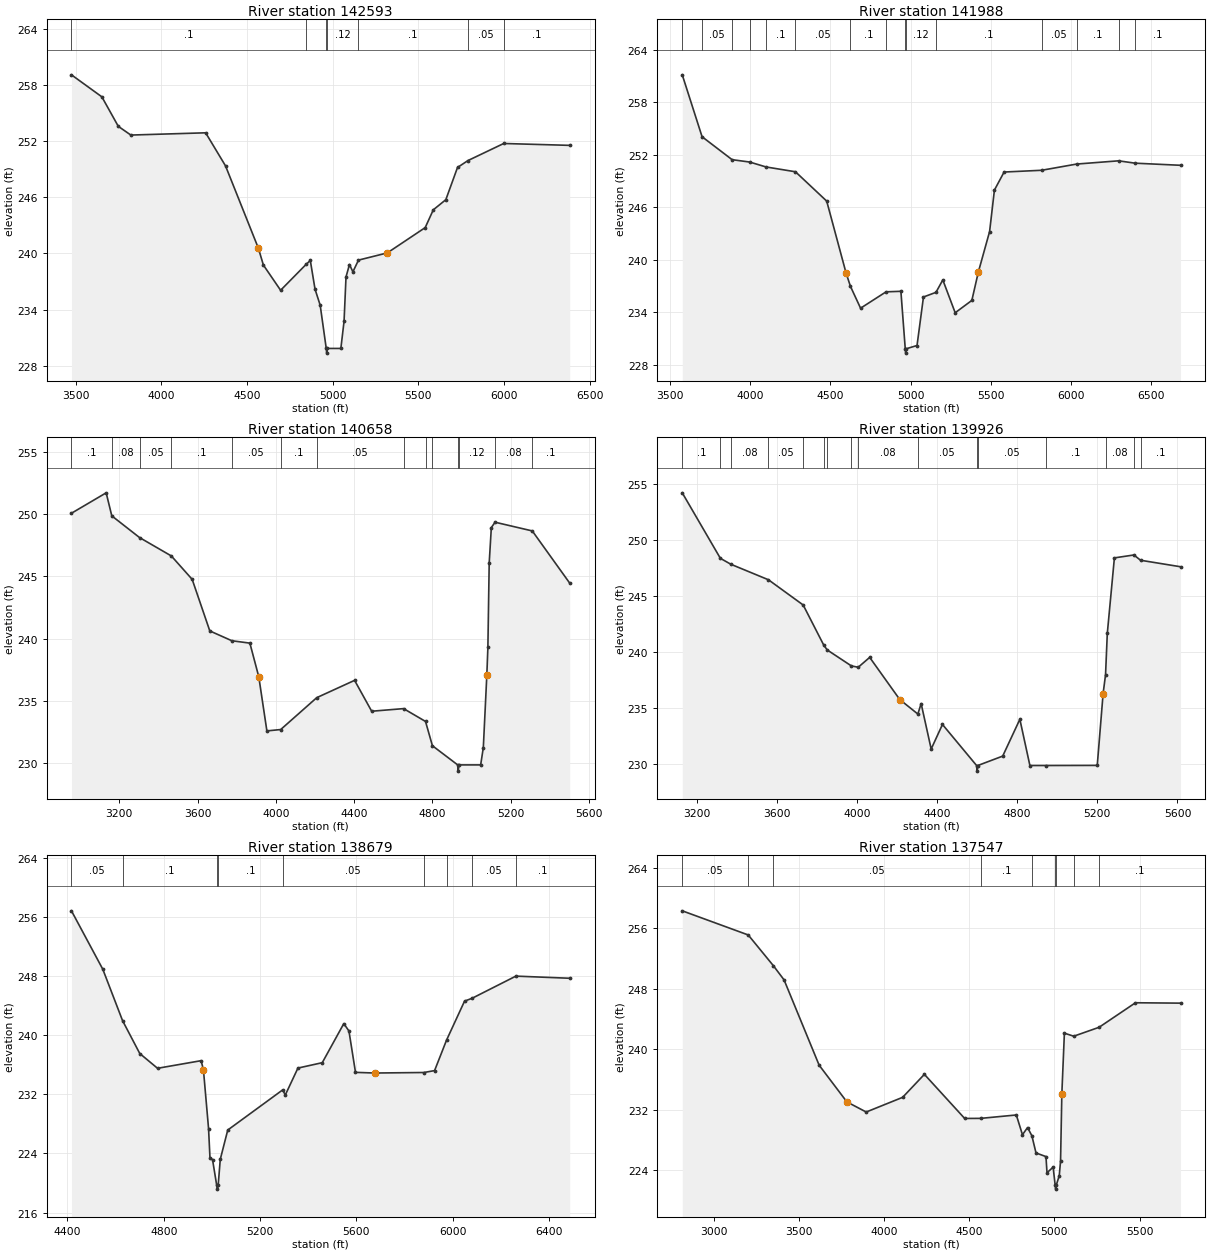
Type RM Length L Ch R = 1 ,142593  ,605,605,605
BEGIN DESCRIPTION:
Mapping XS 9d63c772
END DESCRIPTION:
XS GIS Cut Line= 3
      2244015.57     13202591.88      2244223.91     13200487.69
      2244161.41     13199696.03
#Sta/Elev= 30
  3475.6  259.07  3653.1  256.72  3749.1  253.57  3822.3  252.64    4259  252.88
    4375  249.35    4567  240.55  4596.1  238.76  4696.6  236.07  4846.8  238.86
    4870  239.25  4897.5  236.19  4927.7  234.47    4963  229.86  4965.7  229.36
    4969  229.86  5048.3  229.86    5067  232.76  5078.4  237.49  5098.5  238.82
  5118.6  238.04  5151.2  239.29  5319.6  240.06  5540.7  242.76    5588  244.66
  5661.1  245.74  5729.3  249.18  5790.6  249.92    5999  251.74  6384.2  251.54
#Mann= 7 ,-1 , 0
  3475.6      .1       0  4846.8     .12       0    4963     .07       0
    4969     .12       0  5151.2      .1       0  5790.6     .05       0
    5999      .1       0
Bank Sta=4567,5319.6
XS Rating Curve= 0 ,0
Exp/Cntr=0.3,0.1

Type RM Length L Ch R = 1 ,141988  ,1330,1330,1330
BEGIN DESCRIPTION:
LAGARTO CREEK 107.0
END DESCRIPTION:
XS GIS Cut Line= 3
      2244557.24     13202612.66      2244807.24     13200446.03
      2244557.47     13199551.03
#Sta/Elev= 30
  3574.8  261.14  3698.5  254.07    3886  251.45  3995.9  251.18  4097.7  250.62
  4281.4  250.07  4476.5  246.72  4597.3  238.51  4624.8  236.98  4687.9  234.49
  4847.1  236.36  4939.6  236.42  4966.8  229.86  4969.6  229.36  4972.8  229.86
  5040.3  230.23  5080.5  235.77  5158.5   236.3  5201.3  237.72  5278.5  233.97
  5382.5  235.38  5422.8   238.6  5493.3  243.24  5523.4  247.98  5583.8  250.04
  5818.2  250.24  6036.5  250.95  6298.6  251.32  6402.1  251.05    6685  250.81
#Mann= 15 ,-1 , 0
  3574.8      .1       0  3698.5     .05       0    3886     .08       0
  3995.9     .05       0  4097.7      .1       0  4281.4     .05       0
  4624.8      .1       0  4847.1     .12       0  4966.8     .07       0
  4972.8     .12       0  5158.5      .1       0  5818.2     .05       0
  6036.5      .1       0  6298.6     .08       0  6402.1      .1       0
Bank Sta=4597.3,5422.8
XS Rating Curve= 0 ,0
Exp/Cntr=0.3,0.1

Type RM Length L Ch R = 1 ,140658  ,732,732,732
BEGIN DESCRIPTION:
LAGARTO CREEK 106.0
END DESCRIPTION:
XS GIS Cut Line= 2
      2244890.57     13202591.87      2245910.69     13200260.15
#Sta/Elev= 30
  2955.8  250.07  3133.1  251.71  3161.9  249.86  3303.4  248.12  3466.1  246.64
  3572.5  244.76  3662.5  240.62  3775.2  239.83  3867.2  239.64  3912.8  236.93
  3954.1  232.59  4024.7   232.7  4208.8  235.26  4402.1  236.65  4489.4  234.17
  4652.4  234.38  4764.4  233.35  4799.6   231.4  4928.8  229.86  4931.5  229.36
  4934.8  229.86  5046.1  229.86  5059.7  231.25  5077.6  237.07    5083  239.29
  5089.7  246.07  5100.6  248.92  5119.6  249.35  5309.8  248.65  5500.9  244.46
#Mann= 14 ,-1 , 0
  2955.8      .1       0  3161.9     .08       0  3303.4     .05       0
  3466.1      .1       0  3775.2     .05       0  4024.7      .1       0
  4208.8     .05       0  4652.4      .1       0  4764.4     .05       0
  4799.6     .12       0  4928.8     .07       0  4934.8     .12       0
  5119.6     .08       0  5309.8      .1       0
Bank Sta=3912.8,5077.6
XS Rating Curve= 0 ,0
Exp/Cntr=0.3,0.1

Type RM Length L Ch R = 1 ,139926  ,1247,1247,1247
BEGIN DESCRIPTION:
LAGARTO CREEK 105.0
END DESCRIPTION:
XS GIS Cut Line= 2
      2244973.92     13202800.17      2246452.28     13200801.26
#Sta/Elev= 30
  3128.8  254.17    3319  248.33  3371.5   247.8  3558.8  246.42  3732.2  244.17
  3834.9  240.59  3852.4  240.16  3972.7  238.74  4006.9  238.62    4064   239.5
  4214.3  235.74  4304.4  234.45  4320.8  235.38  4370.9  231.33  4427.2  233.52
  4597.5  229.86  4600.3  229.36  4603.5  229.86  4727.8   230.7  4813.4  233.98
  4863.5  229.86  4944.5  229.86  5199.6  229.87  5228.8  236.27    5241  237.96
  5249.7  241.63  5285.1  248.37  5382.5  248.63  5415.5  248.16    5615  247.58
#Mann= 16 ,-1 , 0
  3128.8      .1       0    3319     .05       0  3371.5     .08       0
  3558.8     .05       0  3732.2     .08       0  3834.9     .05       0
  3852.4     .08       0  3972.7     .05       0  4006.9     .08       0
  4304.4     .05       0  4597.5     .07       0  4603.5     .05       0
  4944.5      .1       0    5241     .08       0  5382.5     .05       0
  5415.5      .1       0
Bank Sta=4214.3,5228.8
XS Rating Curve= 0 ,0
Exp/Cntr=0.3,0.1

Type RM Length L Ch R = 1 ,138679  ,1132,1132,1132
BEGIN DESCRIPTION:
LAGARTO CREEK 104.0
END DESCRIPTION:
XS GIS Cut Line= 3
      2245537.72     13202696.86      2246037.72     13202396.85
      2246802.47     13201122.28
#Sta/Elev= 30
  4416.9  256.85  4547.1  248.94  4629.2  241.98  4700.7  237.53  4774.5  235.53
  4955.3  236.56    4965  235.36  4986.4  227.36  4992.2  223.44  5002.9  223.17
  5020.3  219.67  5023.1  219.17  5026.3  219.67    5035   223.2  5066.1  227.17
    5294   232.6  5305.2  231.92  5357.6  235.56  5458.7  236.29  5548.1  241.58
  5569.5  240.58  5596.7  234.98  5676.4  234.89  5880.9  234.96  5925.2  235.22
  5975.1  239.36  6049.6  244.62  6081.6  245.02  6262.9  248.01  6486.4  247.72
#Mann= 9 ,-1 , 0
  4416.9     .05       0  4629.2      .1       0  5020.3     .07       0
  5026.3      .1       0    5294     .05       0  5880.9      .1       0
  5975.1     .08       0  6081.6     .05       0  6262.9      .1       0
Bank Sta=4965,5676.4
XS Rating Curve= 0 ,0
Exp/Cntr=0.3,0.1

Type RM Length L Ch R = 1 ,137547  ,946,946,946
BEGIN DESCRIPTION:
LAGARTO CREEK 103.0
END DESCRIPTION:
XS GIS Cut Line= 3
      2245733.38      13203903.8      2246644.87     13202786.14
      2247468.64     13201550.47
#Sta/Elev= 30
  2813.5  258.28  3201.1  255.09  3349.1  251.02  3411.7  249.15  3617.7  237.88
  3780.7  233.03  3894.2  231.69  4108.2  233.63    4236  236.67  4472.7  230.84
  4566.5  230.85  4776.2   231.3  4812.2  228.69  4842.3  229.64  4867.8  228.54
  4891.8  226.28  4950.4   225.8  4956.4  223.66  4992.5  224.41  5004.5     222
  5007.3   221.5  5010.5     222  5028.5  223.28  5036.1  225.21  5043.6  234.07
  5058.6  242.11  5113.7  241.71  5262.6  242.89  5476.2  246.13  5740.8  246.08
#Mann= 9 ,-1 , 0
  2813.5     .05       0  3201.1     .08       0  3349.1     .05       0
  4566.5      .1       0  4867.8     .12       0  5004.5     .07       0
  5010.5     .12       0  5113.7     .08       0  5262.6      .1       0
Bank Sta=3780.7,5043.6
XS Rating Curve= 0 ,0
Exp/Cntr=0.3,0.1

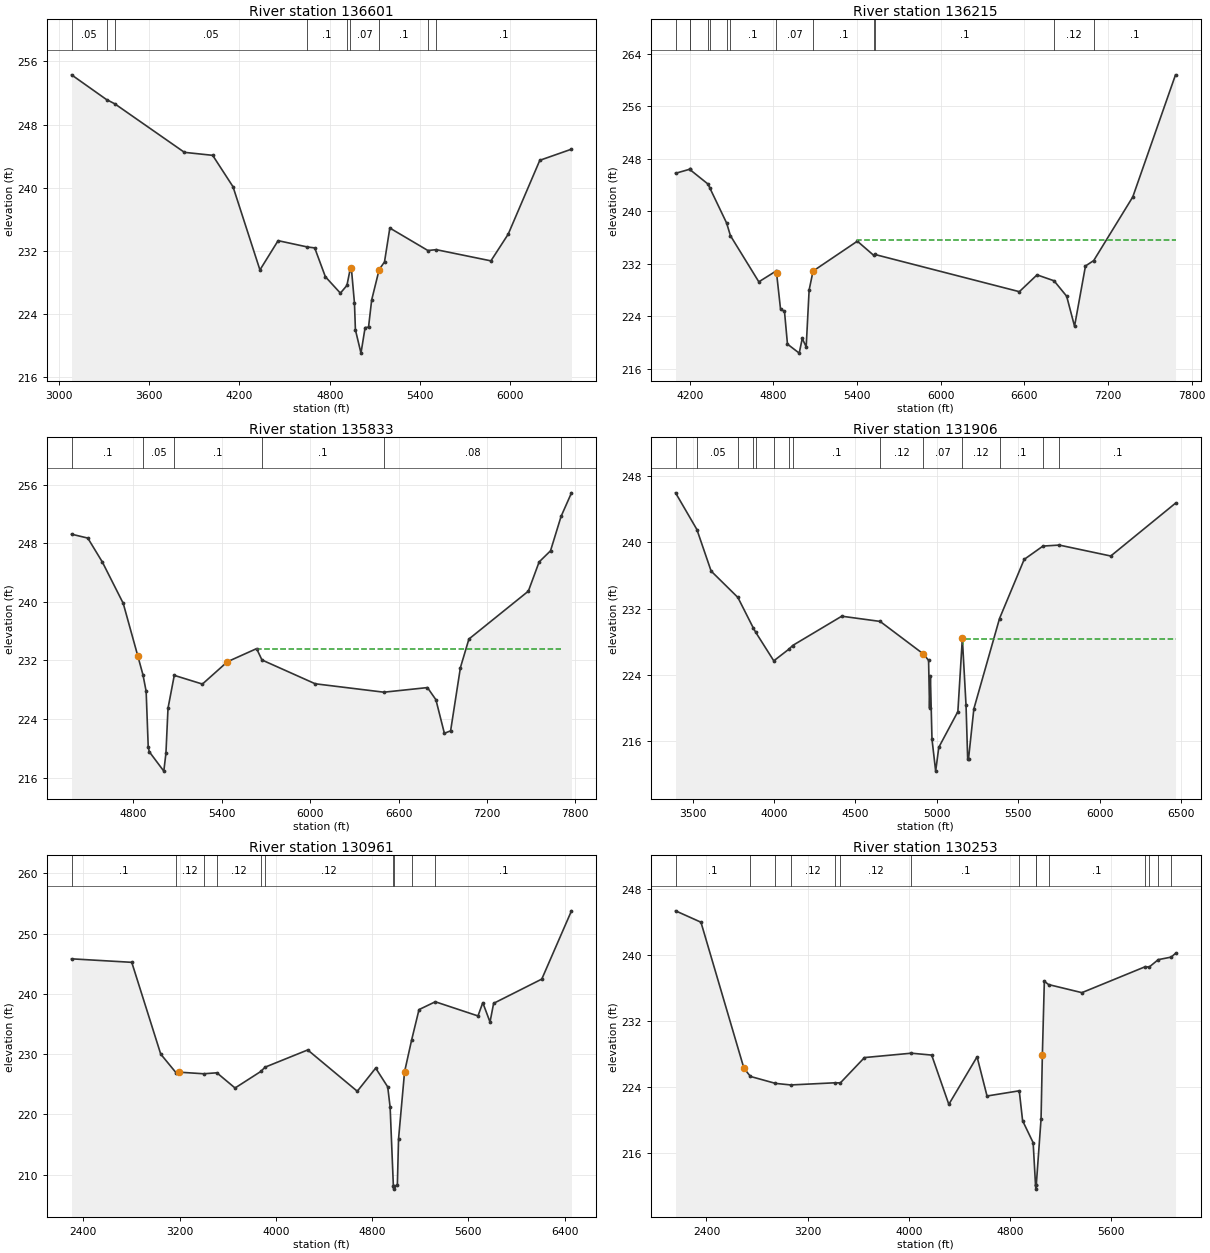
Type RM Length L Ch R = 1 ,136601  ,386,386,386
BEGIN DESCRIPTION:
LAGARTO CREEK 102.0
END DESCRIPTION:
XS GIS Cut Line= 4
      2246134.87      13204207.6      2246829.33     13203773.56
       2248022.9     13202211.06      2247805.89     13201722.77
#Sta/Elev= 30
  3085.9   254.3  3318.5  251.16  3372.9  250.63  3835.3  244.48    4023   244.1
  4158.1  240.12  4336.8  229.58  4457.4  233.29  4651.7  232.49  4700.5  232.37
  4771.2  228.72  4870.9  226.64  4914.4  227.62  4935.3  229.62  4943.6  229.84
  4964.4  225.38  4970.7  221.99  5007.7  219.04  5035.1  222.28  5057.8  222.33
  5078.7  225.78  5128.5  229.63  5163.9   230.6  5199.2  234.89  5452.1  232.04
    5507  232.15  5870.4  230.73  5985.1  234.11    6195  243.47  6405.4  244.88
#Mann= 9 ,-1 , 0
  3085.9     .05       0  3318.5     .08       0  3372.9     .05       0
  4651.7      .1       0  4914.4     .12       0  4935.3     .07       0
  5128.5      .1       0  5452.1     .05       0    5507      .1       0
Bank Sta=4943.6,5128.5
XS Rating Curve= 0 ,0
Exp/Cntr=0.3,0.1

Type RM Length L Ch R = 1 ,136215  ,382,382,382
BEGIN DESCRIPTION:
LAGARTO CREEK 101.0
END DESCRIPTION:
XS GIS Cut Line= 3
      2247143.98     13203827.83      2248294.17     13202623.38
      2249715.63     13201332.14
#Sta/Elev= 30
  4098.4   245.8  4198.5  246.41  4199.1  246.41  4331.9  244.15  4345.3  243.52
  4464.8  238.22    4492   236.3  4695.7  229.27  4816.2  230.87  4823.1  230.57
  4851.4  225.12  4879.7  224.78  4901.1  219.78  4985.5  218.41  5007.1  220.64
  5035.4  219.37  5056.5  228.03  5084.8  230.91 5402.27  235.46  5518.7  233.32
  5527.4  233.44  6564.1  227.77  6691.1  230.33    6813  229.43  6903.5  227.08
  6960.1   222.5  7038.5  231.68  7097.6  232.51  7377.7   242.2  7684.2   260.8
#Mann= 13 ,-1 , 0
  4098.4      .1       0  4198.5     .08       0  4199.1      .1       0
  4331.9     .05       0  4345.3      .1       0  4464.8     .08       0
    4492      .1       0  4816.2     .07       0  5084.8      .1       0
  5518.7     .05       0  5527.4      .1       0    6813     .12       0
  7097.6      .1       0
#XS Ineff= 2 , 0
                            5400          235.61
Permanent Ineff=
       F       F
Bank Sta=4823.1,5084.8
XS Rating Curve= 0 ,0
Exp/Cntr=0.3,0.1

Type RM Length L Ch R = 1 ,135833  ,3927,3927,3927
BEGIN DESCRIPTION:
LAGARTO CREEK 100.0
END DESCRIPTION:
XS GIS Cut Line= 5
      2247526.54     13203911.63      2248442.11     13203003.74
      2249144.78     13202141.27      2249697.78     13201786.13
      2249794.16     13201466.53
#Sta/Elev= 30
  4380.6  249.25  4490.9  248.72  4589.9  245.44  4731.3  239.81  4830.3  232.62
  4865.6  230.02  4886.9  227.79    4901  220.22  4908.1  219.54  5006.8  216.89
  5021.2  219.33  5035.3  225.48  5077.8  229.97  5268.7  228.78  5438.4  231.83
  5636.4  233.62    5673  232.07  6034.3  228.82  6500.3  227.67  6795.9   228.3
  6853.4  226.64  6910.8  222.06  6953.1  222.39  7019.8  231.04  7077.3  234.93
  7480.7  241.47  7553.8  245.46  7631.1  246.98  7702.8  251.68  7773.5   254.9
#Mann= 6 ,-1 , 0
  4380.6      .1       0  4865.6     .05       0  5077.8      .1       0
    5673      .1       0  6500.3     .08       0  7702.8      .1       0
#XS Ineff= 1 ,-1
 5631.98    7700 233.598
Permanent Ineff=
       F
Bank Sta=4830.3,5438.4
XS Rating Curve= 0 ,0
Exp/Cntr=0.3,0.1

Type RM Length L Ch R = 1 ,131906  ,945,945,945
BEGIN DESCRIPTION:
LAGARTO CREEK 99.0
END DESCRIPTION:
XS GIS Cut Line= 4
      2249132.46     13204649.46      2249533.95     13203900.74
      2249913.72     13202663.76      2250087.33     13201752.29
#Sta/Elev= 30
  3395.5  245.97  3526.6  241.54  3614.1  236.52  3778.3  233.34  3873.4  229.64
  3888.6  229.11    3999  225.68  4093.3  227.11  4114.7  227.53  4416.5  231.07
  4652.2  230.44  4917.9  226.51    4950  225.74  4955.8  219.99  4961.1  223.83
  4970.9  216.22  4993.5  212.36  5012.8  215.24  5129.9  219.55  5157.4  228.38
  5180.1  220.29  5190.1  213.85  5195.4  213.85  5228.1  219.88  5385.8  230.79
  5537.3  237.93  5652.8  239.54  5752.8  239.66  6069.2  238.34  6466.9  244.72
#Mann= 14 ,-1 , 0
  3395.5      .1       0  3526.6     .05       0  3778.3     .08       0
  3873.4     .05       0  3888.6     .08       0    3999     .12       0
  4093.3     .08       0  4114.7      .1       0  4652.2     .12       0
  4917.9     .07       0  5157.4     .12       0  5385.8      .1       0
  5652.8     .08       0  5752.8      .1       0
#XS Ineff= 2 , 0
                         5159.66          228.37
Permanent Ineff=
       F       F
Bank Sta=4917.9,5157.4
XS Rating Curve= 0 ,0
Exp/Cntr=0.3,0.1

Type RM Length L Ch R = 1 ,130961  ,708,708,708
BEGIN DESCRIPTION:
Mapping XS 7836c813
END DESCRIPTION:
XS GIS Cut Line= 4
      2249201.18     13205135.86      2250286.27     13203877.15
      2250581.41     13203113.26      2250598.75     13201439.93
#Sta/Elev= 30
  2302.8  245.81  2803.2  245.23  3043.9  230.01  3170.4  226.94  3193.1  227.02
  3400.1  226.75  3510.4  226.91  3661.4  224.39    3876  227.14  3910.4  227.84
  4265.3   230.7  4677.1  223.85    4830  227.69    4930  224.57    4950  221.21
    4977  208.12  4979.7  207.62    4983  208.12    5010  208.25    5020  215.96
    5070  227.07  5127.7  232.27    5190  237.39  5325.3  238.69    5680  236.34
    5720  238.54    5780  235.33    5810  238.43  6210.1  242.45    6457  253.77
#Mann= 10 ,-1 , 0
  2302.8      .1       0  3170.4     .12       0  3400.1     .08       0
  3510.4     .12       0    3876      .1       0  3910.4     .12       0
    4977     .07       0    4983     .12       0  5127.7     .08       0
  5325.3      .1       0
Bank Sta=3193.1,5070
XS Rating Curve= 0 ,0
Exp/Cntr=0.3,0.1

Type RM Length L Ch R = 1 ,130253  ,1353,1353,1353
BEGIN DESCRIPTION:
LAGARTO CREEK 98.0
END DESCRIPTION:
XS GIS Cut Line= 3
      2250025.85     13205404.94       2251032.8     13203521.25
      2251544.94      13201776.5
#Sta/Elev= 30
  2155.6  245.31  2356.5  243.93  2696.3  226.23  2748.1  225.23  2945.8  224.39
  3066.6   224.2  3413.8  224.46  3459.2  224.45  3649.8  227.52  4020.4  228.05
  4181.4  227.82    4317  221.85  4540.4  227.61  4619.2  222.86  4874.1  223.49
  4900.6  219.86    4984   217.2  5002.7  212.07  5005.4  211.57  5008.7  212.07
  5046.5  220.07  5056.9  227.86  5072.5  236.77  5106.1  236.37  5369.6  235.39
  5871.3  238.54  5901.3  238.49  5973.4  239.39  6075.5   239.7  6109.9  240.15
#Mann= 15 ,-1 , 0
  2155.6      .1       0  2748.1     .12       0  2945.8     .05       0
  3066.6     .12       0  3413.8      .1       0  3459.2     .12       0
  4020.4      .1       0  4874.1     .12       0  5002.7     .07       0
  5008.7     .12       0  5106.1      .1       0  5871.3     .05       0
  5901.3      .1       0  5973.4     .05       0  6075.5      .1       0
Bank Sta=2696.3,5056.9
XS Rating Curve= 0 ,0
Exp/Cntr=0.3,0.1

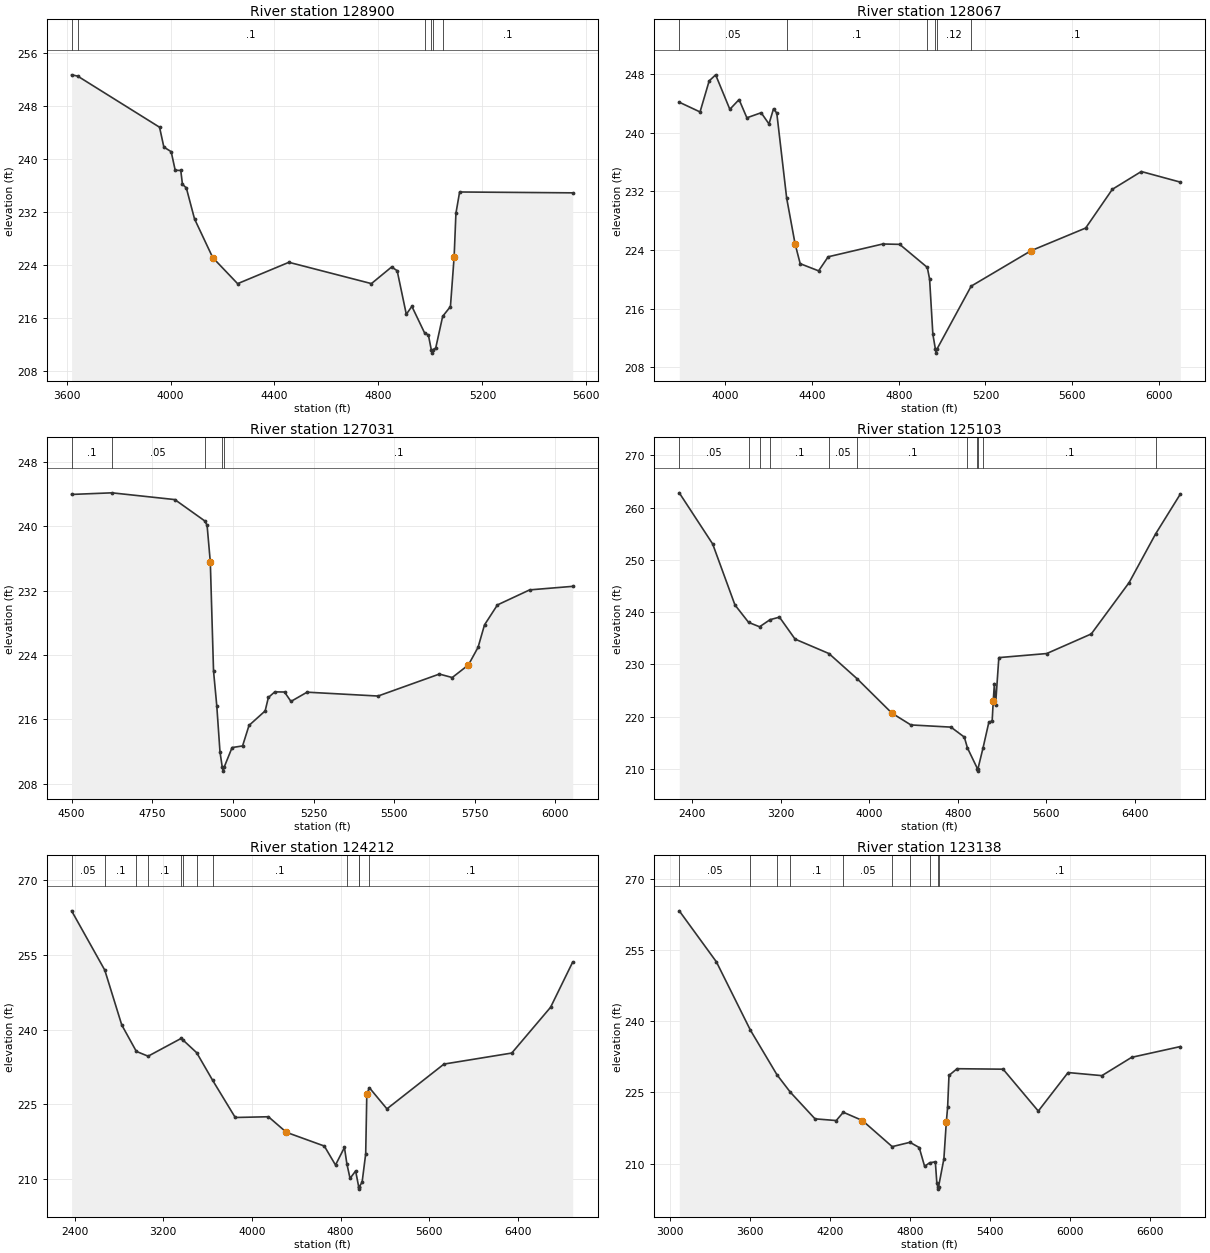
Type RM Length L Ch R = 1 ,128900  ,833,833,833
BEGIN DESCRIPTION:
LAGARTO CREEK 97.0
END DESCRIPTION:
XS GIS Cut Line= 4
      2250989.38      13205075.1      2251163.01     13204736.53
      2251484.19     13204189.65      2252116.92     13203530.92
#Sta/Elev= 30
  3619.3  252.72  3642.5  252.53  3957.7   244.8  3974.3   241.8  4002.5   241.1
  4017.9   238.3  4039.4  238.26  4045.8  236.18  4060.8  235.62  4092.2  230.95
  4162.4  225.09  4258.1  221.15  4455.4  224.38  4772.9  221.16  4850.6  223.67
    4872  223.11  4907.2  216.52  4928.6  217.72  4977.7  213.69  4992.1   213.4
  5003.3  211.15    5006  210.65  5009.3  211.15  5020.4  211.43  5047.1  216.21
    5077  217.69  5091.2   225.2  5098.1  231.79  5112.3  235.01  5547.4  234.88
#Mann= 6 ,-1 , 0
  3619.3     .08       0  3642.5      .1       0  4977.7     .12       0
  5003.3     .07       0  5009.3     .12       0  5047.1      .1       0
Bank Sta=4162.4,5091.2
XS Rating Curve= 0 ,0
Exp/Cntr=0.3,0.1

Type RM Length L Ch R = 1 ,128067  ,1036,1036,1036
BEGIN DESCRIPTION:
LAGARTO CREEK 96.0
END DESCRIPTION:
XS GIS Cut Line= 3
      2251388.68     13205630.66      2252577.94     13203859.79
      2252647.38     13203694.86
#Sta/Elev= 30
  3787.3  244.19  3883.2  242.86  3925.3   247.1  3955.2  247.93  4020.7  243.22
  4063.3  244.55  4099.3  242.06  4165.2  242.75  4201.3  241.22  4222.3   243.3
  4237.3   242.7  4282.9  231.08  4321.9  224.81  4345.3  222.13  4430.3  221.15
  4474.3  223.07  4726.3  224.82  4804.4  224.77  4931.8  221.62  4942.4  220.02
  4957.4   212.5  4969.4  210.41  4972.1  209.91  4975.4  210.41  5134.2  219.06
  5410.4   223.9  5662.5     227  5785.5  232.29  5919.2  234.72  6099.4  233.27
#Mann= 6 ,-1 , 0
  3787.3     .05       0  4282.9      .1       0  4931.8     .12       0
  4969.4     .07       0  4975.4     .12       0  5134.2      .1       0
Bank Sta=4321.9,5410.4
XS Rating Curve= 0 ,0
Exp/Cntr=0.3,0.1

Type RM Length L Ch R = 1 ,127031  ,1928,1928,1928
BEGIN DESCRIPTION:
LAGARTO CREEK 95.0
END DESCRIPTION:
XS GIS Cut Line= 3
      2252937.72     13205346.85      2252937.72     13204846.85
      2252937.72     13203793.45
#Sta/Elev= 30
    4500  243.96  4625.1  244.16    4820  243.32  4912.1  240.69    4920  240.14
    4930  235.57    4940  222.02    4950  217.73    4960  211.98    4967  210.08
  4969.8  209.58    4973  210.08  4997.5  212.51    5030  212.71    5050  215.26
    5100  217.06    5110  218.73    5130  219.43    5160  219.41    5180  218.24
    5230  219.39    5450  218.91    5640  221.64    5680  221.21    5730  222.77
    5760  224.96    5780  227.75    5820  230.23    5920   232.1  6053.4  232.54
#Mann= 5 ,-1 , 0
    4500      .1       0  4625.1     .05       0  4912.1      .1       0
    4967     .07       0    4973      .1       0
Bank Sta=4930,5730
XS Rating Curve= 0 ,0
Exp/Cntr=0.3,0.1

Type RM Length L Ch R = 1 ,125103  ,891,891,891
BEGIN DESCRIPTION:
LAGARTO CREEK 94.0
END DESCRIPTION:
XS GIS Cut Line= 3
      2253487.72     13206346.84      2253787.72     13203646.86
      2253587.72     13201846.83
#Sta/Elev= 30
  2283.4  262.81  2585.2  253.03  2786.5  241.36    2910  238.02  3009.1  237.18
  3103.8  238.54  3188.9  239.02  3329.8  234.82  3635.7  232.06  3892.4   227.2
  4205.1  220.65  4376.2   218.4  4738.4  217.98  4859.1  216.07  4887.3     214
  4976.9  210.06  4979.6  209.56  4982.9  210.06  5028.6  214.04  5080.5  218.89
  5110.7  219.19  5120.7  223.06  5130.8  226.31  5140.9  222.12    5171  231.28
  5603.7  232.06  6006.2  235.81  6348.2  245.64  6587.1  254.94  6811.1  262.58
#Mann= 11 ,-1 , 0
  2283.4     .05       0    2910     .08       0  3009.1     .05       0
  3103.8      .1       0  3635.7     .05       0  3892.4      .1       0
  4887.3     .12       0  4976.9     .07       0  4982.9     .12       0
  5028.6      .1       0  6587.1     .05       0
Bank Sta=4205.1,5120.7
XS Rating Curve= 0 ,0
Exp/Cntr=0.3,0.1

Type RM Length L Ch R = 1 ,124212  ,1074,1074,1074
BEGIN DESCRIPTION:
LAGARTO CREEK 93.0
END DESCRIPTION:
XS GIS Cut Line= 4
      2254756.76     13206403.19      2254392.18     13205378.89
      2254713.36     13202939.65      2254713.36      13201967.4
#Sta/Elev= 30
    2373  263.79  2672.3  251.91  2825.5  240.92    2957  235.63  3063.1  234.67
  3362.7  238.25  3381.1  237.84  3501.2  235.37  3644.9  229.85    3849  222.39
  4148.2  222.54  4310.8  219.42  4652.5  216.67  4753.4  212.87    4834  216.39
  4855.6  213.16  4884.5  210.19  4934.9  211.68  4962.2  208.54  4964.9  208.04
  4968.2  208.54  4993.4  209.43  5025.7  215.11  5035.8  227.12  5058.8  228.35
  5217.3  224.12  5731.7  233.09  6343.3   235.3  6693.3  244.47  6892.8  253.53
#Mann= 12 ,-1 , 0
    2373     .05       0  2672.3      .1       0    2957     .05       0
  3063.1      .1       0  3362.7     .08       0  3381.1      .1       0
  3501.2     .05       0  3644.9      .1       0  4855.6     .12       0
  4962.2     .07       0  4968.2     .12       0  5058.8      .1       0
Bank Sta=4310.8,5035.8
XS Rating Curve= 0 ,0
Exp/Cntr=0.3,0.1

Type RM Length L Ch R = 1 ,123138  ,941,941,941
BEGIN DESCRIPTION:
LAGARTO CREEK 92.0
END DESCRIPTION:
XS GIS Cut Line= 3
      2255138.71      13206203.5      2255199.47     13205734.79
      2255772.39     13202496.92
#Sta/Elev= 30
  3067.1  263.28  3346.1  252.51  3600.7  238.14  3800.3  228.72  3900.1  225.06
    4086  219.42  4245.3  219.06  4298.2  220.81  4441.5  219.07  4665.3  213.56
  4798.5  214.47    4868  213.37  4908.6   209.4  4945.6  210.15    4989  210.36
    5000  205.98  5007.2   205.1  5009.9   204.6  5013.2   205.1  5053.2     211
  5071.1  218.65  5081.2  221.87  5091.4  228.58  5152.3  229.99  5497.6  229.89
  5761.7  221.06  5985.1  229.18    6239  228.53  6462.4  232.39  6827.9  234.66
#Mann= 10 ,-1 , 0
  3067.1     .05       0  3600.7      .1       0  3800.3     .08       0
  3900.1      .1       0  4298.2     .05       0  4665.3      .1       0
  4798.5     .12       0  4945.6      .1       0  5007.2     .07       0
  5013.2      .1       0
Bank Sta=4441.5,5071.1
XS Rating Curve= 0 ,0
Exp/Cntr=0.3,0.1

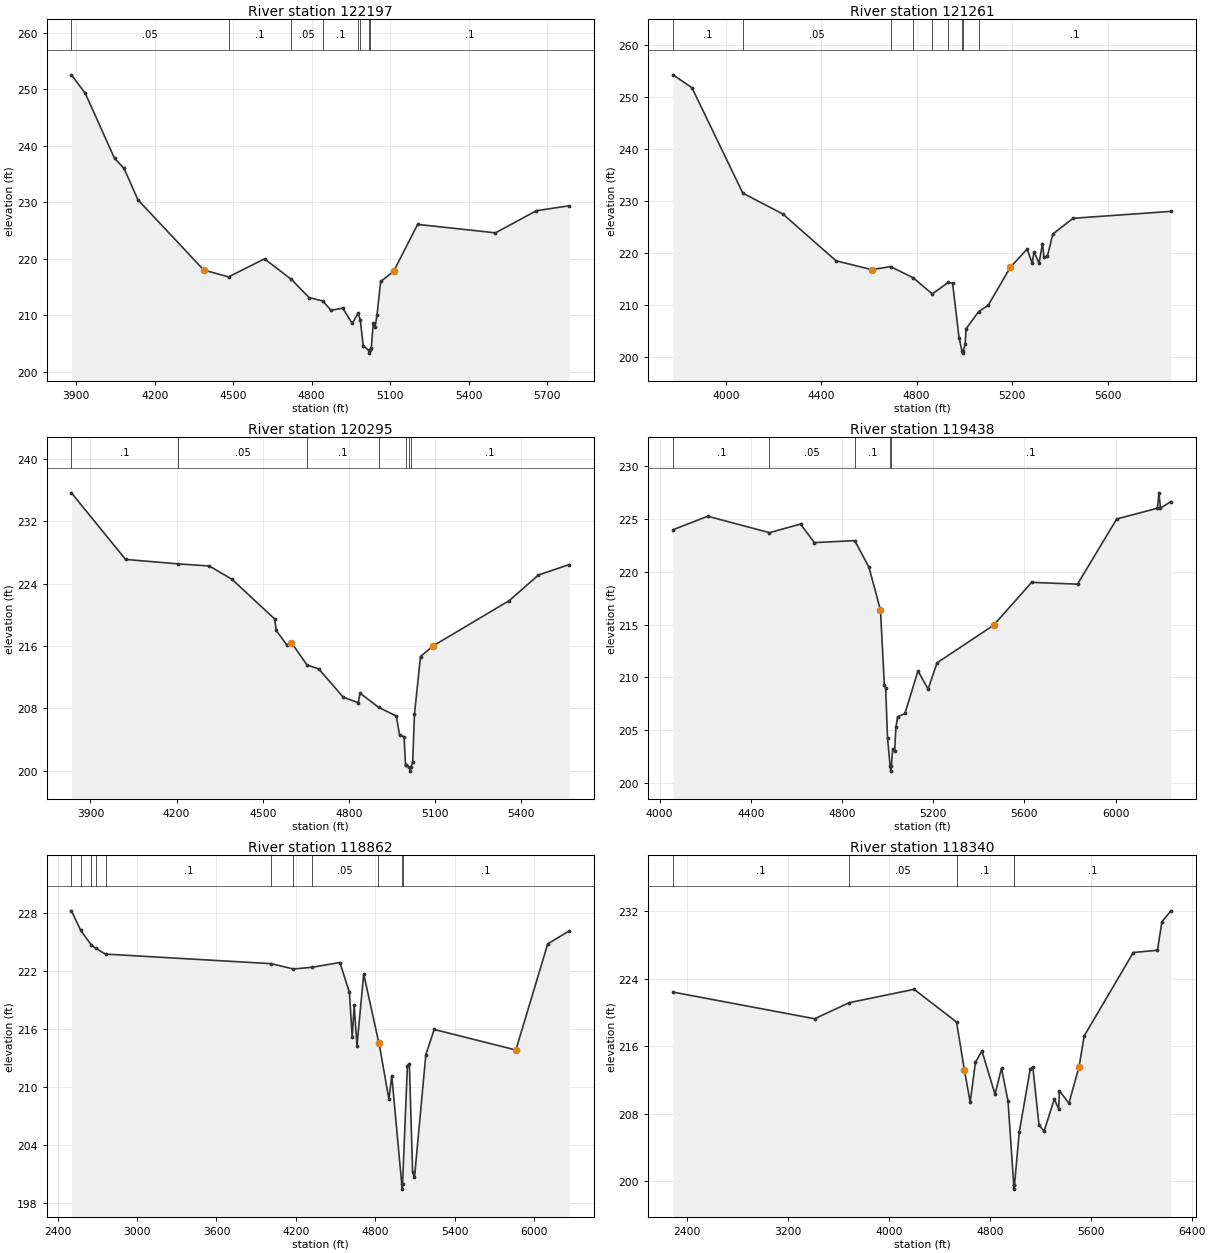
Type RM Length L Ch R = 1 ,122197  ,936,936,936
BEGIN DESCRIPTION:
LAGARTO CREEK 91.0
END DESCRIPTION:
XS GIS Cut Line= 3
      2255637.74     13205846.82      2256137.72     13204846.85
      2256662.52     13204263.74
#Sta/Elev= 30
    3882  252.58  3935.1  249.29  4046.9  237.79  4083.2  236.01  4136.3  230.45
  4387.9  218.03  4482.4  216.82  4619.9  220.02    4723  216.36  4790.4  213.15
  4842.1  212.57  4874.2  210.91  4918.9  211.29  4955.3  208.59  4977.8  210.41
  4985.9   209.2  4997.2  204.63  5018.3  203.83  5021.1  203.33  5024.3  203.83
    5028  204.16  5035.5  208.64  5042.2  207.87  5049.7  210.05  5063.9  216.01
  5113.2  217.79  5205.2  226.11  5502.6  224.62  5658.9  228.53  5784.5  229.41
#Mann= 8 ,-1 , 0
    3882     .05       0  4482.4      .1       0    4723     .05       0
  4842.1      .1       0  4977.8     .12       0  4985.9      .1       0
  5018.3     .07       0  5024.3      .1       0
Bank Sta=4387.9,5113.2
XS Rating Curve= 0 ,0
Exp/Cntr=0.3,0.1

Type RM Length L Ch R = 1 ,121261  ,966,966,966
BEGIN DESCRIPTION:
LAGARTO CREEK 90.0
END DESCRIPTION:
XS GIS Cut Line= 3
      2255837.68     13206046.88      2256837.72     13205346.85
      2257378.39     13204671.01
#Sta/Elev= 30
  3779.3  254.25  3858.3  251.78  4071.8  231.48  4239.3  227.48  4462.5  218.47
  4611.6  216.77  4691.2  217.36  4785.2  215.21  4865.8   212.1    4933  214.33
  4950.7  214.14  4977.8  203.69  4989.6  201.21  4992.3  200.71  4995.6  201.21
  5003.2  202.42  5007.2  205.39  5059.8  208.69    5100  209.91  5192.1  217.19
  5263.3  220.74  5284.1  218.02  5292.1  220.22    5313  217.98  5327.4  221.79
  5333.8  219.13  5348.2  219.38  5370.6  223.62  5455.4  226.65  5865.5  227.98
#Mann= 9 ,-1 , 0
  3779.3      .1       0  4071.8     .05       0  4691.2      .1       0
  4785.2     .05       0  4865.8      .1       0    4933     .12       0
  4989.6     .07       0  4995.6     .12       0  5059.8      .1       0
Bank Sta=4611.6,5192.1
XS Rating Curve= 0 ,0
Exp/Cntr=0.3,0.1

Type RM Length L Ch R = 1 ,120295  ,857,857,857
BEGIN DESCRIPTION:
LAGARTO CREEK 89.0
END DESCRIPTION:
XS GIS Cut Line= 3
      2256637.71     13206346.86      2257637.72     13205746.86
      2257962.99     13205282.19
#Sta/Elev= 30
  3833.8  235.64  4022.3   227.1  4205.3  226.53  4313.9  226.26  4393.6  224.53
  4541.3  219.47  4547.1  217.99  4584.1  216.11  4599.6  216.43  4654.3  213.56
  4694.8  213.07  4780.4  209.43  4832.8  208.73  4838.7  209.95  4904.5  208.11
    4965  207.02  4976.7  204.52  4992.2  204.37  4997.1  200.72  4998.7  200.72
  5010.5  200.45  5013.3  199.95  5016.5  200.45  5022.2  201.18  5028.3  207.27
  5049.3  214.65  5093.7  216.02  5358.8  221.83  5459.9   225.1  5567.2  226.44
#Mann= 7 ,-1 , 0
  3833.8      .1       0  4205.3     .05       0  4654.3      .1       0
  4904.5     .12       0  4998.7      .1       0  5010.5     .07       0
  5016.5      .1       0
Bank Sta=4599.6,5093.7
XS Rating Curve= 0 ,0
Exp/Cntr=0.3,0.1

Type RM Length L Ch R = 1 ,119438  ,576,576,576
BEGIN DESCRIPTION:
Mapping XS 6f02a352
END DESCRIPTION:
XS GIS Cut Line= 5
      2257430.28     13206852.42      2258108.57     13206508.87
      2258452.15     13205804.11      2258390.48     13205575.06
       2258139.9     13205261.21
#Sta/Elev= 30
  4059.3  223.95  4211.6  225.22  4482.1  223.67  4618.2  224.48  4679.4  222.73
    4856  222.92  4918.4  220.41    4969  216.35    4986  209.25  4991.6  209.03
  4999.9   204.3  5011.1  201.66  5013.9  201.16  5017.1  201.66  5022.1  203.24
  5031.1  203.04  5036.6  205.33  5044.4  206.29  5076.2   206.6  5133.4  210.62
  5177.9   208.9  5216.9  211.38  5464.8  214.93  5631.9  218.98  5833.1  218.81
  6004.9  224.96  6183.8  225.98  6190.2  227.43  6196.9  225.99  6242.5   226.6
#Mann= 5 ,-1 , 0
  4059.3      .1       0  4482.1     .05       0    4856      .1       0
  5011.1     .07       0  5017.1      .1       0
Bank Sta=4969,5464.8
XS Rating Curve= 0 ,0
Exp/Cntr=0.3,0.1

Type RM Length L Ch R = 1 ,118862  ,522,522,522
BEGIN DESCRIPTION:
Mapping XS d6bd6594
END DESCRIPTION:
XS GIS Cut Line= 5
      2257378.27     13208443.15      2258628.34     13206588.16
      2258813.34     13206112.44      2259192.15     13205566.25
      2259513.46     13205428.27
#Sta/Elev= 30
  2504.2  228.23  2574.5  226.21  2653.9  224.71  2689.6  224.34  2761.7  223.76
  4013.9  222.77  4181.2  222.22  4323.7   222.4  4532.9  222.89  4604.9   219.8
  4625.9  215.16  4640.9  218.45  4661.9  214.28  4712.8  221.72  4823.8  214.79
  4828.3   214.6  4903.4  208.75  4924.9  211.21  5000.4  199.97  5003.2  199.47
  5006.4  199.97  5042.9   212.2  5057.8  212.45  5082.4  201.29  5096.6   200.7
  5182.4  213.37  5245.6  215.97  5862.6  213.85  6103.3  224.81  6265.9  226.16
#Mann= 11 ,-1 , 0
  2504.2      .1       0  2574.5     .16       0  2653.9      .1       0
  2689.6     .16       0  2761.7      .1       0  4013.9     .05       0
  4181.2      .1       0  4323.7     .05       0  4823.8      .1       0
  5000.4     .07       0  5006.4      .1       0
Bank Sta=4828.3,5862.6
XS Rating Curve= 0 ,0
Exp/Cntr=0.3,0.1

Type RM Length L Ch R = 1 ,118340  ,304,304,304
BEGIN DESCRIPTION:
LAGARTO CREEK 88.0
END DESCRIPTION:
XS GIS Cut Line= 4
      2258211.63     13209007.34      2258871.34     13207687.92
      2259400.86     13205665.35       2259651.3     13205380.35
#Sta/Elev= 30
  2289.9  222.42  3412.2  219.26  3684.8  221.16    4200  222.75  4536.6  218.87
    4599  213.18  4644.8  209.37  4686.2   214.1  4737.8  215.45  4841.5  210.31
  4892.9   213.4  4944.6   209.5  4989.8  199.57  4992.6  199.07  4995.8  199.57
  5033.2  205.79  5120.3  213.27    5141  213.56  5189.7  206.71  5230.1  205.92
    5311  209.73  5346.2   208.6  5351.4  210.74    5427  209.24  5507.9  213.59
  5548.3  217.23  5937.3  227.11    6129  227.38  6164.1  230.75  6235.2  232.05
#Mann= 5 ,-1 , 0
  2289.9      .1       0  3684.8     .05       0  4536.6      .1       0
  4989.8     .07       0  4995.8      .1       0
Bank Sta=4599,5507.9
XS Rating Curve= 0 ,0
Exp/Cntr=0.3,0.1

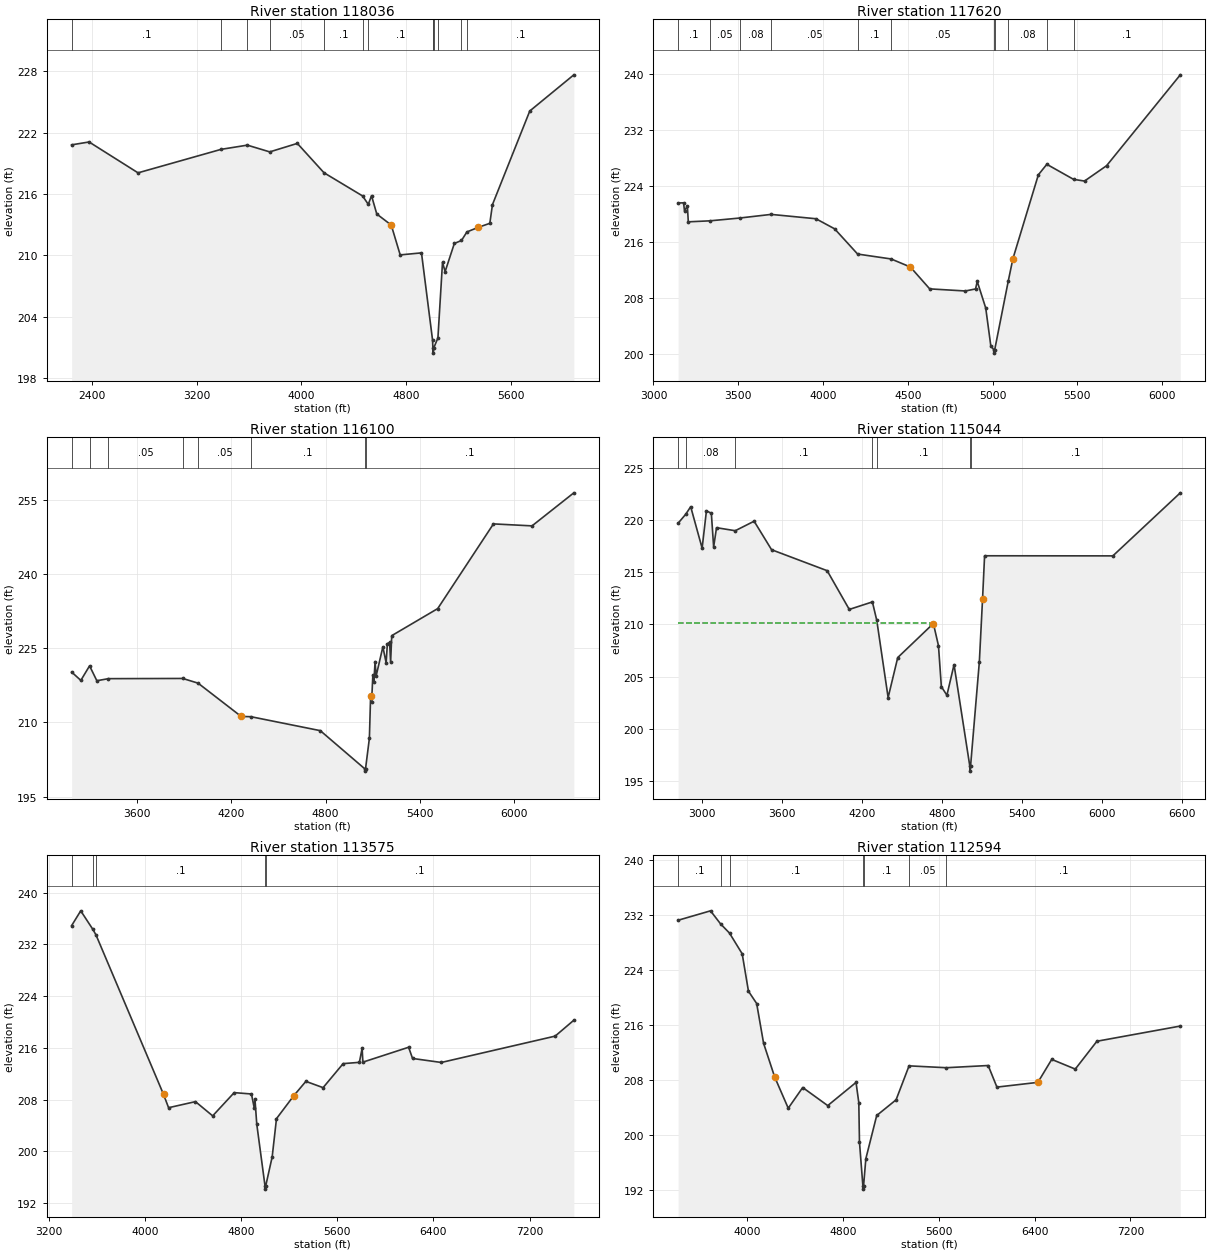
Type RM Length L Ch R = 1 ,118036  ,416,416,416
BEGIN DESCRIPTION:
LAGARTO CREEK 87.0
END DESCRIPTION:
XS GIS Cut Line= 4
      2258896.66     13209244.64      2259298.14     13208127.01
      2259536.85     13205783.26      2259590.96     13205491.06
#Sta/Elev= 30
  2243.6   220.8    2377  221.08  2751.3  218.06  3387.2  220.36  3587.3  220.77
  3758.5  220.11  3969.5  220.94  4173.3  218.07  4468.4   215.8  4512.1  214.98
    4537  215.82  4577.2  214.03  4687.8  212.95  4756.2  210.03    4919  210.23
  5003.5  201.72  5006.4  200.92  5009.2  200.42  5012.4  200.92  5044.7   201.9
  5079.8   209.3  5099.9   208.4  5170.3  211.15  5224.8  211.44  5266.7  212.28
  5353.9  212.73  5441.7  213.12  5461.8  214.95  5747.2  224.11  6084.2  227.65
#Mann= 13 ,-1 , 0
  2243.6      .1       0  3387.2     .05       0  3587.3      .1       0
  3758.5     .05       0  4173.3      .1       0  4468.4     .05       0
  4512.1      .1       0  5003.5     .16       0  5006.4     .07       0
  5012.4     .16       0  5044.7      .1       0  5224.8     .16       0
  5266.7      .1       0
Bank Sta=4687.8,5353.9
XS Rating Curve= 0 ,0
Exp/Cntr=0.3,0.1

Type RM Length L Ch R = 1 ,117620  ,1520,1520,1520
BEGIN DESCRIPTION:
LAGARTO CREEK 86.0
END DESCRIPTION:
XS GIS Cut Line= 4
      2259555.96     13208505.78      2259740.32     13208137.08
      2259839.24     13206329.46      2260234.94     13205704.43
#Sta/Elev= 30
  3145.4  221.56  3177.5  221.58  3183.1  220.44  3199.9  221.13  3205.5  218.87
  3332.4  219.01    3508  219.41  3693.8  219.93  3958.4  219.31  4068.6  217.87
  4204.2  214.27  4401.8  213.57  4515.5  212.42  4629.4   209.3  4839.8     209
  4899.8  209.29  4909.9  210.36  4959.9  206.57    4990  201.16    5007  200.63
  5009.8  200.13    5013  200.63  5093.4  210.48  5120.2   213.6  5270.4  225.58
  5320.3  227.08  5478.2  224.93  5542.7  224.69  5672.8  226.88  6107.7  239.85
#Mann= 11 ,-1 , 0
  3145.4      .1       0  3332.4     .05       0    3508     .08       0
  3693.8     .05       0  4204.2      .1       0  4401.8     .05       0
    5007     .04       0    5013     .05       0  5093.4     .08       0
  5320.3     .05       0  5478.2      .1       0
Bank Sta=4515.5,5120.2
XS Rating Curve= 0 ,0
Exp/Cntr=0.3,0.1

Type RM Length L Ch R = 1 ,116100  ,1056,1056,1056
BEGIN DESCRIPTION:
LAGARTO CREEK 85.0
END DESCRIPTION:
XS GIS Cut Line= 4
      2259438.95     13208650.35      2260111.69     13208205.47
      2261218.46     13207283.16      2261727.94     13206481.01
#Sta/Elev= 30
  3183.3  220.15  3241.8  218.47  3297.4  221.41  3343.7   218.4  3417.4  218.82
  3890.6  218.86  3988.3  217.91  4262.8  211.18  4324.8  211.13  4766.5  208.31
  5048.6  200.63  5051.4  200.13  5054.6  200.63    5079  206.76  5086.8  215.25
  5093.3  214.19  5101.1  219.57  5107.6  218.21  5115.4  222.27  5121.9  219.35
  5164.9  225.25  5185.7  222.02  5193.5  225.87  5207.8  226.15  5214.3  222.19
  5221.3  227.51    5514  232.98  5868.9   250.1  6114.6   249.7  6380.8  256.38
#Mann= 8 ,-1 , 0
  3183.3     .08       0  3297.4      .1       0  3417.4     .05       0
  3890.6      .1       0  3988.3     .05       0  4324.8      .1       0
  5048.6     .07       0  5054.6      .1       0
Bank Sta=4262.8,5086.8
XS Rating Curve= 0 ,0
Exp/Cntr=0.3,0.1

Type RM Length L Ch R = 1 ,115044  ,1469,1469,1469
BEGIN DESCRIPTION:
LAGARTO CREEK 84.0
END DESCRIPTION:
XS GIS Cut Line= 3
      2259221.21     13209235.76       2261826.8     13208170.59
      2262170.94     13207285.65
#Sta/Elev= 30
  2821.5  219.69  2878.1  220.54  2915.7  221.27  3001.4   217.3  3033.8  220.88
  3070.6  220.64  3087.8  217.41  3109.4  219.26  3249.8  218.97  3391.2  219.88
  3522.1  217.15  3938.8  215.14  4104.5  211.43  4277.8  212.15  4310.6  210.38
  4395.7  202.99  4467.8  206.82  4734.9  210.08  4773.1  207.96  4794.7  204.03
  4836.4  203.21  4889.8  206.14  5007.8  196.44  5010.6  195.94  5013.8  196.44
  5079.6  206.42  5103.6  212.45  5118.8  216.57  6080.3  216.56  6585.9   222.6
#Mann= 7 ,-1 , 0
  2821.5      .1       0  2878.1     .08       0  3249.8      .1       0
  4277.8     .05       0  4310.6      .1       0  5007.8     .07       0
  5013.8      .1       0
#XS Ineff= 2 , 0
         4713.07  210.09
Permanent Ineff=
       F       F
Bank Sta=4734.9,5103.6
XS Rating Curve= 0 ,0
Exp/Cntr=0.3,0.1

Type RM Length L Ch R = 1 ,113575  ,981,981,981
BEGIN DESCRIPTION:
Mapping XS a014c877
END DESCRIPTION:
XS GIS Cut Line= 3
       2260646.9     13210849.94      2262228.29     13208555.69
      2262637.73     13207220.94
#Sta/Elev= 30
  3386.7  234.89  3462.3  237.17  3563.5   234.3  3589.4  233.45  4152.1   208.8
    4194  206.75  4417.8  207.69  4561.2  205.49  4740.4  209.08  4884.3  208.87
  4907.4  206.72  4913.5  208.05  4928.4  204.22  4997.1  194.67  4999.8  194.17
  5003.1  194.67  5056.9  199.16  5092.7  205.06  5236.6   208.6  5337.5  210.82
  5480.8  209.85  5647.9  213.56  5783.1  213.76  5806.1  215.94  5812.2  213.79
  6193.2  216.09  6225.9  214.36  6465.6  213.74  7413.6  217.81  7569.3  220.27
#Mann= 5 ,-1 , 0
  3386.7      .1       0  3563.5     .08       0  3589.4      .1       0
  4997.1     .07       0  5003.1      .1       0
Bank Sta=4152.1,5236.6
XS Rating Curve= 0 ,0
Exp/Cntr=0.3,0.1

Type RM Length L Ch R = 1 ,112594  ,1013,1013,1013
BEGIN DESCRIPTION:
Mapping XS 6519ab82
END DESCRIPTION:
XS GIS Cut Line= 3
      2261499.04     13211693.92      2262580.62     13209309.52
       2262744.5     13207744.52
#Sta/Elev= 30
  3424.4  231.28  3694.9  232.65  3778.7  230.75  3853.4  229.41  3959.2   226.4
  4011.5  220.96    4080  219.17  4137.9  213.38  4230.2  208.49  4343.6  203.94
  4464.3  206.95  4673.2  204.32  4909.5  207.69  4932.6  204.75  4938.1  199.03
  4966.5  192.67  4969.2  192.17  4972.5  192.67  4991.4   196.6  5082.1  202.88
  5243.7  205.16  5352.1   210.1  5663.2  209.83  6012.6  210.15  6085.5  207.01
  6427.4   207.7    6543  211.04  6739.5  209.63  6920.1  213.68  7616.2  215.89
#Mann= 7 ,-1 , 0
  3424.4      .1       0  3778.7     .08       0  3853.4      .1       0
  4966.5     .07       0  4972.5      .1       0  5352.1     .05       0
  5663.2      .1       0
Bank Sta=4230.2,6427.4
XS Rating Curve= 0 ,0
Exp/Cntr=0.3,0.1