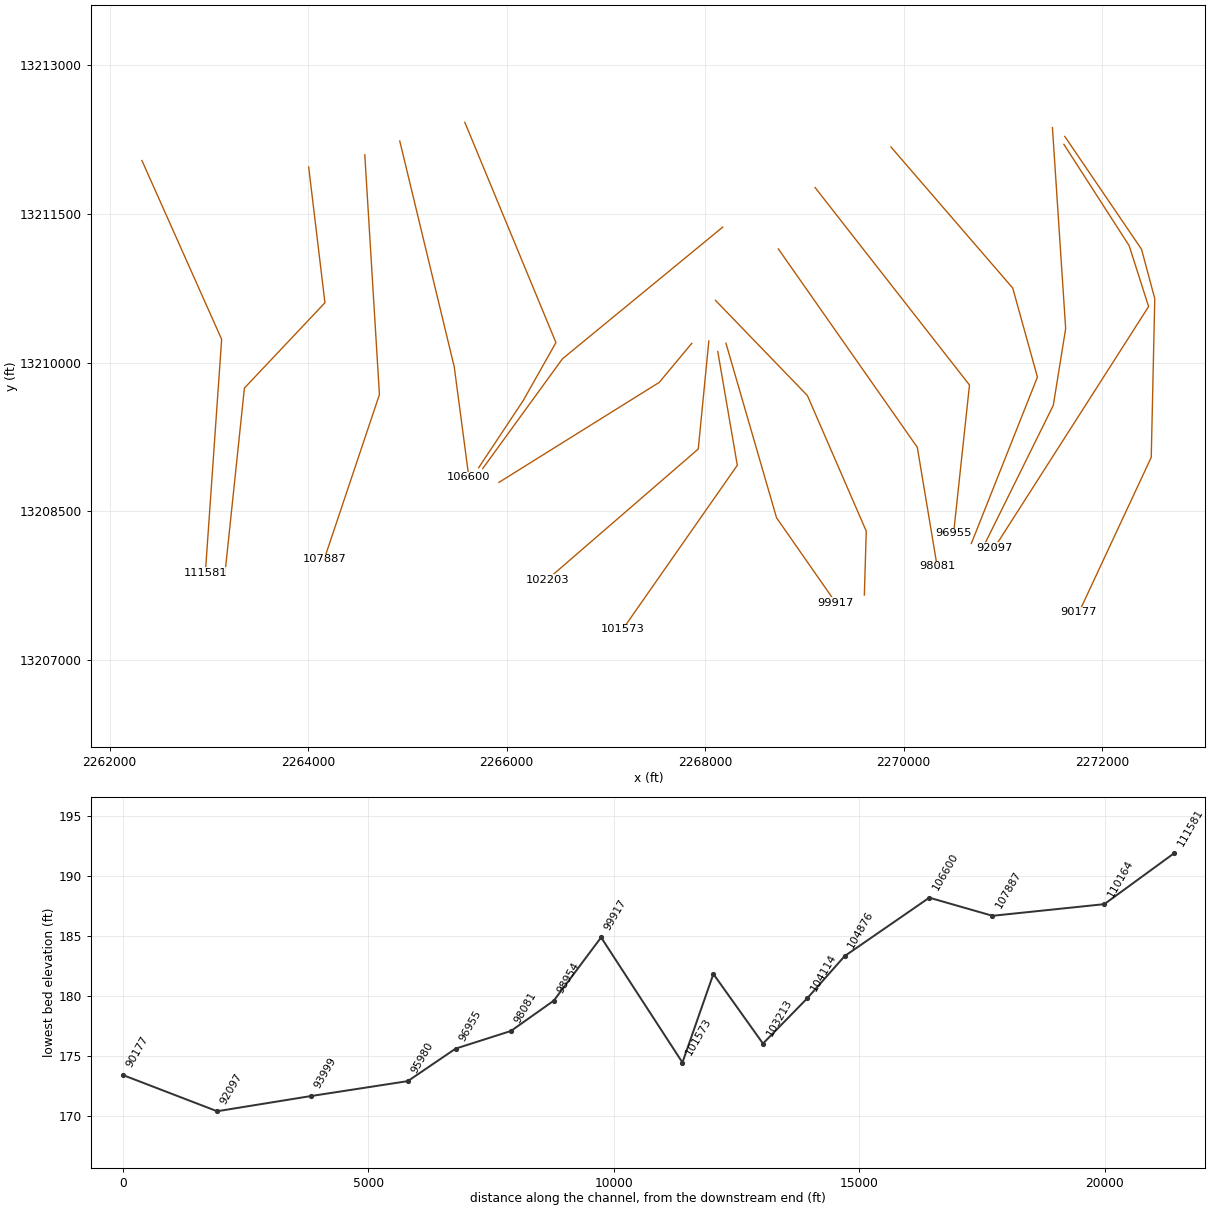
HEC-RAS study LAGARTO CREEK.prj: LAGARTO CREEK Base Level Engineering

--- LAGARTO CREEK.g01 (geometry) --- (continued)

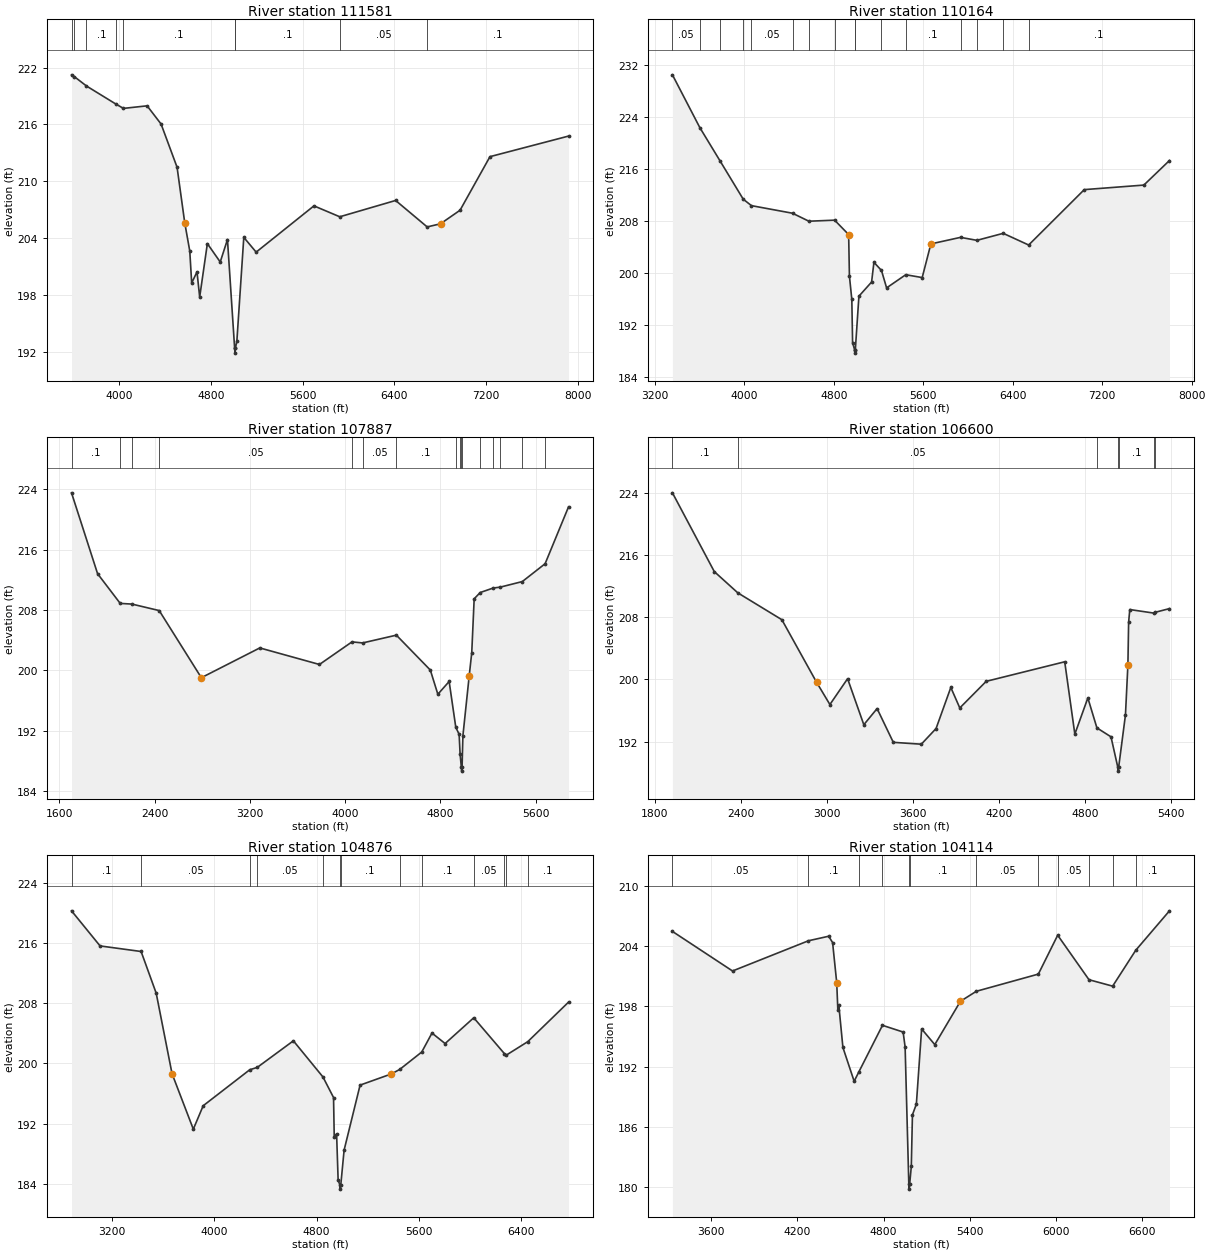
Type RM Length L Ch R = 1 ,111581  ,1417,1417,1417
BEGIN DESCRIPTION:
Mapping XS b8420616
END DESCRIPTION:
XS GIS Cut Line= 3
      2262326.61     13212038.04      2263129.61     13210235.41
      2262965.73     13207883.81
#Sta/Elev= 30
  3586.5  221.23    3612  221.03    3717  220.05  3975.4  218.13    4039  217.69
  4245.3  217.96  4366.9  216.04  4506.3  211.48  4573.1  205.62  4616.8  202.65
  4633.5  199.28  4679.9  200.45  4703.2  197.79  4770.1  203.43  4882.2  201.49
  4945.3  203.86  5007.9  192.38  5010.7  191.88  5013.9  192.38  5027.1  193.13
  5087.6  204.09  5195.2  202.53  5698.8  207.41  5923.8  206.26  6410.5  207.98
  6685.4  205.19  6801.5  205.52  6971.9  206.95  7232.5   212.6  7917.2  214.77
#Mann= 9 ,-1 , 0
  3586.5      .1       0    3612     .16       0    3717      .1       0
  3975.4     .05       0    4039      .1       0  5007.9     .07       0
  5013.9      .1       0  5923.8     .05       0  6685.4      .1       0
Bank Sta=4573.1,6801.5
XS Rating Curve= 0 ,0
Exp/Cntr=0.3,0.1

Type RM Length L Ch R = 1 ,110164  ,2277,2277,2277
BEGIN DESCRIPTION:
LAGARTO CREEK 83.0
END DESCRIPTION:
XS GIS Cut Line= 4
      2264006.33     13211972.53      2264170.21     13210604.13
      2263359.03     13209743.79      2263162.55     13207868.99
#Sta/Elev= 30
  3355.8  230.56  3600.9  222.42  3784.1  217.22  3989.2  211.38  4062.6  210.39
  4429.8  209.22  4576.1  207.99  4806.5  208.15    4932  205.93  4938.8  199.54
  4960.3  195.92  4967.2  189.27  4985.6  188.15  4988.4  187.65  4991.6  188.15
  5023.8  196.43  5137.1  198.61  5158.1  201.65  5225.5   200.4  5271.4  197.71
  5442.8  199.74  5589.8   199.3  5667.5  204.49  5932.8   205.5    6079  205.04
  6314.5  206.12  6542.1  204.32  7039.5  212.86  7572.4  213.56  7801.5  217.35
#Mann= 16 ,-1 , 0
  3355.8     .05       0  3600.9      .1       0  3784.1     .05       0
  3989.2      .1       0  4062.6     .05       0  4429.8      .1       0
  4576.1     .05       0  4806.5      .1       0  4985.6     .07       0
  4991.6      .1       0  5225.5     .16       0  5442.8      .1       0
  5932.8     .05       0    6079      .1       0  6314.5     .05       0
  6542.1      .1       0
Bank Sta=4932,5667.5
XS Rating Curve= 0 ,0
Exp/Cntr=0.3,0.1

Type RM Length L Ch R = 1 ,107887  ,1287,1287,1287
BEGIN DESCRIPTION:
LAGARTO CREEK 82.0
END DESCRIPTION:
XS GIS Cut Line= 3
      2264571.71     13212095.36      2264719.19     13209678.24
      2264162.36     13208015.93
#Sta/Elev= 30
  1701.6   223.5  1920.5   212.8  2110.6  208.87  2209.4  208.78  2438.2  207.92
  2792.1  199.04    3283  202.98    3784  200.79  4057.3  203.78  4146.3  203.64
  4430.1  204.67  4715.4  200.05  4778.5  196.85  4873.4  198.54  4929.2  192.48
  4957.3  191.55  4965.4  188.93  4975.9  187.18  4978.7  186.68  4981.9  187.18
  4988.9  191.35  5042.2  199.33  5063.3  202.36  5083.6  209.48  5134.3  210.31
  5242.5   210.9  5304.3  211.03    5488  211.76  5679.4  214.12  5876.3  221.65
#Mann= 16 ,-1 , 0
  1701.6      .1       0  2110.6     .05       0  2209.4      .1       0
  2438.2     .05       0  4057.3      .1       0  4146.3     .05       0
  4430.1      .1       0  4929.2     .16       0  4965.4      .1       0
  4975.9     .07       0  4981.9      .1       0  5134.3     .05       0
  5242.5      .1       0  5304.3     .05       0    5488      .1       0
  5679.4     .05       0
Bank Sta=2792.1,5042.2
XS Rating Curve= 0 ,0
Exp/Cntr=0.3,0.1

Type RM Length L Ch R = 1 ,106600  ,1724,1724,1724
BEGIN DESCRIPTION:
LAGARTO CREEK 81.0
END DESCRIPTION:
XS GIS Cut Line= 3
      2264924.04     13212234.67      2265473.02     13209956.82
       2265620.5     13208842.51
#Sta/Elev= 30
  1922.3  224.05  2214.3   213.9  2378.4  211.16  2685.7   207.7  2928.1  199.63
  3020.7  196.77  3144.1   200.1  3257.3  194.17  3349.9  196.25    3463   191.9
  3658.4  191.66  3761.3  193.68  3864.2  198.97  3926.8  196.33    4111  199.76
  4658.7  202.28  4729.3  192.96  4820.1  197.62  4883.3  193.76  4981.5  192.61
    5029  188.69  5031.7  188.19    5035  188.69  5082.4  195.43  5099.5   201.9
  5104.5  207.38  5112.7  209.01  5281.4  208.55  5286.4  208.64  5389.4  209.13
#Mann= 7 ,-1 , 0
  1922.3      .1       0  2378.4     .05       0  4883.3      .1       0
    5029     .07       0    5035      .1       0  5281.4     .05       0
  5286.4      .1       0
Bank Sta=2928.1,5099.5
XS Rating Curve= 0 ,0
Exp/Cntr=0.3,0.1

Type RM Length L Ch R = 1 ,104876  ,762,762,762
BEGIN DESCRIPTION:
LAGARTO CREEK 80.0
END DESCRIPTION:
XS GIS Cut Line= 4
      2265579.55      13212423.1      2266497.24     13210202.64
      2266169.49     13209620.88      2265719.16      13208941.3
#Sta/Elev= 30
  2884.1  220.27  3107.3  215.61  3428.1  214.87  3546.2  209.33  3669.9  198.65
  3836.3  191.28  3913.4  194.39  4277.5  199.17    4336  199.48  4618.5  203.01
  4849.8  198.21  4932.5  195.48  4937.9   190.3  4956.4  190.66  4968.4  184.54
  4982.8  183.82  4985.5  183.32  4988.8  183.82  5015.1   188.5    5140  197.13
  5385.2  198.62  5449.7  199.21  5621.9  201.52  5702.1  204.04  5804.7  202.65
  6028.6  206.07  6268.2  201.31    6281  201.09    6451   202.9  6769.7  208.15
#Mann= 13 ,-1 , 0
  2884.1      .1       0  3428.1     .05       0  4277.5      .1       0
    4336     .05       0  4849.8      .1       0  4982.8     .07       0
  4988.8      .1       0  5449.7     .05       0  5621.9      .1       0
  6028.6     .05       0  6268.2      .1       0    6281     .05       0
    6451      .1       0
Bank Sta=3669.9,5385.2
XS Rating Curve= 0 ,0
Exp/Cntr=0.3,0.1

Type RM Length L Ch R = 1 ,104114  ,901,901,901
BEGIN DESCRIPTION:
Mapping XS 9c9ab16d
END DESCRIPTION:
XS GIS Cut Line= 3
      2268176.98     13211366.17      2266562.79     13210038.76
      2265759.78     13208932.58
#Sta/Elev= 30
  3330.8  205.46  3748.8  201.52  4276.9  204.53  4417.4  204.98  4444.7  204.35
  4473.4  200.35  4481.3  197.62  4487.8  198.13  4516.4  193.91  4594.6  190.54
  4627.6  191.48  4791.6  196.11  4935.3  195.44  4949.1  193.95  4974.8   180.3
  4977.5   179.8  4980.8   180.3  4992.1  182.06    5000   187.2  5027.3  188.26
  5063.9  195.75  5155.4  194.19  5333.6   198.5  5444.5   199.5  5875.7  201.21
  6010.2  205.08  6227.9  200.65  6392.4  200.01  6552.9  203.58  6787.6  207.51
#Mann= 12 ,-1 , 0
  3330.8     .05       0  4276.9      .1       0  4627.6     .05       0
  4791.6      .1       0  4974.8     .07       0  4980.8      .1       0
  5444.5     .05       0  5875.7      .1       0  6010.2     .05       0
  6227.9      .1       0  6392.4     .05       0  6552.9      .1       0
Bank Sta=4473.4,5333.6
XS Rating Curve= 0 ,0
Exp/Cntr=0.3,0.1

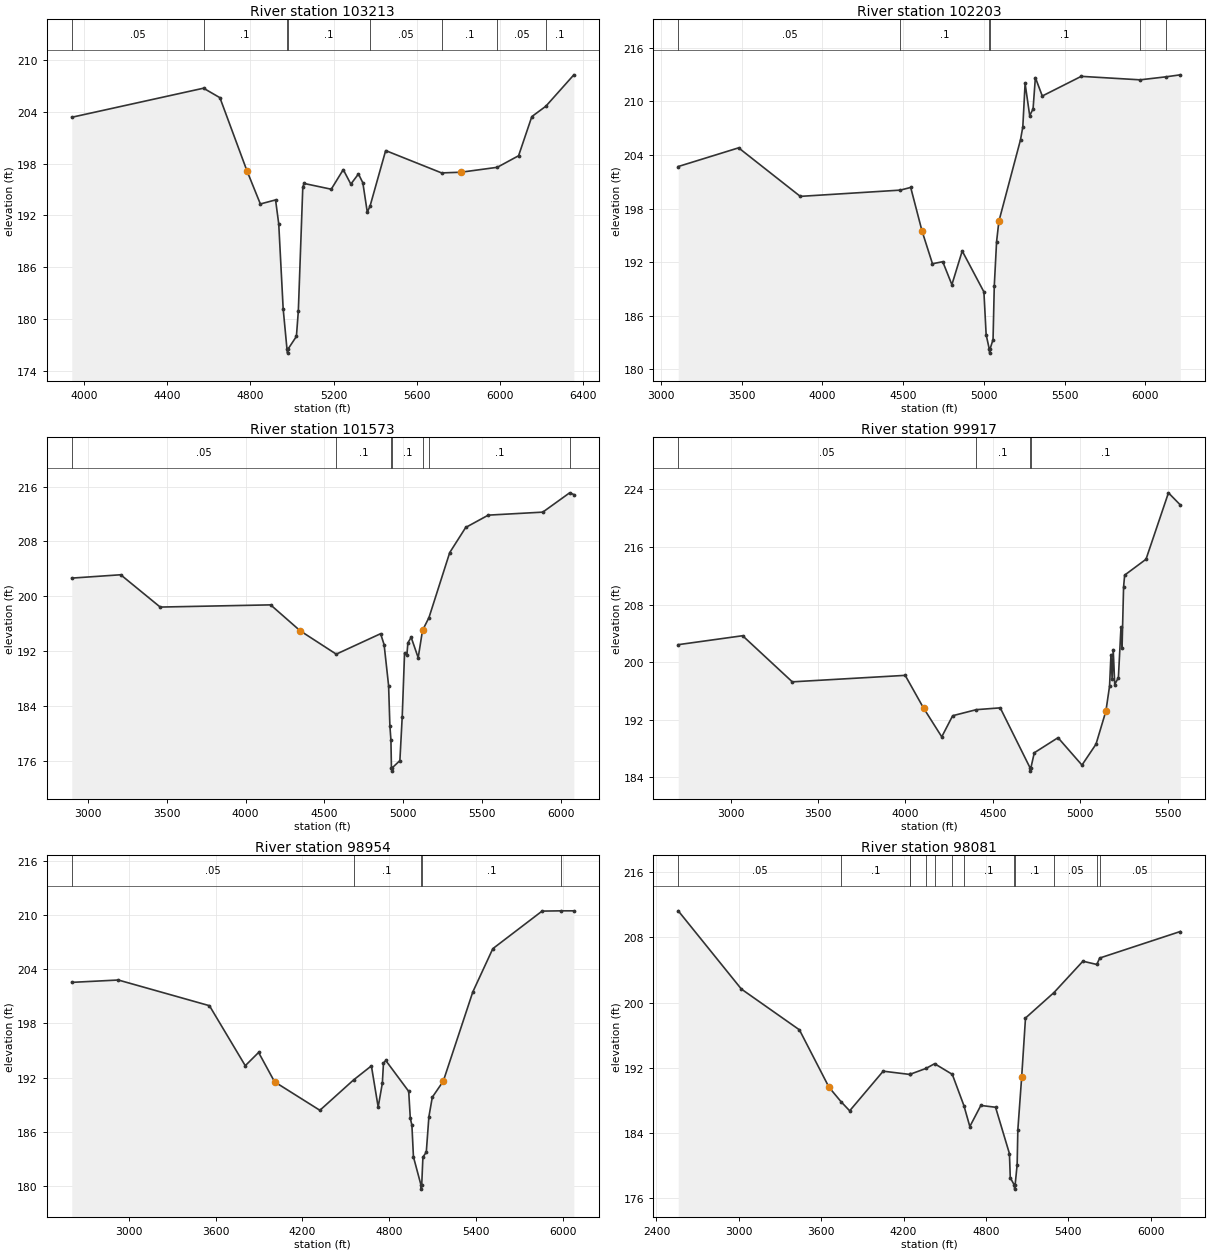
Type RM Length L Ch R = 1 ,103213  ,1010,1010,1010
BEGIN DESCRIPTION:
Mapping XS 2a74590c
END DESCRIPTION:
XS GIS Cut Line= 3
       2267865.6     13210194.45      2267537.84     13209801.14
       2265923.7     13208793.33
#Sta/Elev= 30
  3940.5  203.37  4574.2  206.74    4653  205.64  4782.7  197.19  4847.6  193.32
  4920.7  193.79    4936  191.01  4957.3  181.17  4975.5  176.53  4978.3  176.03
  4981.5  176.53    5021  177.97  5030.3  180.94  5051.7  195.27  5057.6   195.7
  5188.5  195.03  5246.3   197.3  5282.8  195.62  5319.4   196.8  5340.6  195.77
  5361.9  192.36  5375.5   193.1  5450.3  199.51  5719.3  196.92  5812.4     197
    5987  197.57  6089.6  198.91  6153.3  203.45  6220.7  204.65  6355.4  208.29
#Mann= 8 ,-1 , 0
  3940.5     .05       0  4574.2      .1       0  4975.5     .07       0
  4981.5      .1       0  5375.5     .05       0  5719.3      .1       0
    5987     .05       0  6220.7      .1       0
Bank Sta=4782.7,5812.4
XS Rating Curve= 0 ,0
Exp/Cntr=0.3,0.1

Type RM Length L Ch R = 1 ,102203  ,630,630,630
BEGIN DESCRIPTION:
LAGARTO CREEK 79.0
END DESCRIPTION:
XS GIS Cut Line= 3
      2268037.66     13210219.02      2267931.14     13209129.25
      2266408.12     13207810.94
#Sta/Elev= 30
  3106.9  202.71  3480.8   204.8  3862.7  199.37  4482.7  200.07  4546.5  200.37
  4616.7  195.49  4681.4  191.83    4745  192.06  4801.6  189.49  4865.6  193.26
  4999.9  188.68  5013.7   183.9  5032.6  182.33  5035.4  181.83  5038.6  182.33
  5056.5  183.35  5064.1  189.34  5078.4   194.3  5092.5  196.57  5226.5   205.7
  5240.8  207.14    5255     212  5283.5   208.4  5304.4  209.16  5318.6  212.66
  5361.4   210.6  5602.7   212.8    5967  212.41  6128.9  212.75  6216.2  212.97
#Mann= 6 ,-1 , 0
  3106.9     .05       0  4482.7      .1       0  5032.6     .07       0
  5038.6      .1       0    5967     .05       0  6128.9      .1       0
Bank Sta=4616.7,5092.5
XS Rating Curve= 0 ,0
Exp/Cntr=0.3,0.1

Type RM Length L Ch R = 1 ,101573  ,1656,1656,1656
BEGIN DESCRIPTION:
LAGARTO CREEK 78.0
END DESCRIPTION:
XS GIS Cut Line= 3
      2268127.79     13210112.52      2268324.44     13208965.38
      2267169.66     13207311.02
#Sta/Elev= 30
  2898.7  202.65  3208.8  203.14    3459  198.42  4158.7  198.74  4346.2  194.95
  4574.6  191.54  4855.7  194.53  4877.9  192.92  4906.3  186.94  4914.4   181.1
  4921.1  178.96  4924.2  174.95  4926.9  174.45  4930.2  174.95  4977.8  175.99
  4992.6  182.41  5007.5  191.72  5022.3  191.44  5028.4  193.19  5049.3     194
  5093.8  191.02  5121.8   195.1  5124.9  195.18  5162.2  196.89  5293.6  206.38
  5394.8  210.05  5537.8  211.85  5883.3  212.29  6053.5  215.11  6080.1  214.86
#Mann= 7 ,-1 , 0
  2898.7     .05       0  4574.6      .1       0  4924.2     .07       0
  4930.2      .1       0  5124.9     .16       0  5162.2      .1       0
  6053.5     .05       0
Bank Sta=4346.2,5121.8
XS Rating Curve= 0 ,0
Exp/Cntr=0.3,0.1

Type RM Length L Ch R = 1 ,99917   ,963,963,963
BEGIN DESCRIPTION:
Mapping XS 3053d7ce
END DESCRIPTION:
XS GIS Cut Line= 3
      2268210.17     13210195.66      2268719.74     13208436.18
      2269315.36     13207581.18
#Sta/Elev= 30
  2699.4  202.43  3067.9  203.67  3352.2  197.27  3998.5  198.17  4103.6  193.63
  4207.7  189.64  4270.2  192.57  4405.8  193.41  4542.5  193.66  4712.3  185.38
  4715.1  184.88  4718.3  185.38  4737.5  187.43  4873.2  189.52  5010.3  185.72
  5090.6  188.62  5147.3  193.21  5168.2  196.67  5176.3  201.05    5183  197.64
  5189.1  201.75  5197.9  196.89  5218.8  197.87  5233.7  204.86  5239.7  201.95
  5248.5  210.44  5254.6  212.08  5376.8  214.28  5505.3   223.5  5573.2  221.82
#Mann= 4 ,-1 , 0
  2699.4     .05       0  4405.8      .1       0  4712.3     .07       0
  4718.3      .1       0
Bank Sta=4103.6,5147.3
XS Rating Curve= 0 ,0
Exp/Cntr=0.3,0.1

Type RM Length L Ch R = 1 ,98954   ,873,873,873
BEGIN DESCRIPTION:
LAGARTO CREEK 77.0
END DESCRIPTION:
XS GIS Cut Line= 4
      2268104.39     13210628.31      2269030.43     13209668.63
      2269623.51     13208301.58      2269604.28     13207657.44
#Sta/Elev= 30
  2607.1  202.56  2928.7  202.82  3558.1  199.97  3805.6  193.31  3897.7  194.78
  4008.1  191.52    4321  188.36  4553.7  191.73  4676.8  193.29  4723.7  188.72
  4752.6  191.38  4760.2   193.6  4776.1  193.89  4934.6  190.46  4945.5  187.48
  4956.7   186.7  4967.3  183.19  5018.6  180.11  5021.4  179.61  5024.6  180.11
  5032.7  183.17    5056  183.71    5074  187.64  5097.5  189.81  5173.3  191.59
  5377.4   201.5  5515.6   206.3  5855.8  210.47  5989.7   210.5  6075.3   210.5
#Mann= 5 ,-1 , 0
  2607.1     .05       0  4553.7      .1       0  5018.6     .07       0
  5024.6      .1       0  5989.7     .05       0
Bank Sta=4008.1,5173.3
XS Rating Curve= 0 ,0
Exp/Cntr=0.3,0.1

Type RM Length L Ch R = 1 ,98081   ,1126,1126,1126
BEGIN DESCRIPTION:
LAGARTO CREEK 76.0
END DESCRIPTION:
XS GIS Cut Line= 3
      2268737.73     13211146.85      2270137.72     13209146.85
      2270337.73     13207946.81
#Sta/Elev= 30
  2558.7  211.27  3018.6  201.66  3441.5  196.65  3657.3  189.59  3745.4  187.81
  3807.7   186.7  4051.8  191.57  4246.2  191.17  4247.9  191.19  4363.9  191.91
  4426.6  192.49  4555.4  191.18  4640.2  187.33  4683.1  184.77  4763.3  187.36
  4870.5  187.14  4971.7  181.44  4977.8  178.48  5007.1  177.58  5009.9  177.08
  5013.1  177.58  5027.9   180.1  5032.9  184.36  5060.8  190.85  5088.7   198.1
  5296.2  201.23  5506.9  205.08  5608.2  204.68  5629.3  205.47  6216.6  208.73
#Mann= 13 ,-1 , 0
  2558.7     .05       0  3745.4      .1       0  4246.2     .05       0
  4247.9      .1       0  4363.9     .05       0  4426.6      .1       0
  4555.4     .07       0  4640.2      .1       0  5007.1     .07       0
  5013.1      .1       0  5296.2     .05       0  5608.2      .1       0
  5629.3     .05       0
Bank Sta=3657.3,5060.8
XS Rating Curve= 0 ,0
Exp/Cntr=0.3,0.1

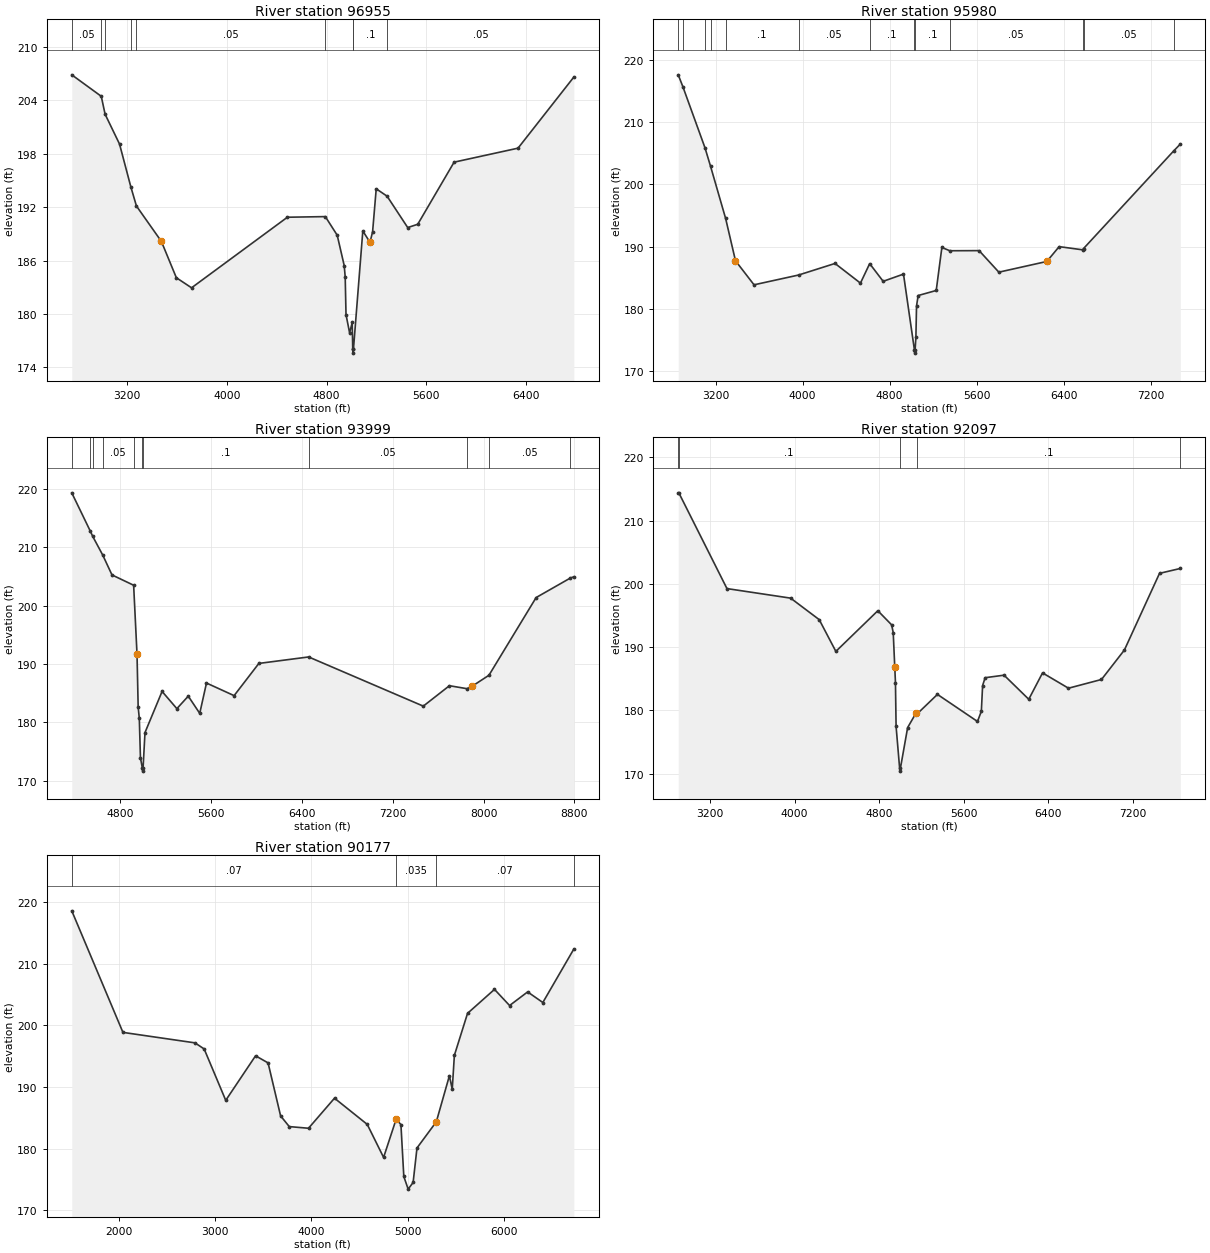
Type RM Length L Ch R = 1 ,96955   ,975,975,975
BEGIN DESCRIPTION:
LAGARTO CREEK 75.0
END DESCRIPTION:
XS GIS Cut Line= 3
      2269108.12     13211765.58      2270663.56      13209774.6
       2270503.6     13208281.59
#Sta/Elev= 30
  2755.5  206.84  2992.1  204.43  3022.9  202.42  3138.7  199.07  3229.7  194.25
  3274.3  192.12  3474.3  188.15  3594.6  184.07  3716.6  182.94  4485.4  190.86
  4789.9  190.93  4885.1  188.84  4941.2  185.44  4949.2  184.17  4955.7  179.94
  4984.6  177.88  5005.4  179.05  5009.7  176.11  5012.4  175.61  5015.7  176.11
  5090.5  189.32  5148.3  188.04  5169.1  189.24  5198.1  194.05  5285.4  193.22
  5450.7   189.7  5531.2  190.07  5822.9  197.04  6335.8  198.61  6783.6  206.59
#Mann= 9 ,-1 , 0
  2755.5     .05       0  2992.1      .1       0  3022.9     .05       0
  3229.7      .1       0  3274.3     .05       0  4789.9      .1       0
  5009.7     .07       0  5015.7      .1       0  5285.4     .05       0
Bank Sta=3474.3,5148.3
XS Rating Curve= 0 ,0
Exp/Cntr=0.3,0.1

Type RM Length L Ch R = 1 ,95980   ,1981,1981,1981
BEGIN DESCRIPTION:
LAGARTO CREEK 74.0
END DESCRIPTION:
XS GIS Cut Line= 4
      2269872.52     13212174.43      2271099.09     13210752.32
      2271347.97      13209854.6      2270682.05     13208176.48
#Sta/Elev= 30
  2856.9  217.59  2899.6  215.68  3102.8  205.87    3154   202.9  3292.6  194.52
  3383.2  187.73  3553.6  183.87  3962.9  185.44  4298.1   187.3  4531.8  184.14
  4616.6  187.27  4740.6  184.43  4927.4  185.59  5028.1   173.4  5030.9   172.9
  5034.1   173.4  5041.5  175.48  5047.3  180.48  5062.3  182.15  5228.3  182.96
  5280.2  189.87  5352.9  189.34  5622.6  189.36  5803.9   185.9  6244.8  187.62
  6358.2     190  6573.6  189.49  6582.3  189.69    7410  205.35  7471.9  206.47
#Mann= 13 ,-1 , 0
  2856.9      .1       0  2899.6     .05       0  3102.8      .1       0
    3154     .05       0  3292.6      .1       0  3962.9     .05       0
  4616.6      .1       0  5028.1     .07       0  5034.1      .1       0
  5352.9     .05       0  6573.6      .1       0  6582.3     .05       0
    7410      .1       0
Bank Sta=3383.2,6244.8
XS Rating Curve= 0 ,0
Exp/Cntr=0.3,0.1

Type RM Length L Ch R = 1 ,93999   ,1902,1902,1902
BEGIN DESCRIPTION:
LAGARTO CREEK 73.0
END DESCRIPTION:
XS GIS Cut Line= 4
      2271499.07     13212370.01      2271632.39     13210343.46
      2271507.96     13209570.17      2270797.28     13208131.05
#Sta/Elev= 30
  4375.5  219.35  4539.7  212.74  4560.3  211.87  4648.6  208.66  4729.4  205.28
  4920.1  203.51  4949.9  191.64  4959.9  182.64  4969.9   180.7    4980  173.93
    4997  172.15  4999.7  171.65    5003  172.15    5020  178.26  5170.4  185.31
  5300.6  182.36  5400.9   184.5  5501.8  181.55  5561.2  186.75  5804.4  184.59
  6022.2  190.11  6460.5  191.22  7469.6  182.79  7699.6  186.29  7854.3  185.78
    7896  186.16  8047.4  188.08  8462.7   201.4  8763.5  204.74  8794.7  204.96
#Mann= 11 ,-1 , 0
  4375.5      .1       0  4539.7     .05       0  4560.3      .1       0
  4648.6     .05       0  4920.1      .1       0    4997     .07       0
    5003      .1       0  6460.5     .05       0  7854.3      .1       0
  8047.4     .05       0  8763.5      .1       0
Bank Sta=4949.9,7896
XS Rating Curve= 0 ,0
Exp/Cntr=0.3,0.1

Type RM Length L Ch R = 1 ,92097   ,1920,1920,1920
BEGIN DESCRIPTION:
Mapping XS 6738ab2b
END DESCRIPTION:
XS GIS Cut Line= 4
      2271614.59     13212201.16      2272272.35     13211178.96
       2272467.9     13210565.67      2270913.09     13208131.28
#Sta/Elev= 30
  2898.9  214.39  2904.5  214.39  3359.6  199.25  3961.8  197.74  4232.1  194.34
  4389.5  189.32  4786.4  195.75  4916.7  193.52  4931.9   192.3  4946.6  186.79
    4953   184.4    4959  177.45  4992.3  170.89  4995.1  170.39  5068.1  177.27
  5148.3   179.6  5156.1  179.41    5350  182.52  5728.8  178.24  5765.2  179.85
  5777.2  183.92  5800.9  185.16  5980.1  185.56  6213.6  181.75  6343.9  185.92
  6589.2   183.5  6901.4  184.88    7118  189.54  7450.2  201.66  7646.7  202.43
#Mann= 5 ,-1 , 0
  2898.9     .05       0  2904.5      .1       0  4992.3     .05       0
  5156.1      .1       0  7646.7      .1       0
Bank Sta=4946.6,5148.3
XS Rating Curve= 0 ,0
Exp/Cntr=0.3,0.1

Type RM Length L Ch R = 1 ,90177   ,941,941,941
BEGIN DESCRIPTION:
LAGARTO CREEK 72.0
END DESCRIPTION:
XS GIS Cut Line= 5
      2271623.52      13212281.1      2272396.79     13211143.41
      2272530.12     13210645.66      2272494.56     13209045.76
       2271765.8     13207481.59
#Sta/Elev= 30
  1509.9  218.58  2041.6  198.85    2790  197.15  2885.5  196.16  3109.7  187.82
  3419.6  195.05  3549.6   193.9  3679.7   185.3  3769.7  183.56  3969.7  183.29
  4239.8  188.17  4579.9  183.92  4749.9  178.56    4880  184.74  4882.4   184.7
    4930  183.89    4960  175.46  5005.2  173.41  5056.7  174.49  5096.9  180.09
  5297.8  184.34  5433.7  191.81  5463.2  189.62  5485.3  195.12  5622.2  201.94
  5902.1  205.83    6059  203.21  6246.5  205.42  6404.5   203.7  6726.7  212.38
#Mann= 4 ,-1 , 0
  1509.9     .07       0  4882.4    .035       0  5297.8     .07       0
  6726.7      .1       0
Bank Sta=4880,5297.8
XS Rating Curve= 0 ,0
Exp/Cntr=0.3,0.1