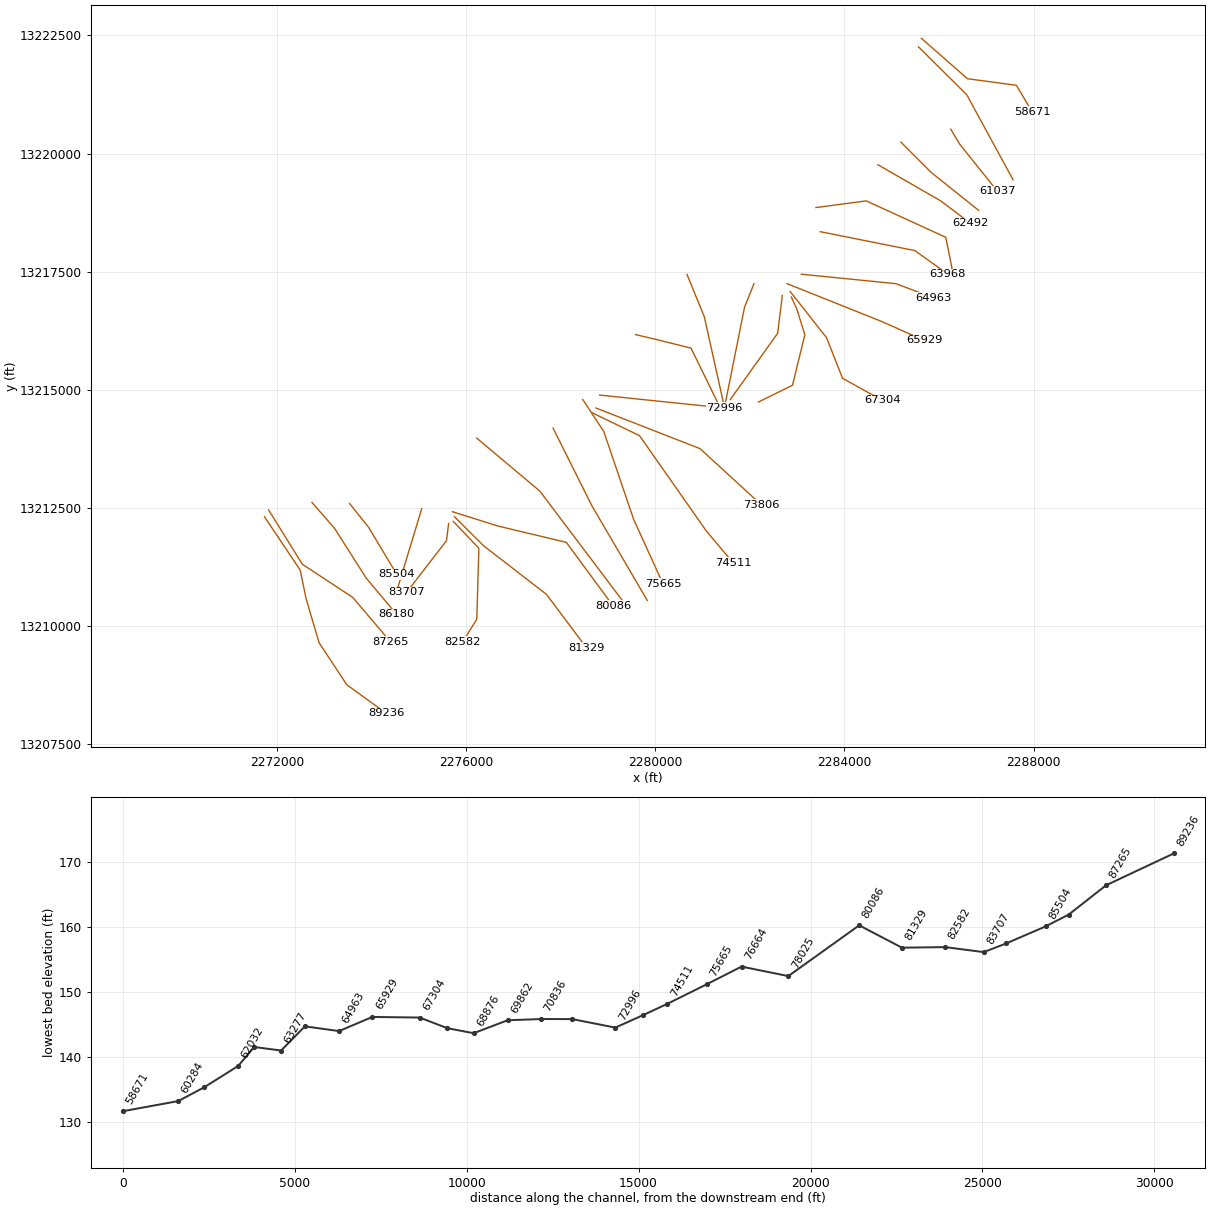
HEC-RAS study LAGARTO CREEK.prj: LAGARTO CREEK Base Level Engineering

--- LAGARTO CREEK.g01 (geometry) --- (continued)

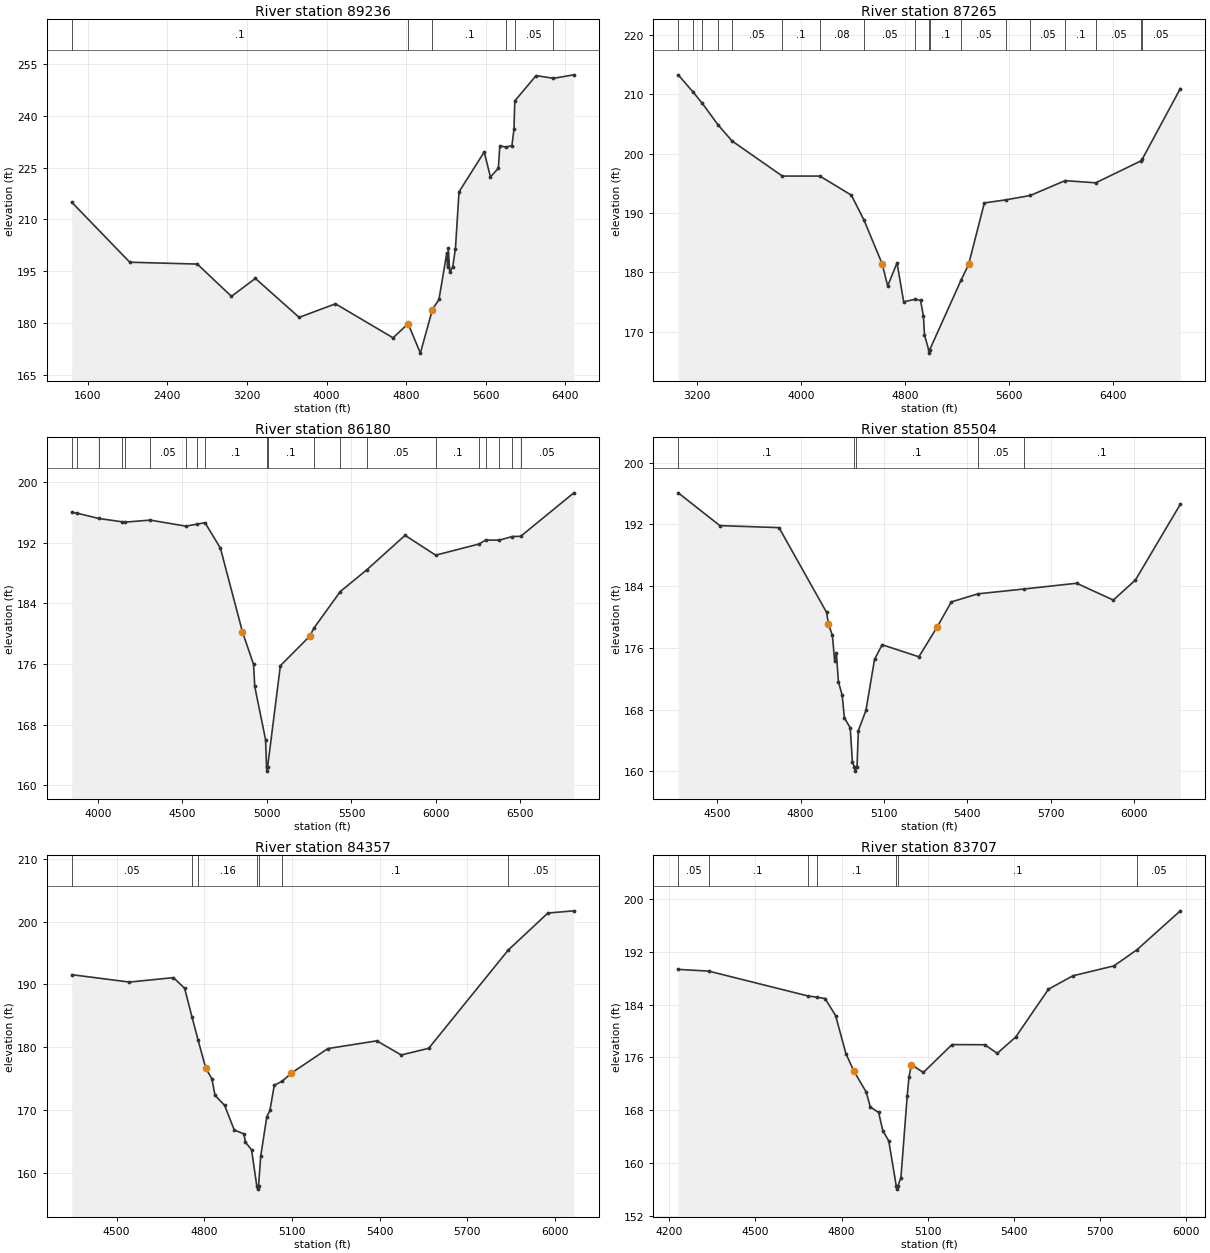
Type RM Length L Ch R = 1 ,89236   ,1971,1971,1971
BEGIN DESCRIPTION:
LAGARTO CREEK 71.0
END DESCRIPTION:
XS GIS Cut Line= 6
      2271739.05     13212316.68      2272494.56     13211187.85
        2272619.     13210583.44      2272894.54     13209650.17
      2273481.17     13208761.33      2274316.69     13208156.91
#Sta/Elev= 30
  1440.5  214.94  2023.2  197.58  2701.7  197.04  3044.9   187.7  3285.2  192.89
  3725.2  181.61  4090.1  185.54  4668.6  175.69  4819.9  179.79  4943.1  171.26
    5064  183.86  5129.9  186.79  5208.2   200.2  5217.3  196.18  5223.3  201.58
  5238.3   194.8  5267.6  196.11  5295.5  201.54  5331.6  217.97  5584.5  229.48
  5647.2  222.25  5726.7  224.79  5741.5  231.24  5805.6  230.92  5862.9  231.32
  5883.8  236.11  5891.7  244.26  6105.7  251.61    6280  250.82  6485.2  251.83
#Mann= 6 ,-1 , 0
  1440.5      .1       0  4819.9     .05       0    5064      .1       0
  5805.6     .08       0  5891.7     .05       0    6280      .1       0
Bank Sta=4819.9,5064
XS Rating Curve= 0 ,0
Exp/Cntr=0.3,0.1

Type RM Length L Ch R = 1 ,87265   ,1085,1085,1085
BEGIN DESCRIPTION:
Mapping XS 331918b6
END DESCRIPTION:
XS GIS Cut Line= 4
      2271827.92     13212458.91      2272539.01     13211312.29
      2273605.61     13210610.11      2274405.58     13209667.91
#Sta/Elev= 30
  3053.7  213.31  3165.5  210.47    3239   208.5    3361  204.84  3467.3  202.16
  3854.5  196.23  4143.2  196.23  4385.4  193.01  4483.4  188.77  4622.4  181.42
  4664.8  177.69  4736.8  181.59    4788  175.01  4877.2  175.46  4917.5  175.24
  4940.1  172.59  4947.7  169.46  4980.8  166.86  4983.6  166.36  4986.8  166.86
  5228.8  178.65  5287.3  181.32  5408.5   191.7  5577.2  192.23  5762.5  192.96
  6029.9  195.46  6265.3  195.09  6615.6  198.82  6622.8  199.07  6915.9  210.99
#Mann= 18 ,-1 , 0
  3053.7     .05       0  3165.5     .08       0    3239     .05       0
    3361     .08       0  3467.3     .05       0  3854.5      .1       0
  4143.2     .08       0  4483.4     .05       0  4877.2      .1       0
  4980.8     .07       0  4986.8      .1       0  5228.8     .05       0
  5577.2      .1       0  5762.5     .05       0  6029.9      .1       0
  6265.3     .05       0  6615.6      .1       0  6622.8     .05       0
Bank Sta=4622.4,5287.3
XS Rating Curve= 0 ,0
Exp/Cntr=0.3,0.1

Type RM Length L Ch R = 1 ,86180   ,676,676,676
BEGIN DESCRIPTION:
LAGARTO CREEK 70.0
END DESCRIPTION:
XS GIS Cut Line= 4
      2272743.42     13212618.89      2273223.41      13212067.8
      2273890.03     13211018.97        2274530.     13210254.56
#Sta/Elev= 30
  3845.2     196  3875.4  195.91  4003.8  195.21  4144.1  194.76  4160.8  194.72
  4308.6  194.99  4520.7  194.19  4584.9  194.45  4633.7  194.64  4724.6  191.29
    4855  180.24  4920.8  175.93  4927.8  173.03  4991.8  166.01  4997.6  162.35
  5000.4  161.85  5003.6  162.35  5079.4  175.77  5252.5  179.65  5277.5  180.72
    5434  185.56  5591.3  188.44  5817.1  192.98  5998.2  190.36  6255.7  191.84
  6293.4  192.35  6375.4  192.35  6451.9  192.82  6501.2  192.85  6815.7  198.59
#Mann= 20 ,-1 , 0
  3845.2     .08       0  3875.4     .05       0  4003.8      .1       0
  4144.1     .05       0  4160.8      .1       0  4308.6     .05       0
  4520.7      .1       0  4584.9     .05       0  4633.7      .1       0
  4997.6     .07       0  5003.6      .1       0  5277.5     .05       0
    5434      .1       0  5591.3     .05       0  5998.2      .1       0
  6255.7     .05       0  6293.4      .1       0  6375.4     .05       0
  6451.9      .1       0  6501.2     .05       0
Bank Sta=4855,5252.5
XS Rating Curve= 0 ,0
Exp/Cntr=0.3,0.1

Type RM Length L Ch R = 1 ,85504   ,1147,1147,1147
BEGIN DESCRIPTION:
LAGARTO CREEK 69.0
END DESCRIPTION:
XS GIS Cut Line= 3
      2273537.73     13212596.85      2273937.72     13212096.85
      2274537.73     13211096.85
#Sta/Elev= 30
  4359.7  196.09  4509.4  191.84  4722.3  191.58  4893.5  180.59    4900  179.12
  4914.4   177.6  4922.4  174.32  4928.8  175.29    4936  171.61  4949.6  169.85
  4957.6  166.92  4978.4  165.64  4986.4  161.25  4993.8  160.52  4996.5  160.02
  4999.8  160.52  5002.9  160.52  5007.8  165.28    5035  167.88  5066.1  174.51
  5093.3   176.4  5225.5  174.84  5291.5  178.71  5342.1  181.95  5438.3     183
  5602.4  183.62    5793  184.37  5925.2  182.19  6004.9   184.8  6166.2  194.61
#Mann= 5 ,-1 , 0
  4359.7      .1       0  4993.8     .07       0  4999.8      .1       0
  5438.3     .05       0  5602.4      .1       0
Bank Sta=4900,5291.5
XS Rating Curve= 0 ,0
Exp/Cntr=0.3,0.1

Type RM Length L Ch R = 1 ,84357   ,650,650,650
BEGIN DESCRIPTION:
LAGARTO CREEK 68.0
END DESCRIPTION:
XS GIS Cut Line= 2
      2275063.31     13212485.58      2274565.65     13210841.55
#Sta/Elev= 30
  4346.9  191.56  4544.1  190.38  4694.8  191.09    4733  189.39  4758.4  184.79
  4779.3   181.1  4805.3  176.67  4826.2  174.99    4837  172.34  4869.9  170.73
  4902.9  166.82  4935.8   166.2  4941.1  164.88    4962  163.66  4979.9   157.9
  4982.6   157.4  4985.9   157.9  4993.3  162.64  5014.2  168.94  5024.7  169.93
  5039.8  173.95  5067.4  174.61  5097.8  175.87  5223.2  179.79  5390.4  181.02
    5474  178.77    5568  179.83  5840.1  195.48  5975.9  201.38  6064.6  201.73
#Mann= 7 ,-1 , 0
  4346.9     .05       0  4758.4      .1       0  4779.3     .16       0
  4979.9     .07       0  4985.9     .16       0  5067.4      .1       0
  5840.1     .05       0
Bank Sta=4805.3,5097.8
XS Rating Curve= 0 ,0
Exp/Cntr=0.3,0.1

Type RM Length L Ch R = 1 ,83707   ,1125,1125,1125
BEGIN DESCRIPTION:
LAGARTO CREEK 67.0
END DESCRIPTION:
XS GIS Cut Line= 3
      2275632.15     13212174.44      2275587.71     13211810.04
      2274743.31     13210716.76
#Sta/Elev= 30
  4231.4  189.32  4337.2  189.06  4682.1  185.31  4716.1   185.1  4742.7  184.91
  4779.4  182.33  4815.2  176.59  4842.6  173.97  4885.8  170.78  4900.3   168.5
  4929.3  167.67  4943.7  164.93  4964.6  163.36  4990.6  156.57  4993.4  156.07
  4996.6  156.57  5006.9  157.82  5028.9  170.21  5035.2   173.1  5043.4   174.9
    5085  173.72  5184.7  177.94  5298.8  177.92  5342.3  176.62  5406.6  179.08
  5520.7  186.32  5605.8  188.35  5748.9  189.85  5829.2   192.3  5979.9  198.18
#Mann= 7 ,-1 , 0
  4231.4     .05       0  4337.2      .1       0  4682.1     .05       0
  4716.1      .1       0  4990.6     .07       0  4996.6      .1       0
  5829.2     .05       0
Bank Sta=4842.6,5043.4
XS Rating Curve= 0 ,0
Exp/Cntr=0.3,0.1

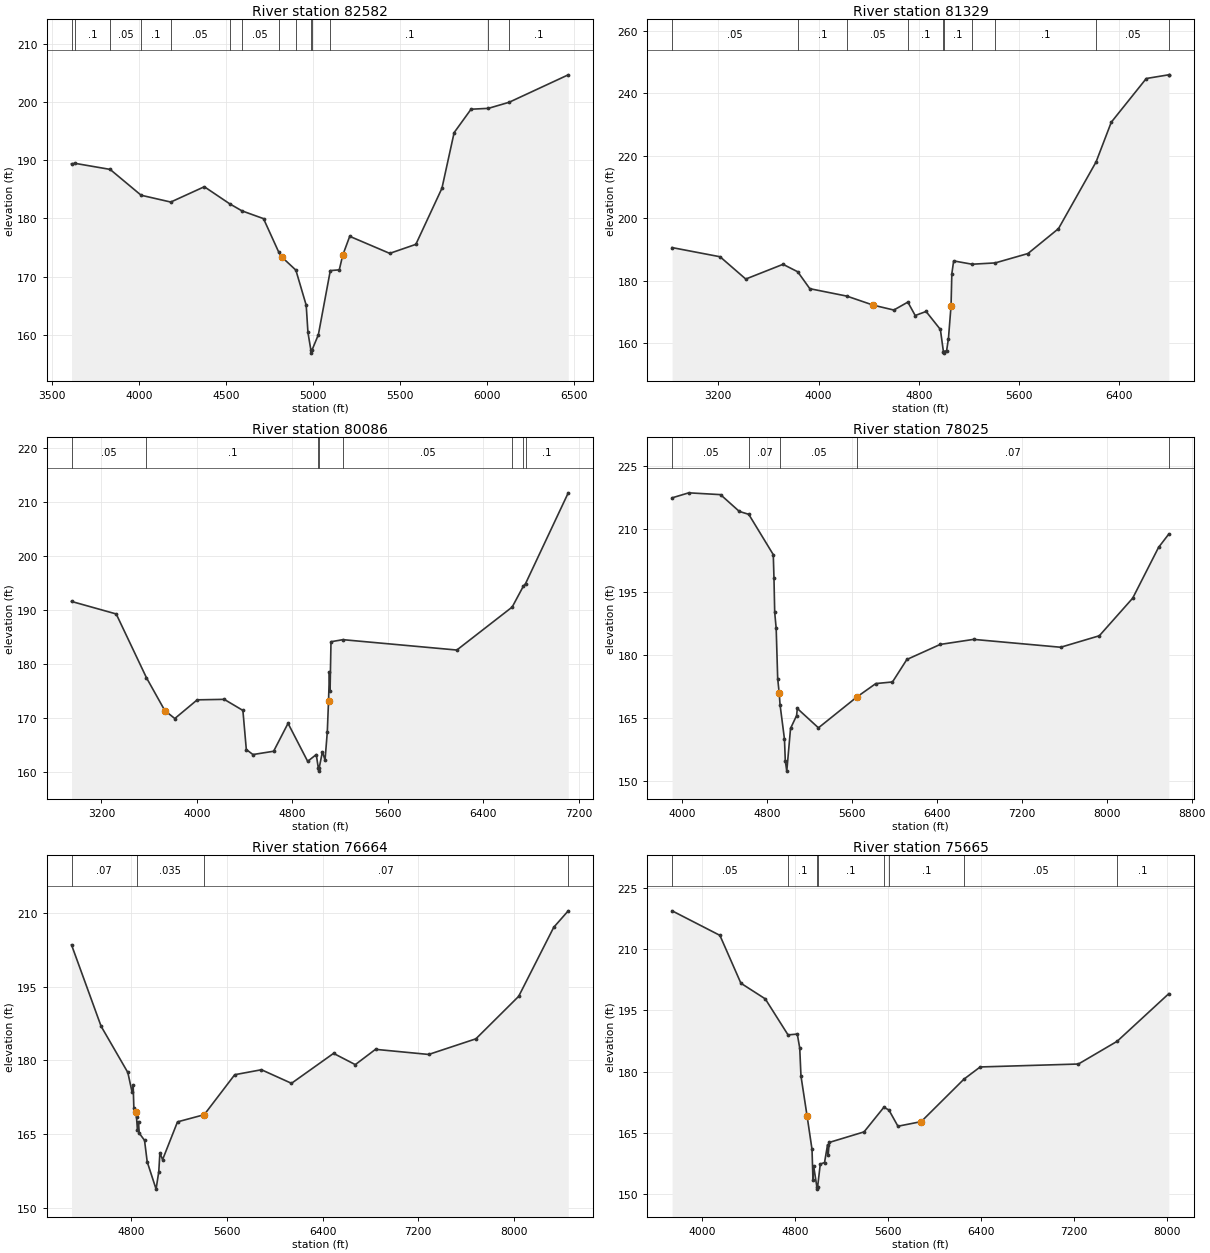
Type RM Length L Ch R = 1 ,82582   ,1253,1253,1253
BEGIN DESCRIPTION:
Mapping XS 0ba6cc29
END DESCRIPTION:
XS GIS Cut Line= 4
      2275729.93     13212218.89      2276272.11     13211650.04
      2276227.67     13210147.91      2275925.48     13209667.96
#Sta/Elev= 30
  3610.7  189.38    3631  189.45  3832.7  188.41  4010.9  183.97  4181.3   182.8
  4374.3  185.43    4520   182.5  4590.3  181.29  4714.5  179.95  4801.7  174.22
  4819.9  173.35  4900.6   171.1    4960  165.07    4970   160.4    4987  157.34
  4989.7  156.84    4993  157.34    5030  160.01  5098.5  171.02  5150.1  171.15
  5170.1  173.67  5210.1  176.91  5440.2  173.98  5590.3  175.53  5740.3  185.17
  5810.4  194.73  5907.6  198.75  6007.2   198.9  6126.2  199.94  6466.5  204.66
#Mann= 14 ,-1 , 0
  3610.7     .05       0    3631      .1       0  3832.7     .05       0
  4010.9      .1       0  4181.3     .05       0    4520      .1       0
  4590.3     .05       0  4801.7      .1       0  4900.6     .05       0
    4987     .04       0    4993     .05       0  5098.5      .1       0
  6007.2     .05       0  6126.2      .1       0
Bank Sta=4819.9,5170.1
XS Rating Curve= 0 ,0
Exp/Cntr=0.3,0.1

Type RM Length L Ch R = 1 ,81329   ,1243,1243,1243
BEGIN DESCRIPTION:
Mapping XS 9b3515bd
END DESCRIPTION:
XS GIS Cut Line= 4
      2275756.62     13212316.64      2276369.89     13211703.37
      2277703.14     13210672.33      2278547.53     13209543.51
#Sta/Elev= 30
  2832.2  190.57  3214.7  187.63  3419.7  180.49    3717  185.21  3834.1  182.82
  3930.7   177.4  4226.1  175.02  4436.9  172.12  4600.8  170.56  4712.6   173.1
  4771.3   168.8    4858   170.1  4972.1  164.33  4996.2  157.25    4999  156.75
  5002.2  157.25  5021.9  157.55  5036.4   161.4  5057.2  171.95  5063.5  182.21
    5078   186.3  5225.2  185.24  5409.7  185.66  5670.4  188.66  5914.2  196.64
  6214.3  218.04  6335.2  230.74  6614.5  244.75  6791.9  245.93  6794.6  245.93
#Mann= 10 ,-1 , 0
  2832.2     .05       0  3834.1      .1       0  4226.1     .05       0
  4712.6      .1       0  4996.2     .07       0  5002.2      .1       0
  5225.2     .05       0  5409.7      .1       0  6214.3     .05       0
  6791.9      .1       0
Bank Sta=4436.9,5057.2
XS Rating Curve= 0 ,0
Exp/Cntr=0.3,0.1

Type RM Length L Ch R = 1 ,80086   ,2061,2061,2061
BEGIN DESCRIPTION:
LAGARTO CREEK 66.0
END DESCRIPTION:
XS GIS Cut Line= 4
      2275712.13     13212423.34      2276672.09     13212121.13
      2278120.89     13211774.48      2279107.53      13210432.3
#Sta/Elev= 30
  2949.3  191.61  3323.9  189.29  3577.4  177.48    3731  171.41  3814.8  169.93
  4002.6  173.39  4228.8  173.48  4385.3  171.43  4413.9  164.19  4469.4  163.26
  4642.7  163.87  4763.5  169.04    4928     162    5000  163.26  5017.6  160.69
  5020.3  160.19  5023.6  160.69  5051.4  163.77  5073.5  162.24  5092.5  167.47
  5102.8   173.2  5110.4  178.59  5115.6  175.02  5123.4  184.15  5223.6  184.53
  6177.7  182.61  6641.4  190.57  6734.4  194.41  6753.4  194.91  7111.2  211.72
#Mann= 8 ,-1 , 0
  2949.3     .05       0  3577.4      .1       0  5017.6     .07       0
  5023.6      .1       0  5223.6     .05       0  6641.4      .1       0
  6734.4     .05       0  6753.4      .1       0
Bank Sta=3731,5102.8
XS Rating Curve= 0 ,0
Exp/Cntr=0.3,0.1

Type RM Length L Ch R = 1 ,78025   ,1361,1361,1361
BEGIN DESCRIPTION:
LAGARTO CREEK 65.0
END DESCRIPTION:
XS GIS Cut Line= 3
      2276227.64     13213978.82      2277560.92     13212858.86
      2279329.68     13210512.37
#Sta/Elev= 30
  3905.5  217.33  4062.5  218.52  4361.7  218.09  4538.6   214.1  4627.5  213.41
  4858.6  203.83  4865.1  198.25    4872  190.11  4885.9  186.31  4900.2  174.34
  4914.5   170.9  4922.3  168.18    4964  159.98  4971.8  154.84  4985.8  152.38
  5021.2  162.53  5078.4  165.59    5085  167.27    5284  162.67  5646.7  170.01
  5824.6  173.19  5981.6  173.57  6116.9  178.91  6431.2  182.49  6745.6  183.69
  7565.9  181.82  7930.2  184.55  8244.6  193.49  8488.1  205.55  8585.2  208.74
#Mann= 5 ,-1 , 0
  3905.5     .05       0  4627.5     .07       0  4922.3     .05       0
  5646.7     .07       0  8585.2      .1       0
Bank Sta=4914.5,5646.7
XS Rating Curve= 0 ,0
Exp/Cntr=0.3,0.1

Type RM Length L Ch R = 1 ,76664   ,999,999,999
BEGIN DESCRIPTION:
LAGARTO CREEK 64.0
END DESCRIPTION:
XS GIS Cut Line= 3
      2277840.28     13214190.17      2278660.59     13212549.56
      2279832.47     13210544.35
#Sta/Elev= 30
  4298.8  203.53  4546.6  186.96  4770.2  177.56  4805.6  173.58  4814.9  174.92
  4820.5  170.38  4837.2  169.47  4842.8  168.47  4850.3  165.93  4859.6  167.59
  4865.2  165.24  4909.9  163.76  4932.3  159.39  5006.6  153.84  5029.2  157.42
  5038.5  161.24  5060.9  159.83  5185.8  167.52  5409.4  168.98  5664.6  177.11
  5888.2  178.12  6139.6  175.36  6491.7  181.45  6673.6  179.16  6842.7  182.27
  7287.7  181.23  7682.8  184.41  8040.7  193.05  8334.1  207.09  8455.6  210.44
#Mann= 4 ,-1 , 0
  4298.8     .07       0  4842.8    .035       0  5409.4     .07       0
  8455.6      .1       0
Bank Sta=4837.2,5409.4
XS Rating Curve= 0 ,0
Exp/Cntr=0.3,0.1

Type RM Length L Ch R = 1 ,75665   ,1154,1154,1154
BEGIN DESCRIPTION:
LAGARTO CREEK 63.0
END DESCRIPTION:
XS GIS Cut Line= 4
      2278467.51     13214796.56      2278911.95     13214121.01
      2279543.03     13212263.34      2280165.23     13210894.49
#Sta/Elev= 30
  3743.4  219.42  4154.6   213.4  4335.3  201.66    4545  197.82  4740.8  188.99
  4820.5  189.18  4841.6  185.73  4852.1  178.91  4904.9  169.06  4947.2   160.9
  4955.5  153.29  4960.8   156.9  4989.2  151.65  4991.9  151.15  4995.2  151.65
  5018.3  157.29    5055  157.68  5081.1  162.07  5086.4  159.57  5095.1   162.6
  5394.9  165.19  5565.5  171.23  5608.8  170.56  5686.5  166.58  5886.6  167.71
  6254.2  178.12  6394.1  181.12  7239.4  181.84  7572.9  187.42  8017.6  199.11
#Mann= 8 ,-1 , 0
  3743.4     .05       0  4740.8      .1       0  4989.2     .07       0
  4995.2      .1       0  5565.5     .05       0  5608.8      .1       0
  6254.2     .05       0  7572.9      .1       0
Bank Sta=4904.9,5886.6
XS Rating Curve= 0 ,0
Exp/Cntr=0.3,0.1

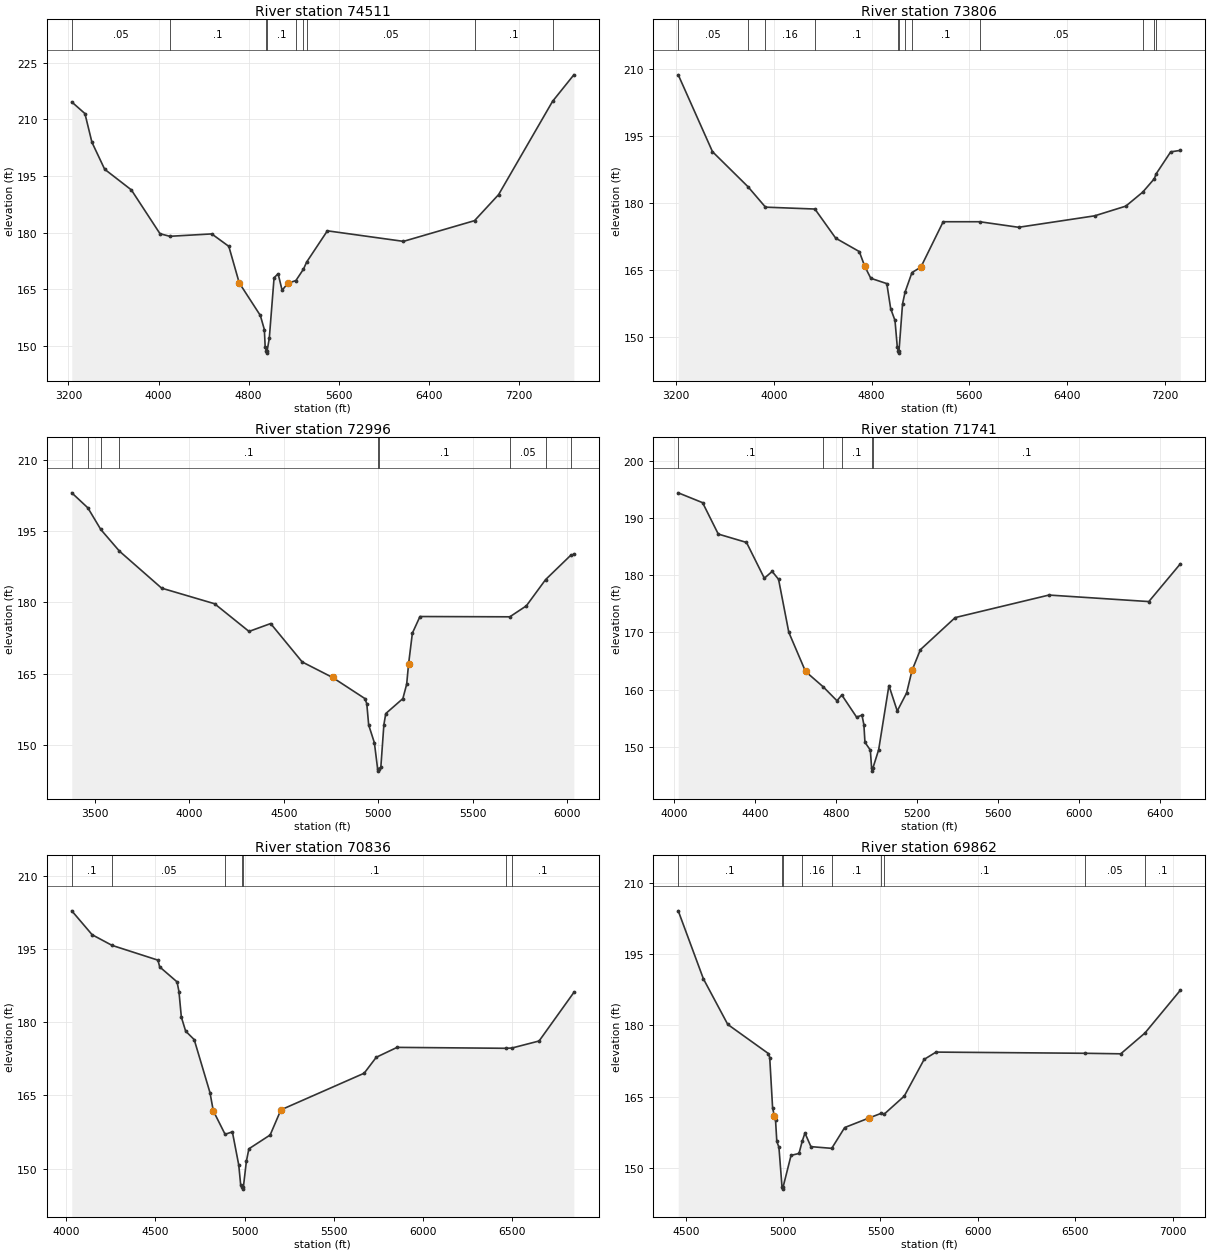
Type RM Length L Ch R = 1 ,74511   ,705,705,705
BEGIN DESCRIPTION:
LAGARTO CREEK 62.0
END DESCRIPTION:
XS GIS Cut Line= 4
       2278654.2     13214520.98      2279667.46     13214032.12
      2281080.71     13212014.47      2281640.68     13211347.84
#Sta/Elev= 30
  3229.6  214.57  3346.4   211.5  3408.6  203.91  3521.7  196.77  3758.9   191.3
  4013.2  179.71    4100  179.03  4472.7  179.66  4624.4  176.37  4716.8  166.71
  4904.2  158.09    4940  154.36  4947.1  149.86  4957.9  148.62  4960.7  148.12
  4963.9  148.62  4983.7     152  5026.3  168.06    5062  169.12  5097.8  164.75
  5148.3   166.6  5220.1  167.32  5287.4  170.34  5315.7  172.22  5499.7  180.48
  6175.3  177.69  6806.7  183.17  7020.3  190.06  7499.6  214.74  7688.6  221.75
#Mann= 9 ,-1 , 0
  3229.6     .05       0    4100      .1       0  4957.9     .07       0
  4963.9      .1       0  5220.1     .05       0  5287.4      .1       0
  5315.7     .05       0  6806.7      .1       0  7499.6     .05       0
Bank Sta=4716.8,5148.3
XS Rating Curve= 0 ,0
Exp/Cntr=0.3,0.1

Type RM Length L Ch R = 1 ,73806   ,810,810,810
BEGIN DESCRIPTION:
LAGARTO CREEK 61.0
END DESCRIPTION:
XS GIS Cut Line= 3
      2278746.47     13214616.61      2280946.98     13213757.24
      2282236.22     13212574.41
#Sta/Elev= 30
  3215.8  208.59  3496.3  191.41  3786.7  183.59  3930.3  179.01  4335.2  178.59
  4505.4  172.08  4698.6  169.08  4743.9  165.75  4792.8  163.11  4924.1  161.92
  4955.8  156.31    4991  153.69    5010   147.7  5017.9  146.88  5020.6  146.38
  5023.9  146.88  5052.9   157.4  5073.8  160.04    5130  164.39    5203   165.6
  5385.7  175.75  5685.1  175.75  6003.5  174.51  6626.2  177.07  6881.5  179.24
    7020  182.37  7115.1  185.37  7129.2  186.43    7249  191.37  7327.8   191.7
#Mann= 12 ,-1 , 0
  3215.8     .05       0  3786.7      .1       0  3930.3     .16       0
  4335.2      .1       0  5017.9     .07       0  5023.9      .1       0
  5073.8     .16       0    5130      .1       0  5685.1     .05       0
    7020      .1       0  7115.1     .05       0  7129.2      .1       0
Bank Sta=4743.9,5203
XS Rating Curve= 0 ,0
Exp/Cntr=0.3,0.1

Type RM Length L Ch R = 1 ,72996   ,1255,1255,1255
BEGIN DESCRIPTION:
LAGARTO CREEK 60.0
END DESCRIPTION:
XS GIS Cut Line= 2
      2278824.63     13214890.05      2281467.82     13214616.61
#Sta/Elev= 30
  3378.3  203.08  3463.3  199.92  3531.9  195.36  3630.9  190.78  3853.9     183
  4134.3  179.71  4316.4  173.88  4430.9  175.54  4597.9  167.45  4758.7  164.18
  4929.6  159.74  4939.7  158.66  4949.7  154.18  4979.9  150.43    4997  144.95
  4999.8  144.45    5003  144.95    5014  145.23  5030.2  154.24  5040.2  156.58
  5130.7  159.73  5150.8  162.76  5160.9  167.02    5181  173.52  5221.2  177.02
  5696.7  176.96  5784.2  179.27  5886.1   184.8  6020.6  189.98  6035.6   190.1
#Mann= 9 ,-1 , 0
  3378.3      .1       0  3463.3     .05       0  3531.9     .08       0
  3630.9      .1       0    4997     .07       0    5003      .1       0
  5696.7     .05       0  5886.1      .1       0  6020.6     .05       0
Bank Sta=4758.7,5160.9
XS Rating Curve= 0 ,0
Exp/Cntr=0.3,0.1

Type RM Length L Ch R = 1 ,71741   ,905,905,905
BEGIN DESCRIPTION:
LAGARTO CREEK 59.0
END DESCRIPTION:
XS GIS Cut Line= 4
       2279585.1     13216169.34      2280027.78     13216065.18
      2280756.94     13215882.89      2281316.85     13214737.04
#Sta/Elev= 30
  4019.6  194.41    4140  192.69  4217.5   187.2    4357  185.74  4445.2  179.48
  4483.8  180.67  4515.5  179.29  4566.2  170.02  4648.7  163.19    4737  160.47
  4804.2  158.06  4828.1  159.07  4901.2   155.2  4927.8  155.54  4937.3  153.86
  4942.5   150.8  4969.1  149.43  4975.5  146.26  4978.3  145.76  4981.5  146.26
  5010.3   149.5    5061  160.72  5102.2  156.27  5148.6  159.44  5175.2  163.36
  5216.5  166.99  5388.5   172.6  5852.3  176.54  6345.7   175.4  6501.3  181.99
#Mann= 5 ,-1 , 0
  4019.6      .1       0    4737     .16       0  4828.1      .1       0
  4975.5     .07       0  4981.5      .1       0
Bank Sta=4648.7,5175.2
XS Rating Curve= 0 ,0
Exp/Cntr=0.3,0.1

Type RM Length L Ch R = 1 ,70836   ,974,974,974
BEGIN DESCRIPTION:
LAGARTO CREEK 58.0
END DESCRIPTION:
XS GIS Cut Line= 3
       2280671.7     13217442.45      2281037.72     13216546.85
      2281437.72     13214746.86
#Sta/Elev= 30
  4032.5  202.92  4146.6  198.01  4257.8  195.83  4515.1  192.79  4524.7  191.41
    4622  188.33  4632.7  186.34    4646  181.12  4670.1  178.22  4718.1  176.47
  4806.4  165.59    4825  161.85    4891  157.03  4931.8  157.53  4967.6  150.71
  4978.4   146.6  4987.7  146.27  4990.4  145.77  4993.7  146.27  5010.2  151.48
  5024.3  154.05  5143.4  156.89  5203.6  162.05  5669.7  169.57  5737.6  172.85
  5854.1  174.88  6462.6  174.69  6497.5  174.75  6649.3  176.19  6843.9  186.16
#Mann= 7 ,-1 , 0
  4032.5      .1       0  4257.8     .05       0    4891      .1       0
  4987.7     .07       0  4993.7      .1       0  6462.6     .05       0
  6497.5      .1       0
Bank Sta=4825,5203.6
XS Rating Curve= 0 ,0
Exp/Cntr=0.3,0.1

Type RM Length L Ch R = 1 ,69862   ,986,986,986
BEGIN DESCRIPTION:
LAGARTO CREEK 57.0
END DESCRIPTION:
XS GIS Cut Line= 3
      2282087.71     13217246.84      2281887.72     13216746.86
      2281487.72     13214746.86
#Sta/Elev= 30
  4461.5  204.07  4590.7  189.78  4715.9  180.19  4924.6  174.07  4931.3  173.22
  4946.1  162.59  4955.6  160.94    4961  160.18  4967.7  155.59  4978.5  154.39
  4994.3  146.08  4997.1  145.58  5000.3  146.08  5040.8  152.67  5081.6  153.08
  5098.6  155.72  5112.2  157.37  5142.8  154.51  5249.7  154.15  5316.1  158.52
  5438.5  160.49  5501.7  161.48  5520.4  161.39  5622.1  165.13  5724.1  172.84
  5785.2  174.38  6551.5  174.13  6733.7  174.02  6857.8  178.38  7039.6  187.37
#Mann= 9 ,-1 , 0
  4461.5      .1       0  4994.3     .07       0  5000.3      .1       0
  5098.6     .16       0  5249.7      .1       0  5501.7     .16       0
  5520.4      .1       0  6551.5     .05       0  6857.8      .1       0
Bank Sta=4955.6,5438.5
XS Rating Curve= 0 ,0
Exp/Cntr=0.3,0.1

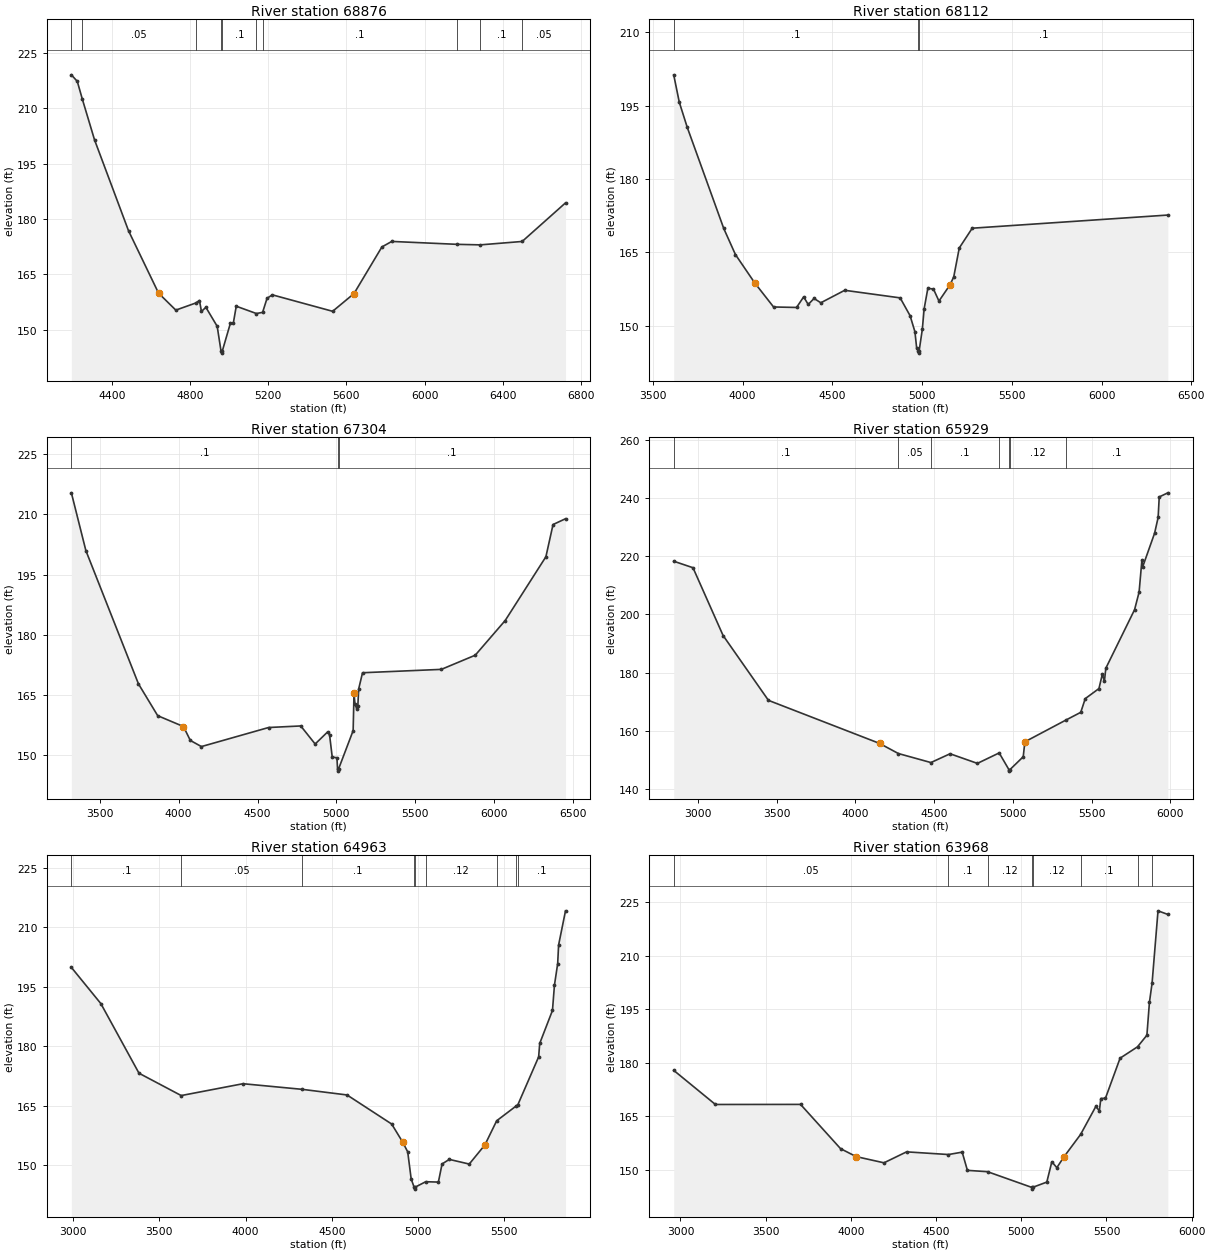
Type RM Length L Ch R = 1 ,68876   ,764,764,764
BEGIN DESCRIPTION:
LAGARTO CREEK 56.0
END DESCRIPTION:
XS GIS Cut Line= 3
      2282687.72     13216996.83      2282587.72     13216196.85
       2281587.7     13214796.83
#Sta/Elev= 30
  4193.8  219.11    4224  217.34  4249.7  212.54  4312.2  201.47    4486   176.8
  4639.7  159.86  4727.9  155.26  4830.2   157.2  4848.8  157.87  4858.9  154.89
  4881.6  156.02  4939.5  150.86  4959.2  144.09    4962  143.59  4965.2  144.09
  5007.4  151.78  5022.1  151.79  5036.9  156.32  5139.7  154.34  5171.6  154.65
  5194.2  158.45  5221.2  159.41  5529.7  154.94    5639  159.75  5781.6   172.4
    5832   173.9  6167.5  173.11    6285  172.97  6498.9  173.89  6720.5  184.36
#Mann= 10 ,-1 , 0
  4193.8      .1       0  4249.7     .05       0  4830.2      .1       0
  4959.2     .07       0  4965.2      .1       0  5139.7     .16       0
  5171.6      .1       0  6167.5     .05       0    6285      .1       0
  6498.9     .05       0
Bank Sta=4639.7,5639
XS Rating Curve= 0 ,0
Exp/Cntr=0.3,0.1

Type RM Length L Ch R = 1 ,68112   ,808,808,808
BEGIN DESCRIPTION:
Mapping XS 27d38863
END DESCRIPTION:
XS GIS Cut Line= 5
      2282876.57     13216964.98      2282989.41     13216721.94
      2283163.02     13216166.39      2282902.61     13215098.68
       2282182.4     13214742.91
#Sta/Elev= 30
  3616.4  201.28  3647.4  195.69  3691.5  190.57  3895.2  169.85  3960.1  164.53
  4068.1   158.7  4172.6   153.8  4300.6   153.7  4340.2  155.86  4365.6  154.31
  4398.1  155.54  4435.8  154.66  4568.9  157.21  4877.7  155.66  4933.1  152.01
    4960  148.73  4969.6  145.41  4977.6  144.86  4980.3  144.36  4983.6  144.86
  5001.2  149.24  5011.3  153.43    5032  157.62  5063.3  157.46  5093.8  155.01
  5155.6  158.34  5176.2  159.96    5207  165.87  5279.1  169.91  6368.7   172.6
#Mann= 3 ,-1 , 0
  3616.4      .1       0  4977.6     .07       0  4983.6      .1       0
Bank Sta=4068.1,5155.6
XS Rating Curve= 0 ,0
Exp/Cntr=0.3,0.1

Type RM Length L Ch R = 1 ,67304   ,1375,1375,1375
BEGIN DESCRIPTION:
LAGARTO CREEK 55.0
END DESCRIPTION:
XS GIS Cut Line= 4
      2282853.29     13217080.82      2283621.53     13216104.24
      2283960.07     13215244.87      2284806.44     13214776.11
#Sta/Elev= 30
  3319.6  215.36  3411.5  200.97    3745  167.75    3867  159.82  4030.6  157.11
  4073.9  153.65  4144.4  152.12  4570.4  156.87  4774.3  157.26  4865.6  152.76
  4944.1  155.75    4957  155.04  4973.9  149.52  5003.7  149.32  5007.7   146.5
  5010.5     146  5013.7   146.5  5106.6   156.1    5112  165.37  5118.2  162.71
    5129  161.55  5136.3  162.29  5141.7  166.49  5166.1  170.52    5666  171.36
  5880.8  174.89  6070.9  183.54    6329  199.43  6374.3  207.46  6453.3   208.9
#Mann= 3 ,-1 , 0
  3319.6      .1       0  5007.7     .07       0  5013.7      .1       0
Bank Sta=4030.6,5112
XS Rating Curve= 0 ,0
Exp/Cntr=0.3,0.1

Type RM Length L Ch R = 1 ,65929   ,966,966,966
BEGIN DESCRIPTION:
LAGARTO CREEK 54.0
END DESCRIPTION:
XS GIS Cut Line= 3
      2282787.69     13217246.87      2284787.72     13216446.86
      2285687.73     13216046.85
#Sta/Elev= 30
  2845.9  218.28  2968.4  216.04  3159.6  192.73  3447.7  170.43  4153.2  155.63
  4273.1  152.14  4479.8  149.04  4601.5  152.06  4775.2  148.75  4913.4  152.35
  4975.5  146.59  4978.2  146.09  4981.5  146.59  5066.3  151.04  5076.6  156.17
  5338.3  163.68  5431.6  166.31  5460.3  171.03  5547.2  174.48    5569  179.47
    5582  176.95  5590.9  181.47  5773.5   201.6  5802.3  207.64  5820.1  218.63
  5825.5  216.41  5900.8  227.92  5923.3  233.35  5930.2  240.39  5984.9   241.8
#Mann= 7 ,-1 , 0
  2845.9      .1       0  4273.1     .05       0  4479.8      .1       0
  4913.4     .12       0  4975.5     .07       0  4981.5     .12       0
  5338.3      .1       0
Bank Sta=4153.2,5076.6
XS Rating Curve= 0 ,0
Exp/Cntr=0.3,0.1

Type RM Length L Ch R = 1 ,64963   ,995,995,995
BEGIN DESCRIPTION:
LAGARTO CREEK 53.0
END DESCRIPTION:
XS GIS Cut Line= 3
       2283087.7     13217446.86      2285087.72     13217246.86
      2285887.72     13216946.86
#Sta/Elev= 30
    2990  199.91  3160.9  190.77    3382  173.19  3626.7  167.55    3985  170.54
  4328.1  169.12    4588   167.7  4846.7  160.36  4909.6  155.86  4939.7  153.33
  4959.8  146.48  4976.9  144.42  4979.7  143.92  4982.9  144.42    5044  145.79
  5117.5   145.7  5138.8  150.27  5180.7  151.43  5296.4  150.25  5387.2  155.09
  5455.4  161.18  5565.8  164.83    5578  165.21  5698.7  177.32  5704.9  180.71
  5778.8  189.04  5790.3  195.42    5809  200.85  5814.4  205.57  5854.4   214.2
#Mann= 9 ,-1 , 0
    2990      .1       0  3626.7     .05       0  4328.1      .1       0
  4976.9     .07       0  4982.9      .1       0    5044     .12       0
  5455.4      .1       0  5565.8     .12       0    5578      .1       0
Bank Sta=4909.6,5387.2
XS Rating Curve= 0 ,0
Exp/Cntr=0.3,0.1

Type RM Length L Ch R = 1 ,63968   ,691,691,691
BEGIN DESCRIPTION:
LAGARTO CREEK 52.0
END DESCRIPTION:
XS GIS Cut Line= 3
      2283487.73     13218346.85      2285487.72     13217946.85
      2286187.69     13217446.87
#Sta/Elev= 30
  2960.4  177.91  3205.1  168.35  3704.8  168.37  3939.4  155.98  4031.2  153.75
  4194.4  152.01  4326.9  155.08  4572.9  154.33  4653.3     155  4683.9   149.9
  4802.2  149.52  5060.9  145.14  5063.7  144.64  5066.9  145.14  5149.9  146.61
  5179.4   152.3  5208.9  150.65  5250.7   153.7  5348.3  159.96  5437.5  167.79
  5458.4  166.57    5467  170.02    5494  170.09    5580  181.32  5682.2   184.5
  5737.3  187.75  5752.1  196.93  5767.7  202.34  5802.5  222.59  5860.2  221.58
#Mann= 8 ,-1 , 0
  2960.4     .05       0  4572.9      .1       0  4802.2     .12       0
  5060.9     .07       0  5066.9     .12       0  5348.3      .1       0
  5682.2     .05       0  5767.7      .1       0
Bank Sta=4031.2,5250.7
XS Rating Curve= 0 ,0
Exp/Cntr=0.3,0.1

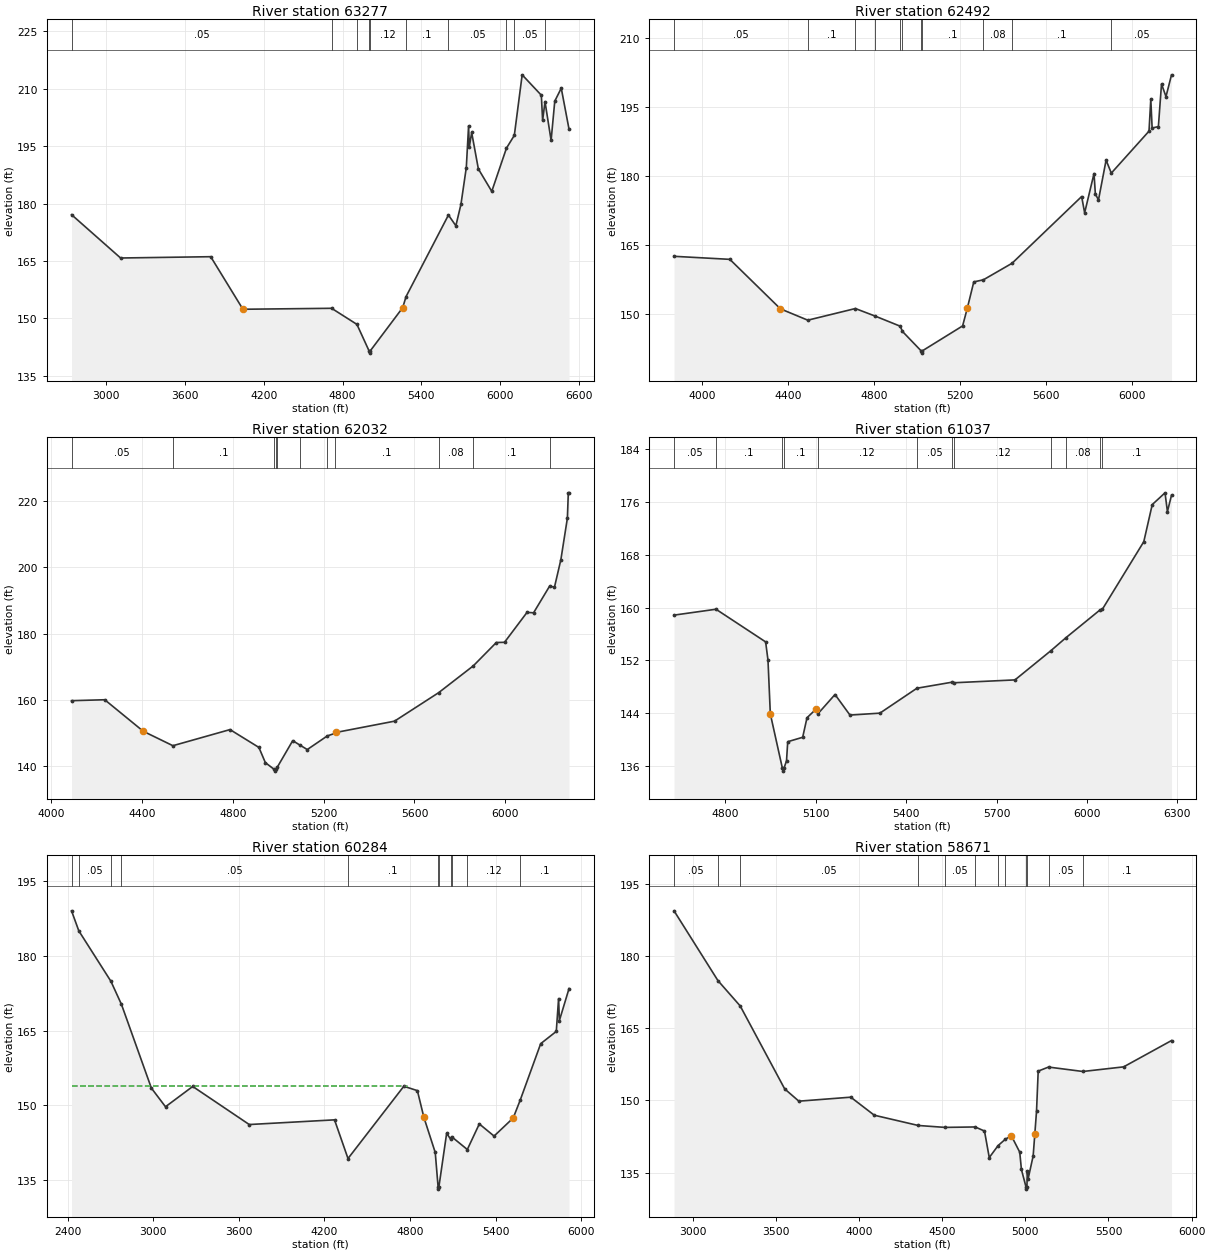
Type RM Length L Ch R = 1 ,63277   ,785,785,785
BEGIN DESCRIPTION:
Mapping XS fc340167
END DESCRIPTION:
XS GIS Cut Line= 6
      2283397.61     13218856.97      2284460.93     13218998.02
      2286142.79     13218227.62        2286273.     13217576.58
        2286273.     13217554.88      2286316.32     13217381.59
#Sta/Elev= 30
    2737  177.09  3110.4  165.77  3796.3  166.11  4041.6  152.38  4716.7  152.63
  4909.3  148.43  5002.8  141.42  5005.5  140.92  5008.8  141.42    5258  152.81
  5283.2  155.68  5605.9  176.99  5662.5  174.19  5701.1  179.78  5741.9   189.4
  5759.2  200.29  5764.3  194.68  5782.7  198.56  5833.7  189.03  5935.7  183.18
  6047.7  194.48  6107.4   197.8  6167.1  213.62    6313  208.29  6322.8  201.72
  6340.9  206.62  6387.4  196.48  6415.3  206.75  6464.7  210.13  6523.8  199.42
#Mann= 10 ,-1 , 0
    2737     .05       0  4716.7      .1       0  4909.3     .12       0
  5002.8     .07       0  5008.8     .12       0  5283.2      .1       0
  5605.9     .05       0  6047.7      .1       0  6107.4     .05       0
  6340.9      .1       0
Bank Sta=4041.6,5258
XS Rating Curve= 0 ,0
Exp/Cntr=0.3,0.1

Type RM Length L Ch R = 1 ,62492   ,460,460,460
BEGIN DESCRIPTION:
LAGARTO CREEK 51.0
END DESCRIPTION:
XS GIS Cut Line= 3
      2284708.37     13219761.89      2286037.36     13218996.93
      2286661.45     13218524.93
#Sta/Elev= 30
    3870  162.51  4129.8  161.85  4365.4  151.09  4492.6  148.63  4714.2  151.16
  4807.8  149.49    4923  147.32  4933.2  146.19  5020.1  141.97  5022.8  141.47
  5026.1  141.97  5213.3  147.38  5234.9  151.17  5265.4  156.95  5309.9   157.4
  5443.6     161  5767.5   175.5  5781.4  171.96  5825.1   180.5  5831.4  176.04
  5845.9  174.76  5881.3  183.41  5905.6  180.59  6081.1  189.71  6089.4  196.65
  6095.6  190.39  6124.7   190.7  6139.3  199.96  6160.1  197.22  6185.9  201.95
#Mann= 11 ,-1 , 0
    3870     .05       0  4492.6      .1       0  4714.2     .05       0
  4807.8      .1       0    4923     .05       0  4933.2      .1       0
  5020.1     .07       0  5026.1      .1       0  5309.9     .08       0
  5443.6      .1       0  5905.6     .05       0
Bank Sta=4365.4,5234.9
XS Rating Curve= 0 ,0
Exp/Cntr=0.3,0.1

Type RM Length L Ch R = 1 ,62032   ,995,995,995
BEGIN DESCRIPTION:
LAGARTO CREEK 50.0
END DESCRIPTION:
XS GIS Cut Line= 3
      2285194.32     13220240.25      2285837.72     13219596.85
       2286837.7     13218796.87
#Sta/Elev= 30
  4090.1  159.81  4236.3  160.09    4406  150.58  4536.4  146.23  4787.9  151.09
  4915.1  145.71  4943.4  141.13  4982.9  139.06  4985.6  138.56  4988.9  139.06
  4995.3  139.66    5064  147.75  5096.9  146.36  5128.1  145.07  5216.7   149.2
  5249.4  149.94  5256.1  150.25  5512.2  153.63  5706.8  162.24  5859.3  170.33
  5960.5  177.36  5996.5  177.42  6095.7  186.45  6124.5  186.32  6194.8  194.33
  6216.6  194.08  6244.6  202.32  6273.4  214.88  6277.4  222.51  6280.6  222.51
#Mann= 11 ,-1 , 0
  4090.1     .05       0  4536.4      .1       0  4982.9     .07       0
  4988.9      .1       0  4995.3     .12       0  5096.9      .1       0
  5216.7     .05       0  5249.4      .1       0  5706.8     .08       0
  5859.3      .1       0  6194.8     .05       0
Bank Sta=4406,5256.1
XS Rating Curve= 0 ,0
Exp/Cntr=0.3,0.1

Type RM Length L Ch R = 1 ,61037   ,753,753,753
BEGIN DESCRIPTION:
LAGARTO CREEK 49.0
END DESCRIPTION:
XS GIS Cut Line= 3
      2286247.36     13220514.13      2286437.72     13220196.86
       2287237.7     13219196.87
#Sta/Elev= 30
    4630  158.85  4769.2  159.74  4933.9   154.8  4941.7  152.05  4949.5   143.9
  4989.2  135.75    4992  135.25  4995.2  135.75  5003.2  136.81  5007.2   139.7
  5056.8  140.37  5071.2  143.33    5100  144.58  5106.5  143.88  5164.1  146.84
  5213.7  143.73    5313  144.02  5435.9  147.79  5553.1  148.71  5559.5  148.62
  5761.2  149.05  5879.3  153.43  5930.2  155.43  6042.4   159.6  6051.2  159.74
  6188.6  169.96  6216.6  175.57    6259  177.35    6267  174.51  6280.6     177
#Mann= 12 ,-1 , 0
    4630     .05       0  4769.2      .1       0  4989.2     .07       0
  4995.2      .1       0  5106.5     .12       0  5435.9     .05       0
  5553.1      .1       0  5559.5     .12       0  5879.3     .05       0
  5930.2     .08       0  6042.4     .12       0  6051.2      .1       0
Bank Sta=4949.5,5100
XS Rating Curve= 0 ,0
Exp/Cntr=0.3,0.1

Type RM Length L Ch R = 1 ,60284   ,1613,1613,1613
BEGIN DESCRIPTION:
LAGARTO CREEK 48.0
END DESCRIPTION:
XS GIS Cut Line= 3
      2285565.47     13222255.87      2286586.27     13221242.01
      2287565.44      13219443.4
#Sta/Elev= 30
  2428.2  189.06  2479.1  185.04    2704  174.91  2778.2  170.25  2987.7  153.44
  3086.7  149.69  3277.6  153.77  3673.6  146.12  4271.3  147.06  4365.8  139.29
    4757  153.81    4852  152.93  4897.5  147.57  4977.2   140.5    4997  133.64
  4999.8  133.14    5003  133.64  5057.1  144.36  5084.7  143.18  5091.3  143.69
    5202   141.1    5286  146.24  5389.5   143.8  5523.7  147.44  5573.4  151.08
  5716.3  162.37  5825.5  164.83  5841.6  171.43  5847.3  167.02  5914.8  173.44
#Mann= 11 ,-1 , 0
  2428.2      .1       0  2479.1     .05       0    2704     .08       0
  2778.2     .05       0  4365.8      .1       0    4997     .07       0
    5003      .1       0  5084.7     .12       0  5091.3     .05       0
    5202     .12       0  5573.4      .1       0
#XS Ineff= 2 , 0
         4778.72  153.87
Permanent Ineff=
       F       F
Bank Sta=4897.5,5523.7
XS Rating Curve= 0 ,0
Exp/Cntr=0.3,0.1

Type RM Length L Ch R = 1 ,58671   ,816,816,816
BEGIN DESCRIPTION:
LAGARTO CREEK 47.0
END DESCRIPTION:
XS GIS Cut Line= 4
      2285627.94     13222436.45      2286600.16     13221582.29
      2287634.88      13221443.4      2287967.91     13220881.41
#Sta/Elev= 30
  2887.6  189.42  3151.5  174.92  3285.6  169.64  3552.9  152.41  3638.2  149.86
  3950.3  150.69  4091.7  146.94  4355.7  144.81  4516.5  144.41  4698.6   144.5
  4754.4  143.65    4783  138.14  4836.2  140.63    4879  141.93  4915.8  142.68
  4966.3  139.26  4976.4  135.67  5003.6  132.08  5006.4  131.58  5009.6  132.08
  5011.8  135.41  5016.8  133.72    5047  138.48  5057.1  143.08  5067.2  147.75
  5077.3  156.11  5139.4  156.95  5345.9  156.03    5591  156.99    5879  162.46
#Mann= 12 ,-1 , 0
  2887.6     .05       0  3151.5     .08       0  3285.6     .05       0
  4355.7      .1       0  4516.5     .05       0  4698.6      .1       0
  4836.2     .12       0    4879      .1       0  5003.6     .07       0
  5009.6      .1       0  5139.4     .05       0  5345.9      .1       0
Bank Sta=4915.8,5057.1
XS Rating Curve= 0 ,0
Exp/Cntr=0.3,0.1