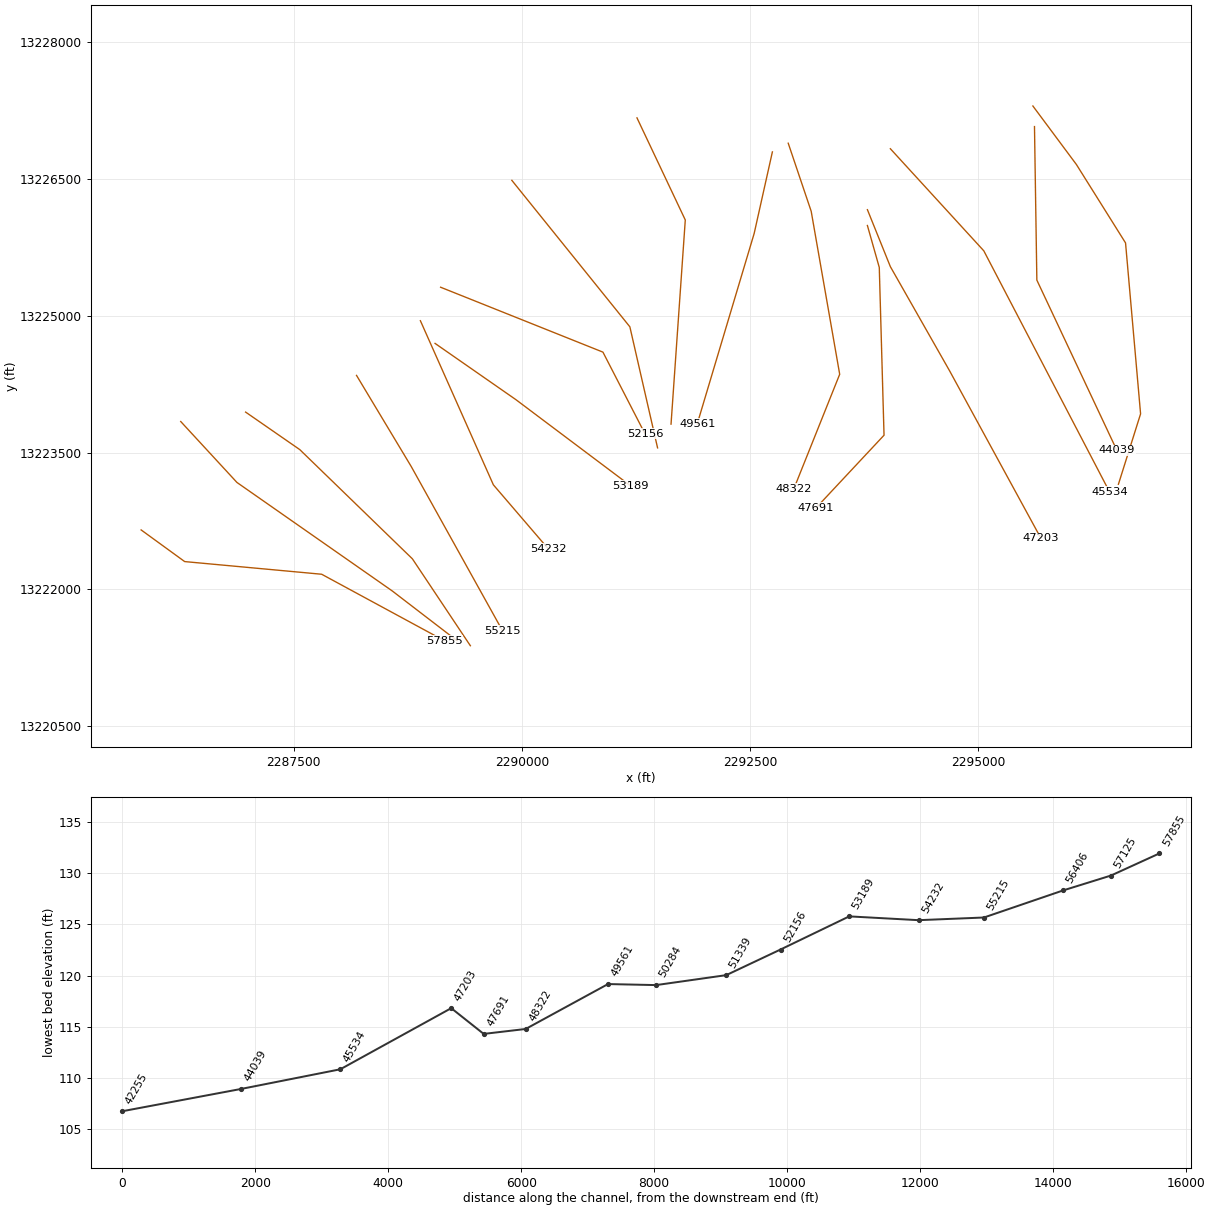
HEC-RAS study LAGARTO CREEK.prj: LAGARTO CREEK Base Level Engineering

--- LAGARTO CREEK.g01 (geometry) --- (continued)

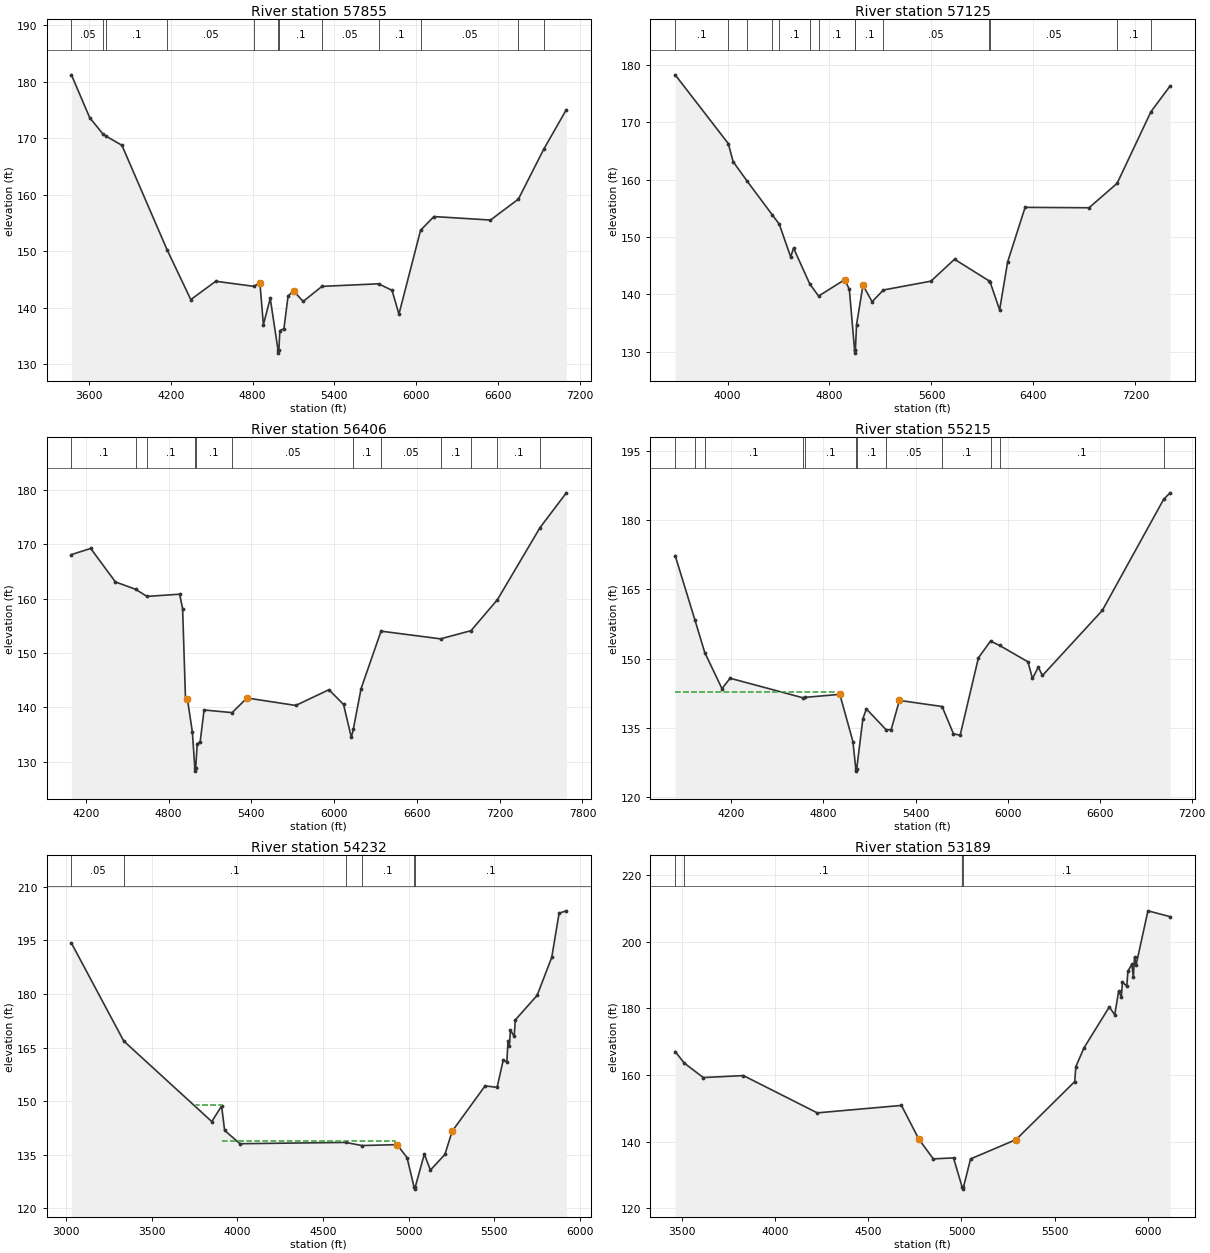
Type RM Length L Ch R = 1 ,57855   ,730,730,730
BEGIN DESCRIPTION:
LAGARTO CREEK 46.0
END DESCRIPTION:
XS GIS Cut Line= 4
      2285826.42     13222651.93      2286303.85      13222304.7
      2287805.59     13222165.81      2289151.11     13221436.63
#Sta/Elev= 30
  3471.8  181.21  3605.6  173.64    3705  170.67  3723.4  170.38  3842.1  168.73
  4172.9  150.25  4347.2   141.4  4530.2  144.65  4810.2  143.75  4853.8   144.4
  4879.5  136.96  4929.7  141.64    4987  132.42  4989.7  131.92    4993  132.42
    5000  135.89  5030.1  136.26  5060.3  142.02  5100.4  142.95  5170.7  141.07
  5308.8  143.74  5723.8   144.2  5822.9  143.04  5873.3  138.82    6032  153.68
    6130  156.11  6544.6  155.49  6749.2   159.2  6934.9  168.03  7100.7  175.04
#Mann= 12 ,-1 , 0
  3471.8     .05       0    3705     .08       0  3723.4      .1       0
  4172.9     .05       0  4810.2      .1       0    4987     .07       0
    4993      .1       0  5308.8     .05       0  5723.8      .1       0
    6032     .05       0  6749.2      .1       0  6934.9     .05       0
Bank Sta=4853.8,5100.4
XS Rating Curve= 0 ,0
Exp/Cntr=0.3,0.1

Type RM Length L Ch R = 1 ,57125   ,719,719,719
BEGIN DESCRIPTION:
LAGARTO CREEK 45.0
END DESCRIPTION:
XS GIS Cut Line= 4
      2286260.43     13223841.18      2286876.77     13223172.76
      2288578.16     13221983.52        2289290.     13221436.62
#Sta/Elev= 30
  3589.4  178.29  4006.4  166.29  4043.7  163.16  4153.7  159.76  4352.5  153.83
  4405.9  152.25  4495.6  146.53  4517.9  148.08  4645.2  141.83  4714.5  139.71
  4919.9  142.58  4955.7  140.87    4997  130.26  4999.7  129.76    5003  130.26
  5012.3  134.75  5062.9   141.6  5134.4  138.72  5222.4  140.77  5595.8  142.31
  5780.8  146.13  6050.4  142.38    6061  142.09  6134.7   137.3  6197.5  145.66
  6334.5  155.18  6836.1  155.11  7056.5  159.37  7321.6  171.85  7472.1  176.35
#Mann= 14 ,-1 , 0
  3589.4      .1       0  4006.4     .05       0  4153.7      .1       0
  4352.5     .08       0  4405.9      .1       0  4645.2     .05       0
  4714.5      .1       0    4997     .07       0    5003      .1       0
  5222.4     .05       0  6050.4      .1       0    6061     .05       0
  7056.5      .1       0  7321.6     .05       0
Bank Sta=4919.9,5062.9
XS Rating Curve= 0 ,0
Exp/Cntr=0.3,0.1

Type RM Length L Ch R = 1 ,56406   ,1191,1191,1191
BEGIN DESCRIPTION:
Mapping XS eb1ac4cd
END DESCRIPTION:
XS GIS Cut Line= 4
      2286971.86     13223944.43      2287565.57       13223533.
      2288799.95     13222335.08      2289435.35     13221381.99
#Sta/Elev= 30
    4095  168.07  4234.9   169.2    4414  163.05    4561  161.69  4643.1  160.39
  4879.7   160.8  4901.1  158.16  4922.2   141.5  4936.3   141.5  4971.8   135.5
  4989.9  128.81  4992.7  128.31  4995.9  128.81  5007.1  133.32  5028.4  133.69
  5056.7  139.54  5260.1  139.05  5367.7  141.74  5721.4  140.37  5961.9  143.26
  6067.9  140.55  6124.4  134.49  6138.3  135.96  6195.2  143.48  6339.6  154.01
  6770.8   152.6  6991.9   154.1  7183.6   159.8  7492.4  173.03  7682.9  179.41
#Mann= 12 ,-1 , 0
    4095      .1       0    4561     .08       0  4643.1      .1       0
  4989.9     .07       0  4995.9      .1       0  5260.1     .05       0
  6138.3      .1       0  6339.6     .05       0  6770.8      .1       0
  6991.9     .05       0  7183.6      .1       0  7492.4     .05       0
Bank Sta=4936.3,5367.7
XS Rating Curve= 0 ,0
Exp/Cntr=0.3,0.1

Type RM Length L Ch R = 1 ,55215   ,983,983,983
BEGIN DESCRIPTION:
LAGARTO CREEK 43.0
END DESCRIPTION:
XS GIS Cut Line= 3
      2288187.72     13224346.86      2288787.72     13223346.85
      2289787.71     13221546.88
#Sta/Elev= 30
  3833.8  172.31  3962.6  158.35  4026.5  151.33    4139   143.5  4191.4  145.77
  4663.9  141.56    4678  141.62  4906.7  142.28  4992.2  132.06  5010.7  126.17
  5013.5  125.67  5016.7  126.17  5057.2  137.04  5080.1  139.12  5209.2   134.6
  5241.4  134.65  5295.1  140.97  5573.2  139.65  5647.5  133.73    5691  133.45
  5809.9  150.18  5888.8   153.8    5948  152.86  6132.5  149.32  6162.3  145.71
    6200  148.15  6227.5  146.37  6617.6  160.45  7017.3  184.49  7059.1  185.88
#Mann= 12 ,-1 , 0
  3833.8      .1       0  3962.6     .05       0  4026.5      .1       0
  4663.9     .16       0    4678      .1       0  5010.7     .07       0
  5016.7      .1       0  5209.2     .05       0  5573.2      .1       0
  5888.8     .05       0    5948      .1       0  7017.3     .05       0
#XS Ineff= 2 , 0
         4868.81  142.85
Permanent Ineff=
       F       F
Bank Sta=4906.7,5295.1
XS Rating Curve= 0 ,0
Exp/Cntr=0.3,0.1

Type RM Length L Ch R = 1 ,54232   ,1043,1043,1043
BEGIN DESCRIPTION:
LAGARTO CREEK 42.0
END DESCRIPTION:
XS GIS Cut Line= 3
      2288887.71     13224946.88      2289687.72     13223146.86
      2290287.75     13222446.82
#Sta/Elev= 30
  3030.2  194.27  3335.9  166.86  3850.3  144.32  3907.7  148.66  3925.5  141.84
  4015.1  138.12  4631.7  138.48  4727.4  137.61  4933.7  137.86  4991.1  134.22
  5032.7  125.91  5035.4  125.41  5038.7  125.91  5092.2   135.2  5127.9  130.74
  5212.4  135.11  5255.2  141.63  5447.3   154.3  5517.5   153.9  5553.2   161.5
  5574.6  161.02  5581.2  166.95  5588.8  165.39  5595.4  169.87  5617.4  168.19
    5624  172.77  5751.3  179.62  5836.9  190.29  5879.7  202.63    5922  203.29
#Mann= 6 ,-1 , 0
  3030.2     .05       0  3335.9      .1       0  4631.7     .16       0
  4727.4      .1       0  5032.7     .07       0  5038.7      .1       0
#XS Ineff= 2 ,-1
 3907.86 4923.83  138.86 3756.83 3907.86  148.83
Permanent Ineff=
       F       F
Bank Sta=4933.7,5255.2
XS Rating Curve= 0 ,0
Exp/Cntr=0.3,0.1

Type RM Length L Ch R = 1 ,53189   ,1033,1033,1033
BEGIN DESCRIPTION:
LAGARTO CREEK 41.0
END DESCRIPTION:
XS GIS Cut Line= 3
      2289048.65     13224697.88      2289934.09     13224081.55
      2291192.71     13223135.42
#Sta/Elev= 30
  3465.3  167.03  3514.4  163.54  3616.2  159.22  3830.9  159.82  4227.1  148.64
  4678.4  150.87  4772.1  140.71  4849.2  134.85  4957.5  135.14  5004.4  126.28
  5007.2  125.78  5010.4  126.28  5049.1  134.84  5292.8  140.63  5607.3  158.01
  5613.5  162.51  5657.2  168.14  5792.6  180.38  5821.8  178.04  5842.6  185.06
  5857.2  183.42  5863.4  187.83  5886.3  186.62  5892.6  191.09  5913.4  193.18
  5921.7  189.35    5928  195.36  5936.3  192.95  5999.9   209.2  6118.7  207.45
#Mann= 4 ,-1 , 0
  3465.3     .05       0  3514.4      .1       0  5004.4     .07       0
  5010.4      .1       0
Bank Sta=4772.1,5292.8
XS Rating Curve= 0 ,0
Exp/Cntr=0.3,0.1

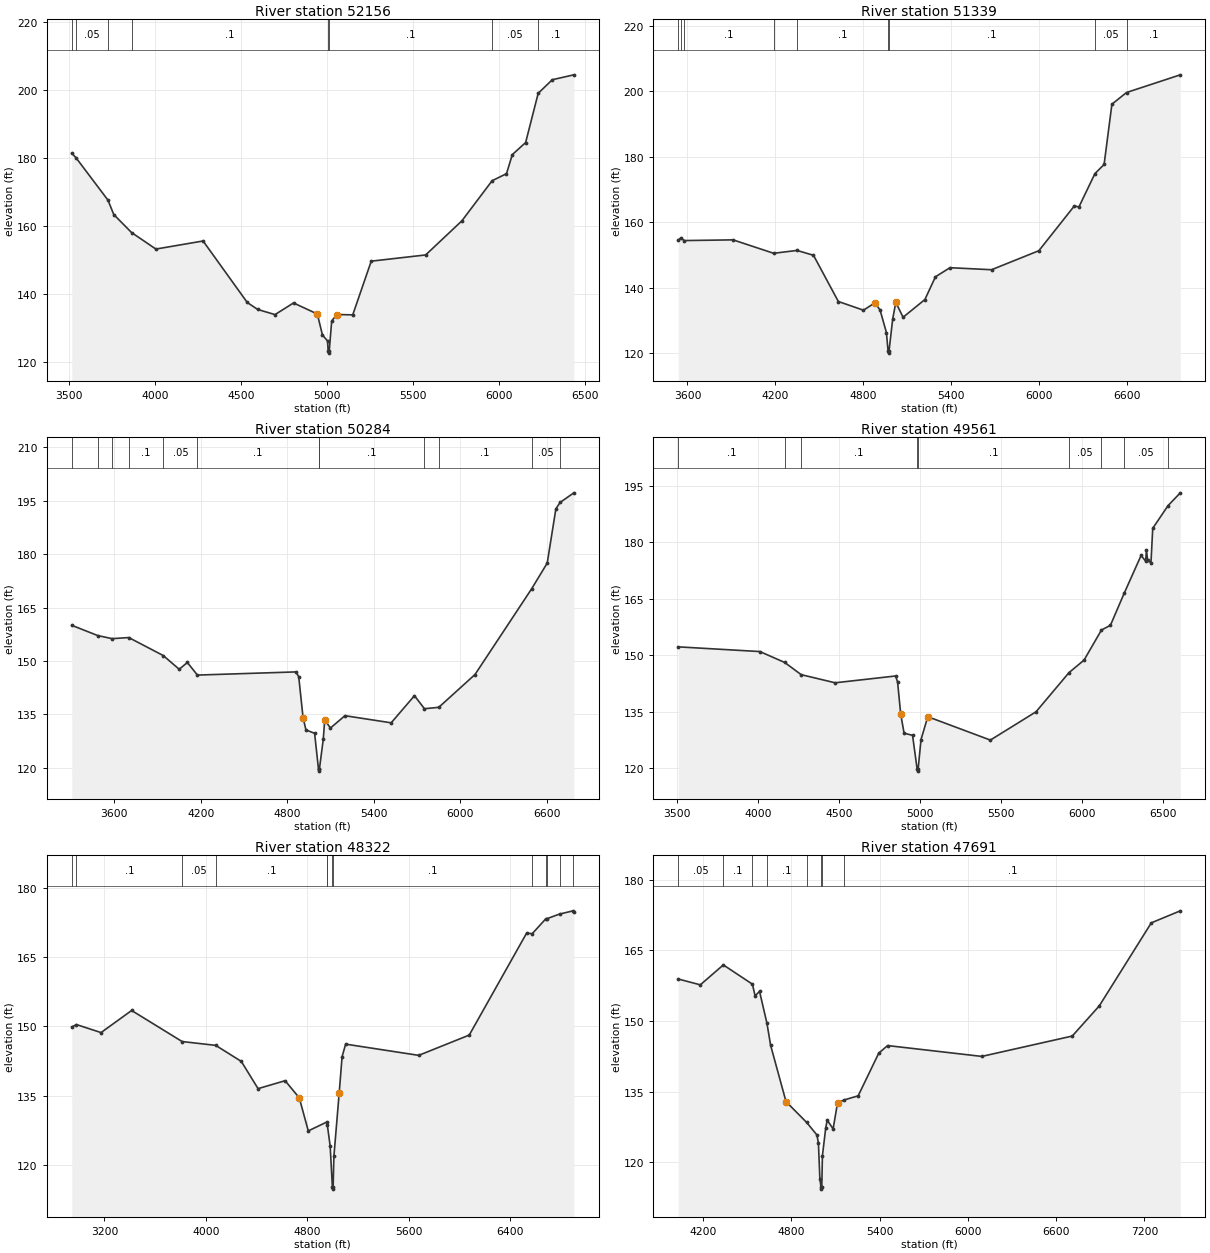
Type RM Length L Ch R = 1 ,52156   ,817,817,817
BEGIN DESCRIPTION:
LAGARTO CREEK 40.0
END DESCRIPTION:
XS GIS Cut Line= 3
       2289109.4     13225314.21      2290888.95     13224602.38
      2291349.04     13223708.25
#Sta/Elev= 30
  3515.5  181.42  3541.2  179.99  3726.2  167.58  3760.1  163.34  3863.4  158.05
  4005.1  153.18  4279.8  155.56  4536.9  137.46  4597.5  135.41  4698.4  133.89
  4806.1  137.32  4944.8  134.07  4974.4   127.9  5004.1  126.14  5007.8  123.05
  5010.5  122.55  5013.8  123.05  5028.3  132.01  5057.9  133.92  5150.8  133.81
  5258.5  149.62  5575.2  151.45  5785.7  161.47  5962.1   173.3  6045.7  175.37
  6079.6  180.98  6157.1  184.54  6230.2  199.03  6312.3  203.03  6437.7  204.47
#Mann= 8 ,-1 , 0
  3515.5      .1       0  3541.2     .05       0  3726.2     .08       0
  3863.4      .1       0  5007.8     .07       0  5013.8      .1       0
  5962.1     .05       0  6230.2      .1       0
Bank Sta=4944.8,5057.9
XS Rating Curve= 0 ,0
Exp/Cntr=0.3,0.1

Type RM Length L Ch R = 1 ,51339   ,1055,1055,1055
BEGIN DESCRIPTION:
LAGARTO CREEK 39.0
END DESCRIPTION:
XS GIS Cut Line= 3
      2289890.66      13226486.1      2291184.09     13224880.16
      2291487.91     13223552.01
#Sta/Elev= 30
  3537.2  154.57  3554.8   155.2  3579.1  154.41  3911.1  154.63  4187.8  150.53
  4347.4   151.4  4459.7  149.92  4629.3  135.81  4800.5  133.16  4878.8   135.4
    4914  133.19  4957.2  126.33  4968.6  120.55  4971.4  120.05  4974.6  120.55
    5000   130.5  5021.2  135.53  5070.8     131  5219.6  136.41  5291.5  143.35
  5390.7  146.13  5674.4  145.51  5997.1  151.32  6238.6  164.97  6270.2  164.68
  6379.4  174.86  6441.9  177.64  6495.1  196.04  6594.8  199.61  6961.7  205.01
#Mann= 9 ,-1 , 0
  3537.2      .1       0  3554.8     .05       0  3579.1      .1       0
  4187.8     .08       0  4347.4      .1       0  4968.6     .07       0
  4974.6      .1       0  6379.4     .05       0  6594.8      .1       0
Bank Sta=4878.8,5021.2
XS Rating Curve= 0 ,0
Exp/Cntr=0.3,0.1

Type RM Length L Ch R = 1 ,50284   ,723,723,723
BEGIN DESCRIPTION:
LAGARTO CREEK 38.0
END DESCRIPTION:
XS GIS Cut Line= 3
       2291262.2     13227171.86      2291791.73     13226052.04
      2291635.48     13223812.49
#Sta/Elev= 30
    3305  160.04    3485  157.16  3584.9  156.29  3700.5   156.6  3939.9  151.54
  4050.5  147.69    4107   149.6  4176.8  146.06  4859.7  146.95  4879.7  145.63
  4909.8  134.13  4929.8  130.65    4990  129.71    5017  119.58  5019.8  119.08
    5023  119.58  5050.1  128.04  5060.1  133.47  5099.7  131.18  5200.5  134.65
  5521.3  132.65  5682.8  140.27  5752.1  136.61  5851.4     137  6102.7  146.21
  6496.1  170.31  6603.9  177.51    6664  192.74    6693  194.54  6788.7  197.25
#Mann= 12 ,-1 , 0
    3305     .05       0    3485      .1       0  3584.9     .05       0
  3700.5      .1       0  3939.9     .05       0  4176.8      .1       0
    5017     .07       0    5023      .1       0  5752.1     .05       0
  5851.4      .1       0  6496.1     .05       0    6693      .1       0
Bank Sta=4909.8,5060.1
XS Rating Curve= 0 ,0
Exp/Cntr=0.3,0.1

Type RM Length L Ch R = 1 ,49561   ,1239,1239,1239
BEGIN DESCRIPTION:
LAGARTO CREEK 37.0
END DESCRIPTION:
XS GIS Cut Line= 3
       2292746.6     13226798.61      2292546.93     13225904.47
      2291922.32     13223813.74
#Sta/Elev= 30
  3507.8  152.17  4011.7  150.92  4164.6  148.03  4266.5  144.79  4476.2  142.63
  4849.4  144.44  4861.5  142.81  4880.7  134.28  4901.6  129.24  4953.7  128.69
  4982.1  119.68  4984.8  119.18  4988.1  119.68  5005.9  127.55  5047.7  133.63
  5433.8  127.42  5715.6  134.93  5919.1  145.33  6011.9  148.65  6119.3  156.63
  6174.8   157.9  6261.3  166.56    6364  176.43  6391.9  174.94  6397.1  177.86
  6404.4  175.14    6425  174.52  6435.8  183.64  6530.1  189.65    6606  193.06
#Mann= 9 ,-1 , 0
  3507.8      .1       0  4164.6     .05       0  4266.5      .1       0
  4982.1     .07       0  4988.1      .1       0  5919.1     .05       0
  6119.3      .1       0  6261.3     .05       0  6530.1      .1       0
Bank Sta=4880.7,5047.7
XS Rating Curve= 0 ,0
Exp/Cntr=0.3,0.1

Type RM Length L Ch R = 1 ,48322   ,631,631,631
BEGIN DESCRIPTION:
Mapping XS f5f2b29d
END DESCRIPTION:
XS GIS Cut Line= 4
      2292920.18      13226894.1      2293171.93     13226147.52
      2293484.43     13224359.33      2292981.19     13223101.22
#Sta/Elev= 30
  2942.5  149.89  2979.6   150.4  3173.3  148.67  3414.5  153.45  3812.5  146.73
  4077.4   145.9  4279.2  142.43  4411.2  136.54  4624.4  138.26  4736.1  134.55
  4807.1   127.4  4953.2  129.32  4957.5  128.63  4979.7   124.1    4997   115.3
  4999.7   114.8    5003   115.3    5009  121.88  5050.8  135.61  5073.6  143.44
  5101.5  146.17  5677.6  143.74  6076.1  148.13  6528.4  170.19  6572.4  170.06
  6680.1   173.3  6691.1  173.33  6787.8  174.31  6895.5  175.01  6900.7  174.81
#Mann= 13 ,-1 , 0
  2942.5     .08       0  2979.6      .1       0  3812.5     .05       0
  4077.4      .1       0  4953.2     .12       0  4957.5      .1       0
    4997     .07       0    5003      .1       0  6572.4     .08       0
  6680.1     .05       0  6691.1      .1       0  6787.8     .05       0
  6895.5      .1       0
Bank Sta=4736.1,5050.8
XS Rating Curve= 0 ,0
Exp/Cntr=0.3,0.1

Type RM Length L Ch R = 1 ,47691   ,488,488,488
BEGIN DESCRIPTION:
LAGARTO CREEK 36.0
END DESCRIPTION:
XS GIS Cut Line= 4
      2293788.25     13225991.29      2293918.46      13225531.2
      2293970.55     13223690.93        2293224.     13222892.29
#Sta/Elev= 30
  4031.9  158.92    4182  157.68  4338.4  161.91  4536.2  157.82  4554.4  155.33
  4584.4  156.31  4634.9  149.51    4660  144.82  4764.5  132.89    4904   128.5
  4974.6  125.81  4984.6   124.1  4994.6  116.56  5001.6  114.82  5004.4  114.32
  5007.6  114.82  5011.8  121.39  5034.6  127.38  5044.6  128.95  5084.6  127.11
  5114.6  132.63  5160.7  133.26  5254.7  134.12  5394.8  143.18  5454.8  144.79
    6095  142.49  6709.8  146.81  6893.5  153.21  7247.2  170.84  7444.3  173.39
#Mann= 8 ,-1 , 0
  4031.9     .05       0  4338.4      .1       0  4536.2     .05       0
  4634.9      .1       0    4904     .12       0  5001.6     .07       0
  5007.6     .12       0  5160.7      .1       0
Bank Sta=4764.5,5114.6
XS Rating Curve= 0 ,0
Exp/Cntr=0.3,0.1

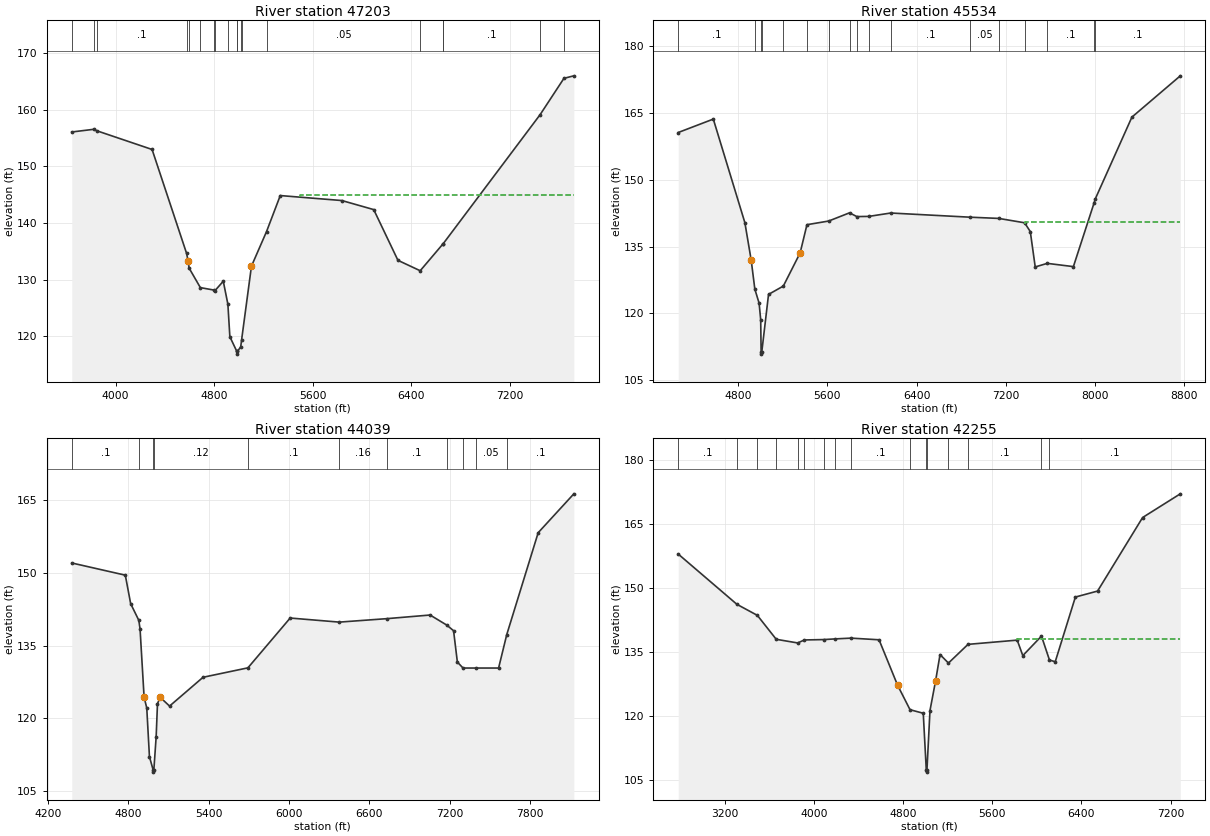
Type RM Length L Ch R = 1 ,47203   ,1669,1669,1669
BEGIN DESCRIPTION:
LAGARTO CREEK 35.0
END DESCRIPTION:
XS GIS Cut Line= 4
      2293788.24     13226164.92      2294039.99     13225539.88
      2294691.03     13224394.05      2295689.31     13222562.43
#Sta/Elev= 30
  3644.1  156.07  3824.9  156.55  3845.3   156.3  4296.4  152.98  4576.7  134.62
  4589.2  133.24  4597.2  132.02  4688.5  128.58  4800.2  128.14  4806.7  128.03
  4874.6  129.71    4912  125.65    4928  119.91  4984.1  117.33  4986.9  116.83
  4990.1  117.33  5016.3  118.12  5023.7  119.39  5103.5  132.37  5225.8  138.47
  5337.4  144.84  5837.6  143.96  6096.5  142.36  6293.2   133.4  6473.9  131.56
  6659.7  136.32  6660.2  136.32  7447.8  159.13  7641.5  165.55  7721.8  165.99
#Mann= 19 ,-1 , 0
  3644.1      .1       0  3824.9     .05       0  3845.3      .1       0
  4576.7     .05       0  4597.2      .1       0  4688.5     .05       0
  4800.2      .1       0  4806.7     .05       0    4912     .12       0
  4984.1     .07       0  4990.1     .12       0  5016.3     .05       0
  5023.7     .12       0  5225.8     .05       0  6473.9      .1       0
  6659.7     .05       0  6660.2      .1       0  7447.8     .08       0
  7641.5      .1       0
#XS Ineff= 2 , 0
                         5498.61          144.95
Permanent Ineff=
       F       F
Bank Sta=4589.2,5103.5
XS Rating Curve= 0 ,0
Exp/Cntr=0.3,0.1

Type RM Length L Ch R = 1 ,45534   ,1495,1495,1495
BEGIN DESCRIPTION:
LAGARTO CREEK 34.0
END DESCRIPTION:
XS GIS Cut Line= 3
      2294040.01     13226833.26       2295064.3      13225713.5
      2296443.62     13223067.62
#Sta/Elev= 30
  4262.6  160.56    4577  163.57    4860  140.35  4916.8  131.93  4949.4  125.44
  4987.7  122.29  5001.9  118.59  5005.7  111.37  5008.4  110.87  5011.7  111.37
  5072.2  124.26  5204.8  126.13  5355.5  133.57  5416.6  139.89  5611.2  140.71
  5798.1  142.55  5864.1  141.71  5970.3  141.75  6167.8  142.51  6881.1  141.57
    7136   141.3  7367.9  140.32    7419  138.35  7463.2  130.42  7571.3  131.22
  7805.4  130.49    7990   144.7  8001.6  145.67    8330  164.01    8764  173.27
#Mann= 17 ,-1 , 0
  4262.6      .1       0  4949.4     .12       0  5005.7     .07       0
  5011.7     .12       0  5204.8      .1       0  5416.6     .05       0
  5611.2      .1       0  5798.1     .05       0  5864.1      .1       0
  5970.3     .05       0  6167.8      .1       0  6881.1     .05       0
    7136      .1       0  7367.9     .05       0  7571.3      .1       0
    7990     .05       0  8001.6      .1       0
#XS Ineff= 2 , 0
                            7375          140.58
Permanent Ineff=
       F       F
Bank Sta=4916.8,5355.5
XS Rating Curve= 0 ,0
Exp/Cntr=0.3,0.1

Type RM Length L Ch R = 1 ,44039   ,1784,1784,1784
BEGIN DESCRIPTION:
LAGARTO CREEK 33.0
END DESCRIPTION:
XS GIS Cut Line= 3
      2295619.85     13227076.34      2295645.89     13225392.32
      2296522.62     13223526.02
#Sta/Elev= 30
  4378.7  151.99  4778.2  149.48  4818.2  143.61  4878.7   140.2  4888.2  138.43
  4918.3   124.4  4938.3  122.13  4958.3  112.12  4985.3  109.45    4988  108.95
  4991.3  109.45  5008.3   116.2  5018.3  123.04  5038.3  124.35  5108.3  122.54
  5358.3  128.47    5693  130.41  6008.4  140.66  6374.5  139.82  6728.5  140.53
  7052.3  141.28    7176  139.22  7227.5  138.05  7255.8   131.6  7298.2  130.37
  7391.3  130.37  7563.4  130.37  7624.5  137.27  7858.8  158.22  8124.9  166.22
#Mann= 11 ,-1 , 0
  4378.7      .1       0  4878.7     .12       0  4985.3     .07       0
  4991.3     .12       0    5693      .1       0  6374.5     .16       0
  6728.5      .1       0    7176     .05       0  7298.2      .1       0
  7391.3     .05       0  7624.5      .1       0
#XS Ineff= 2 , 0
                         7050.28          141.26
Permanent Ineff=
       F       F
Bank Sta=4918.3,5038.3
XS Rating Curve= 0 ,0
Exp/Cntr=0.3,0.1

Type RM Length L Ch R = 1 ,42255   ,714,714,714
BEGIN DESCRIPTION:
Mapping XS eee6c6f5
END DESCRIPTION:
XS GIS Cut Line= 5
      2295602.46     13227302.08      2296079.92     13226659.68
      2296618.12      13225800.3      2296783.05      13223925.3
        2296540.     13223152.77
#Sta/Elev= 30
  2780.6  157.86  3307.1  146.09  3490.8   143.5  3660.4  137.89  3852.7  137.04
  3912.6  137.74  4086.3  137.83    4191  137.99  4331.3  138.17  4583.1  137.78
    4749  127.16  4861.1   121.4  4979.9  120.57    5007  107.28  5009.8  106.78
    5013  107.28  5040.2  121.21  5090.3  128.13  5130.5  134.32    5206  132.33
  5381.7  136.71  5823.2   137.7  5873.4  134.07    6041  138.64  6112.8  133.03
  6164.5  132.64  6345.2  147.79  6544.4  149.19  6948.7  166.42  7287.1  171.97
#Mann= 16 ,-1 , 0
  2780.6      .1       0  3307.1     .05       0  3490.8      .1       0
  3660.4     .05       0  3852.7      .1       0  3912.6     .05       0
  4086.3      .1       0    4191     .05       0  4331.3      .1       0
  4861.1     .12       0    5007     .07       0    5013     .12       0
    5206     .16       0  5381.7      .1       0    6041     .05       0
  6112.8      .1       0
#XS Ineff= 2 , 0
                         5818.18          137.85
Permanent Ineff=
       F       F
Bank Sta=4749,5090.3
XS Rating Curve= 0 ,0
Exp/Cntr=0.3,0.1