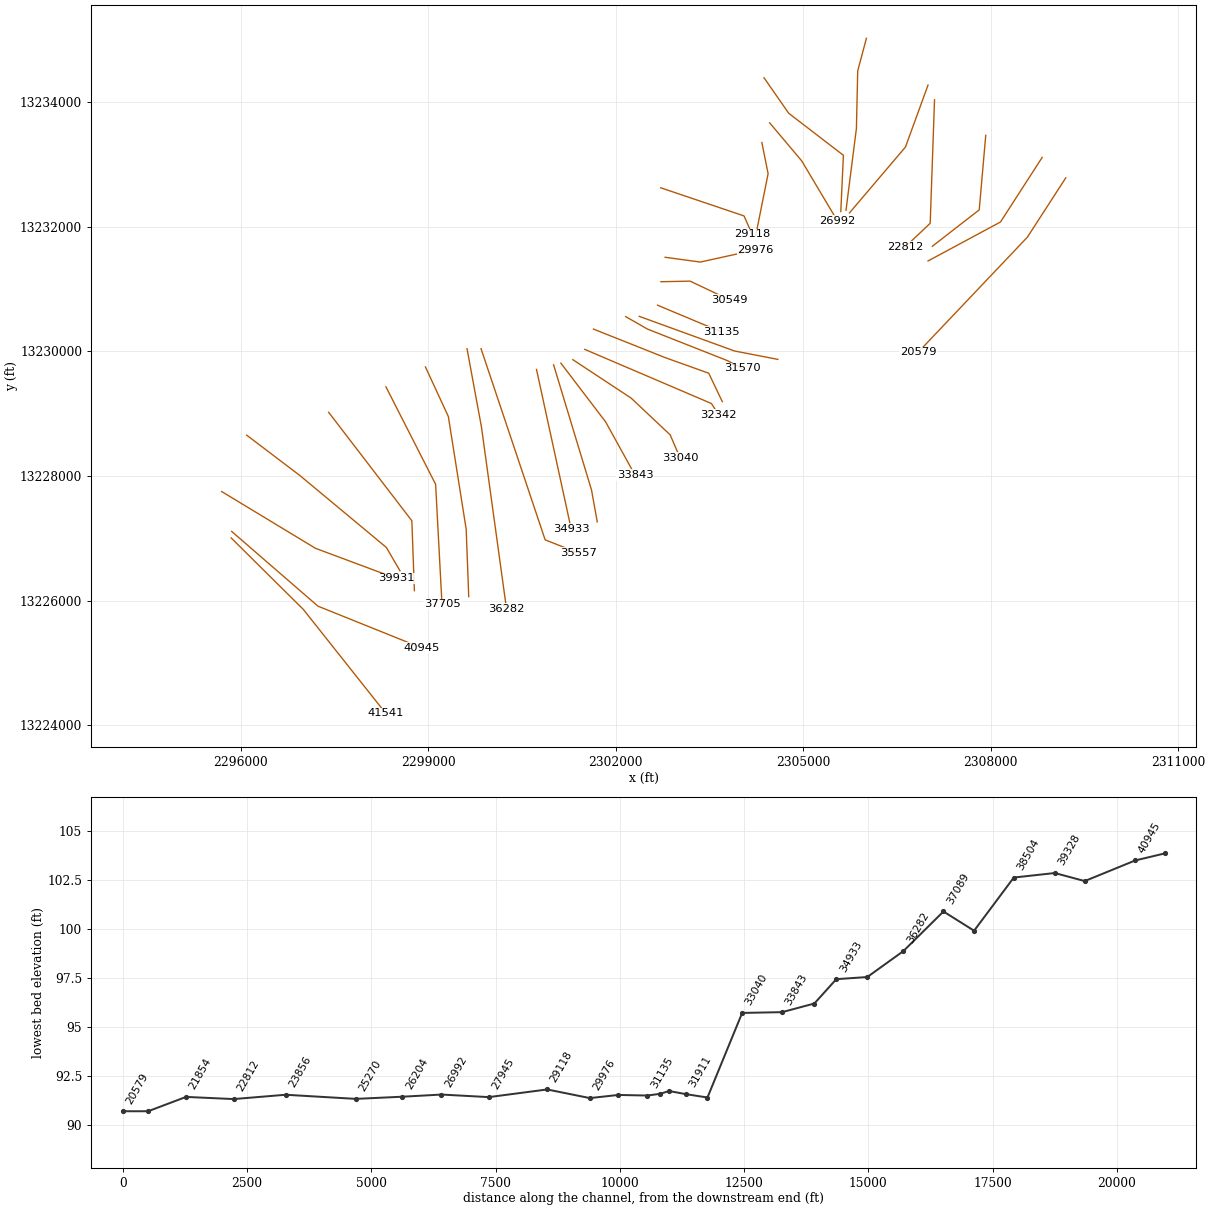
HEC-RAS study LAGARTO CREEK.prj: LAGARTO CREEK Base Level Engineering

--- LAGARTO CREEK.g01 (geometry) --- (continued)

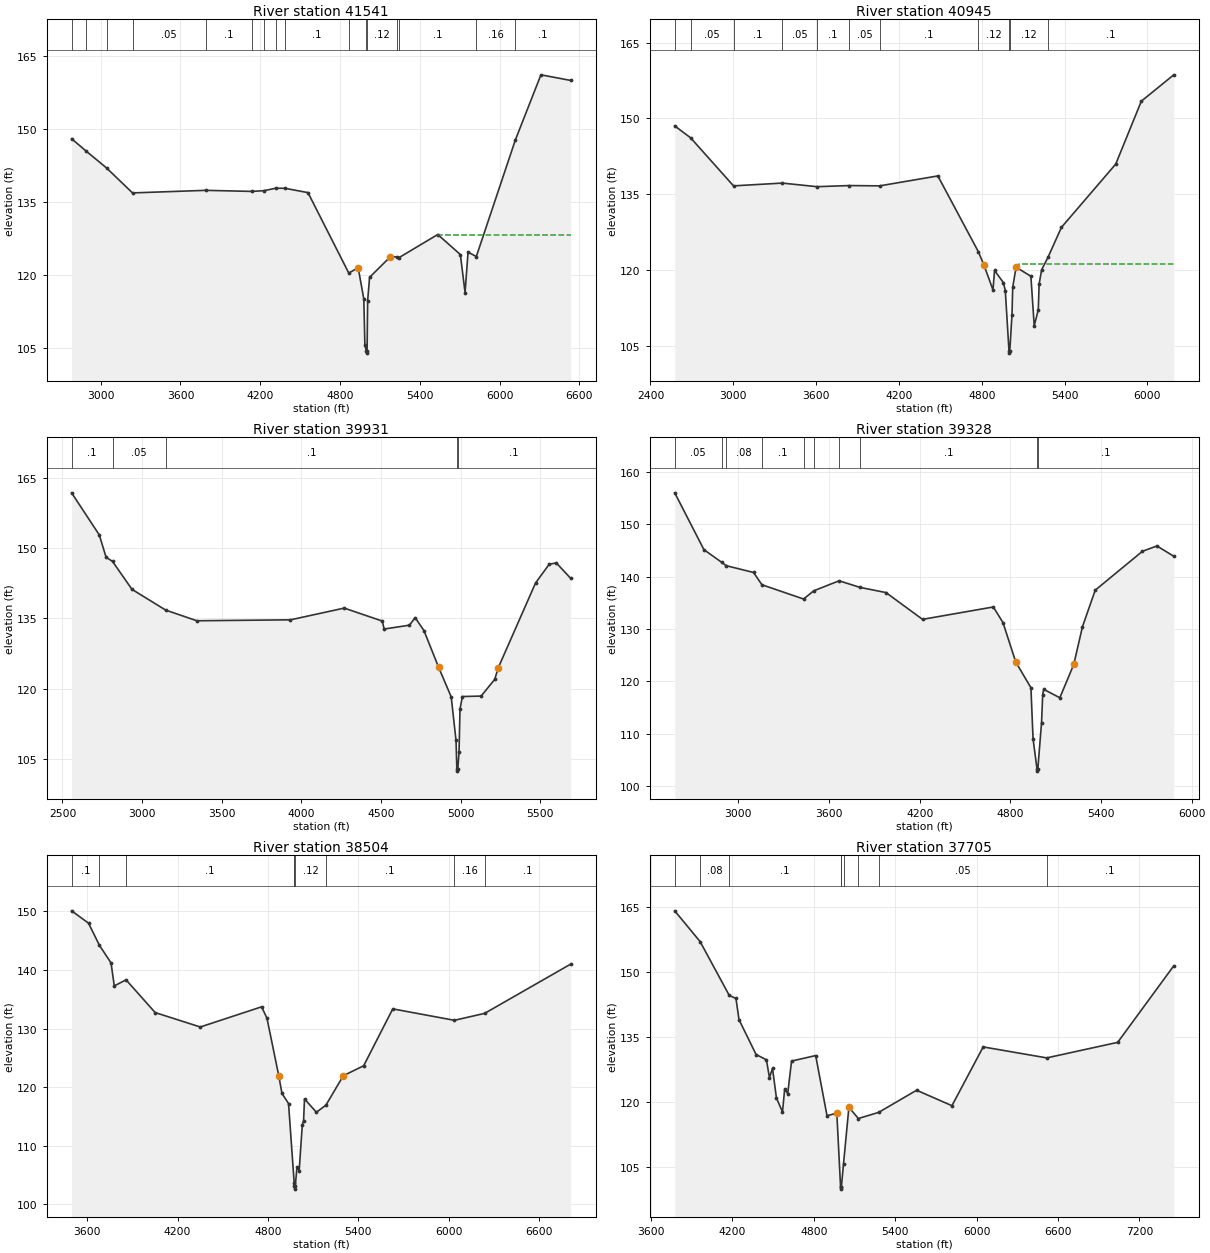
Type RM Length L Ch R = 1 ,41541   ,596,596,596
BEGIN DESCRIPTION:
LAGARTO CREEK 32.0
END DESCRIPTION:
XS GIS Cut Line= 3
      2295845.53     13227006.92      2297000.06     13225861.07
      2298319.53     13224194.36
#Sta/Elev= 30
  2781.3  147.93  2892.3  145.35  3043.7  141.93  3239.3  136.79  3790.1  137.32
  4134.3   137.1  4227.7  137.25  4316.5  137.76  4385.7  137.74  4558.6  136.85
  4865.3  120.32  4936.2   121.4  4978.5  114.98  4986.5  105.48    4997  104.35
  4999.7  103.85    5003  104.35  5007.3  114.62  5021.8  119.43  5178.6  123.68
  5229.9  123.64  5242.1  123.47  5534.6  128.24  5704.5  124.12  5739.8   116.3
  5762.2  124.61  5824.4  123.71  6118.2  147.69  6310.3  161.07  6533.7  159.92
#Mann= 16 ,-1 , 0
  2781.3      .1       0  2892.3     .05       0  3043.7      .1       0
  3239.3     .05       0  3790.1      .1       0  4134.3     .05       0
  4227.7      .1       0  4316.5     .05       0  4385.7      .1       0
  4865.3     .12       0    4997     .07       0    5003     .12       0
  5229.9     .16       0  5242.1      .1       0  5824.4     .16       0
  6118.2      .1       0
#XS Ineff= 2 , 0
                         5525.57          128.21
Permanent Ineff=
       F       F
Bank Sta=4936.2,5178.6
XS Rating Curve= 0 ,0
Exp/Cntr=0.3,0.1

Type RM Length L Ch R = 1 ,40945   ,1014,1014,1014
BEGIN DESCRIPTION:
LAGARTO CREEK 31.0
END DESCRIPTION:
XS GIS Cut Line= 3
      2295854.24     13227111.05      2297234.43     13225913.15
      2298892.43     13225244.74
#Sta/Elev= 30
  2575.9  148.51    2691  146.15  3001.7  136.63  3355.4  137.18  3605.3  136.47
  3839.9  136.69  4060.4  136.63  4482.1   138.6  4775.7  123.57  4816.7  120.88
  4881.4  116.02  4892.9  119.87  4956.9  117.47  4970.8  115.86  4997.3  103.99
  5000.1  103.49  5003.3  103.99  5019.1  111.05  5024.5  116.54  5048.7  120.52
  5156.1  118.72  5180.2  108.91  5209.8  112.09  5215.6  117.12  5233.9  120.01
  5280.6  122.51  5377.4  128.41  5770.9  140.95  5956.2  153.41  6191.1  158.63
#Mann= 11 ,-1 , 0
  2575.9      .1       0    2691     .05       0  3001.7      .1       0
  3355.4     .05       0  3605.3      .1       0  3839.9     .05       0
  4060.4      .1       0  4775.7     .12       0  4997.3     .07       0
  5003.3     .12       0  5280.6      .1       0
#XS Ineff= 2 , 0
                         5072.73          121.18
Permanent Ineff=
       F       F
Bank Sta=4816.7,5048.7
XS Rating Curve= 0 ,0
Exp/Cntr=0.3,0.1

Type RM Length L Ch R = 1 ,39931   ,603,603,603
BEGIN DESCRIPTION:
Mapping XS 85b8ab5e
END DESCRIPTION:
XS GIS Cut Line= 3
      2295693.18     13227751.18      2297194.51     13226840.88
      2298483.97     13226359.02
#Sta/Elev= 30
  2557.6  161.76  2731.2  152.79  2773.9  148.03  2814.3  147.14  2936.7  141.18
  3148.2  136.76  3343.8  134.49  3931.4  134.69  4268.7  137.19  4507.1  134.43
  4519.6  132.73  4678.2  133.55  4713.8  135.16  4769.1   132.4  4861.2  124.57
  4940.2  118.27  4970.5  108.97  4975.6  102.94  4978.4  102.44  4981.6  102.94
  4989.3  106.42  4995.4  115.68  5010.7  118.34  5128.1  118.44  5213.5  122.01
  5234.9  124.42  5469.7  142.55  5555.1  146.52  5599.6  146.83  5689.9  143.54
#Mann= 5 ,-1 , 0
  2557.6      .1       0  2814.3     .05       0  3148.2      .1       0
  4975.6     .07       0  4981.6      .1       0
Bank Sta=4861.2,5234.9
XS Rating Curve= 0 ,0
Exp/Cntr=0.3,0.1

Type RM Length L Ch R = 1 ,39328   ,824,824,824
BEGIN DESCRIPTION:
LAGARTO CREEK 30.0
END DESCRIPTION:
XS GIS Cut Line= 4
      2296093.93     13228654.76      2296943.15     13228009.36
      2298329.02     13226854.46       2298546.1     13226481.35
#Sta/Elev= 30
  2579.3  156.03  2772.5  145.17  2891.1  142.73  2919.8  142.11  3100.9  140.81
  3156.5  138.46  3431.8  135.74  3499.4  137.31  3667.1  139.22  3803.9  137.97
  3977.3  136.97  4219.1  131.85  4687.7  134.22  4751.5  131.23  4836.4  123.67
  4936.3   118.8  4950.6     109  4976.3  103.35    4979  102.85  4982.3  103.35
  5006.6  112.07  5014.4  117.48  5020.9  118.48  5127.7  116.87  5220.1  123.25
  5277.3  130.43    5362  137.43  5674.4  144.86  5770.4  145.88  5881.6  143.91
#Mann= 10 ,-1 , 0
  2579.3     .05       0  2891.1      .1       0  2919.8     .08       0
  3156.5      .1       0  3431.8     .05       0  3499.4      .1       0
  3667.1     .05       0  3803.9      .1       0  4976.3     .07       0
  4982.3      .1       0
Bank Sta=4836.4,5220.1
XS Rating Curve= 0 ,0
Exp/Cntr=0.3,0.1

Type RM Length L Ch R = 1 ,38504   ,799,799,799
BEGIN DESCRIPTION:
LAGARTO CREEK 29.0
END DESCRIPTION:
XS GIS Cut Line= 3
       2297405.1     13229021.59      2298736.63     13227282.45
      2298777.38     13226161.73
#Sta/Elev= 30
  3496.8  150.08  3608.9  147.98  3681.2  144.21  3758.5  141.19  3779.8  137.28
  3858.1  138.31  4051.4  132.73  4350.6  130.27  4757.7  133.71  4793.1  131.78
    4872   121.9  4892.8  118.94  4936.3  117.22  4974.1  103.61    4975  103.12
  4977.7  102.62    4981  103.12  4992.5  106.41    5007  105.79  5027.9  113.64
  5036.1  114.26  5042.4  118.01  5121.3  115.73  5184.5  116.94  5299.9  121.96
    5435  123.66  5628.1  133.36  6036.8  131.41  6237.6  132.59  6808.6  140.99
#Mann= 9 ,-1 , 0
  3496.8      .1       0  3681.2     .08       0  3858.1      .1       0
  4974.1     .12       0    4975     .07       0    4981     .12       0
  5184.5      .1       0  6036.8     .16       0  6237.6      .1       0
Bank Sta=4872,5299.9
XS Rating Curve= 0 ,0
Exp/Cntr=0.3,0.1

Type RM Length L Ch R = 1 ,37705   ,616,616,616
BEGIN DESCRIPTION:
LAGARTO CREEK 28.0
END DESCRIPTION:
XS GIS Cut Line= 3
      2298322.23     13229429.17      2299117.06     13227866.69
      2299218.96     13225944.12
#Sta/Elev= 30
  3774.6  164.02  3961.9  156.92  4176.8  144.52    4226  143.83  4248.4  138.95
  4374.3  130.92  4450.4   129.7  4472.8   125.6  4495.3  127.72  4524.4   120.9
  4568.9  117.69    4585     123  4607.4  121.91  4635.7  129.41  4813.6  130.68
    4897  116.83  4969.4  117.39  4997.1  100.41  4999.9   99.91  5003.1  100.41
  5018.8  105.78  5058.4  118.77    5128  116.18  5277.1  117.58  5557.5  122.69
  5817.9  119.13  6048.2  132.67  6516.6  130.14  7039.6  133.72  7452.9  151.35
#Mann= 9 ,-1 , 0
  3774.6      .1       0  3961.9     .08       0  4176.8      .1       0
  4997.1     .07       0  5003.1      .1       0  5018.8     .12       0
    5128      .1       0  5277.1     .05       0  6516.6      .1       0
Bank Sta=4969.4,5058.4
XS Rating Curve= 0 ,0
Exp/Cntr=0.3,0.1

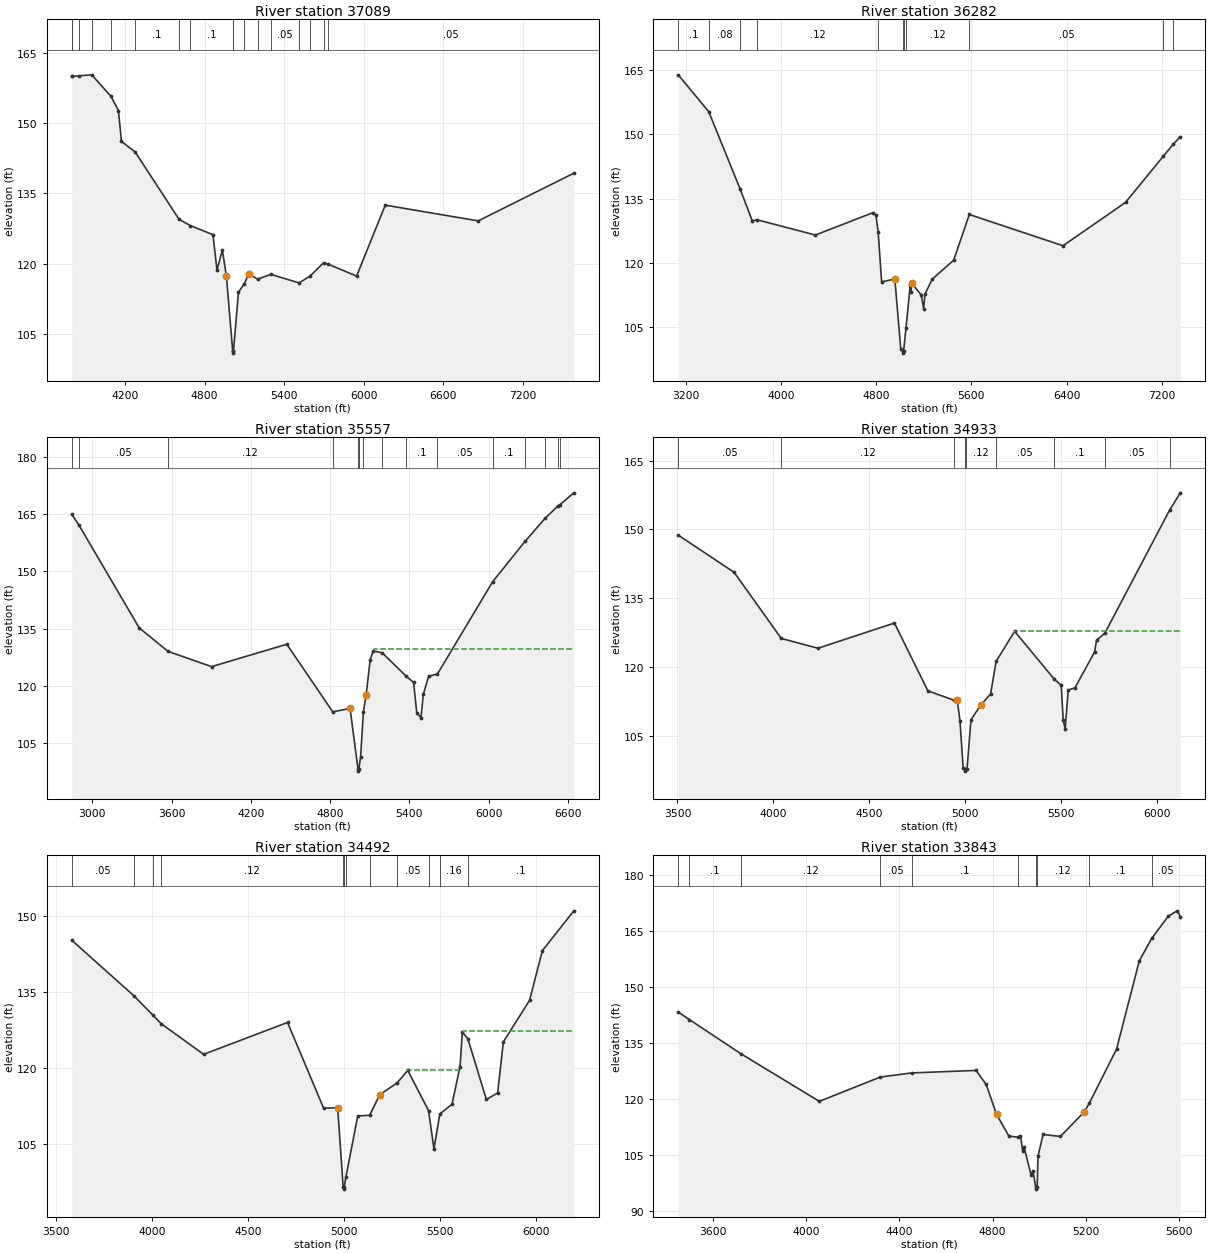
Type RM Length L Ch R = 1 ,37089   ,807,807,807
BEGIN DESCRIPTION:
LAGARTO CREEK 27.0
END DESCRIPTION:
XS GIS Cut Line= 4
      2298954.02     13229748.48      2299320.87     13228953.65
      2299606.19     13227146.58      2299646.95     13226066.41
#Sta/Elev= 30
  3797.9  159.95  3799.6  159.95  3850.9  160.06  3948.4  160.28  4093.5  155.69
  4149.7  152.66  4172.6  146.06  4276.1  143.81  4606.9  129.45  4692.8   128.1
  4862.4  126.17  4892.8  118.61  4933.3  122.87  4963.7  117.36  5011.3  101.39
    5014  100.89  5017.3  101.39  5054.8   113.9  5099.5  115.71  5132.4  117.85
    5199  116.67  5298.6   117.7  5512.6  115.87  5597.2  117.39  5696.8  120.18
  5732.2  119.87  5945.7  117.33  6161.6  132.47  6862.7  129.11  7583.7  139.29
#Mann= 17 ,-1 , 0
  3797.9     .05       0  3799.6      .1       0  3850.9     .05       0
  3948.4      .1       0  4093.5     .05       0  4276.1      .1       0
  4606.9     .05       0  4692.8      .1       0  5011.3     .07       0
  5017.3      .1       0  5099.5      .1       0    5199     .12       0
  5298.6     .05       0  5512.6      .1       0  5597.2     .05       0
  5696.8      .1       0  5732.2     .05       0
Bank Sta=4963.7,5132.4
XS Rating Curve= 0 ,0
Exp/Cntr=0.3,0.1

Type RM Length L Ch R = 1 ,36282   ,725,725,725
BEGIN DESCRIPTION:
Mapping XS 3db7654d
END DESCRIPTION:
XS GIS Cut Line= 3
      2299619.78     13230040.58      2299850.76     13228783.81
       2300251.4     13225870.65
#Sta/Elev= 30
    3137  163.91  3393.1  155.31  3655.8  137.31  3758.9  129.78  3799.9  130.03
  4289.7  126.47  4775.1  131.72  4798.3  131.08    4817   127.1  4845.8  115.53
  4956.8  116.19  5007.3   99.73  5024.5   99.37  5027.2   98.87  5030.5   99.37
  5050.7  104.77  5086.4  114.76  5091.5  113.05  5098.1  115.24  5178.9  112.46
  5199.1  109.24  5209.2  112.58  5269.8  116.12  5451.4   120.6  5582.7  131.27
    6370  123.97  6894.9  134.09  7213.8  144.93  7294.7  147.65  7355.4  149.46
#Mann= 11 ,-1 , 0
    3137      .1       0  3393.1     .08       0  3655.8     .05       0
  3799.9     .12       0    4817     .16       0  5024.5     .07       0
  5030.5     .16       0  5050.7     .12       0  5582.7     .05       0
  7213.8      .1       0  7294.7     .05       0
Bank Sta=4956.8,5098.1
XS Rating Curve= 0 ,0
Exp/Cntr=0.3,0.1

Type RM Length L Ch R = 1 ,35557   ,624,624,624
BEGIN DESCRIPTION:
Mapping XS ad8f043f
END DESCRIPTION:
XS GIS Cut Line= 3
      2299843.95     13230040.64      2300869.78     13226976.75
       2301399.7     13226766.14
#Sta/Elev= 30
  2844.7  164.99  2898.5  162.19  3354.9  135.18  3572.9  129.01  3903.3  124.99
  4472.7  130.87  4820.8  113.11  4951.8  114.03    5012   98.05  5014.7   97.55
    5018   98.05  5031.6  101.34  5052.5  113.08  5072.8  117.44  5104.4  126.86
  5126.5  129.09  5194.7  128.64  5376.5  122.47  5432.4  120.86  5456.9  112.85
  5488.5   111.6  5506.2  117.68  5546.3  122.46  5613.6  123.08  6032.4  147.34
  6276.3  157.88  6430.6  164.02  6525.3  167.17  6537.4  167.41    6646  170.63
#Mann= 15 ,-1 , 0
  2844.7      .1       0  2898.5     .05       0  3572.9     .12       0
  4820.8     .12       0    5012     .07       0    5018     .12       0
  5052.5      .1       0  5194.7     .05       0  5376.5      .1       0
  5613.6     .05       0  6032.4      .1       0  6276.3     .08       0
  6430.6      .1       0  6525.3     .08       0  6537.4     .05       0
#XS Ineff= 2 , 0
                         5136.36          129.54
Permanent Ineff=
       F       F
Bank Sta=4951.8,5072.8
XS Rating Curve= 0 ,0
Exp/Cntr=0.3,0.1

Type RM Length L Ch R = 1 ,34933   ,441,441,441
BEGIN DESCRIPTION:
LAGARTO CREEK 26.0
END DESCRIPTION:
XS GIS Cut Line= 2
      2300731.38     13229708.94      2301286.55     13227149.97
#Sta/Elev= 30
  3503.9  148.77  3795.4  140.68  4041.5  126.29  4232.6  124.17  4631.6  129.65
  4805.6  114.91  4942.6  112.85  4959.1  112.92  4973.4  108.29  4989.8   98.21
    4997   97.94  4999.8   97.44    5003   97.94  5010.2   97.97  5030.7  108.62
  5081.9  111.81    5133  114.22  5161.5  121.29  5258.1  127.86  5462.8  117.55
  5501.4  116.08  5511.6  108.51  5521.9   106.6  5537.8  115.08    5573  115.57
    5675  123.33  5685.6  125.92  5728.9  127.45  6066.7  154.22  6122.4  157.97
#Mann= 9 ,-1 , 0
  3503.9     .05       0  4041.5     .12       0  4942.6     .12       0
    4997     .07       0    5003     .12       0  5161.5     .05       0
  5462.8      .1       0  5728.9     .05       0  6066.7      .1       0
#XS Ineff= 2 , 0
                         5253.98          128.02
Permanent Ineff=
       F       F
Bank Sta=4959.1,5081.9
XS Rating Curve= 0 ,0
Exp/Cntr=0.3,0.1

Type RM Length L Ch R = 1 ,34492   ,649,649,649
BEGIN DESCRIPTION:
LAGARTO CREEK 25.0
END DESCRIPTION:
XS GIS Cut Line= 3
      2301004.83     13229782.69      2301612.46     13227773.17
      2301703.61     13227265.36
#Sta/Elev= 30
  3581.2  145.24  3905.1  134.28  4005.2  130.43    4047  128.79  4268.2  122.76
  4705.1  129.04  4893.2  112.14  4966.3  112.24  4994.7    96.7  4997.4    96.2
  5000.7    96.7    5009   98.55  5070.8  110.62  5132.6  110.75  5185.7  114.82
  5275.1   117.1  5331.4  119.58  5439.5  111.69  5467.8  104.14  5498.3     111
  5561.8  112.92  5603.6  120.35  5615.8  127.11  5644.1  125.86  5740.8  113.87
  5799.5  115.14  5829.2   125.2  5965.7  133.38  6032.4  143.18  6196.5  151.03
#Mann= 12 ,-1 , 0
  3581.2     .05       0  3905.1      .1       0  4005.2     .05       0
    4047     .12       0  4994.7     .07       0  5000.7      .1       0
    5009     .12       0  5132.6      .1       0  5275.1     .05       0
  5439.5      .1       0  5498.3     .16       0  5644.1      .1       0
#XS Ineff= 2 ,-1
 5328.98    5600   119.7 5618.75  6196.5  127.32
Permanent Ineff=
       F       F
Bank Sta=4966.3,5185.7
XS Rating Curve= 0 ,0
Exp/Cntr=0.3,0.1

Type RM Length L Ch R = 1 ,33843   ,803,803,803
BEGIN DESCRIPTION:
LAGARTO CREEK 24.0
END DESCRIPTION:
XS GIS Cut Line= 3
      2301122.02     13229808.74      2301838.15     13228866.92
      2302306.93     13228016.18
#Sta/Elev= 30
  3451.4   143.3  3499.3  141.28  3720.4   132.1  4056.8  119.33  4318.3  125.85
  4453.6  126.96  4729.3  127.63  4772.9  123.86  4817.3  115.83  4870.3  109.99
    4910   109.7  4920.1  110.11  4929.9  105.88  4935.7  106.98  4965.7   99.51
  4973.5  100.64  4985.6   96.26  4988.3   95.76  4991.6   96.26  4995.3  104.62
  5017.1  110.44  5091.3  109.89  5194.1  116.53  5215.7  118.87  5332.3  133.35
  5429.8  157.03  5483.2  163.08  5554.7  169.08  5592.6  170.48  5605.9  168.95
#Mann= 10 ,-1 , 0
  3451.4     .05       0  3499.3      .1       0  3720.4     .12       0
  4318.3     .05       0  4453.6      .1       0    4910     .12       0
  4985.6     .07       0  4991.6     .12       0  5215.7      .1       0
  5483.2     .05       0
Bank Sta=4817.3,5194.1
XS Rating Curve= 0 ,0
Exp/Cntr=0.3,0.1

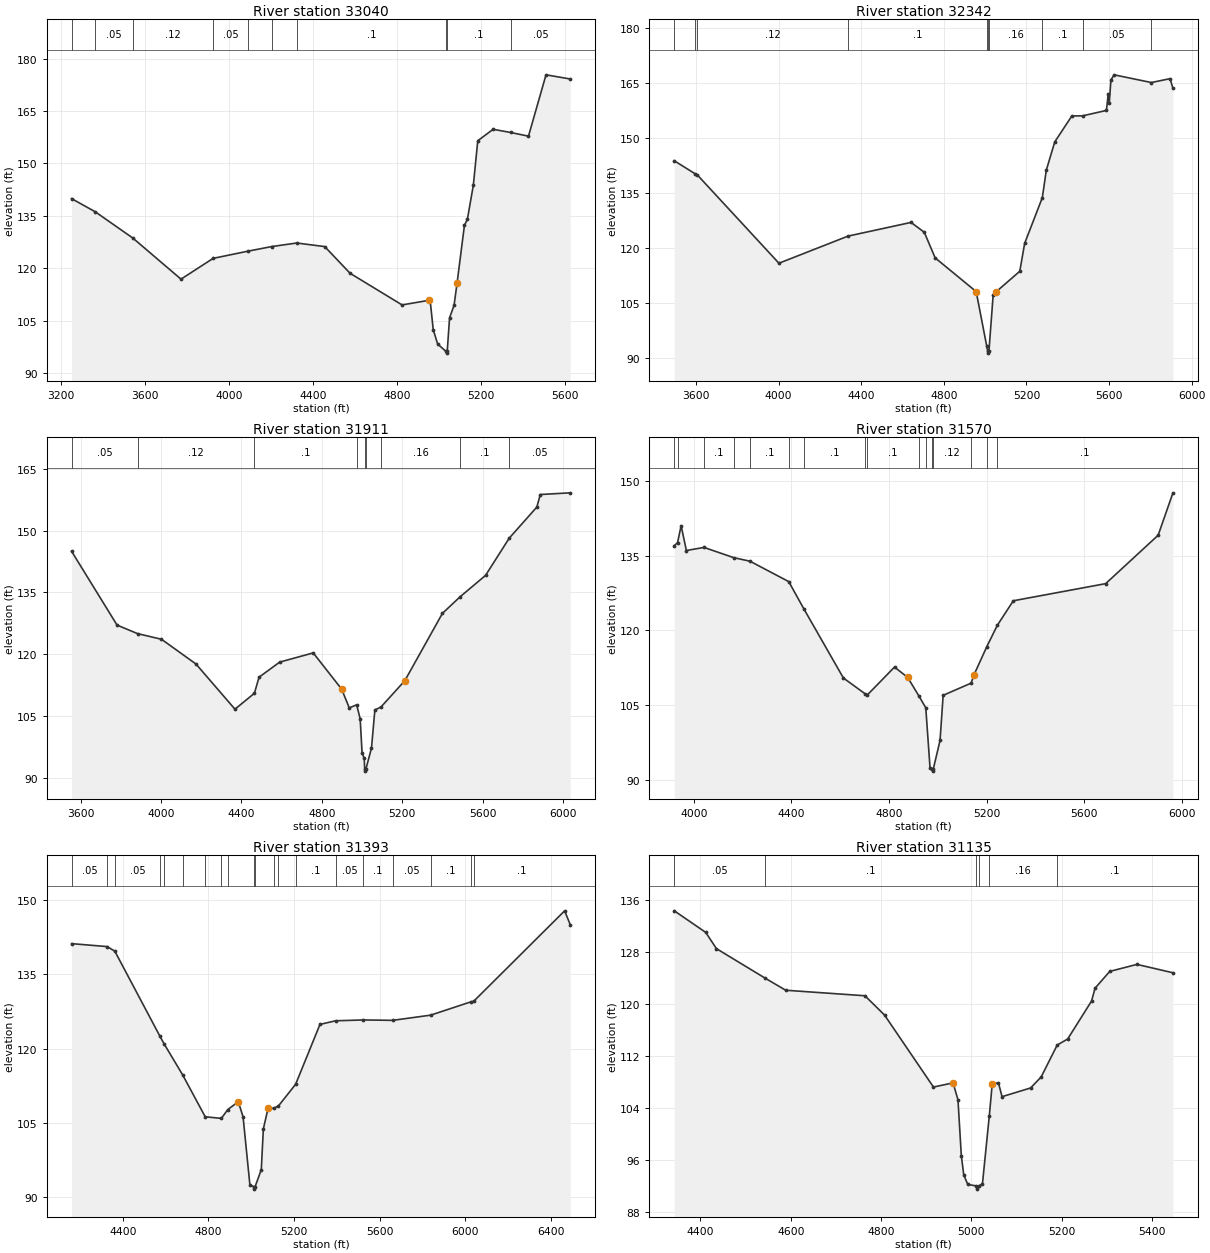
Type RM Length L Ch R = 1 ,33040   ,698,698,698
BEGIN DESCRIPTION:
Mapping XS 202f6919
END DESCRIPTION:
XS GIS Cut Line= 4
      2301313.01     13229865.16      2302246.14     13229248.86
      2302871.14     13228658.59      2303027.38     13228294.02
#Sta/Elev= 30
  3249.6  139.92  3362.2  136.15  3541.4  128.63  3770.6  116.88  3923.7  122.83
  4091.6  124.91    4202   126.2  4321.9  127.22  4455.2  126.19  4575.7  118.56
  4823.3  109.51  4950.4  110.82  4957.6  110.49  4971.8   102.4  4992.8   98.32
  5032.3   96.22  5035.1   95.72  5038.3   96.22  5049.5  105.83  5070.9  109.38
  5085.1  115.68  5120.3  132.27  5134.4  134.02  5162.8  143.79  5183.8  156.47
  5256.8  159.75  5339.9  158.84  5425.3  157.78  5508.8  175.33  5624.2  174.14
#Mann= 10 ,-1 , 0
  3249.6      .1       0  3362.2     .05       0  3541.4     .12       0
  3923.7     .05       0  4091.6      .1       0    4202     .05       0
  4321.9      .1       0  5032.3     .07       0  5038.3      .1       0
  5339.9     .05       0
Bank Sta=4950.4,5085.1
XS Rating Curve= 0 ,0
Exp/Cntr=0.3,0.1

Type RM Length L Ch R = 1 ,32342   ,431,431,431
BEGIN DESCRIPTION:
Mapping XS 9c1611fd
END DESCRIPTION:
XS GIS Cut Line= 3
      2301503.98      13230030.1      2303530.86     13229162.06
       2303643.2     13228984.92
#Sta/Elev= 30
  3494.7  143.79  3596.8   140.2  3605.3  139.99  4001.4  115.89  4336.4  123.28
    4641     127  4705.2  124.33  4757.8  117.35  4956.5  108.17  5007.3   93.41
  5012.3   91.91  5015.1   91.41  5018.3   91.91  5038.9  107.34  5054.4  108.17
  5167.7   113.7  5191.3  121.29  5276.8  133.74  5296.4  141.28  5337.2  148.94
  5419.8  155.99  5471.6  156.02  5587.4   157.5  5595.7  161.91  5601.2  159.65
  5609.2  165.83  5624.7  167.19    5805  165.09  5895.5  166.15  5909.4   163.5
#Mann= 10 ,-1 , 0
  3494.7     .05       0  3596.8      .1       0  3605.3     .12       0
  4336.4      .1       0  5007.3     .16       0  5012.3     .07       0
  5018.3     .16       0  5276.8      .1       0  5471.6     .05       0
    5805      .1       0
Bank Sta=4956.5,5054.4
XS Rating Curve= 0 ,0
Exp/Cntr=0.3,0.1

Type RM Length L Ch R = 1 ,31911   ,341,341,341
BEGIN DESCRIPTION:
Mapping XS 3dde669d
END DESCRIPTION:
XS GIS Cut Line= 4
      2301642.87     13230355.62      2302797.36     13229895.57
      2303487.46     13229648.17      2303704.46     13229192.48
#Sta/Elev= 30
    3555  144.96  3781.1  127.04  3883.2  124.97  4002.2   123.6  4173.8  117.59
  4367.6  106.62  4464.5  110.49  4487.5  114.39    4590  118.05  4757.1  120.29
  4898.4  111.49  4936.3  106.94  4973.1  107.68  4990.6  104.26    5000   95.99
  5010.6   94.69  5013.1   92.08  5015.8   91.58  5019.1   92.08  5046.8   97.18
  5063.7  106.44  5093.6  107.13  5212.5  113.53  5399.9   129.9  5487.5  133.91
  5614.2  139.11    5732  148.15  5869.5  155.71  5886.6  158.75  6035.6  159.16
#Mann= 9 ,-1 , 0
    3555     .05       0  3883.2     .12       0  4464.5      .1       0
  4973.1     .12       0  5013.1     .07       0  5019.1     .12       0
  5093.6     .16       0  5487.5      .1       0    5732     .05       0
Bank Sta=4898.4,5212.5
XS Rating Curve= 0 ,0
Exp/Cntr=0.3,0.1

Type RM Length L Ch R = 1 ,31570   ,177,177,177
BEGIN DESCRIPTION:
Mapping XS c994716d
END DESCRIPTION:
XS GIS Cut Line= 4
      2302158.66      13230555.9       2302505.9     13230356.24
      2303791.28     13229847.82      2304021.32     13229726.29
#Sta/Elev= 30
    3920  136.99  3933.4  137.62    3948  141.01  3969.5  136.03  4041.7  136.65
  4163.8  134.59  4230.2  133.88  4388.8  129.79  4450.6  124.33  4612.9  110.43
  4701.4  107.28  4709.2  106.95  4822.2  112.63  4876.3  110.55  4922.8  106.77
  4950.3  104.46  4967.7   92.44  4975.5   92.24  4978.2   91.74  4981.5   92.24
  5008.8   97.89  5021.5  106.96  5136.4  109.41  5146.6  110.94  5200.2  116.71
  5243.2  120.99  5308.9  125.94  5687.4  129.38  5902.4   139.1    5963  147.61
#Mann= 16 ,-1 , 0
    3920      .1       0  3933.4     .05       0  4041.7      .1       0
  4163.8     .08       0  4230.2      .1       0  4388.8     .08       0
  4450.6      .1       0  4701.4     .12       0  4709.2      .1       0
  4922.8     .05       0  4950.3     .12       0  4975.5     .07       0
  4981.5     .12       0  5136.4      .1       0  5200.2     .16       0
  5243.2      .1       0
Bank Sta=4876.3,5146.6
XS Rating Curve= 0 ,0
Exp/Cntr=0.3,0.1

Type RM Length L Ch R = 1 ,31393   ,258,258,258
BEGIN DESCRIPTION:
LAGARTO CREEK 22.0
END DESCRIPTION:
XS GIS Cut Line= 3
      2302375.01     13230559.89      2303899.13     13230004.68
      2304593.52     13229869.66
#Sta/Elev= 30
  4160.8  141.18  4326.6  140.59  4362.6  139.67  4573.8  122.45  4593.5   120.9
  4679.4  114.69    4785  106.21  4860.4  105.89  4890.6  107.67  4939.6  109.26
  4961.9  106.19  4993.8   92.42  5012.1    92.1  5014.9    91.6  5018.1    92.1
    5047   95.54  5056.6  103.76    5079     108  5104.1  107.92  5127.3  108.41
  5207.4  112.78  5321.1  124.87  5394.2   125.6  5524.2  125.77  5661.1  125.69
  5838.2  126.74  6027.1  129.44  6039.4  129.55    6464  147.81  6490.3  145.01
#Mann= 20 ,-1 , 0
  4160.8     .05       0  4326.6     .08       0  4362.6     .05       0
  4573.8      .1       0  4593.5     .05       0  4679.4      .1       0
    4785     .16       0  4860.4     .05       0  4890.6      .1       0
  5012.1     .07       0  5018.1      .1       0  5104.1     .16       0
  5127.3     .05       0  5207.4      .1       0  5394.2     .05       0
  5524.2      .1       0  5661.1     .05       0  5838.2      .1       0
  6027.1     .05       0  6039.4      .1       0
Bank Sta=4939.6,5079
XS Rating Curve= 0 ,0
Exp/Cntr=0.3,0.1

Type RM Length L Ch R = 1 ,31135   ,586,586,586
BEGIN DESCRIPTION:
LAGARTO CREEK 21.0
END DESCRIPTION:
XS GIS Cut Line= 2
      2302668.31     13230738.67      2303686.86     13230311.24
#Sta/Elev= 30
  4342.1  134.37  4411.7  131.05  4435.4  128.55  4543.6  123.99  4588.9  122.14
  4764.4  121.29  4807.8  118.32  4916.2  107.23  4959.6  107.87  4970.5  105.27
  4977.9   96.67  4983.3   93.71  4992.2   92.23  5010.8   92.01  5013.6   91.51
  5016.8   92.01  5024.7   92.32  5039.9   102.8  5046.4  107.73  5060.1  107.89
  5068.1  105.75  5131.4  107.09  5154.8  108.79  5190.3   113.7  5213.5  114.63
  5266.5  120.49  5274.1  122.45  5306.7  125.04  5366.9  126.12  5446.7  124.83
#Mann= 6 ,-1 , 0
  4342.1     .05       0  4543.6      .1       0  5010.8     .07       0
  5016.8      .1       0  5039.9     .16       0  5190.3      .1       0
Bank Sta=4959.6,5046.4
XS Rating Curve= 0 ,0
Exp/Cntr=0.3,0.1

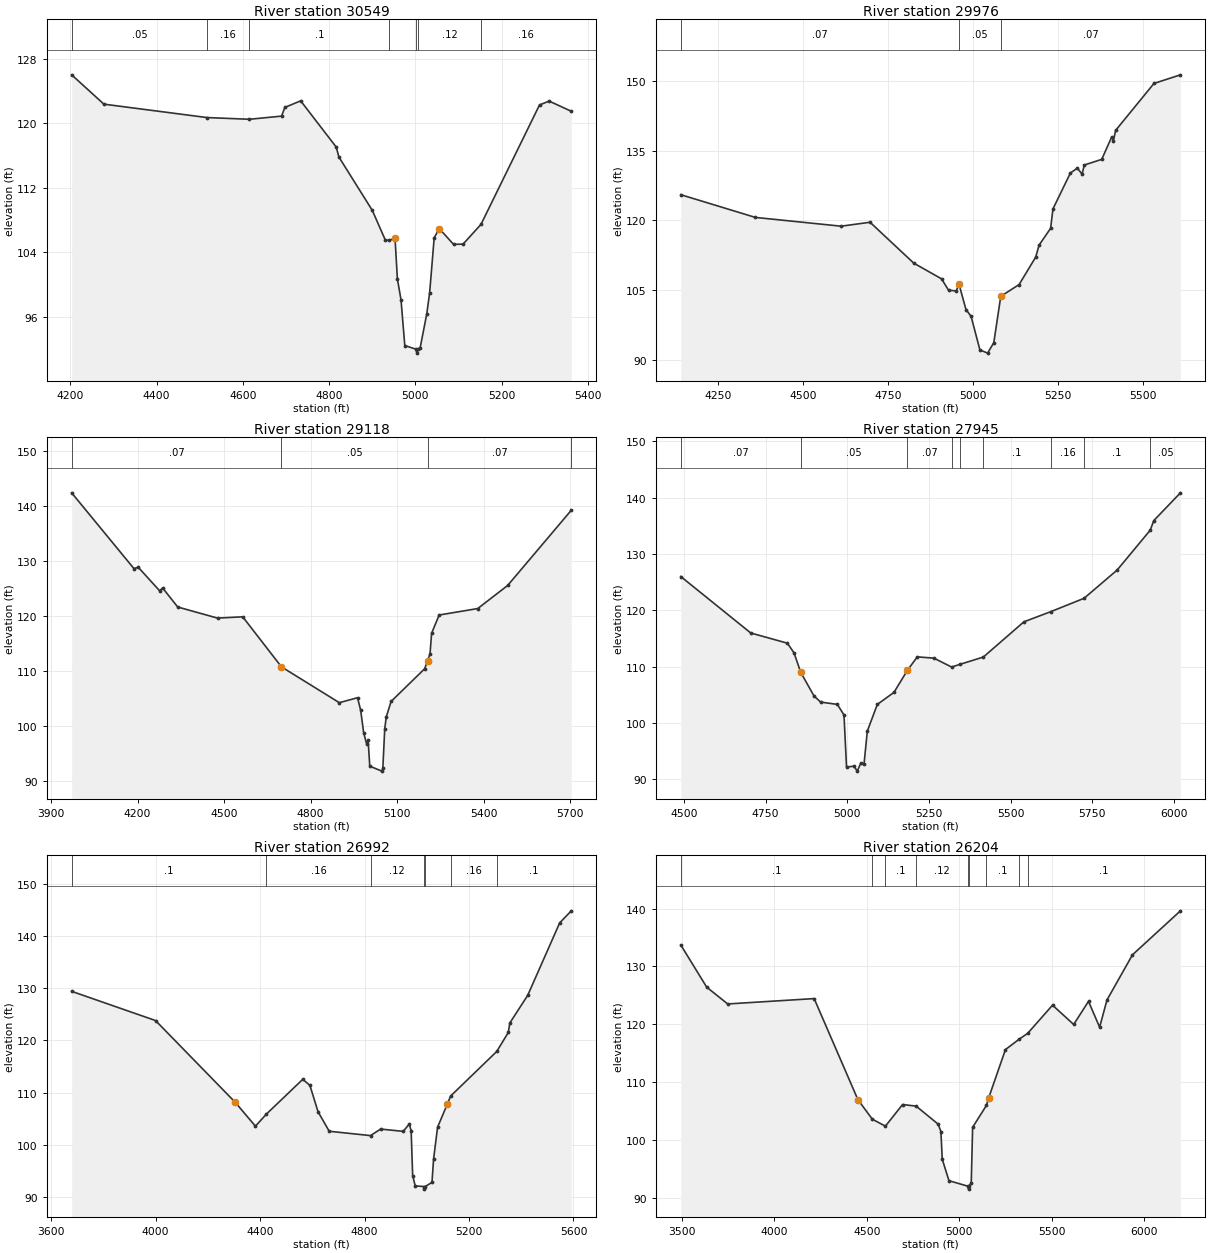
Type RM Length L Ch R = 1 ,30549   ,573,573,573
BEGIN DESCRIPTION:
Mapping XS 6825aa70
END DESCRIPTION:
XS GIS Cut Line= 3
      2302722.93     13231115.08      2303190.48     13231124.19
      2303814.25     13230827.44
#Sta/Elev= 30
  4203.2  125.98    4278  122.35  4517.2  120.69  4615.4  120.48  4689.9  120.87
  4697.5  121.95  4734.2  122.76  4816.6  117.04  4822.8  115.81  4900.3   109.2
  4930.2  105.56  4939.2  105.48  4952.9   105.8  4958.4  100.73  4966.8   98.14
  4975.6   92.48  5000.8   92.04  5003.6   91.54  5006.8   92.04  5011.1   92.17
  5026.6   96.42  5033.2   99.01  5043.7   105.8  5055.4  106.96  5088.6     105
  5110.7  105.03  5152.2  107.47  5287.9  122.25  5310.2  122.73  5361.6  121.47
#Mann= 7 ,-1 , 0
  4203.2     .05       0  4517.2     .16       0  4615.4      .1       0
  4939.2     .12       0  5000.8     .07       0  5006.8     .12       0
  5152.2     .16       0
Bank Sta=4952.9,5055.4
XS Rating Curve= 0 ,0
Exp/Cntr=0.3,0.1

Type RM Length L Ch R = 1 ,29976   ,858,858,858
BEGIN DESCRIPTION:
LAGARTO CREEK 20.0
END DESCRIPTION:
XS GIS Cut Line= 3
      2302790.42     13231506.67      2303352.91     13231430.29
      2304233.81      13231624.5
#Sta/Elev= 30
  4140.7  125.49    4360   120.6  4612.3  118.71  4697.4  119.56  4825.9  110.76
  4907.8  107.37  4928.3  104.92  4950.9  104.78    4959  106.25  4979.5  100.77
  4994.6    99.3  5020.5   92.08  5043.2   91.38  5061.4   93.62  5081.9   103.6
  5135.9  106.15  5184.8  112.07  5194.6  114.63  5228.5  118.25  5235.5  122.44
  5286.7  130.16  5307.2  131.21    5321  129.92  5327.7  131.88  5378.9   133.1
  5408.4  137.95  5413.5  137.15  5419.8  139.34  5532.5  149.44  5610.4   151.3
#Mann= 3 , 0 , 0
  4140.7     .07       0    4959     .05       0  5081.9     .07       0
Bank Sta=4959,5081.9
XS Rating Curve= 0 ,0
Exp/Cntr=0.3,0.1

Type RM Length L Ch R = 1 ,29118   ,1173,1173,1173
BEGIN DESCRIPTION:
LAGARTO CREEK 19.0
END DESCRIPTION:
XS GIS Cut Line= 3
      2302718.86     13232621.27      2304052.22     13232169.87
      2304183.29     13231873.23
#Sta/Elev= 30
  3971.4  142.32  4187.2  128.58  4202.5   128.8  4276.3  124.55  4286.9  125.05
  4339.1   121.6    4477  119.59  4564.4  119.82  4698.7  110.74  4899.3  104.24
  4962.4  105.14  4973.2  102.88  4983.7   98.79  4993.8   96.78  4999.1   97.44
  5004.8   92.72  5046.8   91.82  5050.1   92.32  5056.7    99.5    5062  101.65
  5078.7  104.46  5194.9  110.39  5205.4  111.83  5205.6  111.86  5213.8  113.15
  5219.1  116.82  5245.3  120.15  5379.1  121.32  5482.8  125.51  5703.4  139.16
#Mann= 4 ,-1 , 0
  3971.4     .07       0  4698.7     .05       0  5205.6     .07       0
  5703.4     .05       0
Bank Sta=4698.7,5205.4
XS Rating Curve= 0 ,0
Exp/Cntr=0.3,0.1

Type RM Length L Ch R = 1 ,27945   ,953,953,953
BEGIN DESCRIPTION:
LAGARTO CREEK 18.0
END DESCRIPTION:
XS GIS Cut Line= 3
      2304337.72     13233346.85      2304437.72     13232846.86
      2304237.72     13231846.86
#Sta/Elev= 30
  4490.1     126  4704.3  115.97  4816.4  114.16  4836.8  112.44  4857.2  108.99
    4898  104.78  4918.4  103.69  4969.4  103.29  4989.8   101.4  4997.5   92.17
  5020.4    92.3  5030.3   91.43  5040.8   92.79    5051   92.62  5061.2   98.54
  5091.8  103.28  5142.8  105.42  5183.6  109.31  5214.2  111.73  5265.1   111.5
  5319.3  109.92  5343.8  110.38  5416.5   111.7  5540.5  117.95  5623.3  119.77
  5724.7  122.13    5826  127.15  5927.4  134.24  5938.2  135.94  6019.8  140.87
#Mann= 9 ,-1 , 0
  4490.1     .07       0  4857.2     .05       0  5183.6     .07       0
  5319.3     .08       0  5343.8     .12       0  5416.5      .1       0
  5623.3     .16       0  5724.7      .1       0  5927.4     .05       0
Bank Sta=4857.2,5183.6
XS Rating Curve= 0 ,0
Exp/Cntr=0.3,0.1

Type RM Length L Ch R = 1 ,26992   ,788,788,788
BEGIN DESCRIPTION:
LAGARTO CREEK 17.0
END DESCRIPTION:
XS GIS Cut Line= 3
      2304461.95     13233662.91      2304975.83     13233051.82
      2305545.28     13232093.48
#Sta/Elev= 30
  3678.5   129.4  3999.7  123.81  4304.1  108.21  4382.2   103.6  4424.6  105.93
  4563.5  112.57  4590.8  111.41    4622  106.36  4664.8  102.63  4822.9   101.8
  4861.6  103.05    4948  102.61  4971.3  104.01  4978.5  102.72  4984.3   94.16
  4994.1   92.18  5026.4   92.06  5029.2   91.56  5032.4   92.06  5058.3   92.85
  5064.3   97.28  5079.7  103.41  5116.8   107.8  5129.7  109.37  5306.3   117.9
  5350.5  121.53  5356.4  123.35  5424.6  128.61  5547.3   142.5  5591.7   144.8
#Mann= 7 ,-1 , 0
  3678.5      .1       0  4424.6     .16       0  4822.9     .12       0
  5026.4     .07       0  5032.4     .12       0  5129.7     .16       0
  5306.3      .1       0
Bank Sta=4304.1,5116.8
XS Rating Curve= 0 ,0
Exp/Cntr=0.3,0.1

Type RM Length L Ch R = 1 ,26204   ,934,934,934
BEGIN DESCRIPTION:
Mapping XS 55931afa
END DESCRIPTION:
XS GIS Cut Line= 4
      2304371.68     13234385.12       2304767.5      13233815.7
       2305642.5     13233142.09      2305600.89     13232240.58
#Sta/Elev= 30
  3494.3  133.71  3634.3  126.41  3747.9   123.5    4215  124.43  4451.6  106.93
  4529.5  103.55  4600.2  102.35  4692.9  106.09    4766  105.82  4885.5  102.69
    4900  101.41  4907.4   96.62  4943.6   92.91  5046.5   91.95  5049.3   91.45
  5052.5   91.95    5064   92.53  5071.5  102.15  5146.3  105.95  5157.4  107.17
  5248.8   115.6  5324.6  117.44    5369  118.41  5503.3  123.29  5617.6  119.95
  5697.7  123.95  5757.8  119.48  5797.8  124.21  5935.4  132.01  6194.5  139.62
#Mann= 9 ,-1 , 0
  3494.3      .1       0  4529.5     .07       0  4600.2      .1       0
    4766     .12       0  5046.5     .07       0  5052.5     .12       0
  5146.3      .1       0  5324.6     .16       0    5369      .1       0
Bank Sta=4451.6,5157.4
XS Rating Curve= 0 ,0
Exp/Cntr=0.3,0.1

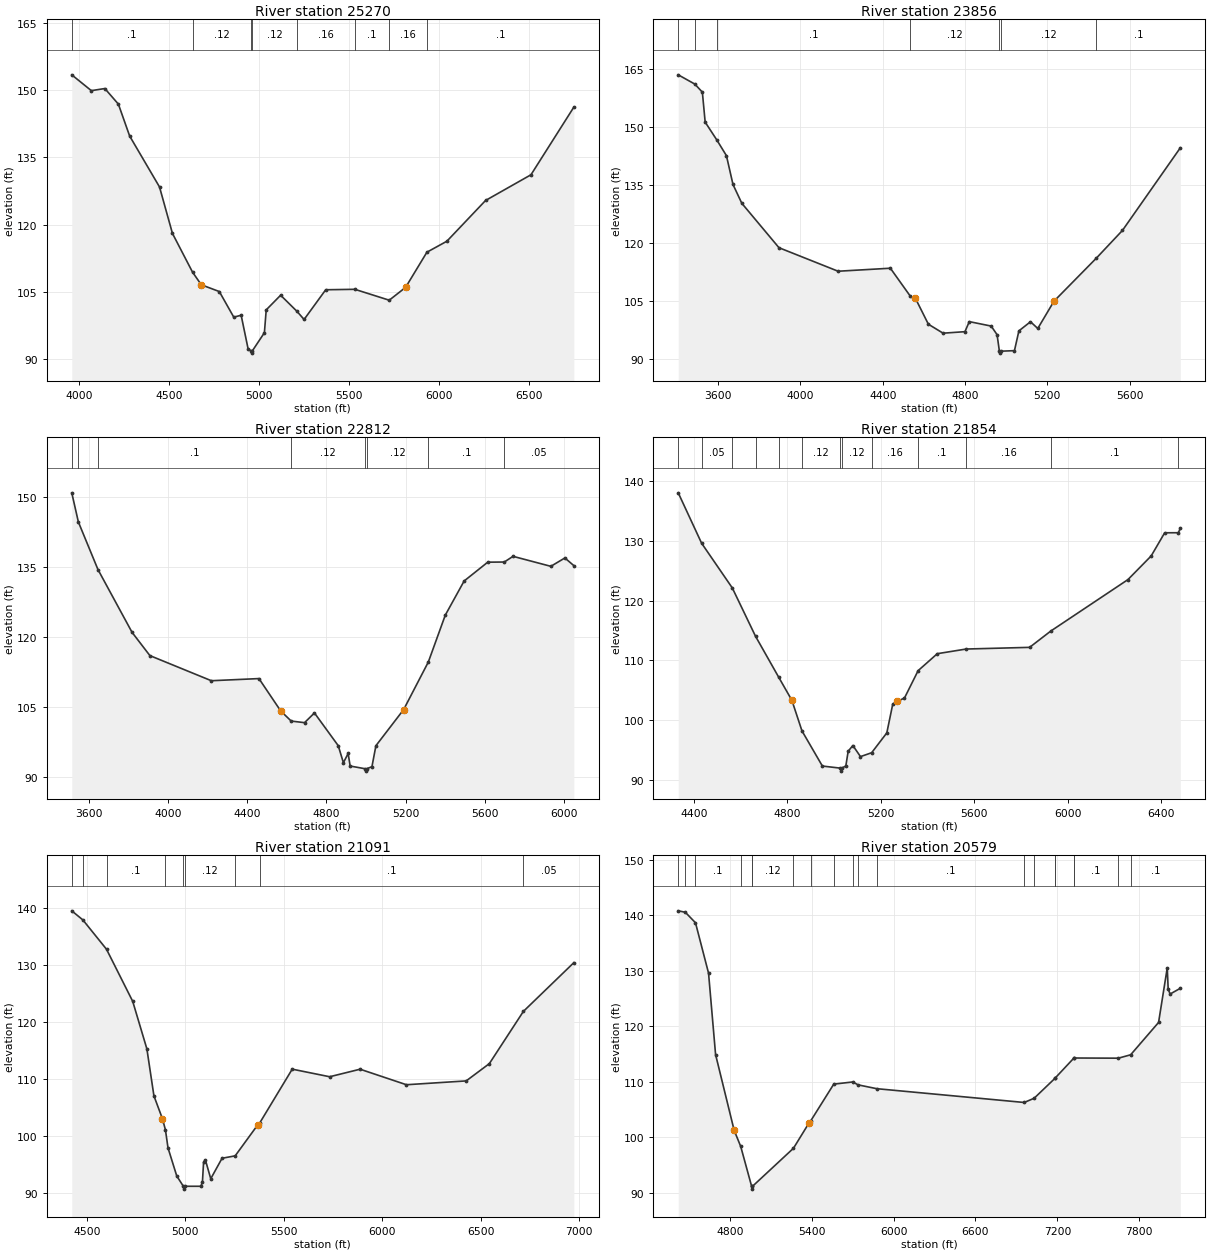
Type RM Length L Ch R = 1 ,25270   ,1414,1414,1414
BEGIN DESCRIPTION:
LAGARTO CREEK 16.0
END DESCRIPTION:
XS GIS Cut Line= 4
      2306010.56     13235017.13      2305871.66     13234496.26
      2305850.83     13233572.65      2305684.27       13232261.
#Sta/Elev= 30
  3961.4  153.44  4069.9  149.91  4144.9  150.38    4220   146.9  4282.5  139.78
  4448.1  128.42  4519.9  118.05  4631.2  109.42  4679.9  106.59  4779.9  105.08
    4860   99.37    4901   99.79    4940   92.21    4957   91.84  4959.7   91.34
    4963   91.84    5030    95.9    5040  100.99    5120  104.26    5210  100.69
  5250.1   98.85  5370.1  105.48  5531.5  105.58  5722.4  103.15  5813.2  106.01
  5931.4  113.86  6042.2  116.31  6256.7   125.4  6508.7  131.14  6746.5  146.23
#Mann= 8 ,-1 , 0
  3961.4      .1       0  4631.2     .12       0    4957     .07       0
    4963     .12       0    5210     .16       0  5531.5      .1       0
  5722.4     .16       0  5931.4      .1       0
Bank Sta=4679.9,5813.2
XS Rating Curve= 0 ,0
Exp/Cntr=0.3,0.1

Type RM Length L Ch R = 1 ,23856   ,1044,1044,1044
BEGIN DESCRIPTION:
LAGARTO CREEK 15.0
END DESCRIPTION:
XS GIS Cut Line= 3
      2306996.65     13234267.07      2306635.55     13233274.04
      2305739.72     13232218.49
#Sta/Elev= 30
  3405.8  163.56  3486.3  161.17  3523.1  159.08  3536.7  151.33  3592.6  146.77
  3640.1  142.65    3672  135.19  3714.9  130.32  3895.5  118.83  4183.1  112.74
  4437.2  113.52  4534.1  106.29  4558.3   105.8    4622   99.03  4693.5   96.71
  4799.8    97.1  4820.9    99.7  4927.4   98.55    4956   96.32  4967.3   92.05
    4970   91.55  4973.3   92.05  5040.5   92.19  5062.1   97.31  5118.5   99.67
  5153.9   97.93  5232.6  104.98  5438.4  116.11  5565.6   123.3  5846.9  144.67
#Mann= 7 ,-1 , 0
  3405.8     .05       0  3486.3     .08       0  3592.6      .1       0
  4534.1     .12       0  4967.3     .07       0  4973.3     .12       0
  5438.4      .1       0
Bank Sta=4558.3,5232.6
XS Rating Curve= 0 ,0
Exp/Cntr=0.3,0.1

Type RM Length L Ch R = 1 ,22812   ,958,958,958
BEGIN DESCRIPTION:
LAGARTO CREEK 14.0
END DESCRIPTION:
XS GIS Cut Line= 3
      2307100.83     13234030.94      2307031.38     13232051.82
      2306629.64     13231670.85
#Sta/Elev= 30
    3515  150.93  3548.3  144.69  3647.3  134.49  3819.3  121.05  3909.3  116.07
  4219.5  110.69  4459.7  111.15  4569.7  104.21  4622.5  102.05  4689.8  101.71
  4739.8  103.79  4859.9   96.78  4885.9   93.13  4909.9   95.11    4920   92.42
    4997   91.83  4999.7   91.33    5003   91.83    5030   92.28    5050   96.77
  5190.1  104.52  5314.7  114.71  5400.2  124.74  5495.3  132.05  5614.5  136.08
    5698  136.11    5742  137.33  5932.9  135.19  6003.7  136.98    6049  135.34
#Mann= 8 ,-1 , 0
    3515     .05       0  3548.3     .08       0  3647.3      .1       0
  4622.5     .12       0    4997     .07       0    5003     .12       0
  5314.7      .1       0    5698     .05       0
Bank Sta=4569.7,5190.1
XS Rating Curve= 0 ,0
Exp/Cntr=0.3,0.1

Type RM Length L Ch R = 1 ,21854   ,763,763,763
BEGIN DESCRIPTION:
LAGARTO CREEK 13.0
END DESCRIPTION:
XS GIS Cut Line= 3
      2307920.27     13233461.53      2307816.11     13232267.09
      2307066.12     13231683.77
#Sta/Elev= 30
  4332.8  138.03  4432.9  129.59  4564.2  122.11  4663.6  114.02    4763  107.15
  4819.3  103.29  4862.4   98.18  4949.8   92.29  5027.1   91.94  5029.9   91.44
  5033.1   91.94  5050.2   92.31  5060.2   94.77  5080.3   95.73  5112.9   93.87
  5160.7   94.52  5225.6   97.84  5250.9  102.63    5271  103.15  5301.1  103.67
  5359.6  108.26  5441.7   111.1  5565.3  111.88  5836.8  112.16  5927.5  114.89
  6257.6   123.5  6357.1  127.46    6415  131.34  6473.3  131.35  6481.9  132.06
#Mann= 13 ,-1 , 0
  4332.8      .1       0  4432.9     .05       0  4564.2      .1       0
  4663.6     .05       0    4763     .07       0  4862.4     .12       0
  5027.1     .07       0  5033.1     .12       0  5160.7     .16       0
  5359.6      .1       0  5565.3     .16       0  5927.5      .1       0
  6473.3     .05       0
Bank Sta=4819.3,5271
XS Rating Curve= 0 ,0
Exp/Cntr=0.3,0.1

Type RM Length L Ch R = 1 ,21091   ,512,512,512
BEGIN DESCRIPTION:
LAGARTO CREEK 12.0
END DESCRIPTION:
XS GIS Cut Line= 3
      2308823.07      13233107.4      2308156.38     13232072.65
       2306996.7     13231447.67
#Sta/Elev= 30
  4424.2  139.47  4480.7  137.87  4600.5  132.74  4733.5  123.61  4805.5  115.27
  4841.2  107.05  4884.6  103.02  4899.7  101.08  4912.6   97.94  4957.2      93
  4990.6   91.21  4993.3   90.71  4996.6   91.21  5079.1   91.21  5087.3   91.91
  5093.2   95.42  5102.5   95.82  5129.6   92.53    5187   96.12  5253.6   96.54
  5368.5  101.99    5379  102.35  5543.1  111.73  5733.1   110.4  5887.6  111.72
  6122.8     109  6426.1  109.67  6543.7   112.7  6716.4  121.85  6972.5  130.39
#Mann= 9 ,-1 , 0
  4424.2      .1       0  4480.7     .05       0  4600.5      .1       0
  4899.7     .12       0  4990.6     .07       0  4996.6     .12       0
  5253.6     .16       0    5379      .1       0  6716.4     .05       0
Bank Sta=4884.6,5368.5
XS Rating Curve= 0 ,0
Exp/Cntr=0.3,0.1

Type RM Length L Ch R = 1 ,20579   ,535,535,535
BEGIN DESCRIPTION:
Mapping XS b081284c
END DESCRIPTION:
XS GIS Cut Line= 3
      2309201.53     13232780.95      2308586.94     13231829.59
      2306836.91     13229982.34
#Sta/Elev= 30
  4422.9  140.78  4474.8  140.52  4549.3  138.63  4644.9  129.57  4696.4  114.92
  4832.5  101.28  4880.5   98.39  4960.5   91.21  4963.3   90.71  4966.5   91.21
  5266.7   98.06  5382.6  102.69  5393.2  102.99  5561.9   109.6  5701.2  109.99
    5740  109.47  5877.2  108.78  6956.9   106.3  7029.6  107.06  7181.5  110.63
  7182.7  110.67    7321   114.3  7321.1   114.3  7646.5  114.27  7736.4  114.88
  7940.9   120.7  8004.4  130.51  8011.3  126.69  8025.4  125.81  8100.1  126.84
#Mann= 20 ,-1 , 0
  4422.9      .1       0  4474.8     .08       0  4549.3      .1       0
  4880.5     .12       0  4960.5     .07       0  4966.5     .12       0
  5266.7     .08       0  5393.2      .1       0  5561.9     .05       0
  5701.2      .1       0    5740     .05       0  5877.2      .1       0
  6956.9     .16       0  7029.6      .1       0  7181.5     .16       0
  7182.7      .1       0    7321     .16       0  7321.1      .1       0
  7646.5     .16       0  7736.4      .1       0
Bank Sta=4832.5,5382.6
XS Rating Curve= 0 ,0
Exp/Cntr=0.3,0.1