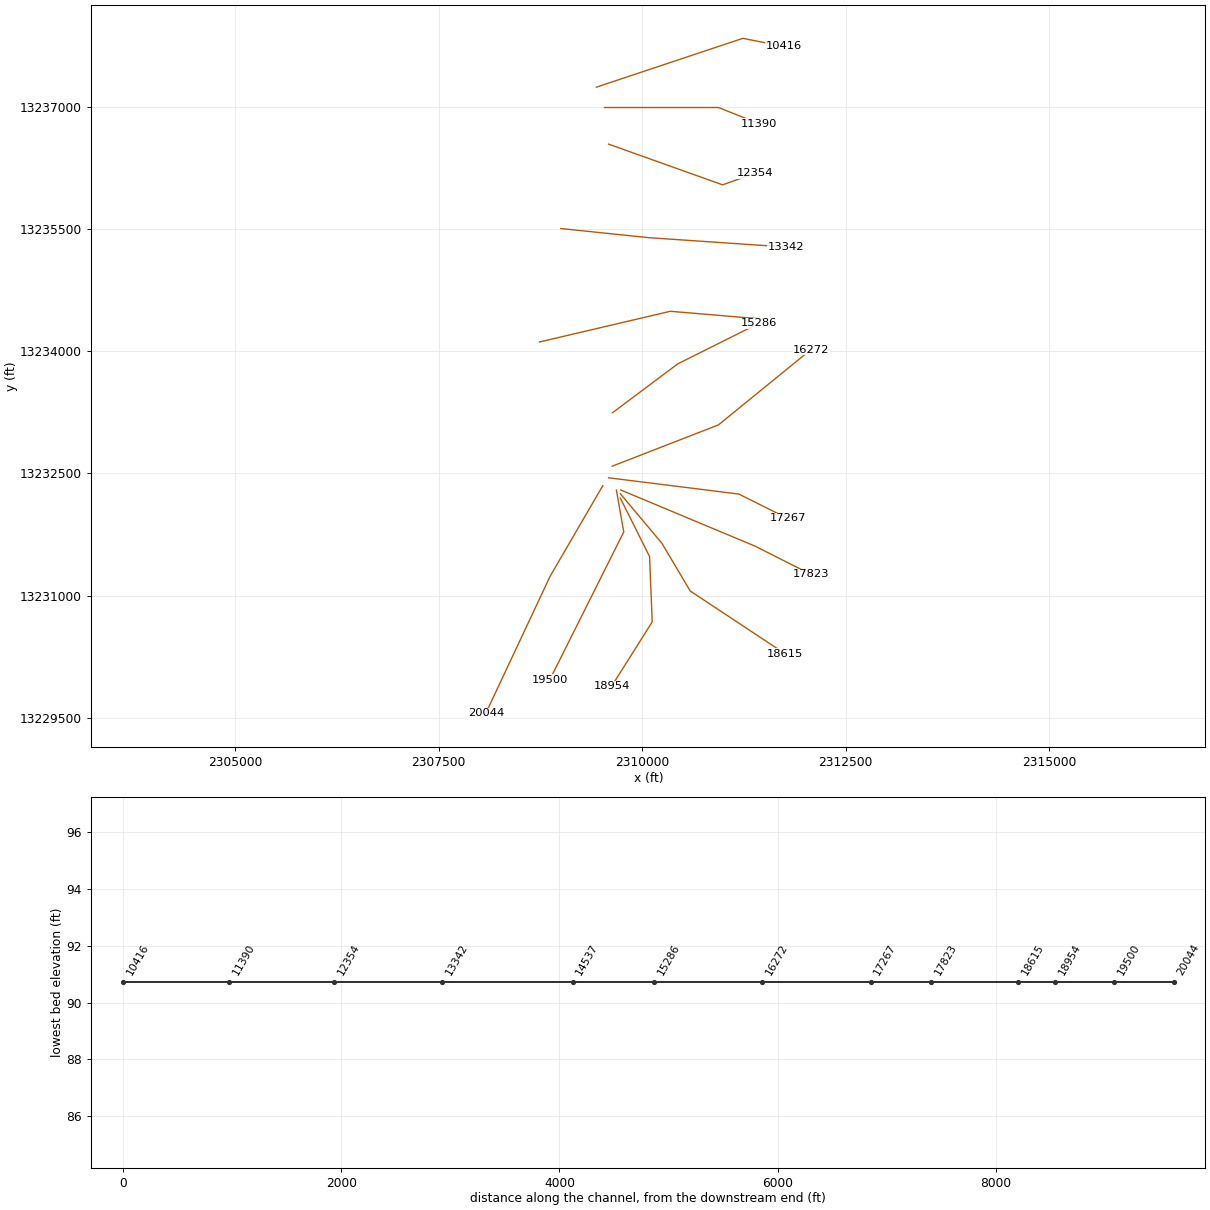
HEC-RAS study LAGARTO CREEK.prj: LAGARTO CREEK Base Level Engineering

--- LAGARTO CREEK.g01 (geometry) --- (continued)

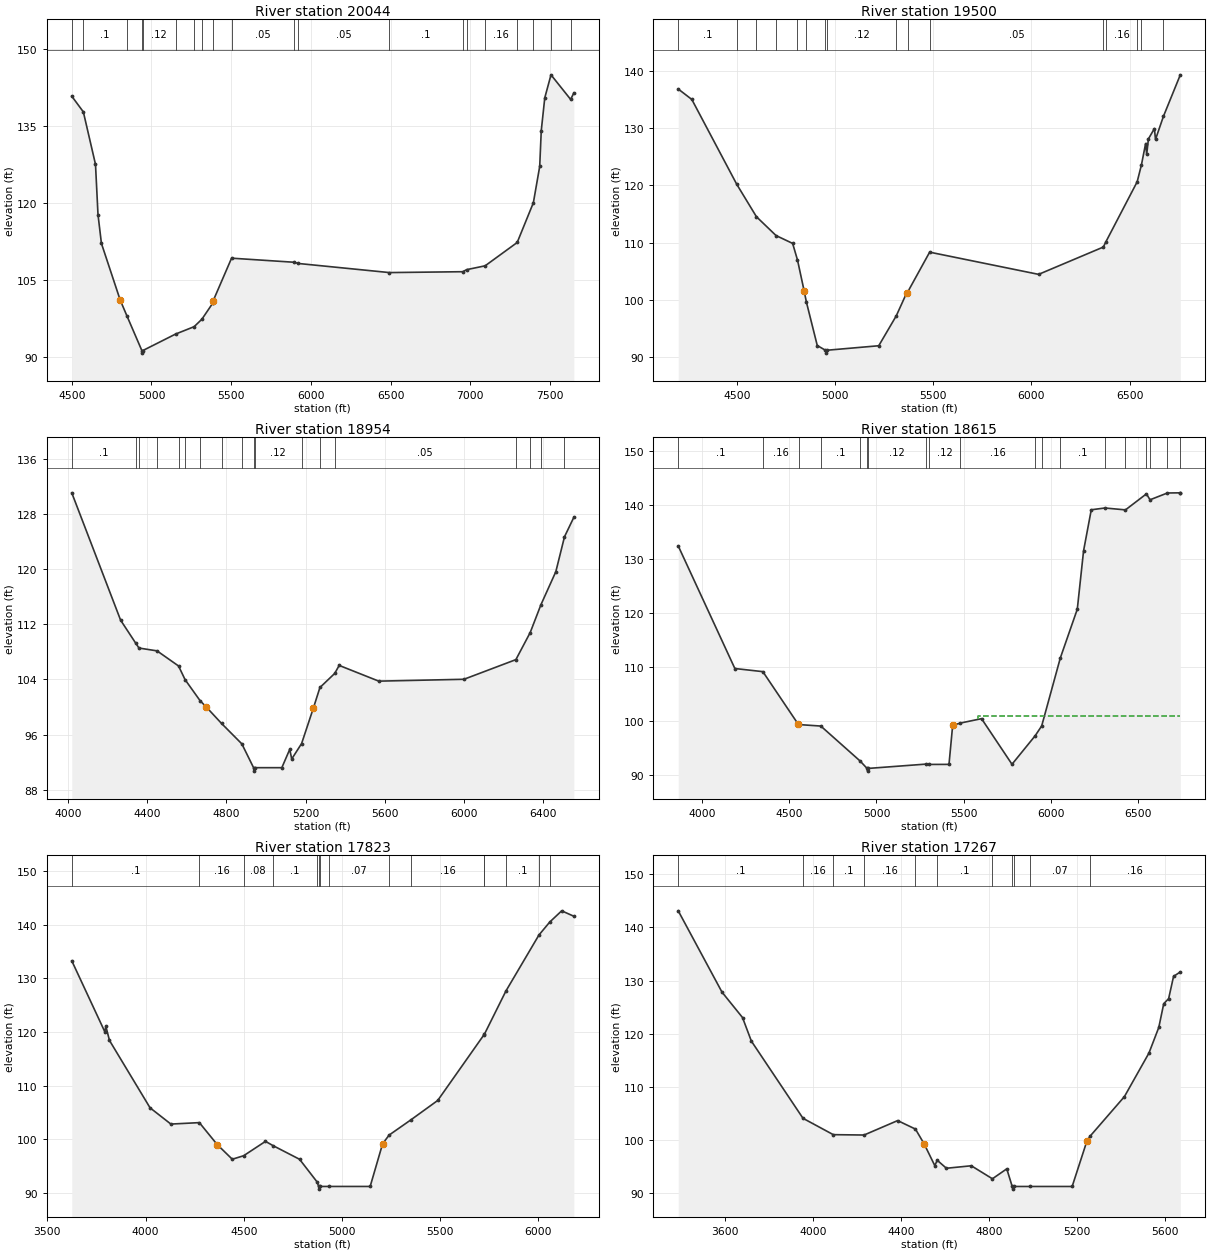
Type RM Length L Ch R = 1 ,20044   ,544,544,544
BEGIN DESCRIPTION:
LAGARTO CREEK 11.0
END DESCRIPTION:
XS GIS Cut Line= 3
      2309517.52     13232350.47      2308871.66     13231239.32
      2308079.99     13229551.81
#Sta/Elev= 30
  4500.1  140.82  4572.7  137.76  4648.9  127.53  4664.6  117.73  4686.1  112.11
  4803.7  101.07  4845.4   98.02  4939.7   91.21  4942.5   90.71  4945.7   91.21
  5151.4   94.43  5267.7   95.87  5316.4   97.33    5384  100.44  5387.2  100.93
  5502.4  109.23  5896.6  108.43  5919.8   108.2  6492.3  106.42  6952.7  106.59
  6976.8  106.99  7092.9  107.74    7294  112.29  7395.4  120.04  7435.2  127.13
  7444.9   134.1    7467  140.51    7506  144.99  7629.3  140.19  7649.3  141.47
#Mann= 20 ,-1 , 0
  4500.1      .1       0  4572.7      .1       0  4845.4     .12       0
  4939.7     .07       0  4945.7     .12       0  5151.4     .05       0
  5267.7     .16       0  5316.4     .05       0    5384     .08       0
  5502.4     .05       0  5896.6      .1       0  5919.8     .05       0
  6492.3      .1       0  6952.7     .16       0  6976.8      .1       0
  7092.9     .16       0    7294      .1       0  7395.4     .16       0
    7506      .1       0  7629.3     .08       0
Bank Sta=4803.7,5387.2
XS Rating Curve= 0 ,0
Exp/Cntr=0.3,0.1

Type RM Length L Ch R = 1 ,19500   ,546,546,546
BEGIN DESCRIPTION:
LAGARTO CREEK 10.0
END DESCRIPTION:
XS GIS Cut Line= 3
      2309684.16      13232294.9      2309774.44     13231780.98
       2308864.8     13229961.71
#Sta/Elev= 30
  4201.8  136.85  4270.9  135.03  4500.1  120.18  4599.9  114.54  4699.7  111.25
  4784.1  109.88  4808.9  106.98  4842.4  101.63  4854.5   99.59  4909.5   92.04
  4951.2   91.21    4954   90.71  4957.2   91.21  5222.5      92  5311.8   97.23
  5365.5   101.3  5369.4  101.36  5481.6  108.35  6036.3  104.47  6365.6  109.24
  6378.5  110.14  6538.1  120.65  6559.8  123.61    6581  127.33  6586.5  125.44
  6595.3  128.14  6625.7  129.94  6631.3  128.04  6671.7  132.08  6757.6  139.33
#Mann= 16 ,-1 , 0
  4201.8      .1       0  4500.1     .08       0  4599.9      .1       0
  4699.7     .12       0  4808.9      .1       0  4854.5     .12       0
  4951.2     .07       0  4957.2     .12       0  5311.8     .08       0
  5369.4     .12       0  5481.6     .05       0  6365.6      .1       0
  6378.5     .16       0  6538.1      .1       0  6559.8     .16       0
  6671.7      .1       0
Bank Sta=4842.4,5365.5
XS Rating Curve= 0 ,0
Exp/Cntr=0.3,0.1

Type RM Length L Ch R = 1 ,18954   ,339,339,339
BEGIN DESCRIPTION:
Mapping XS 9ea5066a
END DESCRIPTION:
XS GIS Cut Line= 4
      2309733.23     13232195.07      2310091.31     13231478.91
      2310123.86     13230675.95      2309624.71     13229883.82
#Sta/Elev= 30
  4017.1  131.07  4264.3   112.6  4339.7  109.31  4357.2  108.56  4448.6  108.15
  4557.4  105.96  4590.4  103.98  4666.3  100.93  4697.1  100.03  4775.1   97.62
  4877.8   94.66    4937   91.21  4939.7   90.71    4943   91.21  5080.1   91.21
  5120.1   93.87  5130.1   92.47  5180.1   94.71  5240.2    99.9  5272.9  102.84
  5347.4  104.87  5370.3  106.04  5570.5  103.76  6001.6  104.03  6264.4  106.88
  6336.9  110.81  6391.4  114.86  6466.6  119.64  6510.4   124.7  6557.7  127.52
#Mann= 18 ,-1 , 0
  4017.1      .1       0  4339.7     .08       0  4357.2     .16       0
  4448.6     .08       0  4557.4      .1       0  4590.4     .08       0
  4666.3     .12       0  4775.1      .1       0  4877.8     .12       0
    4937     .07       0    4943     .12       0  5180.1     .16       0
  5272.9     .08       0  5347.4     .05       0  6264.4     .16       0
  6336.9      .1       0  6391.4     .08       0  6510.4      .1       0
Bank Sta=4697.1,5240.2
XS Rating Curve= 0 ,0
Exp/Cntr=0.3,0.1

Type RM Length L Ch R = 1 ,18615   ,792,792,792
BEGIN DESCRIPTION:
Mapping XS c435f89e
END DESCRIPTION:
XS GIS Cut Line= 4
      2309733.22     13232249.32      2310243.22     13231641.67
      2310590.44     13231055.73      2311759.92      13230281.4
#Sta/Elev= 30
    3864  132.43  4188.5  109.72  4348.9  109.14  4550.1   99.47  4557.9   99.33
    4681   99.06  4906.7   92.57  4946.1   91.21  4948.9   90.71  4952.1   91.21
  5283.2   92.01    5301   91.95  5415.5   91.96  5436.5   99.18  5480.2   99.61
    5602  100.43  5776.5   91.98  5909.2   97.26  5946.6   99.08  6053.5  111.68
  6150.7  120.71  6186.7  131.54  6230.8  139.13  6308.9  139.46  6426.8  139.11
  6546.9  142.08  6567.4  140.98    6667  142.24  6738.7  142.27    6741  142.23
#Mann= 19 ,-1 , 0
    3864      .1       0  4348.9     .16       0  4557.9     .08       0
    4681      .1       0  4906.7     .12       0  4946.1     .07       0
  4952.1     .12       0  5283.2     .16       0    5301     .12       0
  5480.2     .16       0  5909.2     .08       0  5946.6     .16       0
  6053.5      .1       0  6308.9     .16       0  6426.8     .08       0
  6546.9     .05       0  6567.4     .08       0    6667     .05       0
  6738.7     .08       0
#XS Ineff= 2 , 0
                         5581.05          100.87
Permanent Ineff=
       F       F
Bank Sta=4550.1,5436.5
XS Rating Curve= 0 ,0
Exp/Cntr=0.3,0.1

Type RM Length L Ch R = 1 ,17823   ,556,556,556
BEGIN DESCRIPTION:
LAGARTO CREEK 9.0
END DESCRIPTION:
XS GIS Cut Line= 3
      2309737.75     13232296.84      2311385.55     13231607.37
      2312073.01     13231260.17
#Sta/Elev= 30
  3624.4  133.25  3792.6  120.03    3798  121.03  3816.4  118.41    4023  105.86
    4129  102.83    4274   103.1  4364.8   99.02  4441.6   96.28  4499.4   96.93
  4610.8   99.61  4648.9   98.82  4784.3   96.27  4874.1   92.02  4881.1   91.21
  4883.8   90.71  4887.1   91.21  4932.1   91.21  5143.7   91.21    5207   99.15
  5240.2  100.78  5350.5   103.6  5487.7  107.23  5723.3  119.47  5725.3  119.56
  5834.9  127.62    6003  138.05  6058.1  140.47  6118.9  142.56  6180.8  141.55
#Mann= 15 ,-1 , 0
  3624.4      .1       0    4274     .16       0  4499.4     .08       0
  4648.9      .1       0  4874.1     .12       0  4881.1     .07       0
  4887.1     .12       0  4932.1     .07       0  5240.2     .08       0
  5350.5     .16       0  5723.3      .1       0  5725.3     .16       0
  5834.9      .1       0    6003     .08       0  6058.1      .1       0
Bank Sta=4364.8,5207
XS Rating Curve= 0 ,0
Exp/Cntr=0.3,0.1

Type RM Length L Ch R = 1 ,17267   ,995,995,995
BEGIN DESCRIPTION:
LAGARTO CREEK 8.0
END DESCRIPTION:
XS GIS Cut Line= 3
      2309587.67     13232446.86      2311187.72     13232246.85
       2311787.7     13231946.86
#Sta/Elev= 30
  3387.5  143.13  3586.6  127.81  3679.8  123.03  3720.1  118.59  3954.9  104.05
  4092.6  100.97  4232.6   100.9  4385.3  103.62  4466.3  102.02  4506.2    99.2
  4554.1   95.15  4565.6   96.14    4607   94.64  4720.3   95.11  4816.3   92.66
  4881.6   94.53  4906.3   91.21    4909   90.71  4912.3   91.21  4986.2   91.21
  5178.9   91.21    5246   99.76  5259.8  100.65  5416.5  108.13  5528.3  116.35
    5573  121.18  5595.4  125.64  5617.7  126.59  5640.1  130.78  5670.8  131.62
#Mann= 11 ,-1 , 0
  3387.5      .1       0  3954.9     .16       0  4092.6      .1       0
  4232.6     .16       0  4466.3     .05       0  4565.6      .1       0
  4816.3     .12       0  4906.3     .07       0  4912.3     .12       0
  4986.2     .07       0  5259.8     .16       0
Bank Sta=4506.2,5246
XS Rating Curve= 0 ,0
Exp/Cntr=0.3,0.1

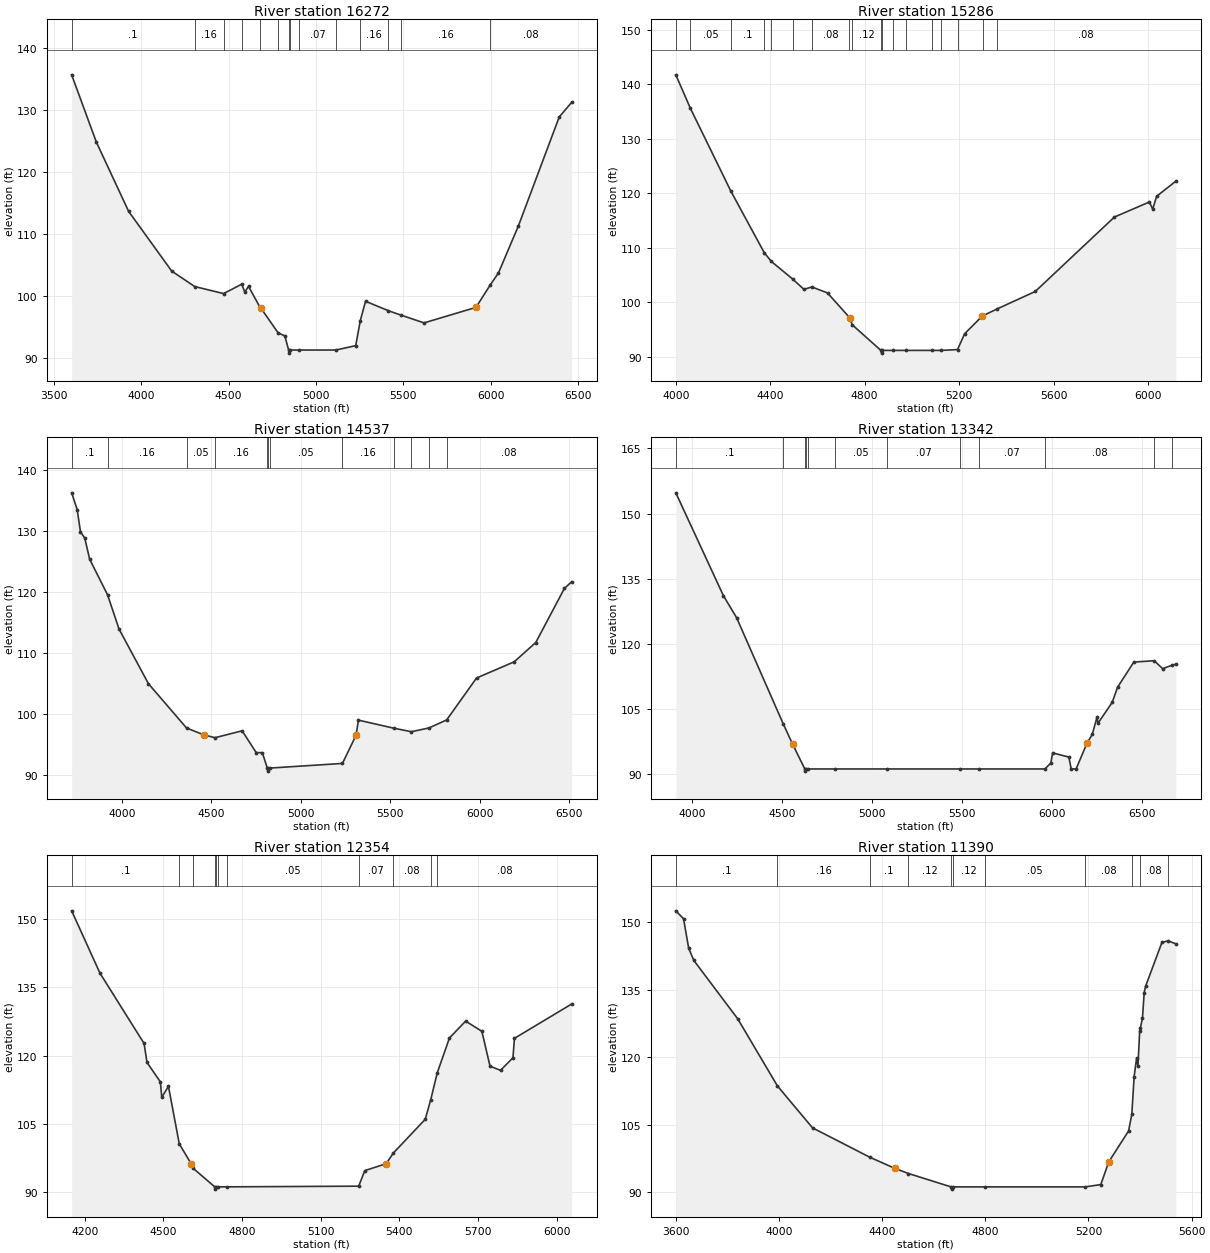
Type RM Length L Ch R = 1 ,16272   ,986,986,986
BEGIN DESCRIPTION:
LAGARTO CREEK 7.0
END DESCRIPTION:
XS GIS Cut Line= 3
      2309633.67      13232589.7      2310937.72     13233096.85
      2312072.74     13234021.85
#Sta/Elev= 30
  3600.8  135.72    3742  124.85    3927  113.64  4173.8  103.98  4305.4  101.48
  4470.8  100.34  4574.9  101.86  4592.3  100.59  4613.7  101.51  4679.1   98.14
  4683.1   98.05  4783.2   93.99  4821.8   93.49  4843.3   91.21  4846.1   90.71
  4849.3   91.21  4903.3   91.21  5114.5   91.21  5227.6   91.92  5253.7   95.95
  5283.8    99.1  5414.6   97.57  5484.5   96.88    5619    95.6  5916.3   98.11
  5997.7  101.72  6044.9  103.67    6159  111.26  6393.2  128.91  6464.2  131.26
#Mann= 14 ,-1 , 0
  3600.8      .1       0  4305.4     .16       0  4470.8      .1       0
  4574.9     .08       0  4679.1      .1       0  4783.2     .12       0
  4843.3     .07       0  4849.3     .12       0  4903.3     .07       0
  5114.5     .12       0  5253.7     .16       0  5414.6     .08       0
  5484.5     .16       0  5997.7     .08       0
Bank Sta=4683.1,5916.3
XS Rating Curve= 0 ,0
Exp/Cntr=0.3,0.1

Type RM Length L Ch R = 1 ,15286   ,749,749,749
BEGIN DESCRIPTION:
LAGARTO CREEK 6.0
END DESCRIPTION:
XS GIS Cut Line= 3
      2309637.72     13233246.85      2310437.72     13233846.85
      2311437.69     13234346.84
#Sta/Elev= 30
    4000  141.77  4061.9  135.61  4233.3  120.42  4374.2  109.17  4404.7  107.53
  4494.3  104.33  4542.7  102.41  4576.2  102.85  4642.7  101.75  4734.4   97.31
  4736.5   97.17  4747.6    95.9  4868.9   91.21  4871.6   90.71  4874.9   91.21
    4919   91.21  4974.5   91.21  5085.2   91.21  5123.9   91.21  5193.3   91.36
  5223.6   94.27  5299.1   97.55  5301.5   97.58  5358.7   98.77  5522.7  102.02
  5858.1  115.68  6006.2  118.44  6020.2  117.13    6037  119.49    6118  122.25
#Mann= 18 ,-1 , 0
    4000      .1       0  4061.9     .05       0  4233.3      .1       0
  4374.2     .05       0  4404.7     .08       0  4494.3     .16       0
  4576.2     .08       0  4734.4      .1       0  4747.6     .12       0
  4868.9    .033       0  4874.9     .12       0    4919     .07       0
  4974.5     .05       0  5085.2     .07       0  5123.9     .12       0
  5193.3     .07       0  5301.5     .16       0  5358.7     .08       0
Bank Sta=4736.5,5299.1
XS Rating Curve= 0 ,0
Exp/Cntr=0.3,0.1

Type RM Length L Ch R = 1 ,14537   ,1195,1195,1195
BEGIN DESCRIPTION:
LAGARTO CREEK 5.0
END DESCRIPTION:
XS GIS Cut Line= 3
      2308739.82     13234115.41      2310345.62     13234492.79
      2311487.75     13234396.85
#Sta/Elev= 30
  3718.1  136.33  3749.1  133.57  3767.3  129.95  3791.5   128.9  3818.7  125.45
  3918.8  119.61    3983     114  4147.4  105.04  4360.5   97.78  4455.6   96.67
  4519.7   96.19  4671.3   97.32    4750   93.75  4784.3   93.73  4812.1   91.21
  4814.8   90.71  4818.1   91.21  4825.9   91.21  5232.2   91.97  5308.2   96.59
  5321.7   99.07    5519   97.75  5617.7   97.17  5716.5   97.79  5815.2   99.11
  5981.9  105.97  6192.6  108.63  6313.1  111.79  6473.6  120.67  6513.8  121.75
#Mann= 12 ,-1 , 0
  3718.1      .1       0  3918.8     .16       0  4360.5     .05       0
  4519.7     .16       0  4812.1    .033       0  4818.1     .16       0
  4825.9     .05       0  5232.2     .16       0    5519     .05       0
  5617.7     .08       0  5716.5     .16       0  5815.2     .08       0
Bank Sta=4455.6,5308.2
XS Rating Curve= 0 ,0
Exp/Cntr=0.3,0.1

Type RM Length L Ch R = 1 ,13342   ,988,988,988
BEGIN DESCRIPTION:
LAGARTO CREEK 4.0
END DESCRIPTION:
XS GIS Cut Line= 3
      2309001.74     13235509.38      2310087.72     13235396.85
      2311770.42     13235282.19
#Sta/Elev= 30
  3908.2  154.76  4172.9  131.07    4246  126.02  4505.7  101.53  4557.6   96.89
    4625   91.21  4627.8   90.71    4631   91.21  4640.6   91.21  4792.3   91.21
  5082.9   91.21    5488   91.21  5594.5   91.21  5959.2   91.21  5992.3   92.58
  6002.3   94.91  6092.5   93.94  6105.4   91.21  6132.6   91.21  6192.8   97.11
  6222.8   99.18  6249.1  103.19  6254.1  101.72  6333.1  106.52  6363.2  110.03
  6453.4  115.81  6566.5  116.12  6613.7  114.29    6665  115.07  6686.6  115.31
#Mann= 12 ,-1 , 0
  3908.2      .1       0  4505.7     .05       0    4625    .033       0
    4631     .05       0  4640.6     .07       0  4792.3     .05       0
  5082.9     .07       0    5488     .05       0  5594.5     .07       0
  5959.2     .08       0  6566.5     .16       0    6665      .1       0
Bank Sta=4557.6,6192.8
XS Rating Curve= 0 ,0
Exp/Cntr=0.3,0.1

Type RM Length L Ch R = 1 ,12354   ,964,964,964
BEGIN DESCRIPTION:
LAGARTO CREEK 3.0
END DESCRIPTION:
XS GIS Cut Line= 3
      2309587.71     13236546.86      2310987.72     13236046.85
      2311383.48     13236186.23
#Sta/Elev= 30
  4150.5  151.78  4258.3  138.11  4426.6  122.67  4437.7  118.51  4488.7  114.24
    4494  110.85  4519.5  113.28  4560.8  100.65  4606.6   96.23  4612.5   95.34
    4696   91.21  4698.7   90.71    4702   91.21  4708.5   91.21  4744.5   91.21
  5244.8   91.36  5268.1   94.77  5349.9    96.3  5376.6   98.61  5498.5  106.03
  5519.2  110.26  5544.4  116.24  5590.9  123.88  5652.6  127.58  5714.5  125.34
  5745.5   117.7  5785.5  116.77    5833  119.54  5838.6   123.8  6056.7  131.33
#Mann= 11 ,-1 , 0
  4150.5      .1       0  4560.8     .16       0  4612.5      .1       0
    4696    .033       0    4702      .1       0  4708.5     .12       0
  4744.5     .05       0  5244.8     .07       0  5376.6     .08       0
  5519.2     .16       0  5544.4     .08       0
Bank Sta=4606.6,5349.9
XS Rating Curve= 0 ,0
Exp/Cntr=0.3,0.1

Type RM Length L Ch R = 1 ,11390   ,974,974,974
BEGIN DESCRIPTION:
LAGARTO CREEK 2.0
END DESCRIPTION:
XS GIS Cut Line= 3
      2309537.72     13236996.85      2310937.72     13236996.85
      2311437.71     13236796.86
#Sta/Elev= 30
    3600  152.52    3630  150.76    3650  144.17    3670  141.49    3840  128.54
  3993.8  113.64    4130  104.32  4352.3   97.79    4450    95.3  4502.1   94.18
    4667   91.21  4669.8   90.71    4673   91.21  4796.9   91.21  5187.4   91.21
  5247.7   91.72  5278.7   96.78  5355.4  103.62    5368  107.32    5377  115.69
  5386.4  119.74  5391.8  118.06  5398.5  125.77  5401.4  126.55  5409.3  128.66
    5416  134.38  5421.4  135.76  5484.7   145.5  5508.3  145.85  5538.5   145.2
#Mann= 11 ,-1 , 0
    3600      .1       0  3993.8     .16       0  4352.3      .1       0
  4502.1     .12       0    4667    .033       0    4673     .12       0
  4796.9     .05       0  5187.4     .08       0    5368      .1       0
  5401.4     .08       0  5508.3      .1       0
Bank Sta=4450,5278.7
XS Rating Curve= 0 ,0
Exp/Cntr=0.3,0.1

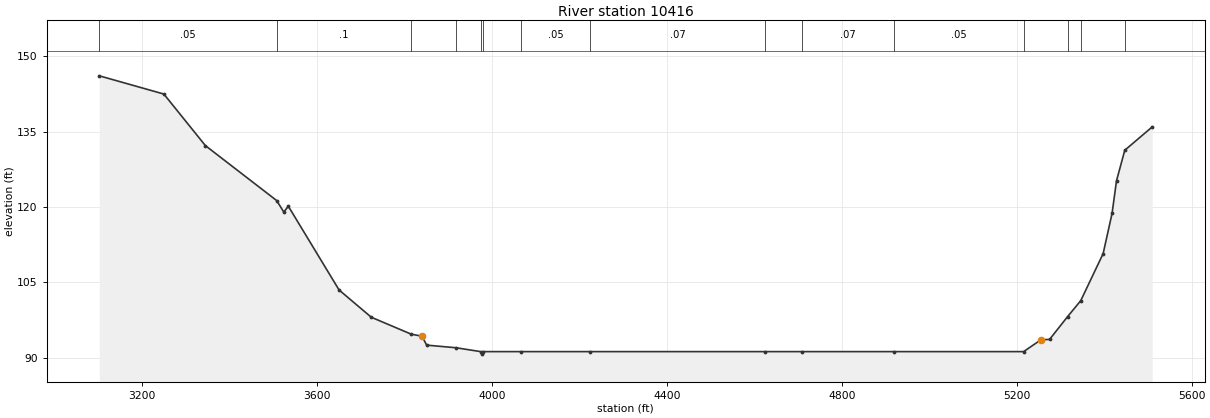
Type RM Length L Ch R = 1 ,10416   ,0,0,0
BEGIN DESCRIPTION:
LAGARTO CREEK 1.0
END DESCRIPTION:
XS GIS Cut Line= 3
      2309437.69     13237246.84      2311237.72     13237846.85
      2311737.72     13237746.86
#Sta/Elev= 30
  3102.6  146.12  3250.2  142.49  3345.1  132.23  3508.2  121.28  3524.3     119
  3534.8  120.15  3650.8  103.48  3724.5   98.05  3815.6   94.69  3840.5   94.27
    3851    92.5  3918.1   91.98  3974.5   91.21  3977.3   90.71  3980.5   91.21
  4066.9   91.21  4225.5   91.21  4624.2   91.21  4708.1   91.21  4920.3   91.21
  5215.9   91.21    5255   93.54  5275.3   93.65  5316.6    98.2  5346.5  101.36
  5397.7  110.73  5418.1  118.74  5428.3  125.25  5447.2  131.31  5509.9  135.95
#Mann= 15 ,-1 , 0
  3102.6     .05       0  3508.2      .1       0  3815.6     .16       0
  3918.1     .07       0  3974.5    .033       0  3980.5     .07       0
  4066.9     .05       0  4225.5     .07       0  4624.2     .12       0
  4708.1     .07       0  4920.3     .05       0  5215.9     .07       0
  5316.6      .1       0  5346.5     .08       0  5447.2      .1       0
Bank Sta=3840.5,5255
XS Rating Curve= 0 ,0
Exp/Cntr=0.3,0.1

Chan Stop Cuts=-1
Use User Specified Reach Order=0
Composite Channel Slope=5