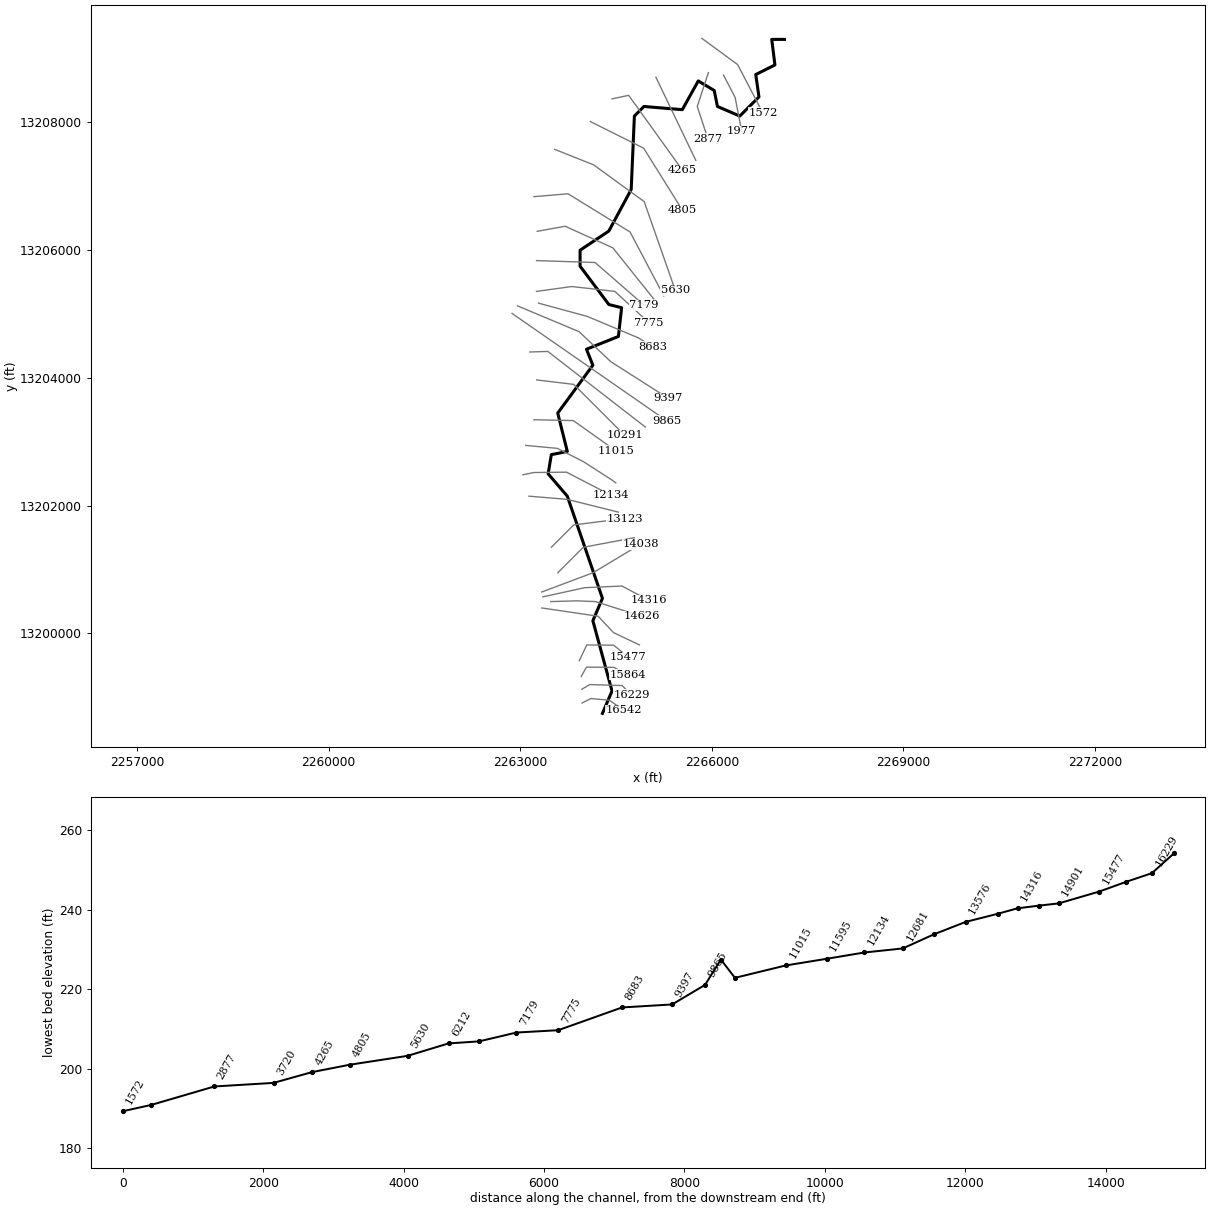
--- LONGORIA CREEK.prj (project) ---

Proj Title=LONGORIA CREEK Base Level Engineering
Current Plan=p01
Default Exp/Contr=0.3,0.1
English Units
Geom File=g01
Flow File=f01
Plan File=p01
Y Axis Title=Elevation
X Axis Title(PF)=Main Channel Distance
X Axis Title(XS)=Station
BEGIN DESCRIPTION:
LONGORIA CREEK
END DESCRIPTION:
DSS Export Rating Curves= 0
DSS Export Rating Curve Sorted= 0
DSS Export Volume Flow Curves= 0
DXF OffsetX= 0
DXF OffsetY= 0
DXF ScaleX= 1
DXF ScaleY= 10

--- LONGORIA CREEK.p01 (plan) ---

Plan Title=Multiple Run
Short Identifier=Multiple
Geom File=g01
Flow File=f01
Subcritical Flow
K Sum by GR= 0
Std Step Tol= 0.01
Critical Tol= 0.01
Num of Std Step Trials= 20
Max Error Tol= 0.3
Flow Tol Ratio= 0.001
Split Flow NTrial= 30
Split Flow Tol= 0.02
Split Flow Ratio= 0.02
Log Output Level= 0
Friction Slope Method= 1
Unsteady Friction Slope Method= 2
Unsteady Bridges Friction Slope Method= 1
Parabolic Critical Depth
Global Vel Dist=  1 , 1 , 1
Global Log Level= 0
CheckData=True
Encroach Param= -1, 0, 0, 0
BEGIN DESCRIPTION:
Multiple Run
END DESCRIPTION:

--- LONGORIA CREEK.f01 (steady flow) ---

Flow Title=Multiple
Number of Profiles=7
Profile Names=10-year,25-year,50-year,1pct_min,100-year,1pct_plu,500-year
River Rch & RM= LONGORIA CREEK,Reach-1,16542
     154     207     248     220     298     403     434
River Rch & RM= LONGORIA CREEK,Reach-1,14901
     233     320     391     352     476     644     715
River Rch & RM= LONGORIA CREEK,Reach-1,12681
     307     426     526     477     645     872     985
River Rch & RM= LONGORIA CREEK,Reach-1,7775
     348     486     601     546     738     998    1132
Boundary for River Rch & Prof#=LONGORIA CREEK,Reach-1,1
Up Type=0
Dn Type=3
Dn Slope=0.005
Boundary for River Rch & Prof#=LONGORIA CREEK,Reach-1,2
Up Type=0
Dn Type=3
Dn Slope=0.005
Boundary for River Rch & Prof#=LONGORIA CREEK,Reach-1,3
Up Type=0
Dn Type=3
Dn Slope=0.005
Boundary for River Rch & Prof#=LONGORIA CREEK,Reach-1,4
Up Type=0
Dn Type=3
Dn Slope=0.005
Boundary for River Rch & Prof#=LONGORIA CREEK,Reach-1,5
Up Type=0
Dn Type=3
Dn Slope=0.005
Boundary for River Rch & Prof#=LONGORIA CREEK,Reach-1,6
Up Type=0
Dn Type=3
Dn Slope=0.005
Boundary for River Rch & Prof#=LONGORIA CREEK,Reach-1,7
Up Type=0
Dn Type=3
Dn Slope=0.005

--- LONGORIA CREEK.g01 (geometry) ---

Geom Title=Existing Conditions
Program Version=4.10

River Reach=LONGORIA CREEK  ,Reach-1
Reach XY= 30
      2264287.72     13198746.85      2264437.72     13199096.85
      2264137.72     13200196.86      2264287.72     13200546.85
      2263737.72     13202146.86      2263437.72     13202496.86
      2263487.72     13202796.86      2263737.72     13202846.85
      2263587.72     13203446.85      2264137.72     13204196.85
      2264037.72     13204446.86      2264537.72     13204646.85
      2264587.72     13205096.86      2264387.72     13205146.85
      2263937.72     13205746.86      2263937.72     13205996.85
      2264387.72     13206296.85      2264737.72     13206946.85
      2264787.72     13208096.85      2264937.72     13208246.86
      2265537.72     13208196.85      2265787.72     13208646.85
      2266037.72     13208496.85      2266087.72     13208246.86
      2266437.72     13208096.85      2266737.72     13208396.86
      2266687.72     13208746.85      2266987.72     13208896.86
      2266937.72     13209296.85      2267137.72     13209296.85

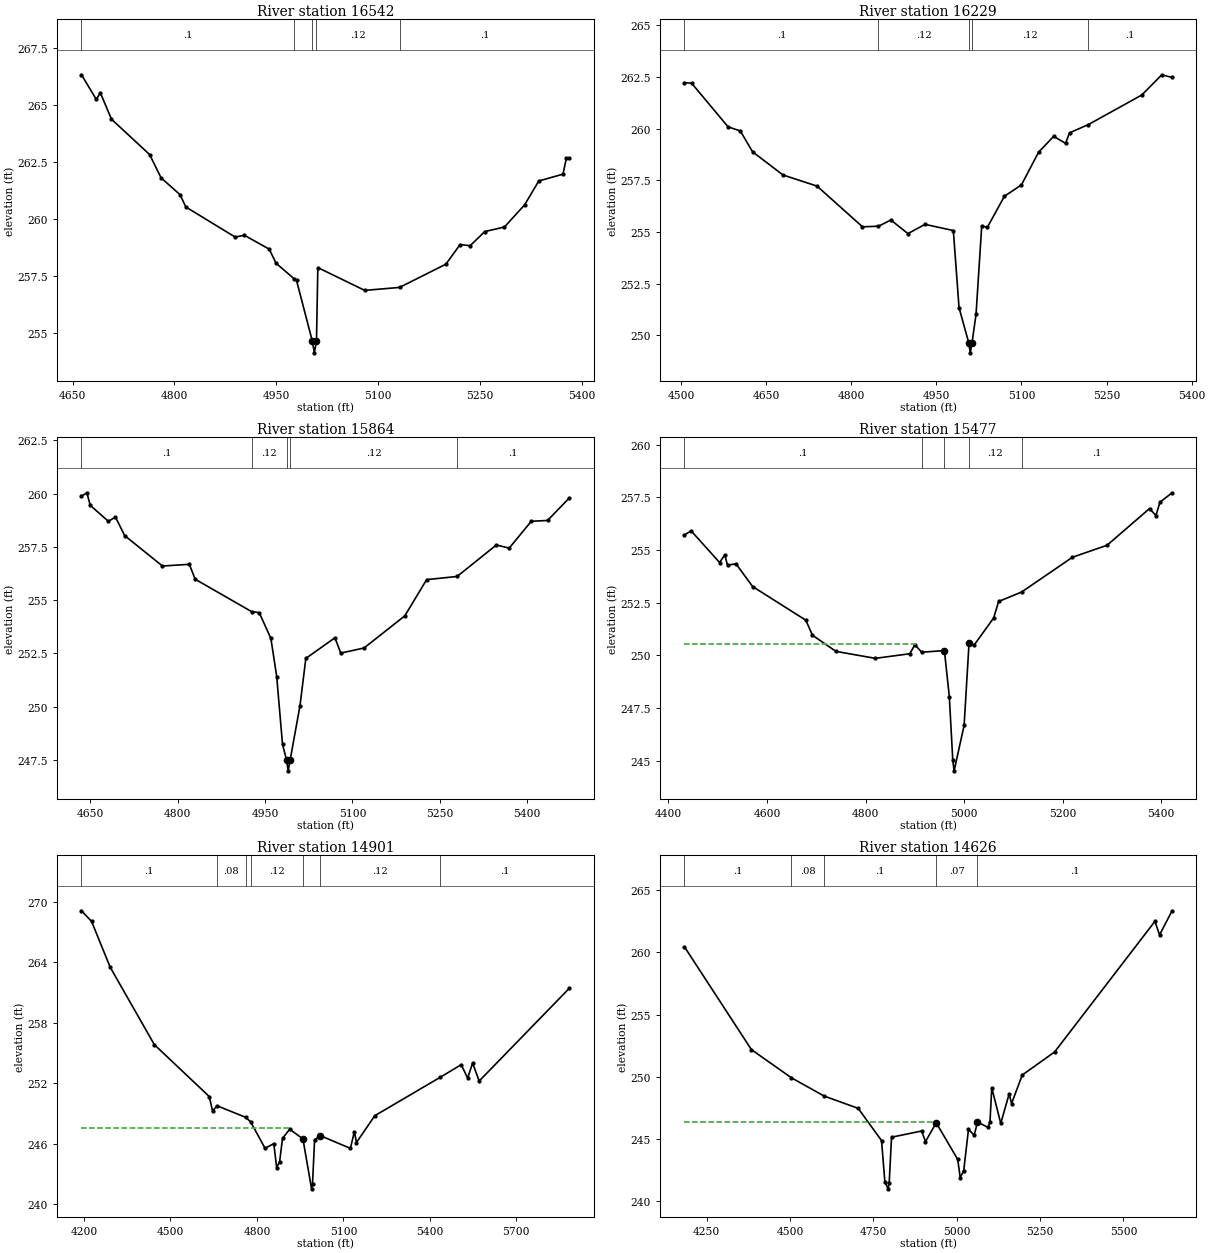
Type RM Length L Ch R = 1 ,16542   ,313,313,313
BEGIN DESCRIPTION:
LONGORIA CREEK 22.0
END DESCRIPTION:
XS GIS Cut Line= 4
       2263968.2     13198909.29      2264108.65     13198979.51
      2264397.26     13198952.21      2264619.56     13198796.21
#Sta/Elev= 30
  4663.1  266.32  4684.9  265.24  4690.9  265.53  4707.3  264.37  4763.5  262.82
  4780.3   261.8  4808.3  261.06  4816.8  260.52  4889.5   259.2    4903  259.28
  4939.7  258.67  4949.8  258.05  4976.8  257.36  4979.9   257.3  5003.3  254.62
  5006.1  254.12  5009.3  254.62  5011.3  257.86  5080.4  256.86  5131.7  256.99
    5200  258.01  5220.9  258.87  5235.7  258.82  5257.2  259.44  5286.2  259.64
  5315.9  260.61  5336.8  261.66  5372.5  261.96  5377.4  262.65  5381.6  262.65
#Mann= 5 ,-1 , 0
  4663.1      .1       0  4976.8     .12       0  5003.3     .07       0
  5009.3     .12       0  5131.7      .1       0
Bank Sta=5003.3,5009.3
XS Rating Curve= 0 ,0
Exp/Cntr=0.3,0.1

Type RM Length L Ch R = 1 ,16229   ,365,365,365
BEGIN DESCRIPTION:
Mapping XS e5a3ee30
END DESCRIPTION:
XS GIS Cut Line= 4
      2263964.33     13199123.81      2264089.15     13199197.92
      2264596.17     13199182.32      2264740.49      13199034.1
#Sta/Elev= 30
  4506.1  262.23  4518.9   262.2  4583.1  260.09  4604.6  259.89  4626.3  258.88
  4679.8  257.76  4739.9  257.22  4819.9  255.25  4848.1  255.28  4869.9  255.58
    4900  254.92    4930  255.37    4980  255.07    4990  251.34    5007  249.65
  5009.8  249.15    5013  249.65    5020  251.02    5030  255.29    5040  255.23
    5070  256.73    5100  257.28  5130.1  258.86  5156.8  259.63  5177.7  259.29
  5184.7   259.8  5217.9   260.2    5312  261.63  5347.4  262.61  5365.4  262.48
#Mann= 5 ,-1 , 0
  4506.1      .1       0  4848.1     .12       0    5007     .07       0
    5013     .12       0  5217.9      .1       0
Bank Sta=5007,5013
XS Rating Curve= 0 ,0
Exp/Cntr=0.3,0.1

Type RM Length L Ch R = 1 ,15864   ,387,387,387
BEGIN DESCRIPTION:
LONGORIA CREEK 21.0
END DESCRIPTION:
XS GIS Cut Line= 4
      2263956.55     13199326.64      2264038.44     13199470.93
      2264467.46     13199467.03      2264680.31     13199350.94
#Sta/Elev= 30
  4634.8  259.88  4644.1  260.04  4649.8  259.45    4681   258.7  4693.1   258.9
  4708.9  258.03  4773.8   256.6    4820  256.68    4830  255.98  4926.8  254.46
    4940  254.41    4960   253.2    4970  251.41    4980  248.22    4987  247.48
  4989.7  246.98    4993  247.48    5010  250.04    5020  252.26    5070  253.23
    5080  252.51    5120  252.75    5190  254.26  5227.4  255.96  5279.8  256.11
  5347.3  257.59  5369.2  257.44  5407.1   258.7  5435.1  258.74  5472.2  259.79
#Mann= 5 ,-1 , 0
  4634.8      .1       0  4926.8     .12       0    4987     .07       0
    4993     .12       0  5279.8      .1       0
Bank Sta=4987,4993
XS Rating Curve= 0 ,0
Exp/Cntr=0.3,0.1

Type RM Length L Ch R = 1 ,15477   ,576,576,576
BEGIN DESCRIPTION:
LONGORIA CREEK 20.0
END DESCRIPTION:
XS GIS Cut Line= 4
      2263925.35     13199572.37      2264042.34     13199818.05
      2264463.56     13199814.15      2264693.21     13199627.32
#Sta/Elev= 30
  4432.5  255.71  4446.3   255.9  4503.9   254.4  4514.4  254.76    4520  254.27
  4537.1  254.34  4570.9  253.26  4678.9  251.66  4692.2  250.95    4740  250.18
    4820  249.85    4890  250.07    4900   250.5    4914  250.14    4960  250.22
    4970  248.02    4977  245.01  4979.7  244.51    5000  246.67    5010  250.57
    5020  250.47    5060  251.77    5070  252.55  5116.8     253  5219.8  254.65
  5290.1  255.22  5376.1  256.96  5389.2  256.63  5397.2  257.26  5421.9  257.71
#Mann= 5 ,-1 , 0
  4432.5      .1       0    4914     .12       0    4960     .07       0
    5010     .12       0  5116.8      .1       0
#XS Ineff= 2 , 0
         4900.36  250.51
Permanent Ineff=
       F       F
Bank Sta=4960,5010
XS Rating Curve= 0 ,0
Exp/Cntr=0.3,0.1

Type RM Length L Ch R = 1 ,14901   ,275,275,275
BEGIN DESCRIPTION:
LONGORIA CREEK 19.0
END DESCRIPTION:
XS GIS Cut Line= 4
      2263337.72     13200396.86      2264219.34     13200267.26
      2264462.72     13200009.92      2264866.33     13199818.96
#Sta/Elev= 30
  4191.4  269.11  4226.3  268.06    4291  263.51  4444.1  255.84  4634.7  250.69
  4646.2  249.25  4661.4  249.78    4761  248.63  4778.3  248.18  4828.2  245.56
  4858.5  246.02  4868.6  243.63  4878.7  244.23  4888.8  246.55  4913.7  247.45
  4959.6  246.49  4989.6  241.54  4992.9  242.04    5000   246.4  5020.2  246.81
  5124.3  245.55  5138.1  247.22  5145.3  246.13  5208.8  248.79  5435.9   252.6
  5508.6  253.85    5531  252.52  5548.2  254.01    5571  252.23  5883.2  261.41
#Mann= 7 ,-1 , 0
  4191.4      .1       0  4661.4     .08       0    4761      .1       0
  4778.3     .12       0  4959.6     .07       0  5020.2     .12       0
  5435.9      .1       0
#XS Ineff= 2 , 0
       0 4913.66  247.55               0
Permanent Ineff=
       F       F
Bank Sta=4959.6,5020.2
XS Rating Curve= 0 ,0
Exp/Cntr=0.3,0.1

Type RM Length L Ch R = 1 ,14626   ,310,310,310
BEGIN DESCRIPTION:
LONGORIA CREEK 18.0
END DESCRIPTION:
XS GIS Cut Line= 4
      2263476.77     13200496.68      2263890.24     13200508.38
      2264178.85     13200496.68      2264903.48     13200266.83
#Sta/Elev= 30
  4183.3  260.45  4384.3  252.18  4504.1  249.92  4602.2  248.45  4704.5  247.46
  4774.6  244.87  4784.6  241.54  4794.3  240.99  4797.6  241.49  4804.6  245.14
  4895.1  245.64  4906.3  244.78  4938.6   246.3  5003.1  243.35  5010.5   241.9
    5021  242.44  5035.4  245.78  5052.5   245.3  5062.4  246.35  5094.4  245.93
  5099.9   246.4  5105.2  249.11  5132.2  246.25  5157.4  248.63  5164.5  247.84
  5196.7  250.14  5293.6  251.99  5594.5  262.49  5608.5   261.4    5646  263.34
#Mann= 5 ,-1 , 0
  4183.3      .1       0  4504.1     .08       0  4602.2      .1       0
  4938.6     .07       0  5062.4      .1       0
#XS Ineff= 2 , 0
         4932.73  246.38
Permanent Ineff=
       F       F
Bank Sta=4938.6,5062.4
XS Rating Curve= 0 ,0
Exp/Cntr=0.3,0.1

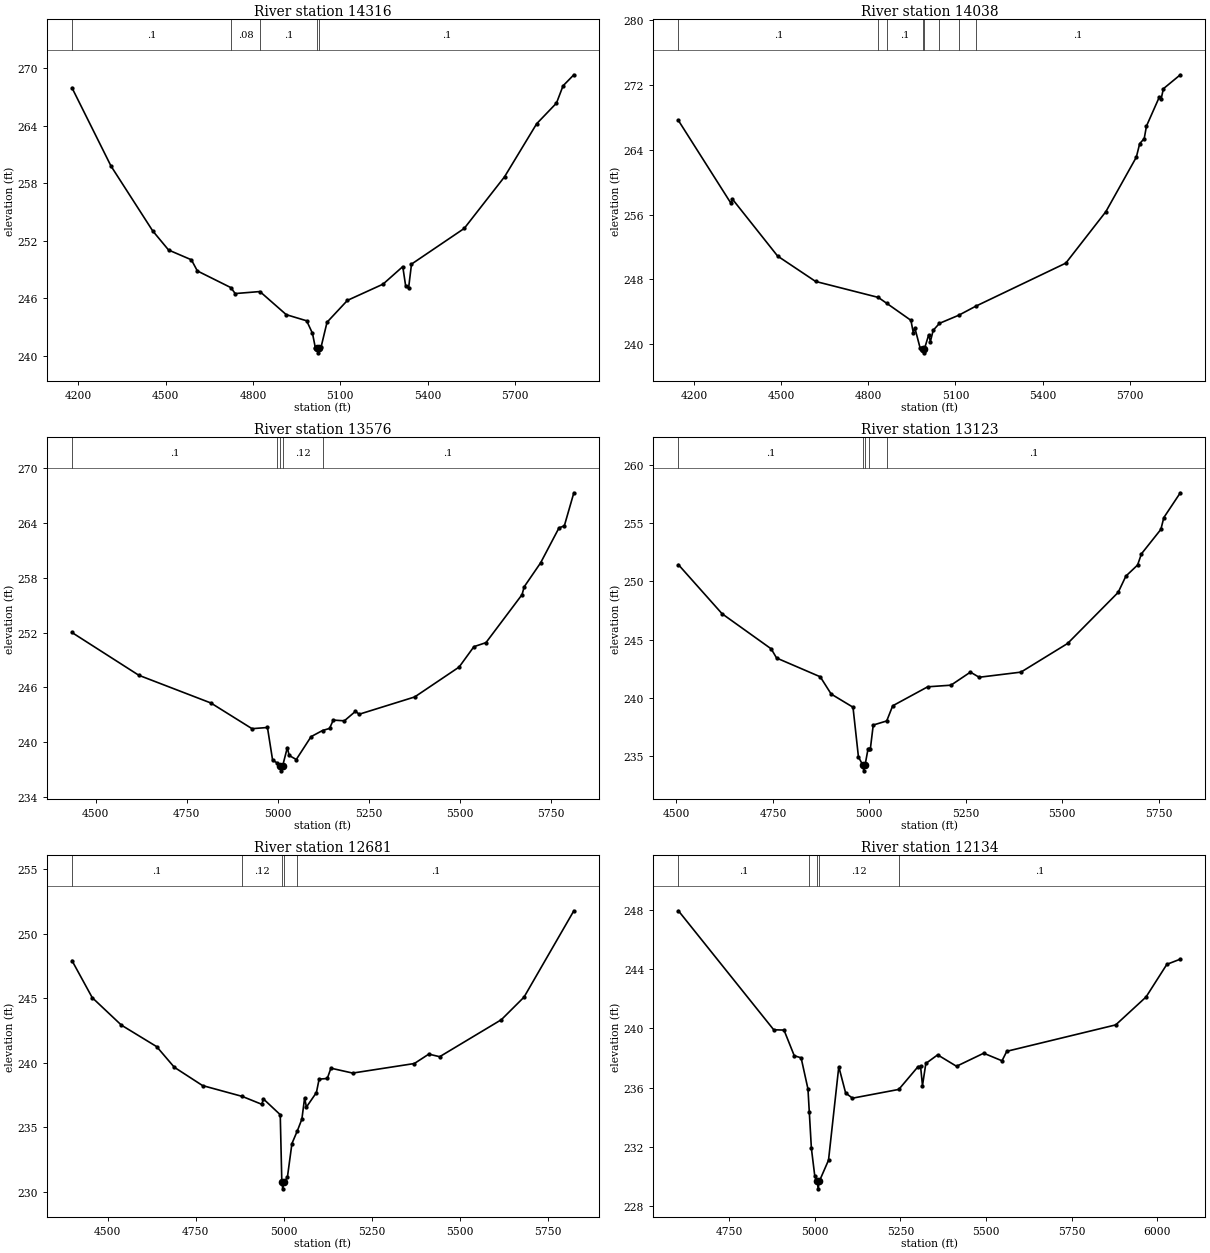
Type RM Length L Ch R = 1 ,14316   ,278,278,278
BEGIN DESCRIPTION:
Mapping XS c21a9ab5
END DESCRIPTION:
XS GIS Cut Line= 4
      2263356.77     13200570.87      2264007.86     13200714.11
       2264593.8     13200740.15      2265010.47     13200518.79
#Sta/Elev= 30
  4177.5  267.95  4311.6  259.79  4454.9  253.03  4509.6  251.03    4588  250.01
  4608.5  248.85  4723.7  247.11  4738.5  246.49  4823.5   246.7  4914.1  244.29
  4984.2  243.65  5004.2  242.34  5013.9  240.86  5021.2  240.81  5023.9  240.31
  5027.2  240.81  5034.2  240.97  5054.2   243.5  5124.3  245.78  5246.6  247.47
  5314.5   249.3  5324.5  247.27  5334.5  247.06  5344.5  249.56  5525.7  253.28
  5664.4  258.67  5774.8   264.2  5842.8  266.35  5865.4  268.15  5902.5   269.3
#Mann= 5 ,-1 , 0
  4177.5      .1       0  4723.7     .08       0  4823.5      .1       0
  5021.2     .07       0  5027.2      .1       0
Bank Sta=5021.2,5027.2
XS Rating Curve= 0 ,0
Exp/Cntr=0.3,0.1

Type RM Length L Ch R = 1 ,14038   ,462,462,462
BEGIN DESCRIPTION:
LONGORIA CREEK 17.0
END DESCRIPTION:
XS GIS Cut Line= 3
      2263337.72     13200646.86      2264137.72     13200946.85
      2264887.68     13201396.83
#Sta/Elev= 30
  4145.6  267.62  4326.3  257.42  4331.6  257.92  4487.4  250.89  4618.2  247.76
  4834.1  245.79  4862.5  245.08  4946.6  242.96  4954.6  241.45  4959.9  242.04
  4978.6   239.5  4987.2  239.45    4990  238.95  4993.2  239.45  5007.8  241.18
  5013.6  240.34  5023.3  241.73  5044.9  242.59  5111.3  243.59  5170.3  244.71
  5480.1  250.02  5618.1  256.37    5723  263.09  5734.7  264.77  5750.2  265.38
    5758  266.93  5802.7  270.55  5808.6  270.29  5816.3  271.54  5874.6  273.26
#Mann= 8 ,-1 , 0
  4145.6      .1       0  4834.1     .08       0  4862.5      .1       0
  4987.2     .07       0  4993.2      .1       0  5044.9     .05       0
  5111.3     .12       0  5170.3      .1       0
Bank Sta=4987.2,4993.2
XS Rating Curve= 0 ,0
Exp/Cntr=0.3,0.1

Type RM Length L Ch R = 1 ,13576   ,453,453,453
BEGIN DESCRIPTION:
LONGORIA CREEK 16.0
END DESCRIPTION:
XS GIS Cut Line= 3
      2263587.71     13200946.84      2263987.72     13201346.86
      2264787.68     13201496.85
#Sta/Elev= 30
  4434.3  252.01  4618.2  247.33  4816.2   244.3  4929.3  241.49  4971.7  241.62
  4985.9  238.04  4998.7  237.74  5007.2  237.38  5009.9  236.88  5013.2  237.38
  5026.3  239.42  5031.4  238.56  5050.9  238.12  5091.6  240.62  5123.1  241.29
  5142.4  241.52  5152.6  242.43  5183.1  242.35  5213.7  243.39  5223.8  243.07
  5376.4  244.96  5498.5  248.23  5539.2  250.46  5572.3   250.9  5671.5  256.15
  5677.4  257.01  5722.4  259.62  5773.2  263.46  5787.7  263.67  5813.9  267.29
#Mann= 5 ,-1 , 0
  4434.3      .1       0  4998.7     .12       0  5007.2     .07       0
  5013.2     .12       0  5123.1      .1       0
Bank Sta=5007.2,5013.2
XS Rating Curve= 0 ,0
Exp/Cntr=0.3,0.1

Type RM Length L Ch R = 1 ,13123   ,442,442,442
BEGIN DESCRIPTION:
LONGORIA CREEK 15.0
END DESCRIPTION:
XS GIS Cut Line= 3
       2263487.7     13201346.84      2263837.72     13201696.85
      2264637.69     13201796.85
#Sta/Elev= 30
    4505  251.44  4618.2  247.23  4745.4  244.22  4759.6  243.43  4872.7  241.82
    4901  240.34  4957.6  239.21  4971.7  234.95  4982.9  234.25  4985.6  233.75
  4988.9  234.25  4996.5  235.61    5000  235.61  5002.5  235.61  5010.1  237.68
    5045  238.03  5060.5  239.33  5151.2  240.96  5211.6   241.1    5262  242.22
  5284.7  241.78    5393  242.22    5514  244.68    5645  249.06  5665.1  250.46
  5695.4  251.41  5705.4  252.37  5755.8  254.47  5763.4  255.48  5806.2  257.61
#Mann= 5 ,-1 , 0
    4505      .1       0  4982.9     .07       0  4988.9      .1       0
    5000     .12       0    5045      .1       0
Bank Sta=4982.9,4988.9
XS Rating Curve= 0 ,0
Exp/Cntr=0.3,0.1

Type RM Length L Ch R = 1 ,12681   ,547,547,547
BEGIN DESCRIPTION:
LONGORIA CREEK 14.0
END DESCRIPTION:
XS GIS Cut Line= 3
       2263137.7     13202146.86      2263737.72     13202096.85
       2264537.7     13201896.86
#Sta/Elev= 30
  4397.9  247.92  4455.6  245.04  4538.4  242.91  4638.8  241.24  4688.9  239.64
  4769.2  238.22    4882  237.38  4937.3  236.77  4942.3  237.18    4990  235.96
  4994.5  230.71  4997.2  230.21  5000.5  230.71  5010.3   231.1  5023.2  233.72
  5038.9  234.73  5051.5  235.62  5059.3  237.27  5064.4  236.55  5092.8  237.68
  5100.5  238.72  5123.7  238.77    5134  239.57  5195.8  239.19  5371.1  239.93
  5412.3  240.66  5443.2  240.46  5618.5  243.33  5682.9  245.08  5824.6  251.78
#Mann= 5 ,-1 , 0
  4397.9      .1       0    4882     .12       0  4994.5     .07       0
  5000.5     .12       0  5038.9      .1       0
Bank Sta=4994.5,5000.5
XS Rating Curve= 0 ,0
Exp/Cntr=0.3,0.1

Type RM Length L Ch R = 1 ,12134   ,539,539,539
BEGIN DESCRIPTION:
LONGORIA CREEK 13.0
END DESCRIPTION:
XS GIS Cut Line= 4
      2263043.12     13202481.42      2263212.88     13202517.01
       2263724.9     13202522.49      2264417.65     13202163.79
#Sta/Elev= 30
  4601.7  247.93    4880  239.91    4910  239.89    4940  238.16    4960  238.02
    4980  235.92  4983.9  234.36    4990  231.92    5000  230.03    5007  229.69
  5009.8  229.19    5013  229.69    5040  231.12    5070  237.42    5090  235.65
    5110   235.3  5245.2  235.89  5301.6  237.43  5308.8  237.45  5314.4  236.15
  5324.2  237.64  5358.7  238.22  5413.8  237.45  5493.1  238.33  5546.6  237.82
  5560.6  238.46  5878.7  240.24  5967.2  242.12    6028  244.32  6067.3  244.67
#Mann= 5 ,-1 , 0
  4601.7      .1       0  4983.9     .12       0    5007     .07       0
    5013     .12       0  5245.2      .1       0
Bank Sta=5007,5013
XS Rating Curve= 0 ,0
Exp/Cntr=0.3,0.1

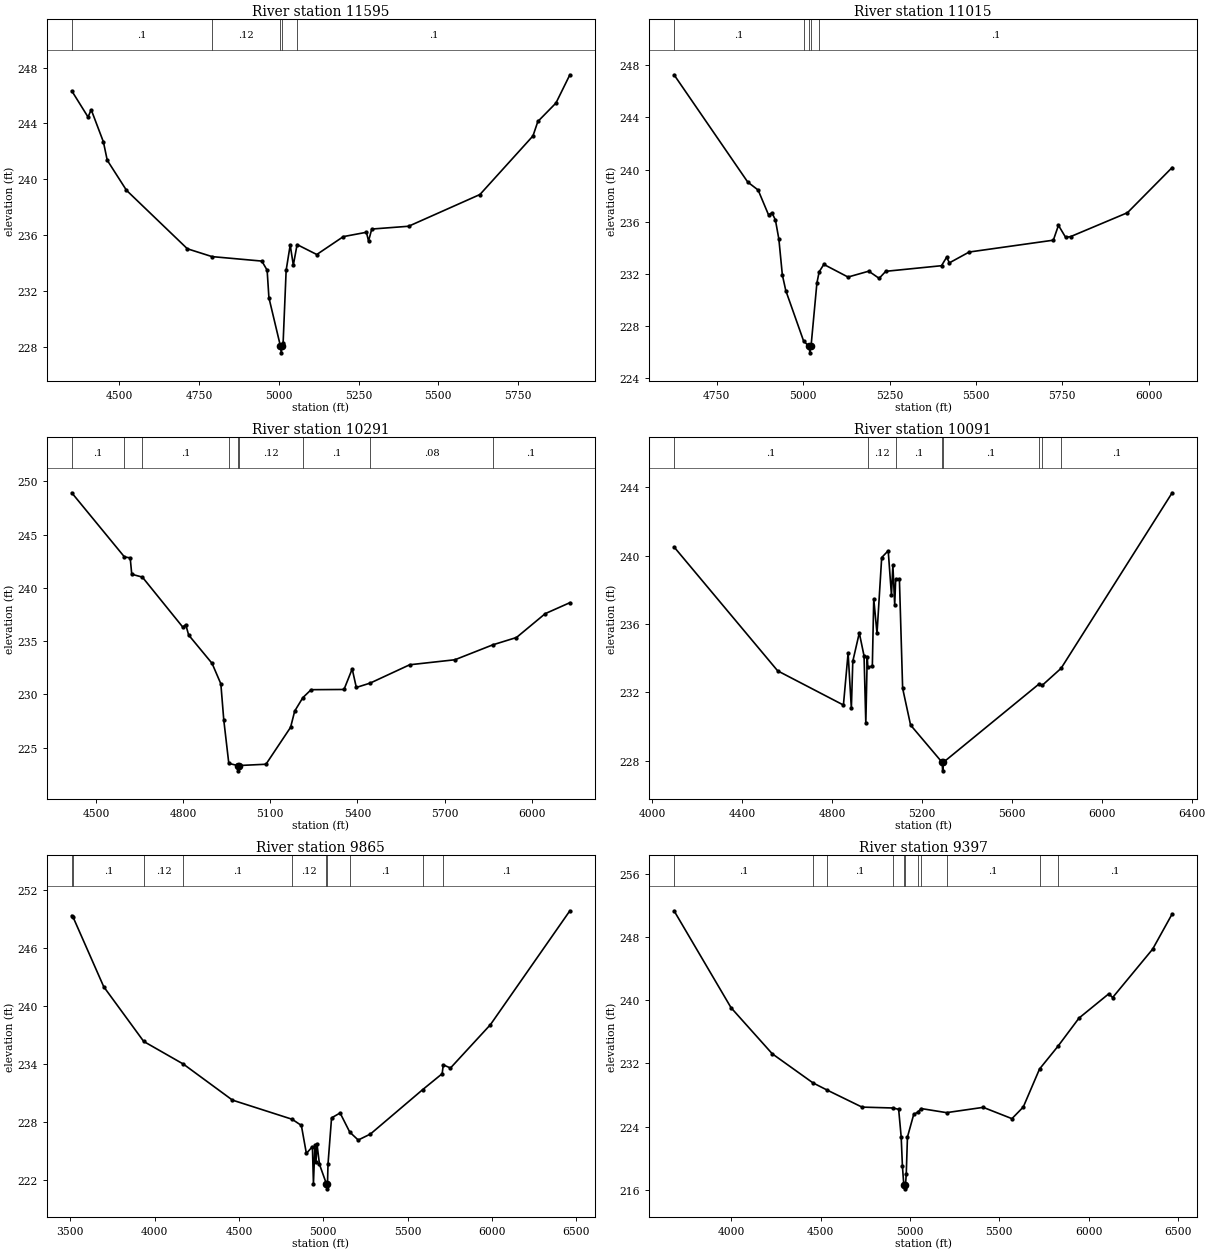
Type RM Length L Ch R = 1 ,11595   ,580,580,580
BEGIN DESCRIPTION:
LONGORIA CREEK 12.0
END DESCRIPTION:
XS GIS Cut Line= 5
      2263086.97     13202941.41      2263582.52     13202894.87
      2263995.97     13202684.03       2264436.8     13202399.27
      2264497.02     13202355.48
#Sta/Elev= 30
  4351.2  246.33  4402.2  244.46  4412.2  244.98  4450.4  242.68  4462.4  241.37
  4522.7  239.22  4713.5  235.04  4790.8  234.48  4946.9  234.16  4963.5  233.51
  4969.1  231.54    5005   228.1  5007.7   227.6    5011   228.1  5013.6  228.31
  5023.1   233.5  5035.8  235.31  5045.6  233.87  5057.4  235.34  5119.1  234.63
  5202.4  235.91  5274.8  236.22  5281.3  235.59  5291.4  236.45  5406.8  236.65
  5630.5  238.92  5796.7  243.11  5811.9  244.14  5868.7  245.46  5912.3  247.48
#Mann= 5 ,-1 , 0
  4351.2      .1       0  4790.8     .12       0    5005     .07       0
    5011     .12       0  5057.4      .1       0
Bank Sta=5005,5011
XS Rating Curve= 0 ,0
Exp/Cntr=0.3,0.1

Type RM Length L Ch R = 1 ,11015   ,724,724,724
BEGIN DESCRIPTION:
LONGORIA CREEK 11.0
END DESCRIPTION:
XS GIS Cut Line= 3
       2263214.6     13203343.21      2263830.96     13203330.18
      2264503.19     13202853.12
#Sta/Elev= 30
  4626.8  247.28    4840  239.04    4870  238.43    4900  236.53    4910  236.68
    4920  236.13    4930  234.66    4940  231.92    4950  230.71  5001.5  226.84
    5017  226.43  5019.8  225.93    5023  226.43    5040  231.29  5046.5  232.15
    5060  232.72    5130  231.75    5190   232.2    5220  231.65  5239.2  232.19
  5400.4  232.62  5415.2  233.27  5423.3  232.84  5480.4  233.67  5723.9  234.58
  5738.7  235.72  5759.6  234.79  5774.4  234.86  5938.3  236.69  6067.6  240.16
#Mann= 5 ,-1 , 0
  4626.8      .1       0  5001.5     .12       0    5017     .07       0
    5023     .12       0  5046.5      .1       0
Bank Sta=5017,5023
XS Rating Curve= 0 ,0
Exp/Cntr=0.3,0.1

Type RM Length L Ch R = 1 ,10291   ,200,200,200
BEGIN DESCRIPTION:
LONGORIA CREEK 10.0
END DESCRIPTION:
XS GIS Cut Line= 3
        2263258.     13203966.58      2263837.72     13203896.85
      2264637.74     13203096.83
#Sta/Elev= 30
  4416.1  248.92  4597.7  242.89  4617.3  242.81  4622.7  241.27  4659.3     241
  4798.6   236.3  4808.6  236.54  4818.7  235.56  4899.3   232.9  4929.5  230.98
  4939.6  227.58  4956.9  223.51  4986.9  223.31  4989.7  222.81  4992.9  223.31
  5084.9  223.43  5169.7   226.9  5183.8  228.42  5211.8  229.68  5240.4  230.43
  5353.6  230.45  5381.8  232.38    5396  230.64  5443.8  231.05  5579.8  232.77
  5735.4  233.24  5865.8  234.64  5947.5  235.33  6046.5  237.57  6131.4   238.6
#Mann= 9 ,-1 , 0
  4416.1      .1       0  4597.7     .08       0  4659.3      .1       0
  4956.9     .12       0  4986.9     .07       0  4992.9     .12       0
  5211.8      .1       0  5443.8     .08       0  5865.8      .1       0
Bank Sta=4986.9,4992.9
XS Rating Curve= 0 ,0
Exp/Cntr=0.3,0.1

Type RM Length L Ch R = 1 ,10091   ,226,226,226
BEGIN DESCRIPTION:
Mapping XS 306454c7
END DESCRIPTION:
XS GIS Cut Line= 3
      2263150.78     13204403.87      2263432.91     13204412.55
      2264960.71     13203227.64
#Sta/Elev= 30
  4097.3  240.51  4558.3  233.26  4850.7  231.26  4871.5   234.3    4886  231.06
  4892.4  233.82  4921.3  235.48  4942.5  234.13  4950.3  230.18  4956.6   234.1
  4959.3  233.47  4979.3  233.54  4985.6  237.47  5000.1  235.45  5020.9  239.89
  5049.9  240.29  5064.4  237.68  5070.7  239.44  5078.8  237.11  5083.2  238.62
  5099.7  238.63  5114.1  232.24  5149.4  230.09  5289.5  227.91  5292.2  227.41
  5295.5  227.91  5718.8  232.47  5735.6  232.42    5819  233.41    6313  243.68
#Mann= 8 ,-1 , 0
  4097.3      .1       0  4959.3     .12       0  5083.2      .1       0
  5289.5     .07       0  5295.5      .1       0  5718.8     .05       0
  5735.6     .08       0    5819      .1       0
Bank Sta=5289.5,5295.5
XS Rating Curve= 0 ,0
Exp/Cntr=0.3,0.1

Type RM Length L Ch R = 1 ,9865    ,468,468,468
BEGIN DESCRIPTION:
LONGORIA CREEK 9.0
END DESCRIPTION:
XS GIS Cut Line= 2
      2262873.01     13205007.18      2265299.24     13203323.14
#Sta/Elev= 30
    3509  249.31  3516.4  249.17  3698.6  241.95  3935.7  236.29  4170.5  233.95
  4461.7  230.22  4815.3  228.24  4870.4   227.6  4900.1   224.7  4935.9  225.41
    4942  221.58  4950.7  225.59  4956.8  223.79  4963.3  225.64  4977.8  223.57
  5019.3  221.54  5022.1  221.04  5025.3  221.54  5028.4  223.62  5049.4  228.38
    5100  228.89  5157.3  226.91  5207.4  226.09  5279.8  226.71    5590  231.31
  5705.1  232.95  5711.9  233.87  5754.5  233.54  5991.5  238.03  6462.4  249.81
#Mann= 10 ,-1 , 0
    3509     .05       0  3516.4      .1       0  3935.7     .12       0
  4170.5      .1       0  4815.3     .12       0  5019.3     .07       0
  5025.3     .12       0  5157.3      .1       0    5590     .05       0
  5711.9      .1       0
Bank Sta=5019.3,5025.3
XS Rating Curve= 0 ,0
Exp/Cntr=0.3,0.1

Type RM Length L Ch R = 1 ,9397    ,714,714,714
BEGIN DESCRIPTION:
Mapping XS 85cc1b12
END DESCRIPTION:
XS GIS Cut Line= 4
      2262958.59     13205125.42       2263922.1     13204721.79
      2264416.89     13204253.04      2265312.65     13203681.83
#Sta/Elev= 30
  3679.1   251.3  3998.4  239.03  4228.7  233.21  4456.5  229.53  4534.8  228.63
  4731.4  226.46    4904  226.35  4936.5  226.18  4950.6  222.71  4957.5  219.04
  4964.8  216.77  4968.7  216.62  4971.4  216.12  4974.7  216.62    4979  217.95
  4985.8  222.68    5021  225.55  5044.6  225.83  5061.8  226.28  5204.6  225.76
  5409.9  226.43  5570.7     225  5634.1  226.47  5725.2  231.28  5827.3  234.13
  5946.4  237.73  6113.1   240.8  6134.3  240.32  6358.5  246.45  6467.7   250.9
#Mann= 11 ,-1 , 0
  3679.1      .1       0  4456.5     .12       0  4534.8      .1       0
    4904     .12       0  4968.7     .07       0  4974.7     .12       0
  5044.6      .1       0  5061.8     .12       0  5204.6      .1       0
  5725.2     .05       0  5827.3      .1       0
Bank Sta=4968.7,4974.7
XS Rating Curve= 0 ,0
Exp/Cntr=0.3,0.1

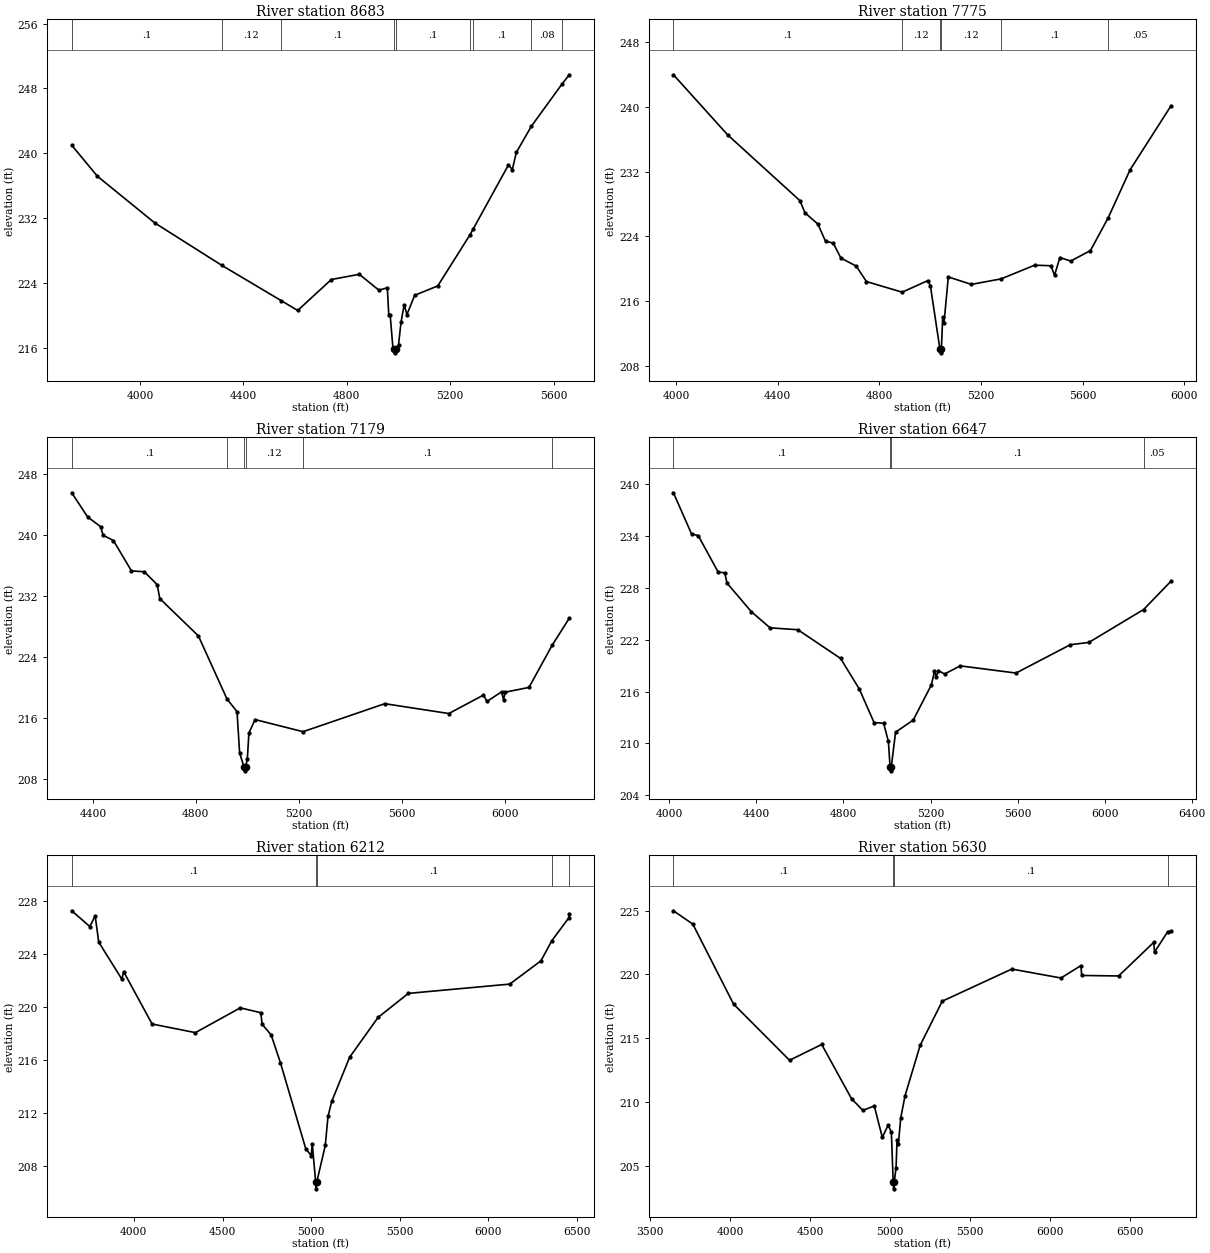
Type RM Length L Ch R = 1 ,8683    ,908,908,908
BEGIN DESCRIPTION:
LONGORIA CREEK 8.0
END DESCRIPTION:
XS GIS Cut Line= 4
       2263287.6     13205167.94      2264047.13     13204961.78
      2264850.08     13204625.41      2265077.98     13204484.33
#Sta/Elev= 30
  3735.3  240.99  3834.4  237.17  4056.6   231.4  4315.1  226.18  4545.6  221.81
  4609.7  220.59  4739.8  224.41  4848.2  225.06  4924.1  223.09  4956.6   223.4
  4962.1  220.08  4967.5  220.07  4978.3  215.95  4982.9  215.86  4985.6  215.36
  4988.9  215.86    5000  216.36  5009.6  219.14  5021.7   221.3  5032.5  220.09
  5062.6  222.47  5151.8  223.62  5275.2  229.87  5288.5  230.63  5425.4  238.56
  5440.3  237.99  5455.7   240.1  5514.1  243.34  5631.7  248.51  5660.9  249.69
#Mann= 9 ,-1 , 0
  3735.3      .1       0  4315.1     .12       0  4545.6      .1       0
  4982.9     .07       0  4988.9      .1       0  5275.2     .05       0
  5288.5      .1       0  5514.1     .08       0  5631.7     .05       0
Bank Sta=4982.9,4988.9
XS Rating Curve= 0 ,0
Exp/Cntr=0.3,0.1

Type RM Length L Ch R = 1 ,7775    ,596,596,596
BEGIN DESCRIPTION:
Mapping XS 2dddf15f
END DESCRIPTION:
XS GIS Cut Line= 4
      2263254.98      13205352.4      2263808.42     13205428.36
      2264481.16      13205352.4      2265012.76      13204864.2
#Sta/Elev= 30
  3990.1  243.93  4203.3  236.52  4487.5  228.41  4507.6  226.91  4558.1  225.52
  4588.3   223.4  4618.5  223.18  4648.7  221.33    4709  220.34  4749.3  218.43
  4889.9  217.12  4990.8  218.55  5000.9   217.9  5038.1  210.14  5040.9  209.64
  5044.1  210.14  5049.3  214.07  5054.3  213.28  5071.3     219  5161.9  218.08
  5278.9  218.76  5411.1  220.45  5475.1  220.38  5489.2  219.21  5510.2  221.39
  5552.8  220.96  5630.4  222.25  5700.2  226.29  5786.4  232.21  5947.5  240.11
#Mann= 6 ,-1 , 0
  3990.1      .1       0  4889.9     .12       0  5038.1     .07       0
  5044.1     .12       0  5278.9      .1       0  5700.2     .05       0
Bank Sta=5038.1,5044.1
XS Rating Curve= 0 ,0
Exp/Cntr=0.3,0.1

Type RM Length L Ch R = 1 ,7179    ,532,532,532
BEGIN DESCRIPTION:
LONGORIA CREEK 7.0
END DESCRIPTION:
XS GIS Cut Line= 3
      2263255.78     13205834.32      2264172.18     13205804.44
      2264939.11     13205137.11
#Sta/Elev= 30
  4317.7  245.49  4379.7  242.31  4429.7  241.06  4439.7  239.92  4479.7  239.23
  4549.8  235.25  4599.8  235.14  4649.8  233.45  4659.8  231.63  4809.9  226.73
  4921.1  218.46    4960  216.81    4970  211.42    4987  209.55  4989.7  209.05
    4993  209.55    5000  210.59  5006.1  213.99    5030  215.77  5216.5  214.18
  5534.1  217.85  5782.9  216.56  5917.7  218.98  5931.2  218.14  5987.9  219.41
  5995.6  218.37  6002.2  219.36  6094.3  219.98  6184.9  225.53  6251.2  229.06
#Mann= 6 ,-1 , 0
  4317.7      .1       0  4921.1     .12       0    4987     .07       0
    4993     .12       0  5216.5      .1       0  6184.9     .05       0
Bank Sta=4987,4993
XS Rating Curve= 0 ,0
Exp/Cntr=0.3,0.1

Type RM Length L Ch R = 1 ,6647    ,435,435,435
BEGIN DESCRIPTION:
LONGORIA CREEK 6.0
END DESCRIPTION:
XS GIS Cut Line= 4
      2263265.76     13206292.49      2263704.05     13206372.18
      2264451.07     13206033.53      2265088.53     13205236.71
#Sta/Elev= 30
  4018.9  238.99  4102.2  234.22  4132.7  234.04  4224.2  229.82  4254.7  229.73
  4264.8  228.55  4376.6  225.24  4462.8  223.37  4590.5  223.15  4786.8  219.83
    4873  216.28  4940.5  212.42  4984.4  212.33  5006.4  210.23    5014  207.33
  5016.8  206.83    5020  207.33  5039.3   211.3  5120.4   212.7    5204  216.77
  5218.2  218.36    5226  217.69  5235.8  218.43  5264.4  218.03  5336.6  218.97
  5592.7  218.14  5842.4  221.42  5927.3  221.68    6179  225.49    6305  228.77
#Mann= 4 ,-1 , 0
  4018.9      .1       0    5014     .07       0    5020      .1       0
    6179     .05       0
Bank Sta=5014,5020
XS Rating Curve= 0 ,0
Exp/Cntr=0.3,0.1

Type RM Length L Ch R = 1 ,6212    ,582,582,582
BEGIN DESCRIPTION:
LONGORIA CREEK 5.0
END DESCRIPTION:
XS GIS Cut Line= 4
      2263216.01     13206835.34      2263748.87     13206880.15
        2264720.     13206282.54       2265247.8      13205281.7
#Sta/Elev= 30
  3649.6  227.28  3751.7  226.09  3781.8   226.9  3801.8  224.92  3932.3  222.12
  3942.3  222.69  4102.9  218.74  4347.2  218.09  4600.3  219.96  4716.3  219.59
  4723.1  218.73  4774.3  217.92  4826.4  215.83  4969.7  209.33  5000.3  208.82
  5006.2  209.72  5025.4  206.81  5028.1  206.31  5031.4  206.81  5079.6  209.58
    5095  211.77  5116.2  212.91  5216.8  216.23  5377.6  219.24  5548.2  221.05
  6120.2  221.75  6296.4  223.51  6357.2  225.02  6453.9  226.76  6456.1  227.07
#Mann= 5 ,-1 , 0
  3649.6      .1       0  5025.4     .07       0  5031.4      .1       0
  6357.2     .05       0  6453.9      .1       0
Bank Sta=5025.4,5031.4
XS Rating Curve= 0 ,0
Exp/Cntr=0.3,0.1

Type RM Length L Ch R = 1 ,5630    ,825,825,825
BEGIN DESCRIPTION:
LONGORIA CREEK 4.0
END DESCRIPTION:
XS GIS Cut Line= 4
      2263539.06     13207576.12      2264150.16     13207333.07
      2264941.82     13206756.68      2265427.93     13205367.82
#Sta/Elev= 30
  3645.3  224.99  3766.4  223.94  4020.5  217.68  4370.5  213.27  4571.4  214.51
  4757.6  210.26  4828.7  209.34  4899.8  209.69    4950  207.22  4985.5  208.16
  5006.4  207.68  5018.1  203.69  5020.8  203.19  5024.1  203.69  5035.8  204.83
  5042.1  207.01  5050.4  206.72  5065.1  208.75  5092.2   210.5  5186.4  214.44
  5324.4   217.9  5758.8  220.42  6066.1  219.72  6190.5  220.69  6195.8  219.92
  6426.3  219.88  6645.3  222.51  6650.6  221.75  6732.7  223.35  6753.7  223.37
#Mann= 4 ,-1 , 0
  3645.3      .1       0  5018.1     .07       0  5024.1      .1       0
  6732.7     .05       0
Bank Sta=5018.1,5024.1
XS Rating Curve= 0 ,0
Exp/Cntr=0.3,0.1

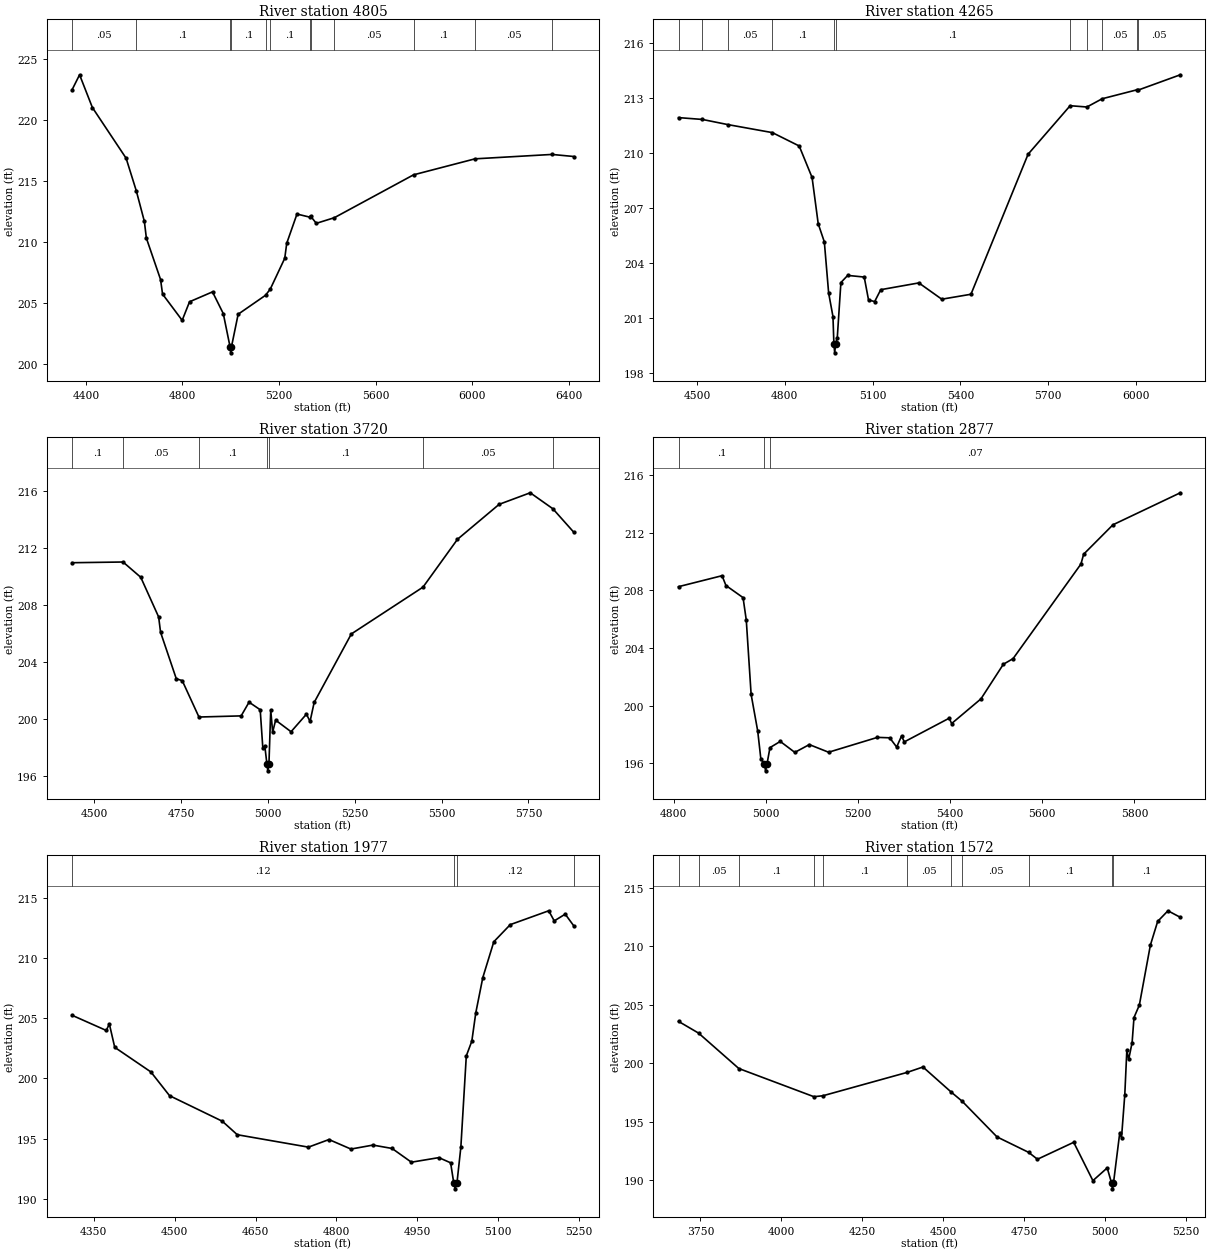
Type RM Length L Ch R = 1 ,4805    ,540,540,540
BEGIN DESCRIPTION:
Mapping XS 2b946813
END DESCRIPTION:
XS GIS Cut Line= 3
       2264099.9     13208010.62       2264933.2     13207593.97
      2265540.82     13206621.79
#Sta/Elev= 30
  4342.8  222.48  4373.9  223.71  4426.9  221.03  4566.6  216.88  4608.8  214.21
  4642.2  211.71  4650.5  210.34  4709.3  206.95  4717.5  205.76  4798.8  203.61
  4829.3  205.13  4924.4  205.94  4969.1  204.16    4997  201.45  4999.8  200.95
    5003  201.45  5030.6  204.11  5143.9  205.66  5163.7  206.17  5223.6  208.69
  5231.8  209.92  5274.2  212.31  5328.8  212.05  5330.5  212.14  5354.3  211.55
  5428.8  212.01  5756.9  215.52  6011.6  216.83  6330.3  217.19  6420.9  217.02
#Mann= 12 ,-1 , 0
  4342.8     .05       0  4608.8      .1       0    4997     .07       0
    5003      .1       0  5143.9     .05       0  5163.7      .1       0
  5328.8     .05       0  5330.5      .1       0  5428.8     .05       0
  5756.9      .1       0  6011.6     .05       0  6330.3      .1       0
Bank Sta=4997,5003
XS Rating Curve= 0 ,0
Exp/Cntr=0.3,0.1

Type RM Length L Ch R = 1 ,4265    ,545,545,545
BEGIN DESCRIPTION:
Mapping XS 97da93d7
END DESCRIPTION:
XS GIS Cut Line= 3
      2264437.62     13208365.89      2264698.17     13208421.16
      2265542.94     13207244.81
#Sta/Elev= 30
  4437.1  211.93  4518.6  211.83  4605.1  211.55  4757.8  211.11  4849.4  210.38
  4893.4  208.66  4914.4  206.13  4935.3  205.14    4950  202.35  4964.8  201.06
  4967.9  199.58  4970.7  199.08  4973.9  199.58  4979.5   199.9  4991.9  202.92
  5015.1  203.31  5071.6  203.22  5086.3  201.97  5107.2  201.88  5128.1  202.53
  5258.2   202.9  5336.6  202.01  5436.3  202.28  5631.5  209.93  5775.2  212.58
  5832.5  212.51  5884.6  212.96  6003.7  213.45    6007  213.43  6151.7  214.27
#Mann= 11 ,-1 , 0
  4437.1     .05       0  4518.6      .1       0  4605.1     .05       0
  4757.8      .1       0  4967.9     .07       0  4973.9      .1       0
  5775.2     .05       0  5832.5      .1       0  5884.6     .05       0
  6003.7      .1       0    6007     .05       0
Bank Sta=4967.9,4973.9
XS Rating Curve= 0 ,0
Exp/Cntr=0.3,0.1

Type RM Length L Ch R = 1 ,3720    ,843,843,843
BEGIN DESCRIPTION:
Mapping XS 475eff38
END DESCRIPTION:
XS GIS Cut Line= 2
       2265124.2     13208705.04      2265749.19     13207402.97
#Sta/Elev= 30
  4436.3  210.96    4583  211.01    4634  209.94  4685.5  207.16    4691  206.09
  4736.3  202.83  4753.4   202.7  4801.5  200.15    4923  200.23  4945.7  201.19
  4977.8  200.66  4985.4  197.96    4991  198.14    4997  196.88  4999.7  196.38
    5003  196.88  5008.1  200.65  5013.6  199.09  5022.2  199.93  5066.6  199.12
  5110.9  200.35  5121.3  199.84  5133.1  201.17  5240.1  205.97  5446.4  209.25
  5545.6   212.6  5665.5  215.05    5755  215.86  5820.2  214.74  5880.6  213.09
#Mann= 7 ,-1 , 0
  4436.3      .1       0    4583     .05       0  4801.5      .1       0
    4997     .07       0    5003      .1       0  5446.4     .05       0
  5820.2      .1       0
Bank Sta=4997,5003
XS Rating Curve= 0 ,0
Exp/Cntr=0.3,0.1

Type RM Length L Ch R = 1 ,2877    ,900,900,900
BEGIN DESCRIPTION:
Mapping XS 7681e790
END DESCRIPTION:
XS GIS Cut Line= 3
      2265945.87     13208776.52      2265772.14     13208247.43
      2265937.98     13207742.02
#Sta/Elev= 30
  4810.9  208.25  4905.3  209.01  4913.8  208.33  4950.9  207.49  4957.9  205.93
  4968.4  200.78  4982.7  198.24  4989.5  196.31    4997  195.98  4999.8  195.48
    5003  195.98  5009.3  197.09  5031.6  197.52  5063.2  196.76  5094.7   197.3
  5136.5  196.77  5242.5   197.8  5269.1  197.77  5284.2  197.13  5294.7  197.89
  5300.9  197.49  5398.2  199.13  5403.5  198.76  5467.1  200.47  5515.7  202.87
  5536.8  203.26  5684.1  209.82  5689.9   210.5  5753.5  212.54  5899.7  214.76
#Mann= 3 ,-1 , 0
  4810.9      .1       0    4997     .05       0  5009.3     .07       0
Bank Sta=4997,5003
XS Rating Curve= 0 ,0
Exp/Cntr=0.3,0.1

Type RM Length L Ch R = 1 ,1977    ,405,405,405
BEGIN DESCRIPTION:
LONGORIA CREEK 3.0
END DESCRIPTION:
XS GIS Cut Line= 3
       2266182.8     13208736.99       2266364.4     13208389.58
      2266466.93     13207861.15
#Sta/Elev= 30
  4309.8  205.23  4373.2  203.97  4378.9  204.51  4388.9  202.57  4455.9  200.53
  4490.5  198.56  4588.3  196.44  4616.1  195.32    4748  194.29  4786.1  194.92
  4826.8  194.13  4867.6  194.46  4903.1  194.18  4938.9  193.04  4989.8  193.42
  5011.6  192.99  5017.4  191.33  5020.1  190.83  5023.4  191.33  5030.6  194.29
  5040.7  201.86  5050.9  203.08  5058.3  205.44  5071.3  208.36  5091.7  211.33
  5122.2  212.75  5193.5   213.9  5203.7  213.06  5224.1  213.62  5240.1  212.64
#Mann= 4 ,-1 , 0
  4309.8     .12       0  5017.4     .07       0  5023.4     .12       0
  5240.1      .1       0
Bank Sta=5017.4,5023.4
XS Rating Curve= 0 ,0
Exp/Cntr=0.3,0.1

Type RM Length L Ch R = 1 ,1572    ,706,706,706
BEGIN DESCRIPTION:
Mapping XS 67948f81
END DESCRIPTION:
XS GIS Cut Line= 3
      2265843.22      13209313.5      2266403.88     13208902.87
      2266798.72     13208144.79
#Sta/Elev= 30
  3682.4  203.57  3744.2  202.57  3868.6  199.54  4100.4  197.13  4128.2  197.21
  4388.6  199.21  4437.3  199.67  4525.1  197.51  4558.4  196.74    4666  193.69
  4763.6  192.37  4790.9  191.78  4902.8  193.23  4962.1  189.95  5006.3  191.04
  5019.7  189.75  5022.5  189.25  5025.7  189.75  5044.8  193.99  5050.5  193.63
  5060.6  197.31  5066.9   201.1  5072.6  200.32  5083.2  201.76    5089   203.9
  5105.5  204.96  5139.6  210.09  5162.1  212.12  5193.9  213.03  5232.1  212.47
#Mann= 11 ,-1 , 0
  3682.4      .1       0  3744.2     .05       0  3868.6      .1       0
  4100.4     .05       0  4128.2      .1       0  4388.6     .05       0
  4525.1      .1       0  4558.4     .05       0  4763.6      .1       0
  5019.7     .07       0  5025.7      .1       0
Bank Sta=5019.7,5025.7
XS Rating Curve= 0 ,0
Exp/Cntr=0.3,0.1