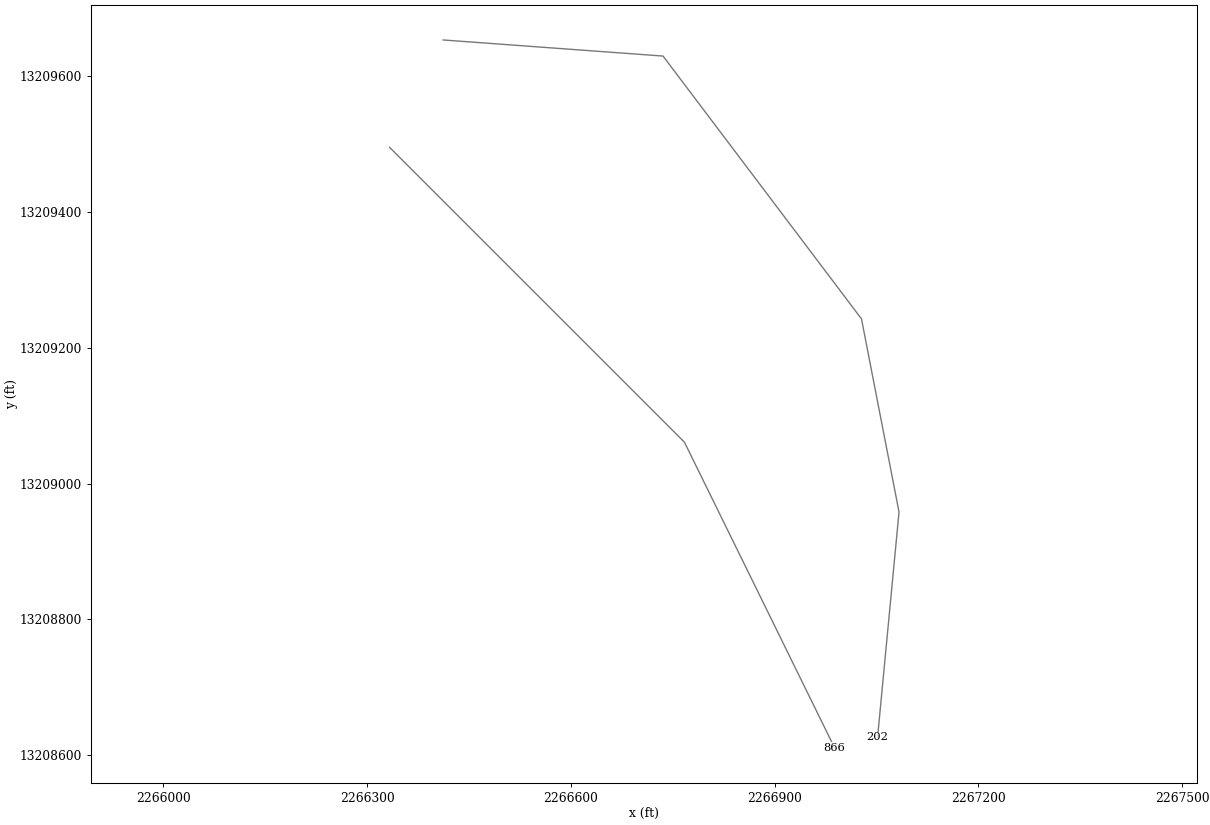
HEC-RAS study LONGORIA CREEK.prj: LONGORIA CREEK Base Level Engineering

--- LONGORIA CREEK.g01 (geometry) --- (continued)

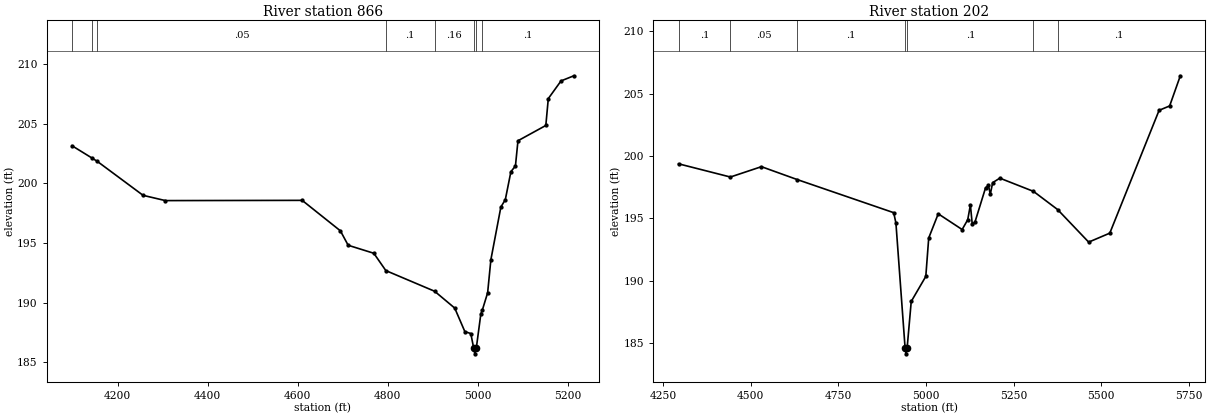
Type RM Length L Ch R = 1 ,866     ,664,664,664
BEGIN DESCRIPTION:
LONGORIA CREEK 2.0
END DESCRIPTION:
XS GIS Cut Line= 3
      2266332.83     13209495.11      2266767.14     13209060.81
      2266987.94     13208611.31
#Sta/Elev= 30
  4098.5  203.14  4142.9  202.11  4154.7  201.83  4256.3  198.99  4305.8  198.55
  4609.8  198.57  4694.7  196.02    4712  194.81    4769  194.14  4795.7  192.69
  4904.1  190.96  4948.8  189.55  4971.3  187.58  4984.5  187.42  4990.8  186.22
  4993.6  185.72  4996.8  186.22  5006.8  189.06  5010.1  189.38  5021.9  190.83
  5029.1   193.6  5051.3  198.01  5061.2  198.63  5073.6  200.97  5083.7  201.45
  5089.3  203.56  5151.2  204.84  5156.7  207.09    5185  208.57  5213.5     209
#Mann= 8 ,-1 , 0
  4098.5     .05       0  4142.9      .1       0  4154.7     .05       0
  4795.7      .1       0  4904.1     .16       0  4990.8     .07       0
  4996.8     .16       0  5010.1      .1       0
Bank Sta=4990.8,4996.8
XS Rating Curve= 0 ,0
Exp/Cntr=0.3,0.1

Type RM Length L Ch R = 1 ,202     ,0,0,0
BEGIN DESCRIPTION:
LONGORIA CREEK 1.0
END DESCRIPTION:
XS GIS Cut Line= 5
      2266411.76     13209653.07      2266735.55     13209629.38
      2267027.73     13209242.43      2267083.01     13208958.15
      2267051.42     13208626.48
#Sta/Elev= 30
  4293.6  199.37  4441.6  198.31  4530.2  199.14    4633   198.1  4907.8  195.45
  4914.1  194.62  4940.2  184.63  4942.9  184.13  4946.2  184.63  4957.8  188.33
  4999.4  190.34  5007.7  193.42  5034.9  195.36  5103.1   194.1    5119  194.88
  5126.7  196.07  5131.8  194.57  5139.4  194.67  5169.9  197.44  5178.3  197.64
  5183.4  196.92  5190.3  197.86  5210.7  198.22  5306.7  197.16  5375.7   195.7
  5464.3  193.09  5524.6  193.81  5665.3  203.66  5695.4  204.01  5725.9  206.43
#Mann= 7 ,-1 , 0
  4293.6      .1       0  4441.6     .05       0    4633      .1       0
  4940.2     .07       0  4946.2      .1       0  5306.7     .16       0
  5375.7      .1       0
Bank Sta=4940.2,4946.2
XS Rating Curve= 0 ,0
Exp/Cntr=0.3,0.1

Chan Stop Cuts=-1
Use User Specified Reach Order=0
Composite Channel Slope=5