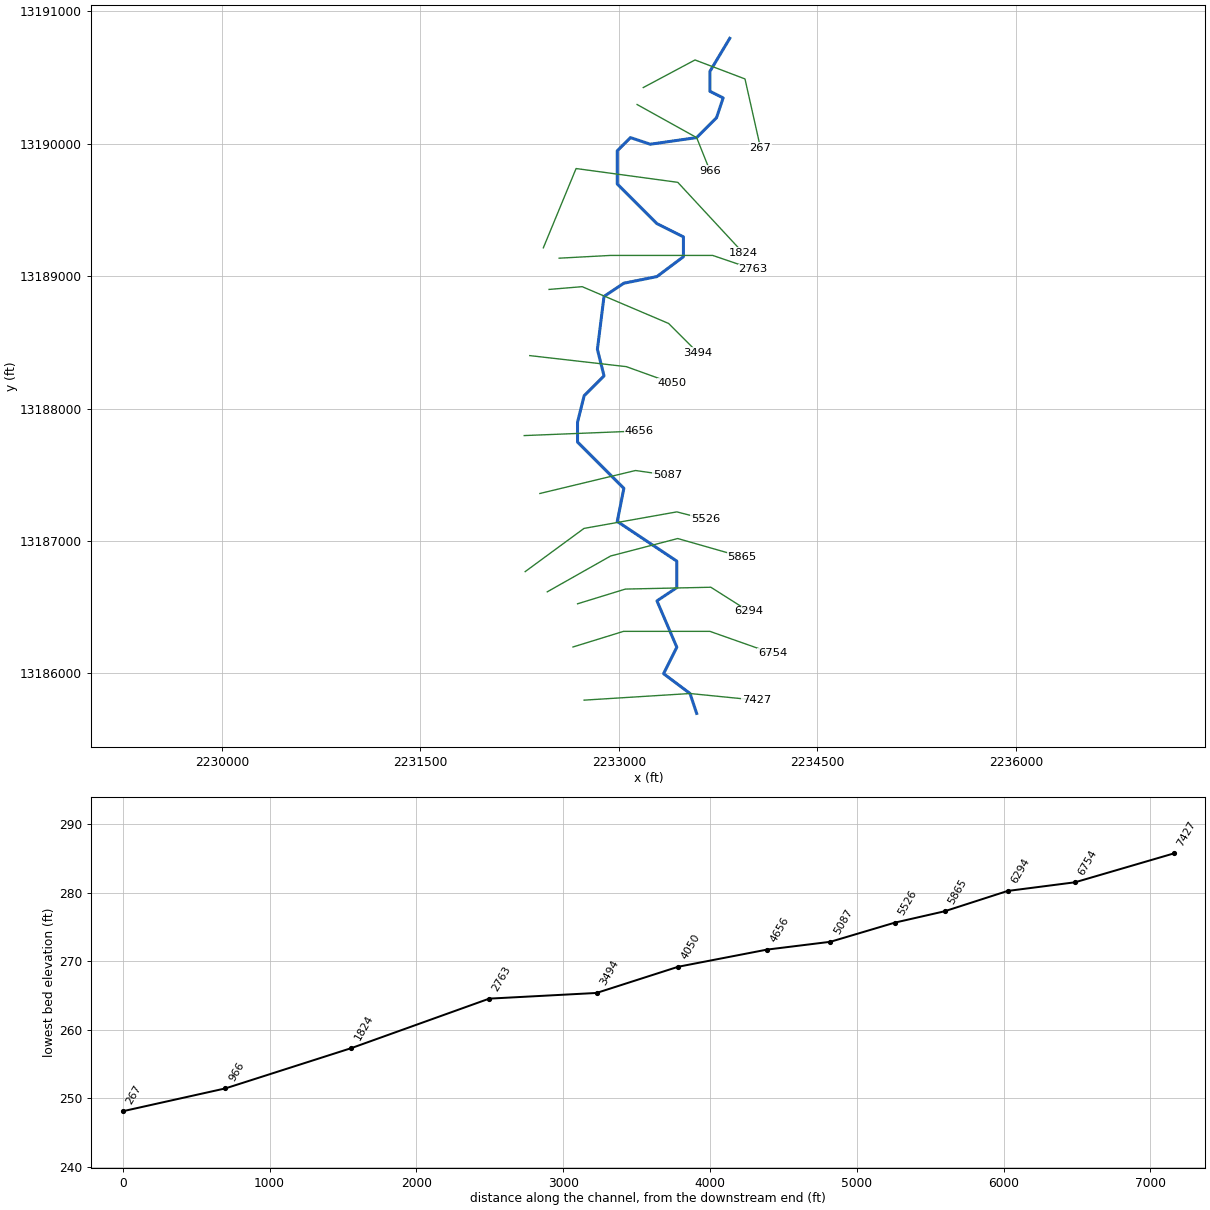
--- MULE TANK CREEK.prj (project) ---

Proj Title=MULE TANK CREEK Base Level Engineering
Current Plan=p01
Default Exp/Contr=0.3,0.1
English Units
Geom File=g01
Flow File=f01
Plan File=p01
Y Axis Title=Elevation
X Axis Title(PF)=Main Channel Distance
X Axis Title(XS)=Station
BEGIN DESCRIPTION:
MULE TANK CREEK
END DESCRIPTION:
DSS Export Rating Curves= 0
DSS Export Rating Curve Sorted= 0
DSS Export Volume Flow Curves= 0
DXF OffsetX= 0
DXF OffsetY= 0
DXF ScaleX= 1
DXF ScaleY= 10

--- MULE TANK CREEK.p01 (plan) ---

Plan Title=Multiple Run
Short Identifier=Multiple
Geom File=g01
Flow File=f01
Subcritical Flow
K Sum by GR= 0
Std Step Tol= 0.01
Critical Tol= 0.01
Num of Std Step Trials= 20
Max Error Tol= 0.3
Flow Tol Ratio= 0.001
Split Flow NTrial= 30
Split Flow Tol= 0.02
Split Flow Ratio= 0.02
Log Output Level= 0
Friction Slope Method= 1
Unsteady Friction Slope Method= 2
Unsteady Bridges Friction Slope Method= 1
Parabolic Critical Depth
Global Vel Dist=  1 , 1 , 1
Global Log Level= 0
CheckData=True
Encroach Param= -1, 0, 0, 0
BEGIN DESCRIPTION:
Multiple Run
END DESCRIPTION:

--- MULE TANK CREEK.f01 (steady flow) ---

Flow Title=Multiple
Program Version=4.10
Number of Profiles= 7
Profile Names=10-year,25-year,50-year,1pct_min,100-year,1pct_plu,500-year
River Rch & RM=MULE TANK CREEK,Reach-1         ,7427
     214     291     353     315     426     576     628
Boundary for River Rch & Prof#=MULE TANK CREEK,Reach-1         , 1
Up Type= 0
Dn Type= 3
Dn Slope=0.004
Boundary for River Rch & Prof#=MULE TANK CREEK,Reach-1         , 2
Up Type= 0
Dn Type= 3
Dn Slope=0.004
Boundary for River Rch & Prof#=MULE TANK CREEK,Reach-1         , 3
Up Type= 0
Dn Type= 3
Dn Slope=0.004
Boundary for River Rch & Prof#=MULE TANK CREEK,Reach-1         , 4
Up Type= 0
Dn Type= 3
Dn Slope=0.004
Boundary for River Rch & Prof#=MULE TANK CREEK,Reach-1         , 5
Up Type= 0
Dn Type= 3
Dn Slope=0.004
Boundary for River Rch & Prof#=MULE TANK CREEK,Reach-1         , 6
Up Type= 0
Dn Type= 3
Dn Slope=0.004
Boundary for River Rch & Prof#=MULE TANK CREEK,Reach-1         , 7
Up Type= 0
Dn Type= 3
Dn Slope=0.004
DSS Import GetInterval= 0
DSS Import GetPeak= 0
DSS Import FillOption= 0

--- MULE TANK CREEK.g01 (geometry) ---

Geom Title=Existing Conditions
Program Version=4.10

River Reach=MULE TANK CREEK ,Reach-1
Reach XY= 30
      2233587.72     13185696.85      2233537.72     13185846.85
      2233337.72     13185996.85      2233437.72     13186196.85
      2233287.72     13186546.85      2233437.72     13186646.85
      2233437.72     13186846.85      2232987.72     13187146.85
      2233037.72     13187396.86      2232687.72     13187746.85
      2232687.72     13187896.86      2232737.72     13188096.85
      2232887.72     13188246.85      2232837.72     13188446.85
      2232887.72     13188846.85      2233037.72     13188946.85
      2233287.72     13188996.85      2233487.72     13189146.85
      2233487.72     13189296.85      2233287.72     13189396.85
      2232987.72     13189696.86      2232987.72     13189946.85
      2233087.72     13190046.85      2233237.72     13189996.85
      2233587.72     13190046.85      2233737.72     13190196.86
      2233787.72     13190346.86      2233687.72     13190396.85
      2233687.72     13190546.85      2233837.72     13190796.85

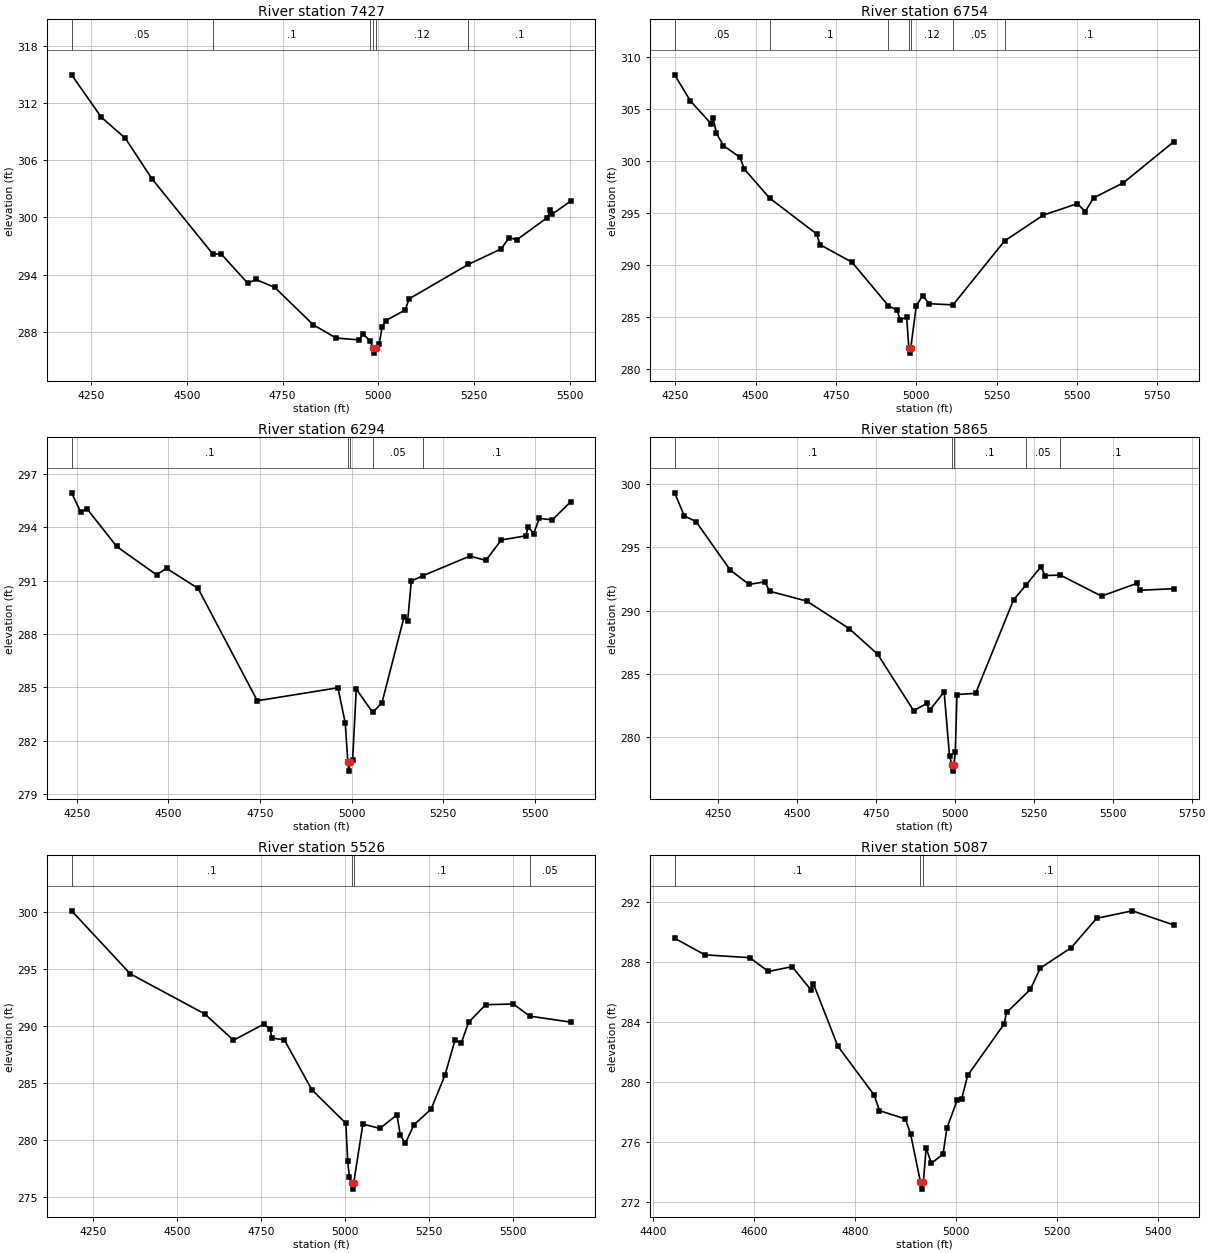
Type RM Length L Ch R = 1 ,7427    ,673,673,673
BEGIN DESCRIPTION:
MULE TANK CREEK 13.0
END DESCRIPTION:
XS GIS Cut Line= 3
      2232737.68     13185796.85      2233537.72     13185846.85
      2234037.73     13185796.85
#Sta/Elev= 30
  4198.4  314.95  4276.1   310.5  4338.7   308.3  4408.8  304.03  4567.5  296.16
  4589.2  296.17  4659.3  293.08  4679.4   293.5  4729.5  292.66  4829.7  288.75
  4889.8  287.35  4949.9  287.16  4959.9  287.79  4977.7  287.09    4987  286.27
  4989.7  285.77    4993  286.27  5002.5  286.76  5010.1  288.54  5020.1  289.19
  5070.3  290.29  5080.4  291.46  5235.3  295.07  5321.6  296.71  5341.7  297.89
  5361.8  297.65  5442.2  299.99  5449.7  300.78  5454.8  300.34  5502.5  301.71
#Mann= 6 ,-1 , 0
  4198.4     .05       0  4567.5      .1       0  4977.7     .12       0
    4987     .04       0    4993     .12       0  5235.3      .1       0
Bank Sta=4987,4993
XS Rating Curve= 0 ,0
Exp/Cntr=0.3,0.1

Type RM Length L Ch R = 1 ,6754    ,460,460,460
BEGIN DESCRIPTION:
MULE TANK CREEK 12.0
END DESCRIPTION:
XS GIS Cut Line= 4
      2232653.25      13186198.4      2233035.24     13186316.47
      2233688.02     13186316.47      2234160.27      13186149.8
#Sta/Elev= 30
  4247.7   308.3  4296.4  305.81  4361.6  303.59  4367.5  304.14    4378  302.67
  4399.5   301.5  4451.2  300.37  4464.8  299.24  4543.8  296.44    4690     293
    4700  291.98    4800  290.29  4913.4   286.1    4940  285.68    4950  284.73
    4970  285.03    4977  282.05  4979.8  281.55    4983  282.05    5000   286.1
    5020  287.08    5040   286.3  5114.5  286.19  5274.8  292.33  5395.4  294.81
  5501.5  295.92  5526.2  295.16  5551.9  296.47  5644.7  297.92  5801.1  301.85
#Mann= 7 ,-1 , 0
  4247.7     .05       0  4543.8      .1       0  4913.4     .12       0
    4977     .07       0    4983     .12       0  5114.5     .05       0
  5274.8      .1       0
Bank Sta=4977,4983
XS Rating Curve= 0 ,0
Exp/Cntr=0.3,0.1

Type RM Length L Ch R = 1 ,6294    ,429,429,429
BEGIN DESCRIPTION:
MULE TANK CREEK 11.0
END DESCRIPTION:
XS GIS Cut Line= 4
      2232687.98     13186524.79      2233049.13     13186635.92
      2233694.97     13186649.81       2233979.7     13186469.24
#Sta/Elev= 30
  4236.1  295.94    4261  294.85  4277.7  295.05  4359.1  292.92  4467.7  291.33
  4495.1  291.69  4581.1  290.56  4742.6  284.24  4962.6  284.97  4982.6  282.98
  4989.6  280.78  4992.4  280.28  4995.6  280.78  5002.6   280.9  5012.6   284.9
  5057.3  283.58  5082.7  284.13  5142.7  288.94  5152.7  288.71  5162.7  290.97
  5193.7  291.27  5322.4  292.38    5366  292.14  5408.4  293.29  5475.3  293.52
  5481.2  294.03  5496.5  293.65  5511.7   294.5  5547.4  294.42  5597.1  295.43
#Mann= 5 ,-1 , 0
  4236.1      .1       0  4989.6     .07       0  4995.6      .1       0
  5057.3     .05       0  5193.7      .1       0
Bank Sta=4989.6,4995.6
XS Rating Curve= 0 ,0
Exp/Cntr=0.3,0.1

Type RM Length L Ch R = 1 ,5865    ,339,339,339
BEGIN DESCRIPTION:
MULE TANK CREEK 10.0
END DESCRIPTION:
XS GIS Cut Line= 4
      2232458.85     13186615.08      2232938.02     13186885.92
      2233444.97     13187017.86      2233931.07     13186878.98
#Sta/Elev= 30
  4112.9  299.32  4143.7  297.49  4180.5  297.05  4289.4   293.2  4348.6  292.08
  4398.8  292.28  4413.6  291.54    4532  290.75  4665.7  288.58    4756  286.55
  4869.7  282.09    4911  282.66  4920.6  282.13  4966.3  283.58  4983.3  278.51
  4990.7  277.81  4993.4  277.31  4996.7  277.81  5001.7   278.8  5006.8  283.37
    5066  283.46    5186  290.85  5225.2  292.02  5273.2  293.48  5285.3  292.78
  5334.5  292.81  5464.7  291.15  5576.5  292.16  5585.2  291.61  5692.7  291.74
#Mann= 5 ,-1 , 0
  4112.9      .1       0  4990.7     .07       0  4996.7      .1       0
  5225.2     .05       0  5334.5      .1       0
Bank Sta=4990.7,4996.7
XS Rating Curve= 0 ,0
Exp/Cntr=0.3,0.1

Type RM Length L Ch R = 1 ,5526    ,439,439,439
BEGIN DESCRIPTION:
MULE TANK CREEK 9.0
END DESCRIPTION:
XS GIS Cut Line= 4
      2232292.22     13186767.88      2232736.63     13187094.25
      2233438.02     13187219.25      2233653.05     13187163.76
#Sta/Elev= 30
  4186.8  300.08  4361.8  294.54  4583.3  291.03  4668.9  288.72  4759.6  290.14
  4778.2  289.67  4783.3  288.91  4820.5  288.75  4901.8  284.39  5003.4  281.43
    5009  278.13  5014.1   276.7  5020.7  276.15  5023.5  275.65  5026.7  276.15
  5054.2  281.36    5105  280.98  5155.7  282.17  5165.9  280.36  5180.8  279.67
  5206.5  281.31  5257.3  282.66  5298.8  285.66  5328.4  288.72  5347.6   288.5
  5369.1  290.29  5419.8  291.84    5502   291.9  5551.1  290.84  5672.7  290.31
#Mann= 4 ,-1 , 0
  4186.8      .1       0  5020.7     .07       0  5026.7      .1       0
  5551.1     .05       0
Bank Sta=5020.7,5026.7
XS Rating Curve= 0 ,0
Exp/Cntr=0.3,0.1

Type RM Length L Ch R = 1 ,5087    ,431,431,431
BEGIN DESCRIPTION:
MULE TANK CREEK 8.0
END DESCRIPTION:
XS GIS Cut Line= 3
      2232403.34     13187358.15      2233125.52     13187531.75
       2233368.6     13187497.03
#Sta/Elev= 30
  4441.9  289.61  4501.8   288.5  4590.8  288.31  4627.6  287.39  4674.7  287.71
  4711.6  286.17  4716.7  286.58  4765.2   282.4  4837.2  279.13  4847.7  278.09
  4898.9  277.54  4909.2  276.55  4928.7  273.35  4931.4  272.85  4934.7  273.35
  4940.1   275.6  4950.4  274.57  4973.6  275.19  4981.2  276.92  5001.8  278.81
  5010.4  278.87  5022.4  280.45  5094.4  283.87  5099.5  284.65  5146.6  286.19
  5166.3  287.62  5227.3  288.97  5277.8  290.94  5348.5  291.44  5430.2   290.5
#Mann= 3 ,-1 , 0
  4441.9      .1       0  4928.7     .07       0  4934.7      .1       0
Bank Sta=4928.7,4934.7
XS Rating Curve= 0 ,0
Exp/Cntr=0.3,0.1

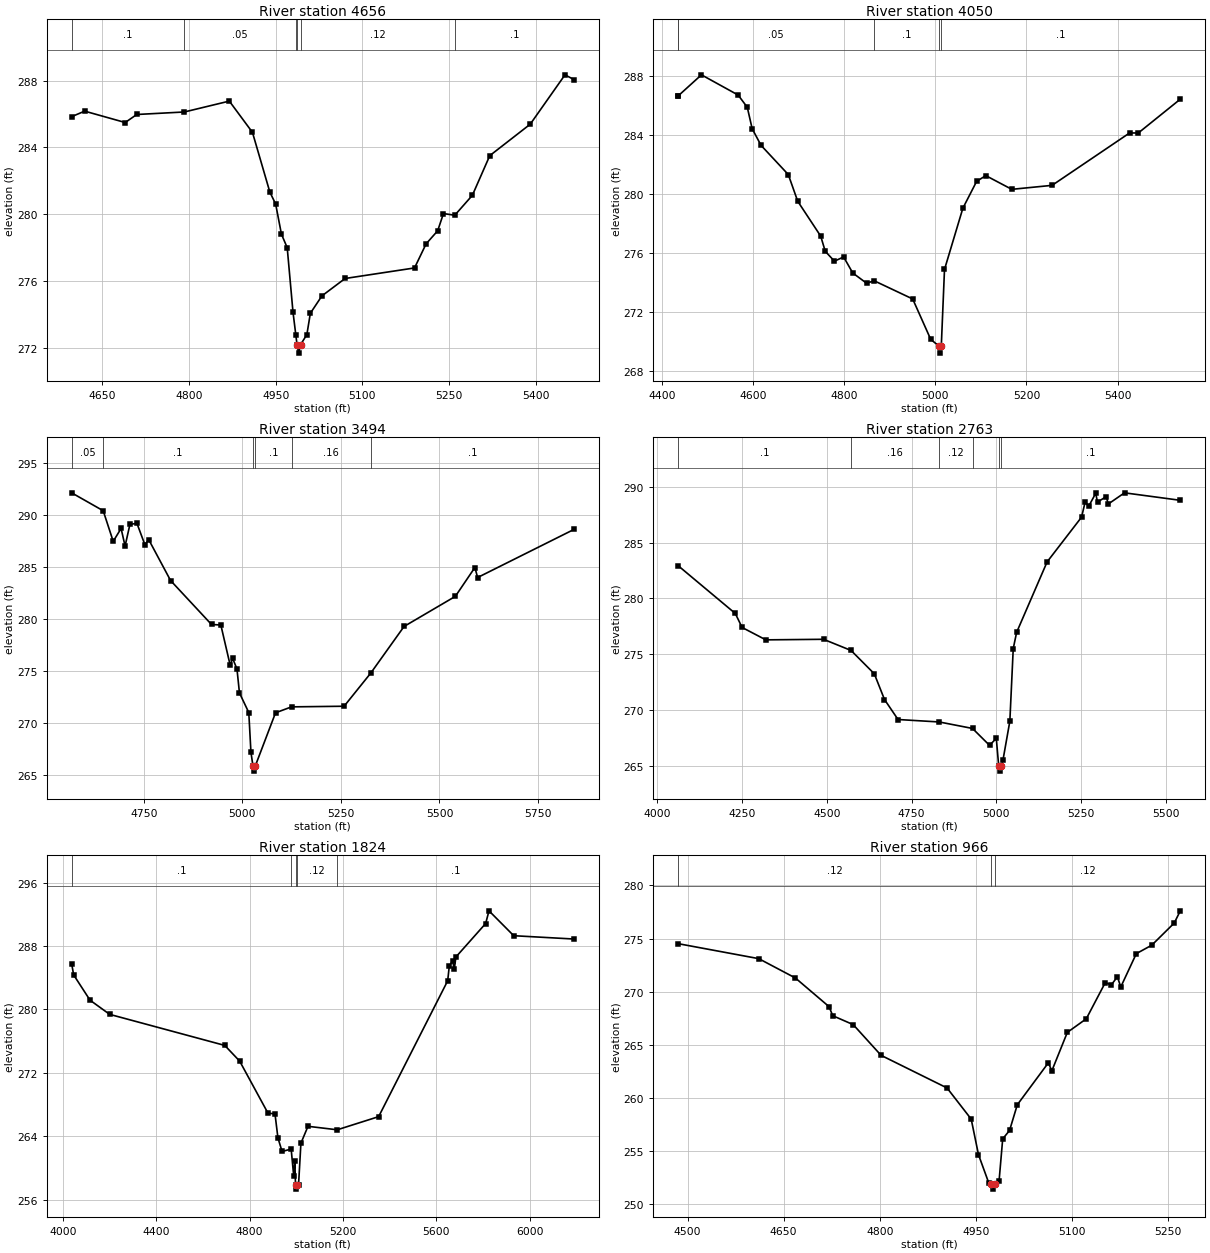
Type RM Length L Ch R = 1 ,4656    ,606,606,606
BEGIN DESCRIPTION:
MULE TANK CREEK 7.0
END DESCRIPTION:
XS GIS Cut Line= 2
      2232285.24     13187795.64      2233153.05     13187830.35
#Sta/Elev= 30
  4597.2  285.84  4619.7  286.17  4689.8  285.49  4709.8  285.97  4792.1  286.12
  4869.9  286.77  4909.9   284.9    4940  281.33    4950  280.62    4960  278.82
    4970  278.01    4980  274.16  4984.8  272.82    4987  272.21  4989.7  271.71
    4993  272.21    5004  272.82    5010  274.09    5030  275.13  5070.1  276.17
  5190.2   276.8  5210.2  278.24  5230.2  279.02  5240.2  280.05  5259.8  279.95
  5290.2  281.14  5320.3  283.51  5390.3  285.39  5450.4  288.34  5465.7  288.06
#Mann= 6 ,-1 , 0
  4597.2      .1       0  4792.1     .05       0  4984.8     .12       0
    4987     .07       0    4993     .12       0  5259.8      .1       0
Bank Sta=4987,4993
XS Rating Curve= 0 ,0
Exp/Cntr=0.3,0.1

Type RM Length L Ch R = 1 ,4050    ,556,556,556
BEGIN DESCRIPTION:
MULE TANK CREEK 6.0
END DESCRIPTION:
XS GIS Cut Line= 3
      2232326.87     13188399.81      2233056.08     13188316.47
      2233402.46     13188191.77
#Sta/Elev= 30
  4435.5  286.64  4435.9  286.64  4486.7  288.06  4567.2  286.69  4587.3  285.86
    4598  284.41  4617.5  283.28  4677.3   281.3    4698  279.49  4748.4  277.13
  4758.4   276.1  4778.6  275.43  4798.7  275.72  4818.8  274.63    4849  273.94
    4866   274.1  4950.3  272.87  4989.9  270.13  5007.1   269.7  5009.8   269.2
  5013.1   269.7  5020.1  274.87  5060.4  279.02  5090.6  280.84  5110.7  281.23
  5167.8   280.3  5256.2  280.57  5426.3  284.12  5445.5  284.12  5537.6  286.41
#Mann= 5 ,-1 , 0
  4435.5      .1       0  4435.9     .05       0    4866      .1       0
  5007.1     .07       0  5013.1      .1       0
Bank Sta=5007.1,5013.1
XS Rating Curve= 0 ,0
Exp/Cntr=0.3,0.1

Type RM Length L Ch R = 1 ,3494    ,731,731,731
BEGIN DESCRIPTION:
MULE TANK CREEK 5.0
END DESCRIPTION:
XS GIS Cut Line= 4
      2232472.73     13188899.81      2232722.74     13188920.64
      2233375.52     13188642.86      2233597.13     13188421.25
#Sta/Elev= 30
  4567.1  292.09  4647.1  290.37  4672.5  287.43  4692.5  288.67  4702.6  286.98
  4714.9  289.06  4732.7  289.16  4752.7  287.12  4762.8  287.58    4818  283.67
  4921.8  279.45  4945.5   279.4  4969.1  275.55  4975.5  276.19  4986.4  275.17
  4992.7  272.88  5016.4  270.99  5021.8   267.2  5026.9  265.87  5029.6  265.37
  5032.9  265.87  5084.2  270.97  5124.8  271.54  5258.1   271.6  5325.9  274.79
  5410.2  279.26  5540.3  282.15  5589.8  284.92  5596.8  283.96  5840.8  288.57
#Mann= 6 ,-1 , 0
  4567.1     .05       0  4647.1      .1       0  5026.9     .07       0
  5032.9      .1       0  5124.8     .16       0  5325.9      .1       0
Bank Sta=5026.9,5032.9
XS Rating Curve= 0 ,0
Exp/Cntr=0.3,0.1

Type RM Length L Ch R = 1 ,2763    ,939,939,939
BEGIN DESCRIPTION:
MULE TANK CREEK 4.0
END DESCRIPTION:
XS GIS Cut Line= 4
      2232549.18     13189135.92      2232938.02     13189156.75
      2233708.85     13189156.75       2234013.6     13189052.86
#Sta/Elev= 30
  4060.9  282.93  4229.7  278.65  4249.7   277.4  4319.8  276.29    4490  276.34
  4571.4  275.34    4640  273.25    4670  270.95    4710  269.16  4831.7  268.94
  4929.8  268.36    4980  266.85    5000  267.47    5007  265.04  5009.7  264.54
    5013  265.04    5020  265.58    5040  269.01    5050  275.51    5060  276.96
    5150  283.27  5251.6  287.27  5262.1  288.61  5272.8  288.25  5293.4  289.41
  5298.7  288.62  5324.8  289.12  5330.1  288.44  5378.4  289.45  5543.1  288.78
#Mann= 6 ,-1 , 0
  4060.9      .1       0  4571.4     .16       0  4831.7     .12       0
  4929.8      .1       0    5007     .07       0    5013      .1       0
Bank Sta=5007,5013
XS Rating Curve= 0 ,0
Exp/Cntr=0.3,0.1

Type RM Length L Ch R = 1 ,1824    ,858,858,858
BEGIN DESCRIPTION:
MULE TANK CREEK 3.0
END DESCRIPTION:
XS GIS Cut Line= 4
      2232429.34     13189214.14      2232676.75     13189813.14
      2233444.98     13189708.98      2233939.75     13189175.15
#Sta/Elev= 30
  4038.1  285.77  4046.7  284.35  4116.8  281.16    4201  279.37    4694  275.45
  4757.8  273.47  4878.9  266.91  4909.2   266.8  4921.7  263.78  4939.5  262.06
  4978.4  262.37  4989.2  259.01  4994.2  260.88    4997  257.81  4999.8  257.31
    5003  257.81  5010.1  257.87  5020.2  263.11  5050.5  265.24  5175.7   264.8
  5353.2  266.46  5648.9  283.61  5655.7  285.45  5669.9  286.13  5677.2  285.07
    5684  286.61  5811.6  290.84  5825.8  292.44  5931.8   289.3  6189.3  288.88
#Mann= 5 ,-1 , 0
  4038.1      .1       0  4978.4     .12       0    4997     .07       0
    5003     .12       0  5175.7      .1       0
Bank Sta=4997,5003
XS Rating Curve= 0 ,0
Exp/Cntr=0.3,0.1

Type RM Length L Ch R = 1 ,966     ,699,699,699
BEGIN DESCRIPTION:
MULE TANK CREEK 2.0
END DESCRIPTION:
XS GIS Cut Line= 3
       2233137.7     13190296.86      2233587.72     13190046.85
      2233687.74     13189796.82
#Sta/Elev= 30
  4485.2  274.52  4611.1  273.11  4668.3  271.29  4720.9  268.59  4726.6  267.74
  4758.6   266.9  4802.1  264.01  4905.1  260.94  4942.8  258.01  4954.2  254.66
  4970.3  251.99  4974.1  251.92  4976.9  251.42  4980.1  251.92  4986.3  252.17
    4992  256.15  5002.7  256.94  5014.8  259.36  5063.3  263.31  5068.7  262.55
  5092.9  266.17  5122.5  267.45  5152.1  270.85  5161.6  270.64    5171   271.4
  5176.4  270.45  5200.6  273.58  5224.8  274.38  5259.8  276.46  5269.3  277.61
#Mann= 3 ,-1 , 0
  4485.2     .12       0  4974.1     .07       0  4980.1     .12       0
Bank Sta=4974.1,4980.1
XS Rating Curve= 0 ,0
Exp/Cntr=0.3,0.1

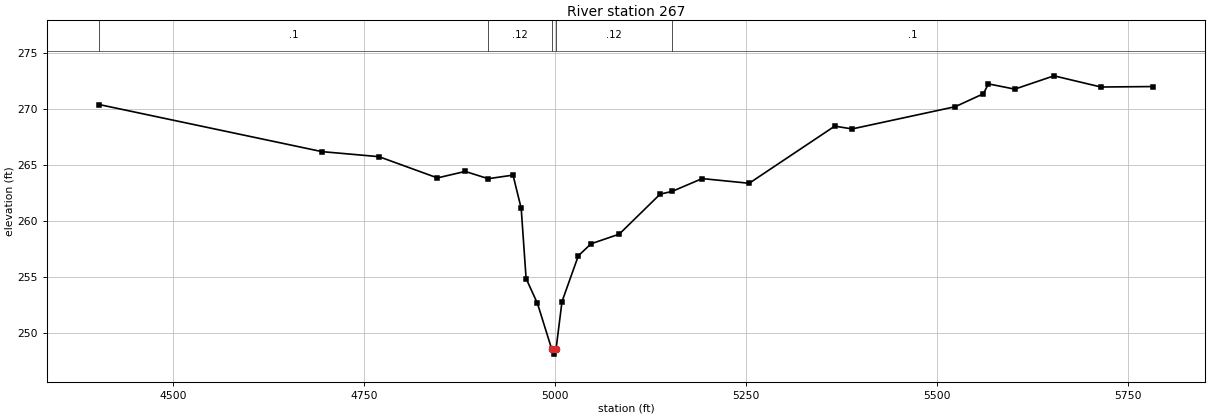
Type RM Length L Ch R = 1 ,267     ,0,0,0
BEGIN DESCRIPTION:
MULE TANK CREEK 1.0
END DESCRIPTION:
XS GIS Cut Line= 4
      2233184.58     13190425.13      2233575.19     13190633.46
       2233952.8     13190490.23       2234069.7     13189970.67
#Sta/Elev= 30
  4402.9   270.4  4694.5  266.19  4769.1  265.74  4845.6  263.84    4882  264.42
  4912.1  263.77  4944.6  264.09  4955.3  261.11  4961.7  254.84  4976.6  252.61
    4995  248.58  4997.8  248.08    5001  248.58  5008.7  252.78  5030.1  256.88
  5046.8  257.95  5083.6  258.81  5137.2  262.39  5152.7  262.63  5192.2  263.78
  5253.7  263.36  5365.7  268.47  5388.5  268.22  5523.5  270.21  5560.4  271.37
  5566.8  272.25  5601.4  271.78  5652.7  272.97  5714.2  271.97    5782  272.01
#Mann= 5 ,-1 , 0
  4402.9      .1       0  4912.1     .12       0    4995     .07       0
    5001     .12       0  5152.7      .1       0
Bank Sta=4995,5001
XS Rating Curve= 0 ,0
Exp/Cntr=0.3,0.1

Chan Stop Cuts=-1
Use User Specified Reach Order=0
Composite Channel Slope=5