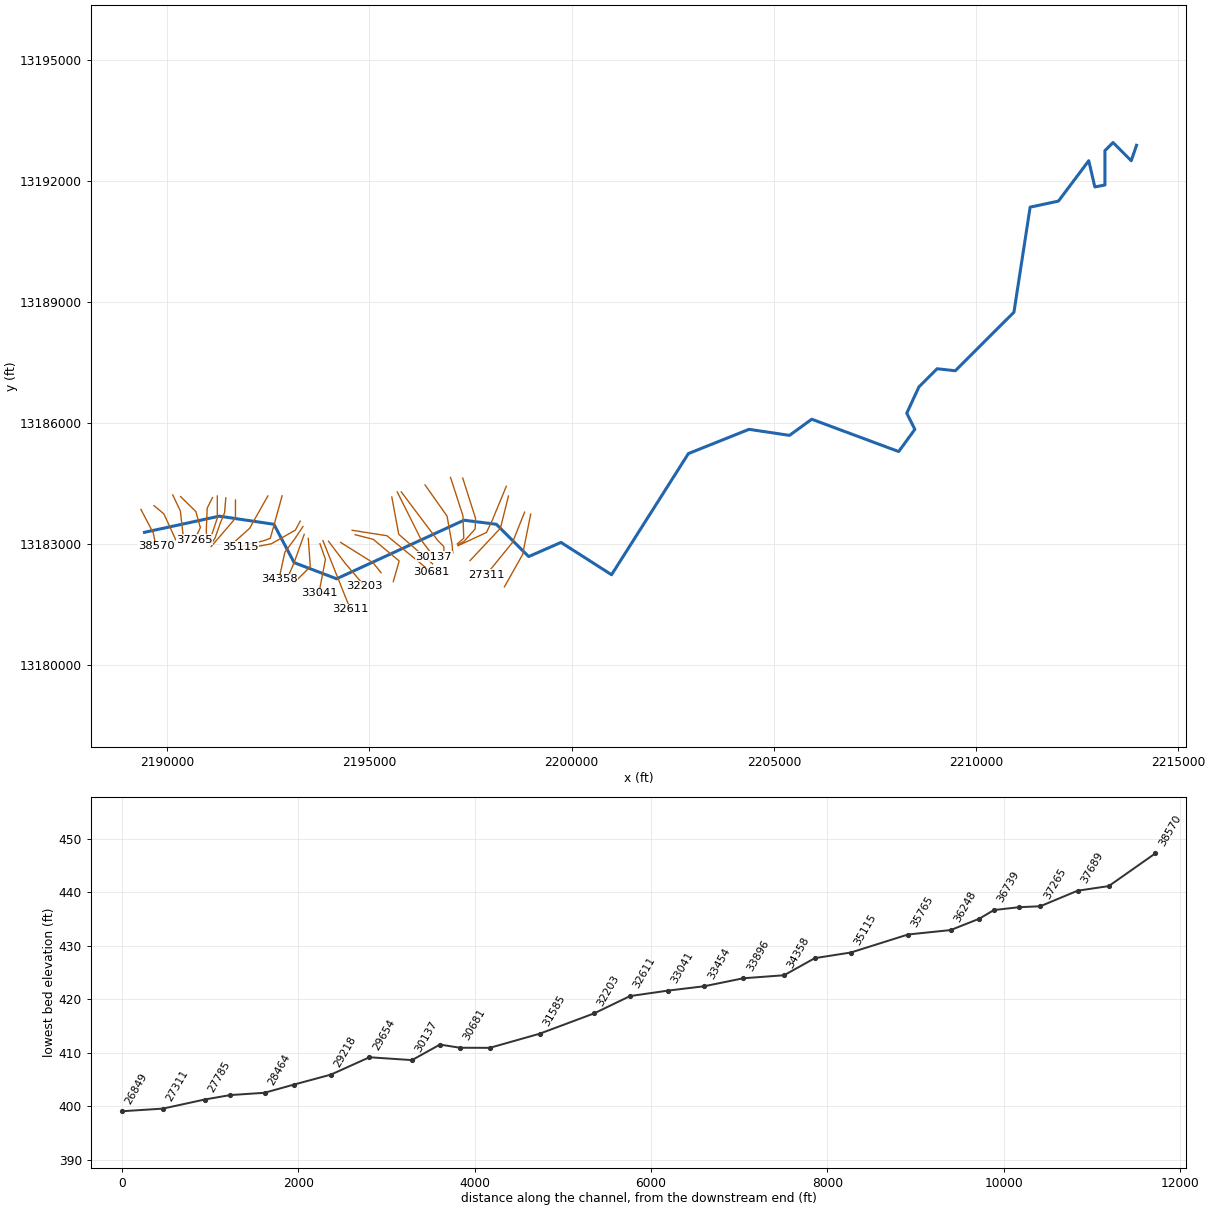
--- PALO AMARILLO CREEK.prj (project) ---

Proj Title=PALO AMARILLO CREEK Base Level Engineering
Current Plan=p01
Default Exp/Contr=0.3,0.1
English Units
Geom File=g01
Flow File=f01
Plan File=p01
Y Axis Title=Elevation
X Axis Title(PF)=Main Channel Distance
X Axis Title(XS)=Station
BEGIN DESCRIPTION:
PALO AMARILLO CREEK
END DESCRIPTION:
DSS Export Rating Curves= 0
DSS Export Rating Curve Sorted= 0
DSS Export Volume Flow Curves= 0
DXF OffsetX= 0
DXF OffsetY= 0
DXF ScaleX= 1
DXF ScaleY= 10

--- PALO AMARILLO CREEK.p01 (plan) ---

Plan Title=Multiple Run
Short Identifier=Multiple
Geom File=g01
Flow File=f01
Subcritical Flow
K Sum by GR= 0
Std Step Tol= 0.01
Critical Tol= 0.01
Num of Std Step Trials= 20
Max Error Tol= 0.3
Flow Tol Ratio= 0.001
Split Flow NTrial= 30
Split Flow Tol= 0.02
Split Flow Ratio= 0.02
Log Output Level= 0
Friction Slope Method= 1
Unsteady Friction Slope Method= 2
Unsteady Bridges Friction Slope Method= 1
Parabolic Critical Depth
Global Vel Dist=  1 , 1 , 1
Global Log Level= 0
CheckData=True
Encroach Param= -1, 0, 0, 0
BEGIN DESCRIPTION:
Multiple Run
END DESCRIPTION:

--- PALO AMARILLO CREEK.f01 (steady flow) ---

Flow Title=Multiple
Program Version=4.10
Number of Profiles= 7
Profile Names=10-year,25-year,50-year,1pct_min,100-year,1pct_plu,500-year
River Rch & RM=PALO AMARILLO CR,Reach-1         ,38570
     156     214     262     236     319     432     481
River Rch & RM=PALO AMARILLO CR,Reach-1         ,37022
     224     313     387     352     477     644     734
River Rch & RM=PALO AMARILLO CR,Reach-1         ,36739
     224     313     387     352     477     644     734
River Rch & RM=PALO AMARILLO CR,Reach-1         ,34358
     315     447     560     515     696     942    1095
River Rch & RM=PALO AMARILLO CR,Reach-1         ,33896
     315     447     560     515     696     942    1095
River Rch & RM=PALO AMARILLO CR,Reach-1         ,32611
     369     527     663     612     827    1119    1309
River Rch & RM=PALO AMARILLO CR,Reach-1         ,32203
     369     527     663     612     827    1119    1309
River Rch & RM=PALO AMARILLO CR,Reach-1         ,30681
     460     663     838     778    1052    1423    1683
River Rch & RM=PALO AMARILLO CR,Reach-1         ,30454
     460     663     838     778    1052    1423    1683
River Rch & RM=PALO AMARILLO CR,Reach-1         ,28074
     513     743     940     873    1181    1597    1894
River Rch & RM=PALO AMARILLO CR,Reach-1         ,24415
     648     943    1199    1117    1511    2043    2437
River Rch & RM=PALO AMARILLO CR,Reach-1         ,17561
     734    1074    1371    1281    1733    2343    2815
River Rch & RM=PALO AMARILLO CR,Reach-1         ,14212
     860    1266    1621    1521    2057    2781    3363
River Rch & RM=PALO AMARILLO CR,Reach-1         ,12341
     889    1304    1667    1560    2109    2853    3433
River Rch & RM=PALO AMARILLO CR,Reach-1         ,11991
     889    1304    1667    1560    2109    2853    3433
Boundary for River Rch & Prof#=PALO AMARILLO CR,Reach-1         , 1
Up Type= 0
Dn Type= 3
Dn Slope=0.0007
Boundary for River Rch & Prof#=PALO AMARILLO CR,Reach-1         , 2
Up Type= 0
Dn Type= 3
Dn Slope=0.0007
Boundary for River Rch & Prof#=PALO AMARILLO CR,Reach-1         , 3
Up Type= 0
Dn Type= 3
Dn Slope=0.0007
Boundary for River Rch & Prof#=PALO AMARILLO CR,Reach-1         , 4
Up Type= 0
Dn Type= 3
Dn Slope=0.0007
Boundary for River Rch & Prof#=PALO AMARILLO CR,Reach-1         , 5
Up Type= 0
Dn Type= 3
Dn Slope=0.0007
Boundary for River Rch & Prof#=PALO AMARILLO CR,Reach-1         , 6
Up Type= 0
Dn Type= 3
Dn Slope=0.0007
Boundary for River Rch & Prof#=PALO AMARILLO CR,Reach-1         , 7
Up Type= 0
Dn Type= 3
Dn Slope=0.0007
DSS Import GetInterval= 0
DSS Import GetPeak= 0
DSS Import FillOption= 0

--- PALO AMARILLO CREEK.g01 (geometry) ---

Geom Title=Existing Conditions
Program Version=4.10

River Reach=PALO AMARILLO CR,Reach-1
Reach XY= 30
      2189437.72     13183296.86      2191287.72     13183696.85
      2192637.72     13183496.85      2193137.72     13182546.85
      2194187.72     13182146.86      2197337.72     13183596.85
      2198137.72     13183496.85      2198937.72     13182696.85
      2199737.72     13183046.85      2200987.72     13182246.85
      2202887.72     13185246.86      2204387.72     13185846.85
      2205387.72     13185696.85      2205937.72     13186096.86
      2208087.72     13185296.85      2208487.72     13185846.85
      2208287.72     13186246.86      2208587.72     13186896.86
      2209037.72     13187346.85      2209487.72     13187296.85
      2210937.72     13188746.85      2211337.72     13191346.86
      2212037.72     13191496.86      2212787.72     13192496.86
      2212937.72     13191846.85      2213187.72     13191896.85
      2213187.72     13192746.85      2213387.72     13192946.85
      2213837.72     13192496.86      2213969.02     13192878.16

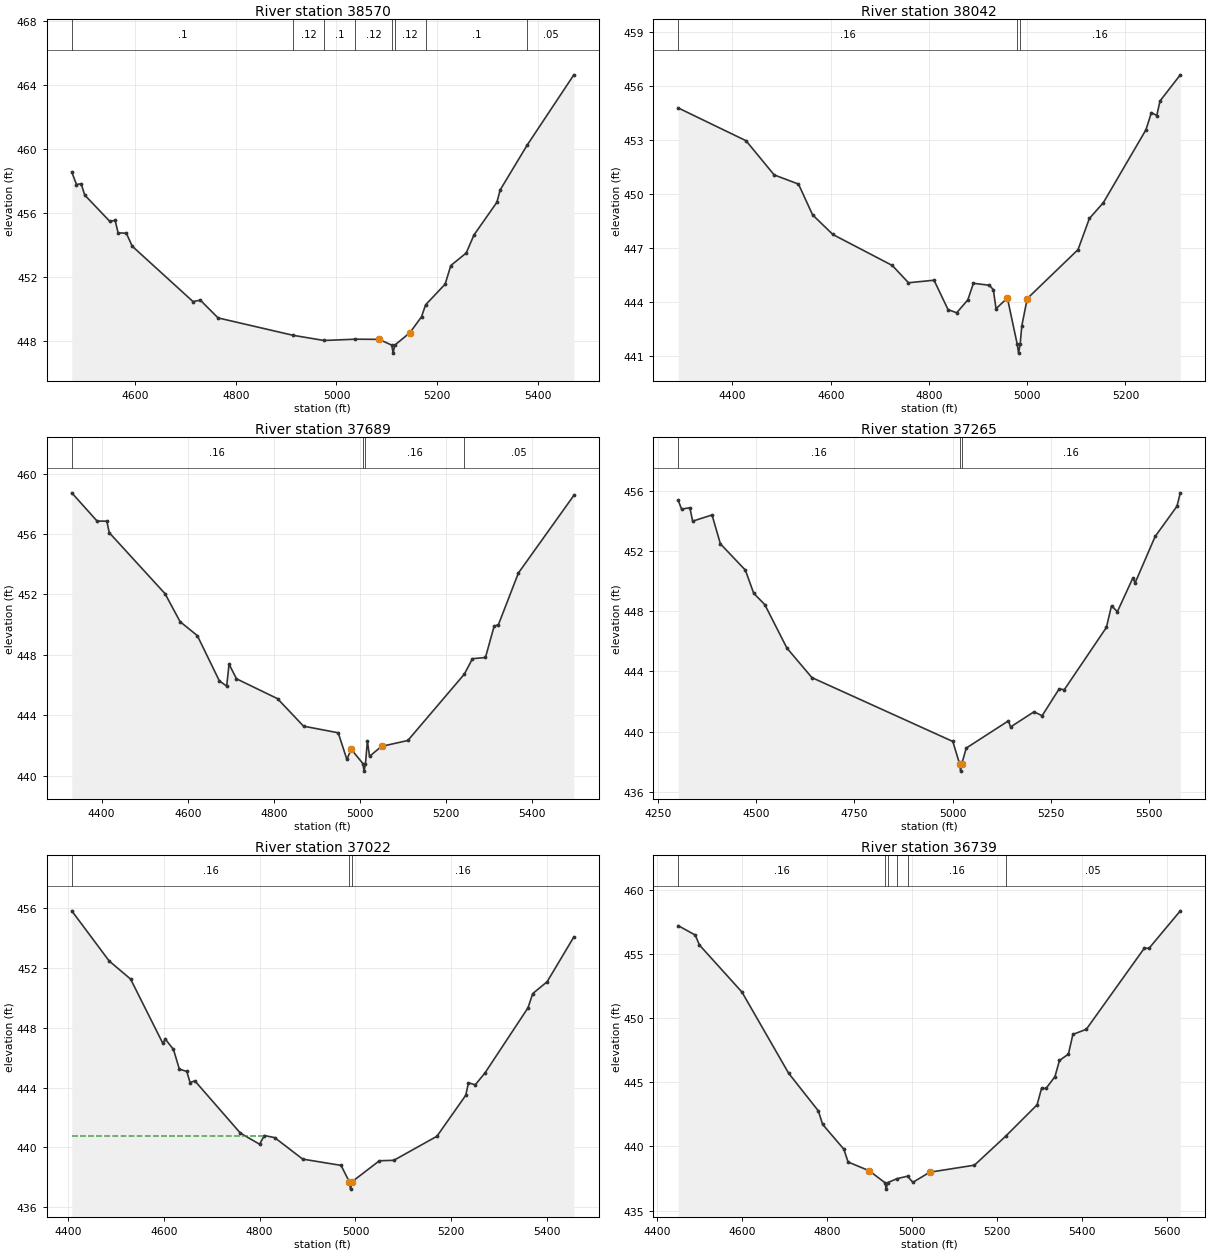
Type RM Length L Ch R = 1 ,38570   ,528,528,528
BEGIN DESCRIPTION:
PALO AMARILLO CREEK 64.0
END DESCRIPTION:
XS GIS Cut Line= 3
        2189350.      13183863.3      2189657.31     13183274.72
      2189719.81      13182946.6
#Sta/Elev= 30
  4473.8  458.57  4483.2  457.79  4492.4  457.84  4499.6  457.13  4549.4  455.49
    4560  455.55  4565.9  454.77  4582.3  454.75  4593.9  453.94  4714.8  450.48
  4729.3  450.57  4764.6  449.46  4914.2  448.37  4975.2  448.05  5037.7  448.13
  5084.6  448.12  5109.8  447.76  5112.6  447.26  5115.8  447.76  5145.8  448.53
    5169  449.53  5177.2  450.28    5216  451.57  5227.2  452.73  5257.8  453.51
  5273.3  454.64  5318.8  456.68  5325.5  457.46    5379  460.25  5471.8  464.64
#Mann= 8 ,-1 , 0
  4473.8      .1       0  4914.2     .12       0  4975.2      .1       0
  5037.7     .12       0  5109.8     .07       0  5115.8     .12       0
  5177.2      .1       0    5379     .05       0
Bank Sta=5084.6,5145.8
XS Rating Curve= 0 ,0
Exp/Cntr=0.3,0.1

Type RM Length L Ch R = 1 ,38042   ,353,353,353
BEGIN DESCRIPTION:
PALO AMARILLO CREEK 63.0
END DESCRIPTION:
XS GIS Cut Line= 3
      2189672.93     13183957.02      2189917.73     13183753.89
       2190209.4     13183113.26
#Sta/Elev= 30
  4289.6  454.77  4427.6  452.95  4484.9  451.05  4534.4  450.54  4563.1  448.83
  4604.4  447.74  4725.3  446.02  4758.3  445.06  4810.3   445.2  4838.8  443.57
  4856.4  443.39  4879.1  444.11  4890.4  445.03  4923.1  444.92    4931  444.67
  4936.5  443.62  4959.6  444.21  4979.6  441.65  4982.4  441.15  4985.6  441.65
    4989  442.67    5000  444.18  5103.4   446.9  5126.5  448.63    5155  449.51
  5241.7  453.56  5252.7  454.51  5263.7  454.35  5270.3  455.16  5311.6  456.61
#Mann= 3 ,-1 , 0
  4289.6     .16       0  4979.6     .07       0  4985.6     .16       0
Bank Sta=4959.6,5000
XS Rating Curve= 0 ,0
Exp/Cntr=0.3,0.1

Type RM Length L Ch R = 1 ,37689   ,424,424,424
BEGIN DESCRIPTION:
PALO AMARILLO CREEK 62.0
END DESCRIPTION:
XS GIS Cut Line= 3
      2190136.46     13184222.67      2190323.98     13183826.81
      2190407.32     13183102.82
#Sta/Elev= 30
  4330.5  458.73  4389.3  456.86    4412  456.85  4417.6  456.09  4547.2  452.05
  4582.3  450.19  4622.3  449.27  4673.3  446.28  4690.5  445.92    4696  447.38
  4713.2  446.41  4808.7  445.09  4869.1  443.27  4949.7  442.83  4969.8  441.07
  4979.9  441.74  5007.1  440.79  5009.8  440.29  5013.1  440.79  5017.5  442.29
  5022.5  441.27  5050.3  441.93  5111.5  442.32  5242.9  446.72  5261.7  447.74
  5291.9  447.82    5312  449.89  5322.1     450  5368.5  453.42  5497.3  458.56
#Mann= 4 ,-1 , 0
  4330.5     .16       0  5007.1     .07       0  5013.1     .16       0
  5242.9     .05       0
Bank Sta=4979.9,5050.3
XS Rating Curve= 0 ,0
Exp/Cntr=0.3,0.1

Type RM Length L Ch R = 1 ,37265   ,243,243,243
BEGIN DESCRIPTION:
Mapping XS b8732f82
END DESCRIPTION:
XS GIS Cut Line= 4
      2190329.96     13184181.01      2190707.94      13183810.8
      2190819.27     13183412.07      2190671.71     13183109.17
#Sta/Elev= 30
  4300.7  455.36  4309.2  454.78  4330.3  454.87  4337.5  453.98  4386.9  454.39
  4408.2  452.47  4471.8  450.73  4493.1  449.19  4521.3  448.44  4577.8  445.55
  4641.5  443.59  5000.7  439.35  5017.8  437.88  5020.5  437.38  5023.8  437.88
  5034.9  438.91  5142.6  440.72  5147.8  440.31  5207.7  441.32  5228.4  441.06
  5271.8  442.84    5285  442.79  5392.2  446.92  5405.3  448.36  5420.3  447.97
  5459.8  450.21  5465.4  449.88  5516.5  452.96  5572.2  454.97  5580.7  455.86
#Mann= 3 ,-1 , 0
  4300.7     .16       0  5017.8     .07       0  5023.8     .16       0
Bank Sta=5017.8,5023.8
XS Rating Curve= 0 ,0
Exp/Cntr=0.3,0.1

Type RM Length L Ch R = 1 ,37022   ,283,283,283
BEGIN DESCRIPTION:
PALO AMARILLO CREEK 61.0
END DESCRIPTION:
XS GIS Cut Line= 4
      2191119.62     13184157.76      2190987.57     13183893.65
      2190966.86     13183360.28      2190969.44     13183141.05
#Sta/Elev= 30
  4407.7  455.84  4485.8  452.48  4530.5  451.27  4597.6  446.98  4603.2  447.24
    4620  446.56  4632.3  445.24  4647.9  445.08  4654.7  444.34  4664.7  444.45
  4759.8  440.95  4799.8  440.21  4809.9  440.79  4831.4  440.65  4889.9  439.21
    4970  438.79    4987   437.7  4989.7   437.2    4993   437.7    5050   439.1
  5080.1  439.13  5170.1  440.74  5230.2  443.48    5236  444.32  5250.2  444.19
  5270.2  444.97  5360.2  449.34  5370.2   450.3  5400.2  451.09    5456  454.09
#Mann= 3 ,-1 , 0
  4407.7     .16       0    4987     .07       0    4993     .16       0
#XS Ineff= 2 , 0
         4809.09  440.79
Permanent Ineff=
       F       F
Bank Sta=4987,4993
XS Rating Curve= 0 ,0
Exp/Cntr=0.3,0.1

Type RM Length L Ch R = 1 ,36739   ,166,166,166
BEGIN DESCRIPTION:
PALO AMARILLO CREEK 60.0
END DESCRIPTION:
XS GIS Cut Line= 3
      2191237.72     13184196.85      2191237.72     13183646.85
      2191037.71     13183046.81
#Sta/Elev= 30
    4450  457.24    4490  456.51    4500  455.73    4600  452.06    4710  445.72
    4780  442.78    4790  441.73    4840  439.79    4850  438.79    4900   438.1
    4937  437.17  4939.8  436.67    4943  437.17  4964.6  437.48    4990  437.68
  5002.6   437.2  5042.2  437.99  5147.6  438.54  5221.4  440.81  5295.1  443.25
  5305.7  444.54  5316.2  444.53  5337.3  445.46  5347.9  446.72  5368.9  447.21
  5379.5  448.75  5411.1  449.15  5548.1   455.5  5558.7  455.47  5632.5   458.4
#Mann= 6 ,-1 , 0
    4450     .16       0    4937     .04       0    4943      .1       0
  4964.6     .05       0    4990     .16       0  5221.4     .05       0
Bank Sta=4900,5042.2
XS Rating Curve= 0 ,0
Exp/Cntr=0.3,0.1

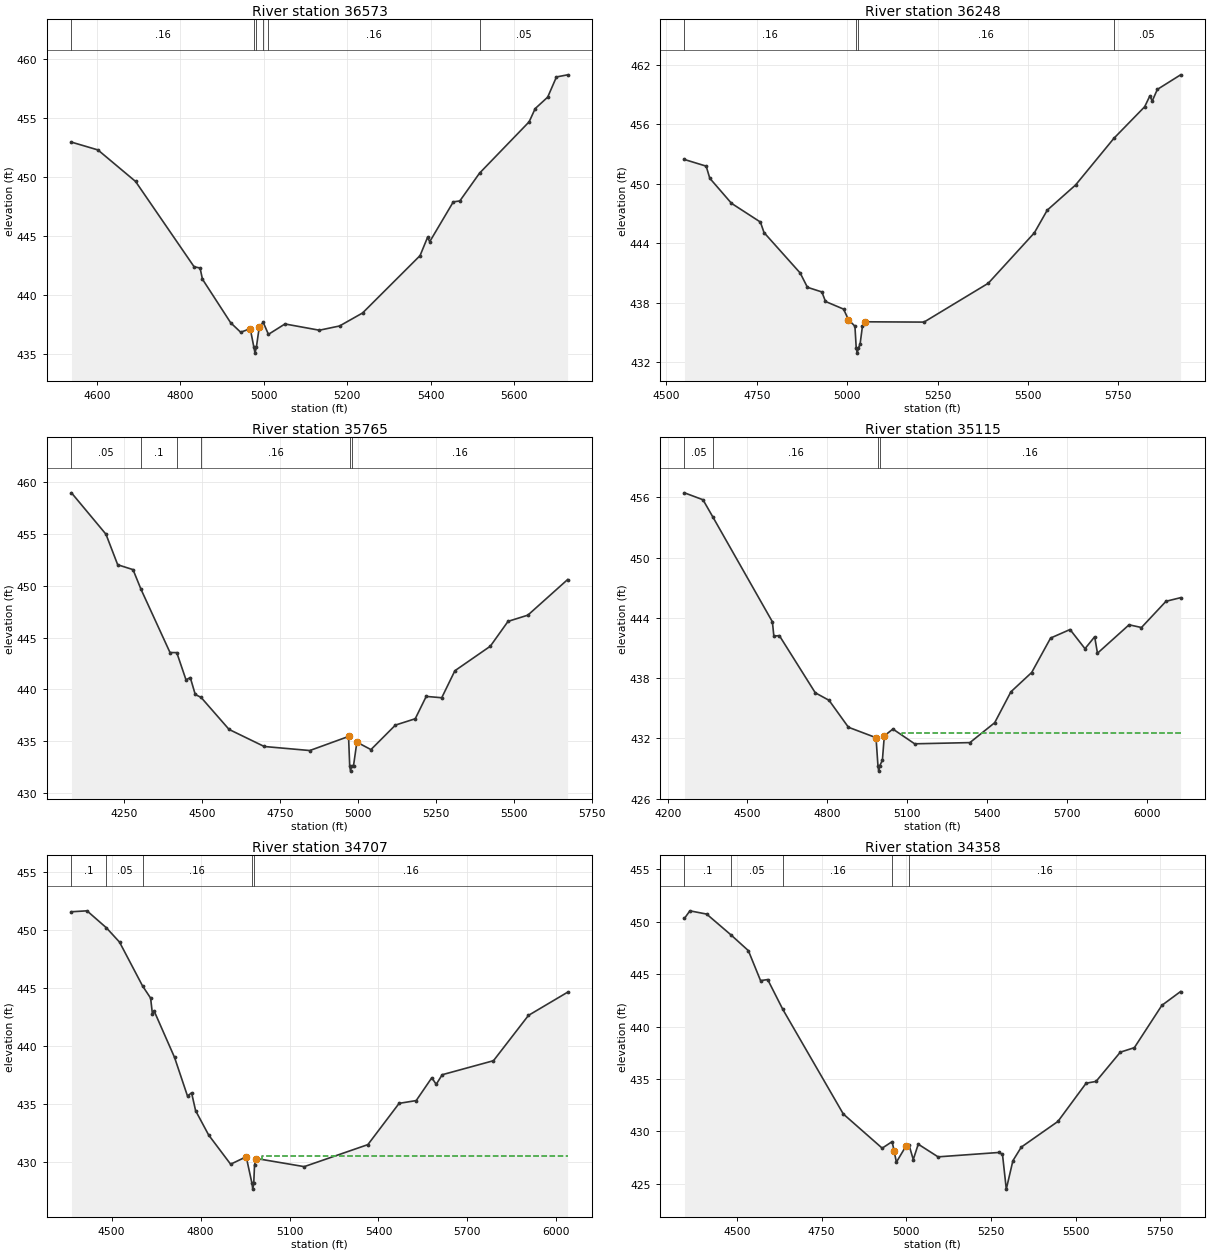
Type RM Length L Ch R = 1 ,36573   ,325,325,325
BEGIN DESCRIPTION:
Mapping XS b3fe83cc
END DESCRIPTION:
XS GIS Cut Line= 5
      2191448.44       13184150.      2191417.37     13183779.73
      2191316.39     13183536.35      2191181.76     13183155.74
      2191097.29     13183030.32
#Sta/Elev= 30
  4538.7  452.92  4602.1  452.26  4692.4  449.59  4832.9  442.36  4847.1  442.26
  4852.9  441.31  4920.6  437.62  4944.5  436.82  4967.5  437.12  4976.2  435.55
  4978.9  435.05  4982.2  435.55  4989.2  437.28  4998.7  437.65  5011.1  436.64
  5050.8  437.52  5133.3  436.99  5181.7  437.35  5236.9  438.45  5374.8  443.31
  5392.7  444.85    5398  444.49  5454.5  447.86  5470.2  447.94  5517.4  450.29
  5636.4  454.64  5650.9  455.76  5680.9  456.73  5701.9  458.44  5728.7  458.62
#Mann= 6 ,-1 , 0
  4538.7     .16       0  4976.2     .04       0  4982.2      .1       0
  4998.7     .05       0  5011.1     .16       0  5517.4     .05       0
Bank Sta=4967.5,4989.2
XS Rating Curve= 0 ,0
Exp/Cntr=0.3,0.1

Type RM Length L Ch R = 1 ,36248   ,483,483,483
BEGIN DESCRIPTION:
PALO AMARILLO CREEK 59.0
END DESCRIPTION:
XS GIS Cut Line= 3
      2191687.72     13184096.85      2191687.72     13183646.85
      2191087.69     13182946.82
#Sta/Elev= 30
    4550  452.46    4610  451.79    4620  450.57    4680  448.04    4760  446.15
    4770  445.09    4870  441.01    4890  439.57    4930   439.1    4940  438.14
    4990  437.37  5003.3  436.32  5021.4  435.64    5025  433.43  5027.7  432.93
    5031  433.43  5035.7  433.85  5042.3  435.69  5049.9  436.09  5212.4  436.06
  5390.2  439.98  5517.5  445.06  5553.2  447.35  5631.6  449.89  5737.6   454.6
  5822.6  457.78  5836.9  458.87  5843.5  458.36  5857.7  459.53    5922     461
#Mann= 4 ,-1 , 0
    4550     .16       0    5025     .07       0    5031     .16       0
  5737.6     .05       0
Bank Sta=5003.3,5049.9
XS Rating Curve= 0 ,0
Exp/Cntr=0.3,0.1

Type RM Length L Ch R = 1 ,35765   ,650,650,650
BEGIN DESCRIPTION:
PALO AMARILLO CREEK 58.0
END DESCRIPTION:
XS GIS Cut Line= 3
      2192487.73     13184196.87      2192037.72     13183396.85
      2191537.71     13182946.84
#Sta/Elev= 30
  4082.1  458.99  4192.7  454.99  4230.3  452.04  4279.4  451.57  4305.3  449.65
    4398  443.56  4419.7  443.55  4449.3  440.92    4463  441.14  4478.9  439.51
  4497.7  439.22  4587.3  436.13  4700.1  434.48  4846.1  434.09  4970.4  435.45
  4974.1   432.6  4976.8   432.1  4980.1   432.6  4986.3  432.62  4997.1   434.9
  5042.2  434.18  5120.7  436.55  5184.2  437.16  5219.4  439.32  5269.1  439.19
  5311.3   441.8  5424.9  444.17  5481.7  446.57  5545.2  447.17  5672.7  450.61
#Mann= 6 ,-1 , 0
  4082.1     .05       0  4305.3      .1       0  4419.7     .05       0
  4497.7     .16       0  4974.1     .07       0  4980.1     .16       0
Bank Sta=4970.4,4997.1
XS Rating Curve= 0 ,0
Exp/Cntr=0.3,0.1

Type RM Length L Ch R = 1 ,35115   ,408,408,408
BEGIN DESCRIPTION:
PALO AMARILLO CREEK 57.0
END DESCRIPTION:
XS GIS Cut Line= 4
      2192840.89     13184200.55      2192549.21     13183148.45
      2192392.96     13183091.16      2191804.47     13182945.33
#Sta/Elev= 30
  4263.2  456.44  4332.8  455.75    4370  454.03  4593.6   443.6  4599.1  442.18
  4619.9  442.22  4754.8  436.53  4806.6  435.78  4879.3   433.1  4983.1  432.06
  4990.4  429.23  4993.2  428.73  4996.4  429.23    5007  429.81  5014.2  432.24
  5046.5  432.92  5128.3  431.45  5335.9  431.57    5429  433.55    5490  436.63
    5568  438.55  5639.1  441.98  5712.2  442.83  5768.4  440.92  5804.7  442.11
  5815.3  440.47    5934   443.3  5980.6  443.03  6072.8  445.64  6127.7     446
#Mann= 4 ,-1 , 0
  4263.2     .05       0    4370     .16       0  4990.4     .07       0
  4996.4     .16       0
#XS Ineff= 2 , 0
       0                 5080.71       0  432.57
Permanent Ineff=
       F       T
Bank Sta=4983.1,5014.2
XS Rating Curve= 0 ,0
Exp/Cntr=0.3,0.1

Type RM Length L Ch R = 1 ,34707   ,349,349,349
BEGIN DESCRIPTION:
PALO AMARILLO CREEK 56.0
END DESCRIPTION:
XS GIS Cut Line= 4
      2193288.78      13183575.5      2193169.01     13183351.57
      2192575.26     13183013.03      2191852.03     13182877.75
#Sta/Elev= 30
  4364.7  451.61  4417.1  451.69  4482.3  450.23  4526.8  448.99  4604.4  445.21
  4631.6  444.16  4637.8  442.77  4643.6  443.04  4712.2  439.05    4756  435.71
  4769.8  435.99  4783.3  434.45  4827.3  432.35  4901.4  429.83    4954  430.47
  4973.4  428.18  4976.1  427.68  4979.4  428.18  4982.1  429.79  4988.5  430.32
  5149.6  429.62  5364.3  431.52  5469.6  435.08  5527.3  435.32  5579.9  437.29
  5594.7  436.72    5615  437.55  5787.9  438.76  5905.9  442.67  6037.9  444.67
#Mann= 5 ,-1 , 0
  4364.7      .1       0  4482.3     .05       0  4604.4     .16       0
  4973.4     .07       0  4979.4     .16       0
#XS Ineff= 2 , 0
                         5007.95          430.58
Permanent Ineff=
       F       F
Bank Sta=4954,4988.5
XS Rating Curve= 0 ,0
Exp/Cntr=0.3,0.1

Type RM Length L Ch R = 1 ,34358   ,462,462,462
BEGIN DESCRIPTION:
PALO AMARILLO CREEK 55.0
END DESCRIPTION:
XS GIS Cut Line= 4
      2193356.53     13183440.15      2193158.59     13183143.24
      2192908.59      13182804.7      2192762.76     13182132.82
#Sta/Elev= 30
  4344.8  450.32  4360.8  451.04  4410.3  450.73  4482.6  448.73  4533.5  447.24
  4569.5  444.38  4590.6  444.48  4635.3  441.63  4813.9  431.65  4928.7  428.39
    4958  429.01  4964.2   428.1  4970.6  427.05  4999.7  428.63  5007.9   428.7
  5020.5   427.3  5035.2  428.77  5093.7  427.56  5273.8  427.98    5284  427.79
  5295.2  424.48  5314.7  427.19  5339.5  428.49  5447.7  430.94    5531  434.59
  5560.3  434.76  5631.9  437.55  5673.4  437.98  5754.7  442.02    5810  443.34
#Mann= 5 ,-1 , 0
  4344.8      .1       0  4482.6     .05       0  4635.3     .16       0
    4958     .07       0  5007.9     .16       0
#XS Ineff= 2 , 0
       0                 5035.27       0  428.75
Permanent Ineff=
       F       T
Bank Sta=4964.2,4999.7
XS Rating Curve= 0 ,0
Exp/Cntr=0.3,0.1

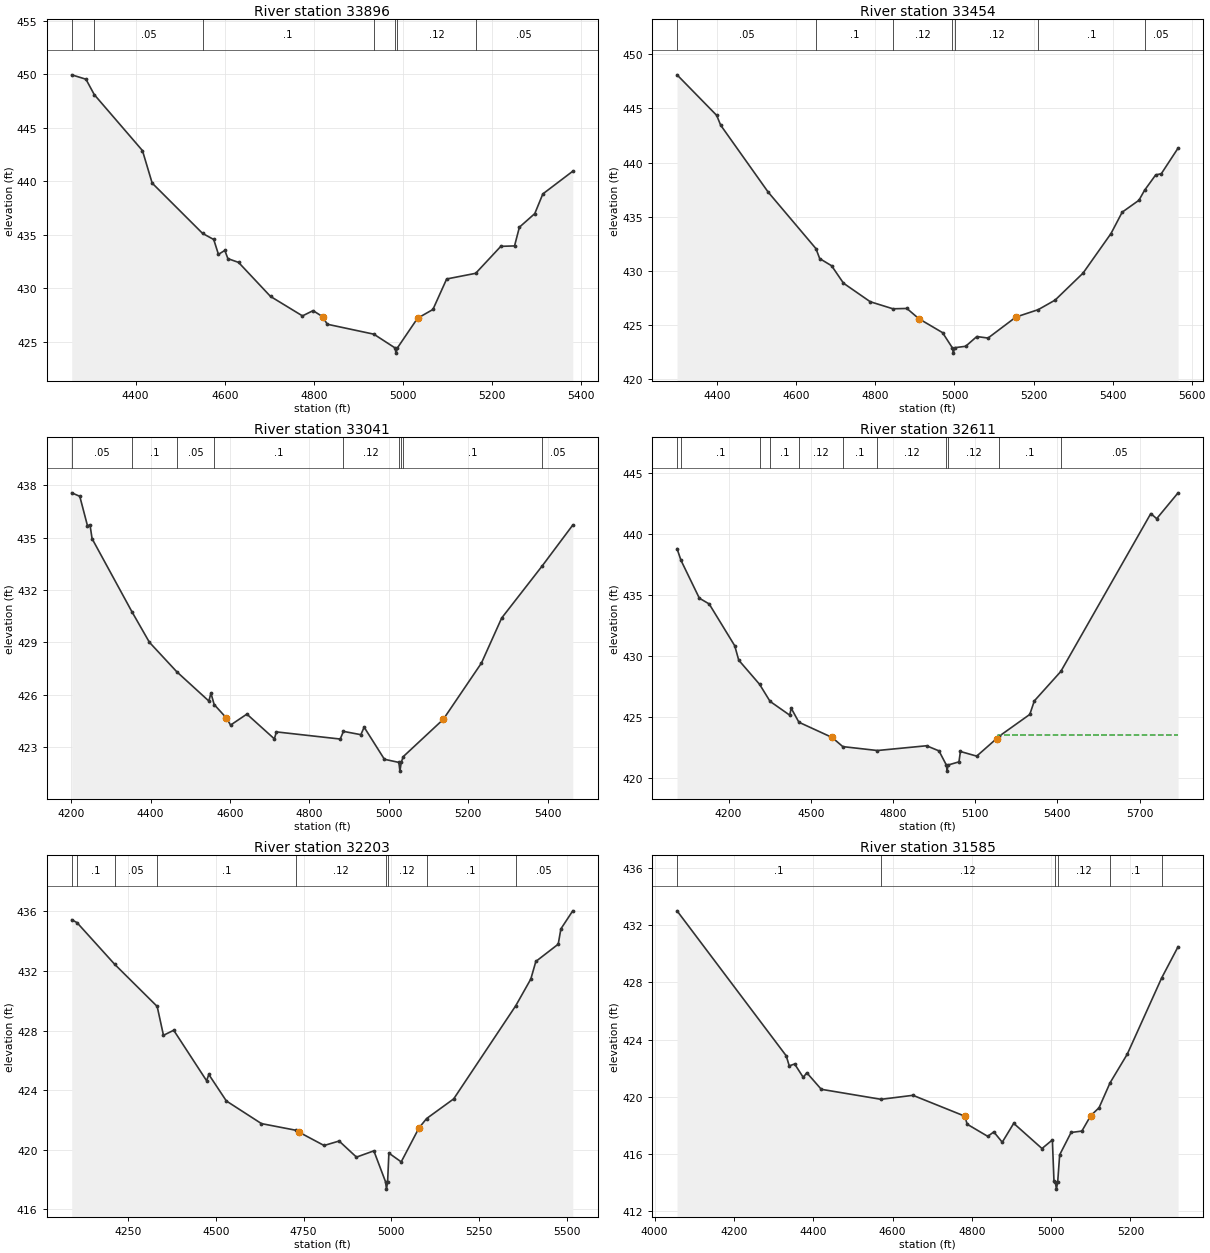
Type RM Length L Ch R = 1 ,33896   ,442,442,442
BEGIN DESCRIPTION:
PALO AMARILLO CREEK 54.0
END DESCRIPTION:
XS GIS Cut Line= 3
      2193387.72     13183246.85      2193137.72     13182546.85
      2192987.72     13182196.84
#Sta/Elev= 30
  4256.7  449.93  4288.6  449.52  4307.3  448.08  4415.4  442.85  4437.2  439.81
  4550.3  435.11  4575.3  434.54  4585.9  433.15  4600.2  433.52  4607.1  432.75
    4631   432.4  4702.7  429.22  4774.4   427.4  4798.2  427.89  4819.5  427.33
  4830.1  426.62  4934.6  425.69  4981.6  424.42  4984.4  423.92  4987.6  424.42
  5032.6  427.18  5067.1     428  5097.9  430.85    5163  431.38  5219.4   433.9
  5250.2  433.94  5261.1  435.69  5295.6  436.96  5313.7   438.8  5380.8  440.92
#Mann= 7 ,-1 , 0
  4256.7      .1       0  4307.3     .05       0  4550.3      .1       0
  4934.6     .12       0  4981.6     .07       0  4987.6     .12       0
    5163     .05       0
Bank Sta=4819.5,5032.6
XS Rating Curve= 0 ,0
Exp/Cntr=0.3,0.1

Type RM Length L Ch R = 1 ,33454   ,413,413,413
BEGIN DESCRIPTION:
PALO AMARILLO CREEK 53.0
END DESCRIPTION:
XS GIS Cut Line= 3
      2193487.72     13183146.87      2193537.72     13182446.85
      2193137.71     13182046.84
#Sta/Elev= 30
  4298.2   448.1  4398.5  444.36  4408.5  443.46  4528.8  437.28  4649.6  432.07
  4659.1  431.15  4689.2  430.49  4719.3  428.88    4787  427.17  4844.3  426.52
  4879.7  426.55  4909.8  425.61  4969.9  424.32  4994.5  422.93  4997.2  422.43
  5000.5  422.93  5028.3  423.06  5056.6  423.96  5084.9  423.82  5155.6  425.76
  5211.9  426.44  5254.6  427.32  5325.3  429.81    5396  433.46  5424.3  435.43
  5466.7  436.53  5480.9  437.45  5509.1  438.87  5523.3  438.98  5565.7  441.34
#Mann= 7 ,-1 , 0
  4298.2     .05       0  4649.6      .1       0  4844.3     .12       0
  4994.5     .07       0  5000.5     .12       0  5211.9      .1       0
  5480.9     .05       0
Bank Sta=4909.8,5155.6
XS Rating Curve= 0 ,0
Exp/Cntr=0.3,0.1

Type RM Length L Ch R = 1 ,33041   ,430,430,430
BEGIN DESCRIPTION:
PALO AMARILLO CREEK 52.0
END DESCRIPTION:
XS GIS Cut Line= 3
      2193777.11     13183014.28      2193912.52     13182628.89
       2193751.2     13181791.07
#Sta/Elev= 30
  4201.4  437.57  4221.7  437.37  4241.1  435.68  4247.4  435.74  4252.7  434.94
  4352.8  430.76    4397     429  4465.9  427.31  4546.7  425.63    4552  426.08
  4560.1  425.43  4590.8  424.66  4601.4  424.25  4642.5  424.88  4711.7  423.46
  4716.8  423.86  4877.6  423.45  4885.6  423.89  4929.5   423.7  4937.8  424.13
  4988.8  422.29  5025.2  422.11  5027.9  421.61  5031.2  422.11  5036.2  422.44
  5137.1  424.58  5233.2  427.81  5284.1  430.39  5385.9  433.37  5463.1  435.72
#Mann= 9 ,-1 , 0
  4201.4     .05       0  4352.8      .1       0  4465.9     .05       0
  4560.1      .1       0  4885.6     .12       0  5025.2     .07       0
  5031.2     .12       0  5036.2      .1       0  5385.9     .05       0
Bank Sta=4590.8,5137.1
XS Rating Curve= 0 ,0
Exp/Cntr=0.3,0.1

Type RM Length L Ch R = 1 ,32611   ,408,408,408
BEGIN DESCRIPTION:
Mapping XS ddc3bcc3
END DESCRIPTION:
XS GIS Cut Line= 3
      2193850.02     13183092.44       2194402.1     13181707.02
      2194527.12     13181394.47
#Sta/Elev= 30
  4012.2  438.83  4026.7  437.87  4093.6  434.77  4129.4   434.3  4222.7  430.87
  4237.3  429.69  4313.3  427.71  4351.6  426.31  4423.3  425.18  4428.7  425.75
  4456.8   424.6    4578  423.35    4617   422.6  4743.2  422.28  4922.5  422.67
  4967.9  422.25  4994.8  421.09  4997.6  420.59  5000.8  421.09  5040.8  421.35
  5046.1   422.2  5105.5  421.82  5178.3  423.26  5186.1  423.43  5299.2  425.24
  5315.8  426.35  5412.3  428.76  5740.7  441.71  5762.2  441.29  5840.2  443.41
#Mann= 11 ,-1 , 0
  4012.2     .05       0  4026.7      .1       0  4313.3     .05       0
  4351.6      .1       0  4456.8     .12       0    4617      .1       0
  4743.2     .12       0  4994.8     .07       0  5000.8     .12       0
  5186.1      .1       0  5412.3     .05       0
#XS Ineff= 2 , 0
                         5183.96          423.54
Permanent Ineff=
       F       F
Bank Sta=4578,5178.3
XS Rating Curve= 0 ,0
Exp/Cntr=0.3,0.1

Type RM Length L Ch R = 1 ,32203   ,618,618,618
BEGIN DESCRIPTION:
PALO AMARILLO CREEK 51.0
END DESCRIPTION:
XS GIS Cut Line= 3
      2193988.92     13183075.06      2194388.19     13182545.58
      2194882.83     13181964.17
#Sta/Elev= 30
  4089.8  435.44  4104.8  435.25  4212.1  432.45  4333.1  429.62    4351  427.68
  4380.2  428.02  4473.8  424.63  4480.1  425.05  4530.1  423.27    4630  421.75
  4728.9   421.3  4738.2  421.16  4808.3  420.28  4851.1  420.58  4900.5   419.5
    4950  419.92  4983.2  417.85    4986  417.35  4989.2  417.85  4992.8  419.77
  5027.9  419.18  5078.5  421.46  5100.2  422.09  5177.3  423.41  5354.1  429.67
  5396.9  431.46  5411.2  432.64  5474.9   433.8  5482.6  434.83  5516.3  436.04
#Mann= 9 ,-1 , 0
  4089.8     .05       0  4104.8      .1       0  4212.1     .05       0
  4333.1      .1       0  4728.9     .12       0  4983.2     .07       0
  4989.2     .12       0  5100.2      .1       0  5354.1     .05       0
Bank Sta=4738.2,5078.5
XS Rating Curve= 0 ,0
Exp/Cntr=0.3,0.1

Type RM Length L Ch R = 1 ,31585   ,566,566,566
BEGIN DESCRIPTION:
PALO AMARILLO CREEK 50.0
END DESCRIPTION:
XS GIS Cut Line= 3
      2194287.72     13183046.86      2195087.72     13182546.85
      2195287.75     13182296.82
#Sta/Elev= 30
  4056.6  433.01    4332  422.87  4339.6  422.17  4353.2   422.3    4375  421.36
  4383.8  421.69  4420.4  420.53  4571.1  419.83  4651.5  420.11  4782.4  418.65
  4788.3  418.09  4840.2  417.24  4855.5  417.55  4876.8  416.83  4905.7  418.15
    4977  416.39  5003.2  416.99  5007.2  414.14  5010.6  414.05  5013.4  413.55
  5016.6  414.05  5021.6  415.95  5050.4  417.51  5077.6  417.61    5100  418.69
  5120.9  419.24  5148.6  420.98  5192.1  422.99  5278.7  428.31  5320.2   430.5
#Mann= 6 ,-1 , 0
  4056.6      .1       0  4571.1     .12       0  5010.6     .07       0
  5016.6     .12       0  5148.6      .1       0  5278.7     .05       0
Bank Sta=4782.4,5100
XS Rating Curve= 0 ,0
Exp/Cntr=0.3,0.1

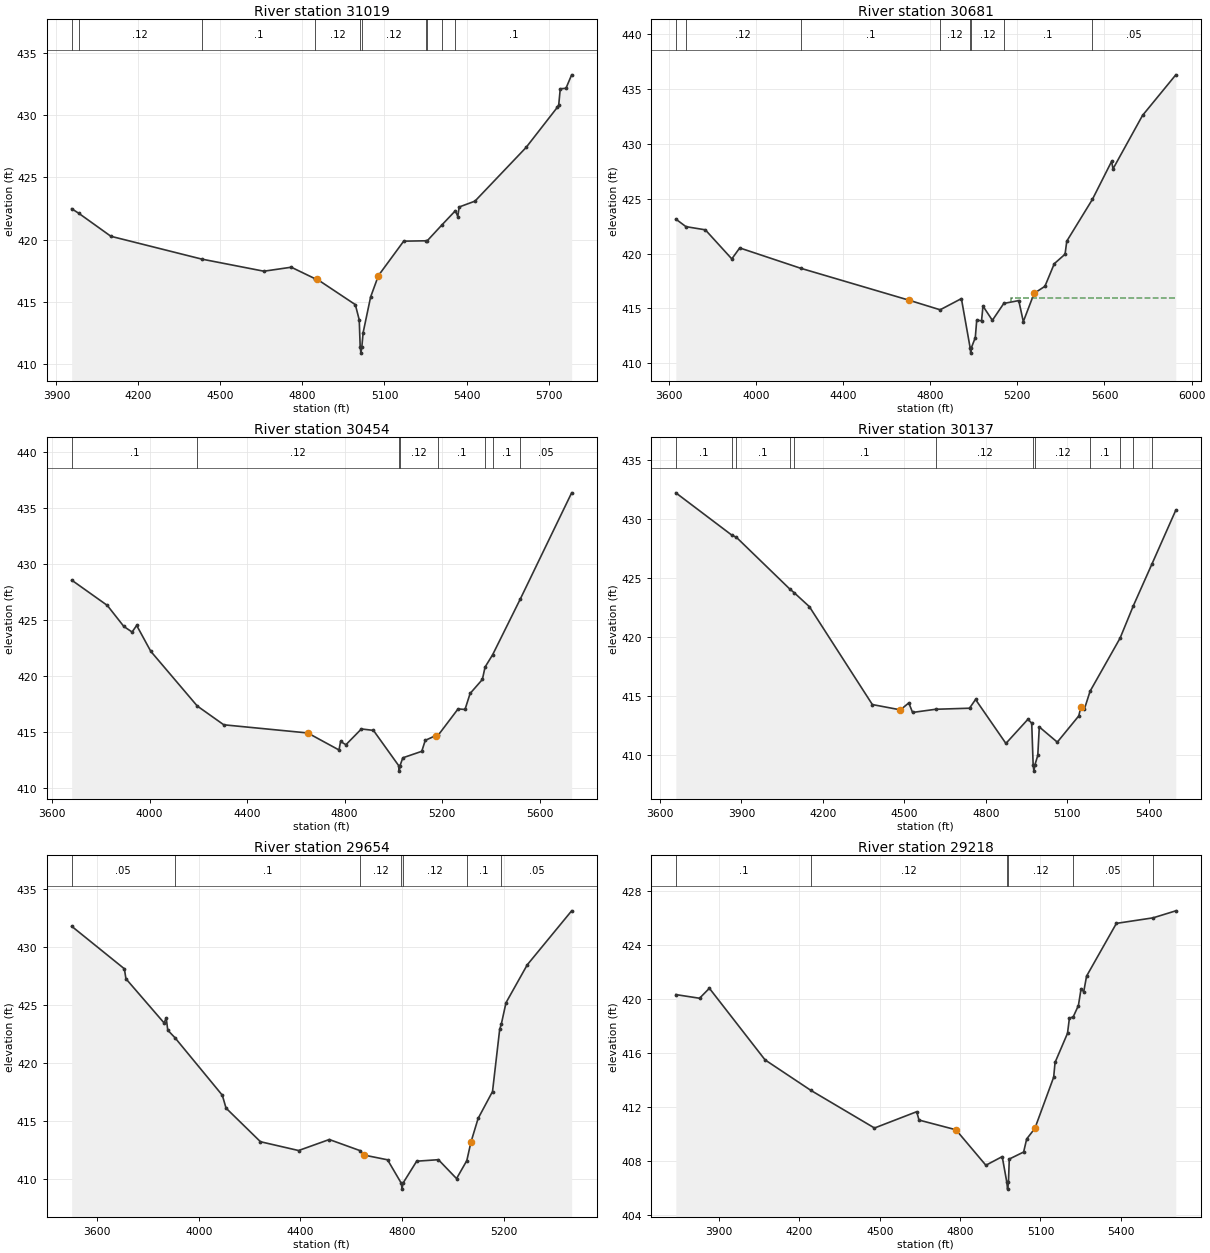
Type RM Length L Ch R = 1 ,31019   ,338,338,338
BEGIN DESCRIPTION:
Mapping XS 9a59b365
END DESCRIPTION:
XS GIS Cut Line= 4
      2194646.94     13183238.25      2195094.81     13183123.68
      2195735.44     13182587.22      2195589.61     13182076.82
#Sta/Elev= 30
  3955.8  422.49  3981.5  422.13  4099.3  420.28  4431.8  418.45  4658.9  417.48
    4759   417.8  4846.9  416.87  4851.4  416.87  4993.3   414.8  5007.6  413.58
  5011.1  411.41  5013.8  410.91  5017.1  411.41  5021.9  412.56  5049.2  415.41
  5077.8  417.13  5170.2  419.89  5252.6  419.92  5256.3  419.92  5309.5  421.18
  5359.6  422.34    5368  421.86  5373.2  422.63  5430.9   423.1  5618.1  427.41
    5732  430.62  5737.2  430.81  5742.9  432.11  5763.7  432.15  5784.5  433.23
#Mann= 10 ,-1 , 0
  3955.8      .1       0  3981.5     .12       0  4431.8      .1       0
  4846.9     .12       0  5011.1     .07       0  5017.1     .12       0
  5252.6      .1       0  5256.3     .12       0  5309.5     .05       0
  5359.6      .1       0
Bank Sta=4851.4,5077.8
XS Rating Curve= 0 ,0
Exp/Cntr=0.3,0.1

Type RM Length L Ch R = 1 ,30681   ,227,227,227
BEGIN DESCRIPTION:
PALO AMARILLO CREEK 49.0
END DESCRIPTION:
XS GIS Cut Line= 4
      2194573.97     13183347.64      2195433.35     13183212.22
      2196188.56     13182592.43      2196532.29     13182305.99
#Sta/Elev= 30
  3632.9  423.15  3679.3  422.46  3768.3  422.17  3889.8  419.52  3926.1  420.52
  4205.3  418.67  4702.2  415.76  4845.8  414.88  4943.4   415.9  4983.4  411.43
  4986.2  410.93  4989.4  411.43  5007.2  412.35  5013.7  413.93  5035.9  413.88
  5042.4  415.22  5085.5  413.92  5137.9  415.46  5206.7  415.72  5227.5   413.8
  5277.1  416.38  5326.6  417.02  5369.6  419.08  5419.1  419.95    5427  421.14
  5544.4  424.94  5632.7  428.41  5639.2  427.73  5774.6   432.6  5927.3   436.3
#Mann= 8 ,-1 , 0
  3632.9      .1       0  3679.3     .12       0  4205.3      .1       0
  4845.8     .12       0  4983.4     .07       0  4989.4     .12       0
  5137.9      .1       0  5544.4     .05       0
#XS Ineff= 2 , 0
                         5169.98          415.96
Permanent Ineff=
       F       F
Bank Sta=4702.2,5277.1
XS Rating Curve= 0 ,0
Exp/Cntr=0.3,0.1

Type RM Length L Ch R = 1 ,30454   ,317,317,317
BEGIN DESCRIPTION:
PALO AMARILLO CREEK 48.0
END DESCRIPTION:
XS GIS Cut Line= 3
      2195553.14     13184170.57      2195725.02     13183248.68
      2196563.17     13182514.65
#Sta/Elev= 30
    3680  428.59  3826.2  426.33  3894.1  424.45  3927.9  423.95  3946.8  424.54
  4004.6  422.23  4195.4  417.34  4304.3  415.66  4648.9  414.93  4777.1  413.41
  4783.7  414.17  4805.5  413.88  4869.1  415.29  4918.5  415.16  5021.8  412.02
  5024.5  411.52  5027.8  412.02    5039  412.71  5116.8  413.29  5131.1  414.27
  5173.8  414.69  5185.2  414.76  5265.8  417.08  5294.3  417.03  5315.2  418.46
  5365.5  419.71  5376.6  420.82  5407.6  421.92  5521.6  426.92  5731.9  436.39
#Mann= 8 ,-1 , 0
    3680      .1       0  4195.4     .12       0  5021.8     .07       0
  5027.8     .12       0  5185.2      .1       0  5376.6     .05       0
  5407.6      .1       0  5521.6     .05       0
Bank Sta=4648.9,5173.8
XS Rating Curve= 0 ,0
Exp/Cntr=0.3,0.1

Type RM Length L Ch R = 1 ,30137   ,483,483,483
BEGIN DESCRIPTION:
PALO AMARILLO CREEK 47.0
END DESCRIPTION:
XS GIS Cut Line= 3
      2195687.74     13184296.82      2196287.72     13183096.85
      2196587.72     13182696.85
#Sta/Elev= 30
  3658.4  432.24  3864.6  428.65  3881.3  428.47  4077.5  424.09  4093.5  423.78
  4150.3  422.58  4382.3  414.27  4485.7  413.82  4516.5  414.41  4530.4   413.6
  4615.4  413.87  4740.1  413.96  4762.4   414.7  4874.2  410.97  4955.3  413.02
  4969.3  412.69  4974.6  409.12  4977.4  408.62  4980.6  409.12  4991.6  409.95
  4997.2  412.37  5063.5  411.08  5142.7  413.31    5150  414.04  5163.5   413.9
  5184.2   415.4  5294.8  419.91  5343.7  422.66  5412.7  426.23    5500  430.77
#Mann= 12 ,-1 , 0
  3658.4      .1       0  3864.6     .05       0  3881.3      .1       0
  4077.5     .05       0  4093.5      .1       0  4615.4     .12       0
  4974.6     .07       0  4980.6     .12       0  5184.2      .1       0
  5294.8     .05       0  5343.7      .1       0  5412.7     .05       0
Bank Sta=4485.7,5150
XS Rating Curve= 0 ,0
Exp/Cntr=0.3,0.1

Type RM Length L Ch R = 1 ,29654   ,436,436,436
BEGIN DESCRIPTION:
PALO AMARILLO CREEK 46.0
END DESCRIPTION:
XS GIS Cut Line= 4
      2195787.72     13184296.85      2196687.72     13183096.85
      2196837.72     13182946.85      2196848.83     13182692.33
#Sta/Elev= 30
    3500  431.83  3707.3  428.16  3713.5   427.3  3863.5  423.49  3871.9  423.91
  3878.1  422.86  3906.1  422.22  4092.7  417.25  4107.3  416.14  4242.7  413.24
  4392.7  412.48  4513.5  413.43  4634.7  412.47    4650  412.09  4742.7  411.68
    4797  409.65  4799.8  409.15    4803  409.65  4857.3  411.56  4942.7  411.69
  5014.1  410.06  5054.5  411.61  5070.7   413.2    5099  415.25  5155.6  417.57
  5183.8  422.93  5190.2  423.38  5208.6  425.23  5292.2   428.5  5466.9  433.16
#Mann= 7 ,-1 , 0
    3500     .05       0  3906.1      .1       0  4634.7     .12       0
    4797     .07       0    4803     .12       0  5054.5      .1       0
  5190.2     .05       0
Bank Sta=4650,5070.7
XS Rating Curve= 0 ,0
Exp/Cntr=0.3,0.1

Type RM Length L Ch R = 1 ,29218   ,421,421,421
BEGIN DESCRIPTION:
PALO AMARILLO CREEK 45.0
END DESCRIPTION:
XS GIS Cut Line= 4
      2196376.25     13184469.27      2196918.81     13183698.84
      2197038.16     13183036.95      2197062.37     13182786.08
#Sta/Elev= 30
  3738.4  420.33    3827  420.06  3863.7   420.8  4071.6  415.49  4242.7  413.23
  4480.2  410.44  4637.9  411.65  4646.4  411.03  4784.3  410.31  4896.1  407.68
  4957.1  408.32  4974.4  406.41  4977.1  405.91  4980.4  406.41  4983.5  408.14
  5037.1  408.66  5048.5  409.63    5079  410.41  5149.3  414.21  5154.4   415.3
  5200.9  417.46    5208  418.58  5222.2  418.68  5241.6  419.52  5251.7  420.77
  5261.5  420.54  5272.1   421.7  5383.5  425.61  5520.4  426.02  5605.3  426.54
#Mann= 6 ,-1 , 0
  3738.4      .1       0  4242.7     .12       0  4974.4     .07       0
  4980.4     .12       0  5222.2     .05       0  5520.4      .1       0
Bank Sta=4784.3,5079
XS Rating Curve= 0 ,0
Exp/Cntr=0.3,0.1

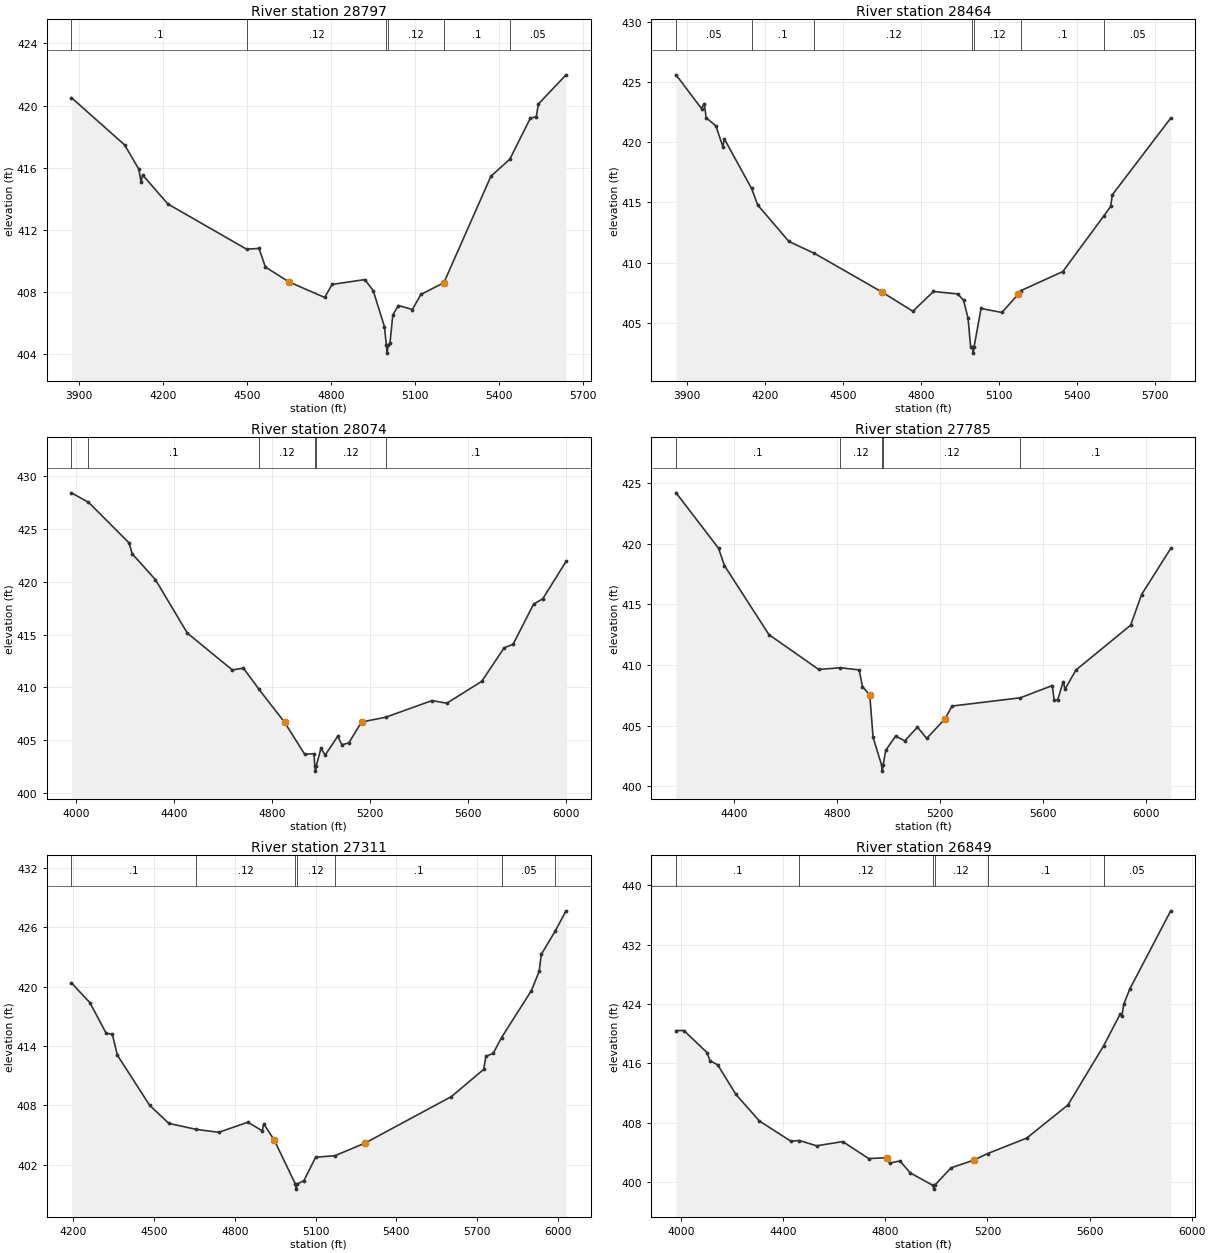
Type RM Length L Ch R = 1 ,28797   ,333,333,333
BEGIN DESCRIPTION:
PALO AMARILLO CREEK 44.0
END DESCRIPTION:
XS GIS Cut Line= 4
      2197005.08     13184655.87      2197312.37     13183707.97
       2197333.2     13183150.68      2197173.29      13183011.4
#Sta/Elev= 30
  3871.9  420.51  4062.1  417.46  4112.6   415.9  4120.8  415.06    4126  415.53
  4216.7  413.65  4497.6  410.74  4541.8  410.79  4564.7  409.59  4648.8  408.63
  4776.2  407.63  4802.9  408.47  4919.5  408.78  4949.5  408.07  4989.6  405.75
  4996.6  404.54  4999.3  404.04  5002.6  404.54  5009.6  404.71  5019.6  406.51
  5039.6  407.11  5089.6  406.85  5119.6  407.82  5201.9  408.58  5369.8  415.44
  5437.2  416.54  5510.9  419.19  5531.8  419.28  5539.4   420.1  5638.1  421.98
#Mann= 6 ,-1 , 0
  3871.9      .1       0  4497.6     .12       0  4996.6     .07       0
  5002.6     .12       0  5201.9      .1       0  5437.2     .05       0
Bank Sta=4648.8,5201.9
XS Rating Curve= 0 ,0
Exp/Cntr=0.3,0.1

Type RM Length L Ch R = 1 ,28464   ,390,390,390
BEGIN DESCRIPTION:
Mapping XS 1275ef7d
END DESCRIPTION:
XS GIS Cut Line= 5
      2197307.17     13184640.23      2197624.87     13183640.26
      2197614.45     13183379.84      2197343.62     13183077.76
      2197182.47     13182984.19
#Sta/Elev= 30
  3857.3  425.58  3955.3  422.78  3965.8   423.2  3972.9  422.03  4010.4  421.34
  4037.4  419.62  4042.6  420.28  4147.7  416.16  4171.6  414.78    4291  411.77
  4389.3  410.78  4647.8  407.59  4767.9  405.98  4847.1  407.62    4940  407.42
  4962.6   406.9    4980  405.41    4990  403.02    4997  403.01  4999.8  402.51
    5003  403.01    5030  406.21  5110.1  405.88  5173.8  407.41  5183.1  407.69
  5344.3  409.27  5502.9  413.91  5528.2  414.67  5534.9  415.64  5759.2  421.99
#Mann= 7 ,-1 , 0
  3857.3     .05       0  4147.7      .1       0  4389.3     .12       0
    4997     .07       0    5003     .12       0  5183.1      .1       0
  5502.9     .05       0
Bank Sta=4647.8,5173.8
XS Rating Curve= 0 ,0
Exp/Cntr=0.3,0.1

Type RM Length L Ch R = 1 ,28074   ,289,289,289
BEGIN DESCRIPTION:
PALO AMARILLO CREEK 43.0
END DESCRIPTION:
XS GIS Cut Line= 4
      2198384.57     13184435.83      2198047.76      13183619.3
      2197894.66     13183292.69      2197191.57     13182966.62
#Sta/Elev= 30
  3981.5  428.43  4051.2  427.54  4217.7  423.67  4229.2  422.67  4324.2  420.22
  4454.7  415.15  4638.4  411.66  4683.5  411.83  4747.8  409.81  4851.5  406.71
  4933.7  403.68  4971.6  403.73  4974.9  402.58  4977.7  402.08  4980.9  402.58
    5000  404.23  5017.3   403.6  5068.5  405.38  5085.8  404.57  5114.1  404.76
  5165.7  406.73  5263.8  407.18  5453.6  408.76  5513.5  408.51  5656.4  410.58
    5748  413.76  5784.3  414.09  5868.1  417.89  5905.5   418.4  6000.5  421.93
#Mann= 6 ,-1 , 0
  3981.5     .05       0  4051.2      .1       0  4747.8     .12       0
  4974.9     .07       0  4980.9     .12       0  5263.8      .1       0
Bank Sta=4851.5,5165.7
XS Rating Curve= 0 ,0
Exp/Cntr=0.3,0.1

Type RM Length L Ch R = 1 ,27785   ,474,474,474
BEGIN DESCRIPTION:
PALO AMARILLO CREEK 42.0
END DESCRIPTION:
XS GIS Cut Line= 3
      2198437.72     13184196.83      2198237.72     13183396.85
      2197487.71     13182596.84
#Sta/Elev= 30
  4175.4  424.21  4340.3  419.64  4363.5   418.2  4536.2  412.51  4729.4  409.64
  4813.8  409.78  4886.6   409.6  4899.5  408.23  4927.8  407.52  4940.7  404.03
  4973.8  401.75  4976.6  401.25  4979.8  401.75  4989.7  402.97  5028.1  404.14
  5063.7  403.75  5113.1  404.88  5148.7  403.95  5219.3  405.54  5247.4  406.62
  5512.4   407.3  5636.7  408.31    5644  407.08    5658  407.15  5679.2  408.64
  5686.1  408.01  5728.5  409.59    5941  413.29  5983.5  415.82  6096.6  419.62
#Mann= 5 ,-1 , 0
  4175.4      .1       0  4813.8     .12       0  4973.8     .07       0
  4979.8     .12       0  5512.4      .1       0
Bank Sta=4927.8,5219.3
XS Rating Curve= 0 ,0
Exp/Cntr=0.3,0.1

Type RM Length L Ch R = 1 ,27311   ,462,462,462
BEGIN DESCRIPTION:
PALO AMARILLO CREEK 41.0
END DESCRIPTION:
XS GIS Cut Line= 3
      2198837.73     13183796.88      2198537.72     13183046.85
      2197887.71     13182246.84
#Sta/Elev= 30
  4192.2  420.38  4260.9  418.39  4321.5  415.29  4344.4  415.19  4363.2  413.08
    4483  408.02  4554.4  406.19  4657.1  405.58  4740.2  405.29  4847.9  406.31
  4901.7  405.44  4907.1  406.14  4946.1  404.51    5025  400.05  5027.7  399.55
    5031  400.05  5056.7  400.42  5099.9  402.77    5172  402.93  5283.7   404.2
  5604.8   408.9  5724.8  411.65  5732.7  412.96  5760.2  413.27  5791.1  414.86
  5902.2  419.61  5930.9  421.55  5938.8  423.26  5990.4  425.61  6030.8  427.66
#Mann= 7 ,-1 , 0
  4192.2      .1       0  4657.1     .12       0    5025     .07       0
    5031     .12       0    5172      .1       0  5791.1     .05       0
  5990.4      .1       0
Bank Sta=4946.1,5283.7
XS Rating Curve= 0 ,0
Exp/Cntr=0.3,0.1

Type RM Length L Ch R = 1 ,26849   ,463,463,463
BEGIN DESCRIPTION:
PALO AMARILLO CREEK 40.0
END DESCRIPTION:
XS GIS Cut Line= 3
      2198987.72     13183746.85      2198787.72     13182746.85
      2198337.71     13181946.84
#Sta/Elev= 30
  3980.2  420.42  4010.8  420.44  4102.6  417.43  4112.8  416.37  4143.4  415.81
  4214.8  411.82  4306.5  408.25  4428.9  405.54  4463.7  405.61  4530.9   404.9
  4632.9  405.47  4734.9  403.18  4806.2   403.3  4816.4  402.57  4857.2  402.86
    4898  401.24  4986.8  399.56  4989.6  399.06  4992.8  399.56  5057.4  401.93
  5148.2  402.99  5200.3  403.85  5353.4  405.93  5515.3   410.4  5654.8  418.36
  5720.6  422.69  5726.3  422.33  5734.3     424  5757.2     426  5917.9  436.57
#Mann= 6 ,-1 , 0
  3980.2      .1       0  4463.7     .12       0  4986.8     .07       0
  4992.8     .12       0  5200.3      .1       0  5654.8     .05       0
Bank Sta=4806.2,5148.2
XS Rating Curve= 0 ,0
Exp/Cntr=0.3,0.1