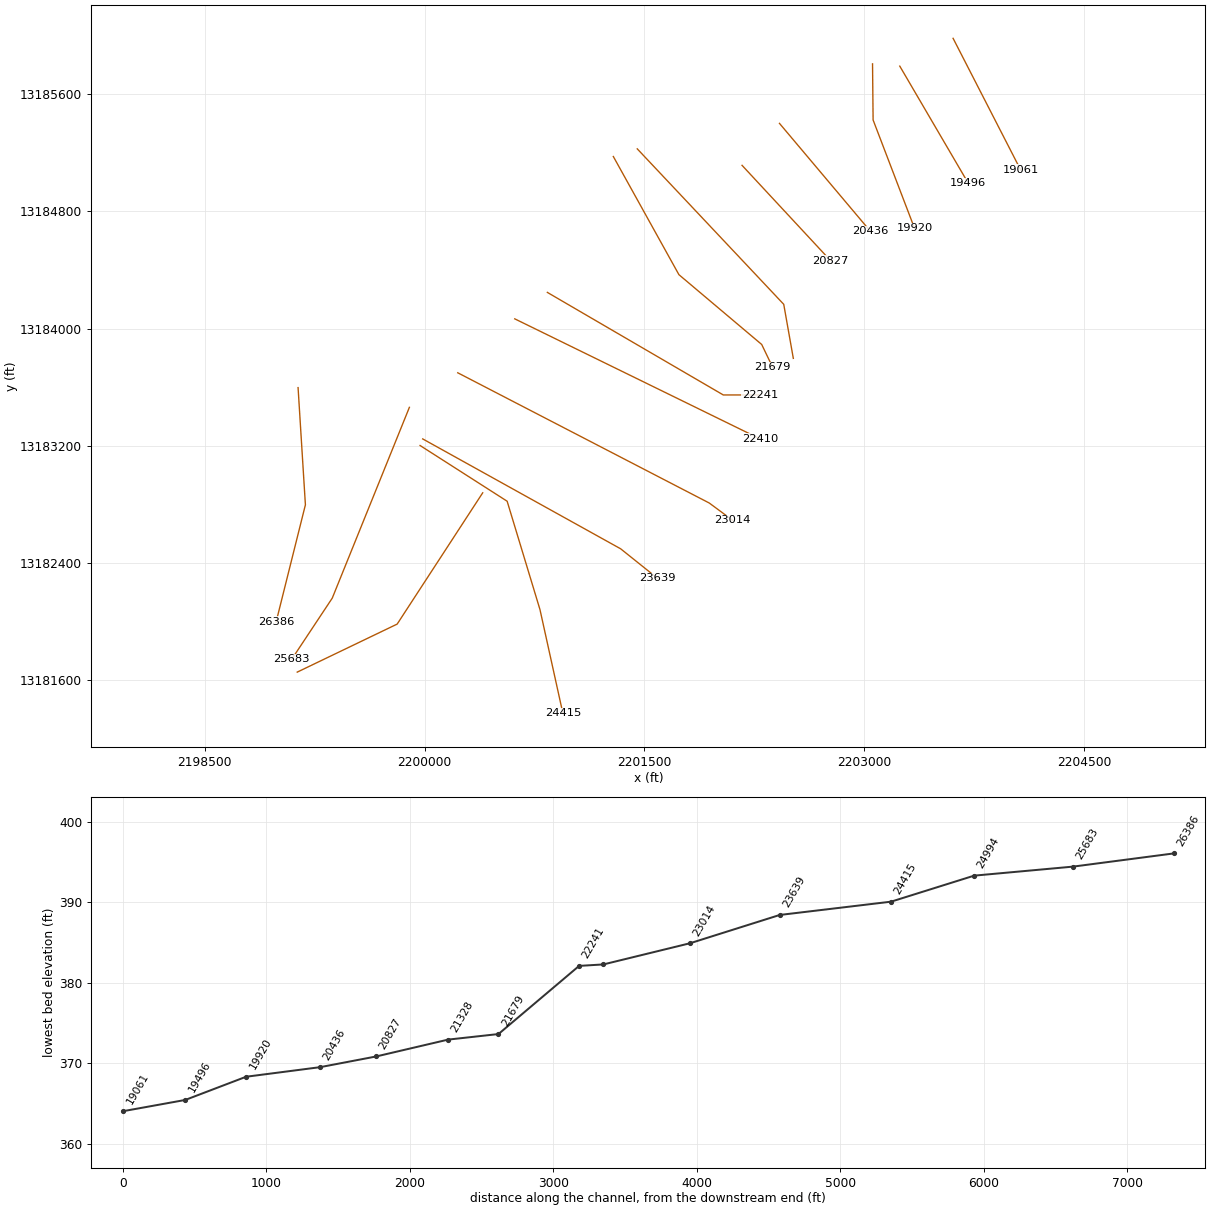
HEC-RAS study PALO AMARILLO CREEK.prj: PALO AMARILLO CREEK Base Level Engineering

--- PALO AMARILLO CREEK.g01 (geometry) --- (continued)

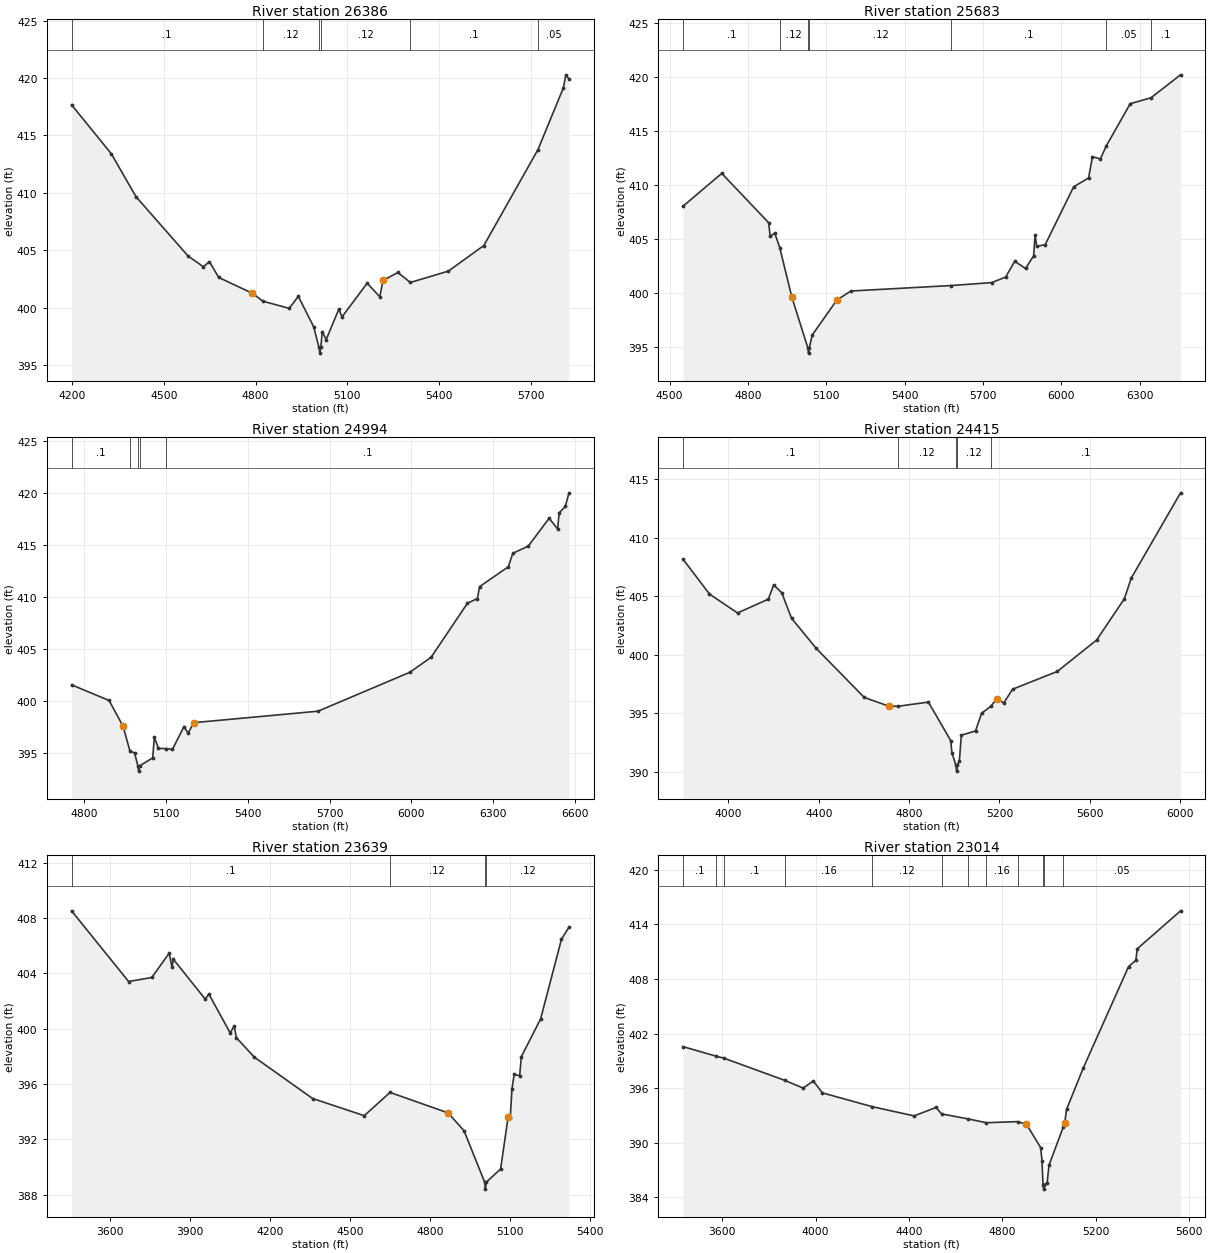
Type RM Length L Ch R = 1 ,26386   ,703,703,703
BEGIN DESCRIPTION:
PALO AMARILLO CREEK 39.0
END DESCRIPTION:
XS GIS Cut Line= 3
      2199137.72     13183596.89      2199187.72     13182796.86
      2198987.73     13181996.88
#Sta/Elev= 30
  4198.4  417.67  4328.7   413.4  4408.8  409.68  4579.2  404.51  4629.3  403.57
  4649.3  404.01  4679.4  402.64  4789.6  401.26  4824.1  400.57  4909.8  399.95
  4939.9  400.99    4990  398.34  5007.3  396.55  5010.1  396.05  5013.3  396.55
    5018  397.93  5030.9  397.23  5072.2  399.88  5082.5   399.2  5164.9  402.14
  5206.2  400.95  5216.5  402.38  5265.4  403.07    5306   402.2  5430.3  403.19
  5546.3  405.42    5723  413.76  5806.6  419.17  5814.3  420.28  5824.6  419.92
#Mann= 6 ,-1 , 0
  4198.4      .1       0  4824.1     .12       0  5007.3     .07       0
  5013.3     .12       0    5306      .1       0    5723     .05       0
Bank Sta=4789.6,5216.5
XS Rating Curve= 0 ,0
Exp/Cntr=0.3,0.1

Type RM Length L Ch R = 1 ,25683   ,689,689,689
BEGIN DESCRIPTION:
Mapping XS f7941728
END DESCRIPTION:
XS GIS Cut Line= 3
       2199896.9     13183462.24      2199370.85     13182160.14
      2199094.79     13181743.44
#Sta/Elev= 30
    4552  408.04    4700  411.08  4879.7   406.5  4885.1  405.24  4902.9  405.54
  4922.1  404.19  4968.3   399.6  5029.4  394.91  5032.1  394.41  5035.4  394.91
  5046.1  396.08  5140.2  399.32  5194.1  400.17    5579  400.68  5732.9  400.95
  5786.6  401.46  5821.5  402.93  5862.8  402.26  5893.9  403.44  5899.3  405.35
    5906   404.3  5938.3  404.48  6046.9  409.83  6104.2  410.66  6119.1  412.63
  6149.2  412.42  6172.3  413.64  6263.5  417.54  6342.9  418.09  6456.2  420.22
#Mann= 7 ,-1 , 0
    4552      .1       0  4922.1     .12       0  5029.4     .07       0
  5035.4     .12       0    5579      .1       0  6172.3     .05       0
  6342.9      .1       0
Bank Sta=4968.3,5140.2
XS Rating Curve= 0 ,0
Exp/Cntr=0.3,0.1

Type RM Length L Ch R = 1 ,24994   ,579,579,579
BEGIN DESCRIPTION:
PALO AMARILLO CREEK 38.0
END DESCRIPTION:
XS GIS Cut Line= 3
       2200396.9     13182878.89      2199813.56     13181983.06
        2199132.     13181655.28
#Sta/Elev= 30
  4753.4  401.57  4891.2  400.07  4942.6  397.59  4967.6  395.23  4984.7  395.03
  4996.9  393.79  4999.6  393.29  5002.9  393.79  5051.2  394.56  5057.2  396.55
  5072.3  395.47  5099.8  395.45  5123.7  395.38  5165.9  397.56    5181  396.93
  5202.1  397.94  5657.9  399.04  5995.3  402.78    6073  404.22  6206.2   409.4
  6242.8  409.85  6250.6  410.99  6355.9  412.89  6372.6  414.19  6429.4  414.88
  6505.8  417.55    6537  416.52  6542.5  418.07  6565.2  418.68  6578.7  419.99
#Mann= 5 ,-1 , 0
  4753.4      .1       0  4967.6     .12       0  4996.9     .07       0
  5002.9     .12       0  5099.8      .1       0
Bank Sta=4942.6,5202.1
XS Rating Curve= 0 ,0
Exp/Cntr=0.3,0.1

Type RM Length L Ch R = 1 ,24415   ,776,776,776
BEGIN DESCRIPTION:
Mapping XS 7b89d901
END DESCRIPTION:
XS GIS Cut Line= 4
       2199969.8     13183201.82      2200563.56      13182821.6
      2200787.52     13182082.02      2200943.78     13181373.66
#Sta/Elev= 30
  3798.9  408.17  3915.6   405.2  4039.9  403.58  4176.4  404.76  4200.2  405.98
  4235.8  405.31  4279.2  403.13  4388.2  400.56  4601.2  396.36  4710.4  395.61
  4752.3  395.61  4885.4  395.96  4984.2  392.67  4989.6  391.62  5007.4  390.56
  5010.2  390.06  5013.4  390.56  5022.4  390.89  5031.3  393.13    5094   393.5
  5121.1  395.01  5162.6  395.61    5187  396.24  5219.4  395.89  5258.1  397.06
  5456.1  398.58  5630.6  401.27  5753.1  404.79  5783.8  406.56  6002.1  413.85
#Mann= 5 ,-1 , 0
  3798.9      .1       0  4752.3     .12       0  5007.4     .07       0
  5013.4     .12       0  5162.6      .1       0
Bank Sta=4710.4,5187
XS Rating Curve= 0 ,0
Exp/Cntr=0.3,0.1

Type RM Length L Ch R = 1 ,23639   ,625,625,625
BEGIN DESCRIPTION:
PALO AMARILLO CREEK 37.0
END DESCRIPTION:
XS GIS Cut Line= 3
      2199987.76     13183246.83      2201337.72     13182496.85
      2201587.75     13182296.83
#Sta/Elev= 30
  3455.7  408.53  3669.6  403.42  3756.5  403.71  3821.7  405.47    3832  404.47
  3837.7  405.02  3956.7  402.15  3970.4  402.51  4050.5   399.7  4065.4  400.21
  4073.4  399.36  4140.9  397.95  4359.4  394.96  4552.7  393.72  4649.5   395.4
  4867.3  393.92  4926.8  392.63  5004.2  388.91    5007  388.41  5010.2  388.91
    5064  389.87    5092  393.62    5100  393.54  5106.5  395.64  5114.5   396.7
  5135.3  396.61  5141.7  397.99  5213.7  400.71  5292.1  406.48  5320.2  407.35
#Mann= 4 ,-1 , 0
  3455.7      .1       0  4649.5     .12       0  5004.2     .07       0
  5010.2     .12       0
Bank Sta=4867.3,5092
XS Rating Curve= 0 ,0
Exp/Cntr=0.3,0.1

Type RM Length L Ch R = 1 ,23014   ,604,604,604
BEGIN DESCRIPTION:
PALO AMARILLO CREEK 36.0
END DESCRIPTION:
XS GIS Cut Line= 3
      2200226.77     13183698.17      2201942.02      13182809.3
      2202101.34     13182691.54
#Sta/Elev= 30
    3433  400.56  3573.5  399.52  3607.3   399.3    3869  396.85  3946.6  396.01
  3990.8  396.78  4029.5  395.48  4243.4  393.96  4422.2  392.95  4516.3  393.88
  4539.6  393.17  4654.9  392.61  4731.6   392.2  4865.4  392.32  4903.4  392.03
  4964.2  389.46  4969.8     388  4974.1   385.4  4976.9   384.9  4980.1   385.4
  4991.9   385.6  4999.6  387.52  5060.3  391.69  5067.2  392.16  5074.8  393.66
  5146.8  398.23  5340.4  409.36  5371.6  410.06  5377.8  411.32    5563  415.49
#Mann= 12 ,-1 , 0
    3433      .1       0  3573.5     .16       0  3607.3      .1       0
    3869     .16       0  4243.4     .12       0  4539.6     .16       0
  4654.9     .12       0  4731.6     .16       0  4865.4     .12       0
  4974.1     .07       0  4980.1     .12       0  5060.3     .05       0
Bank Sta=4903.4,5067.2
XS Rating Curve= 0 ,0
Exp/Cntr=0.3,0.1

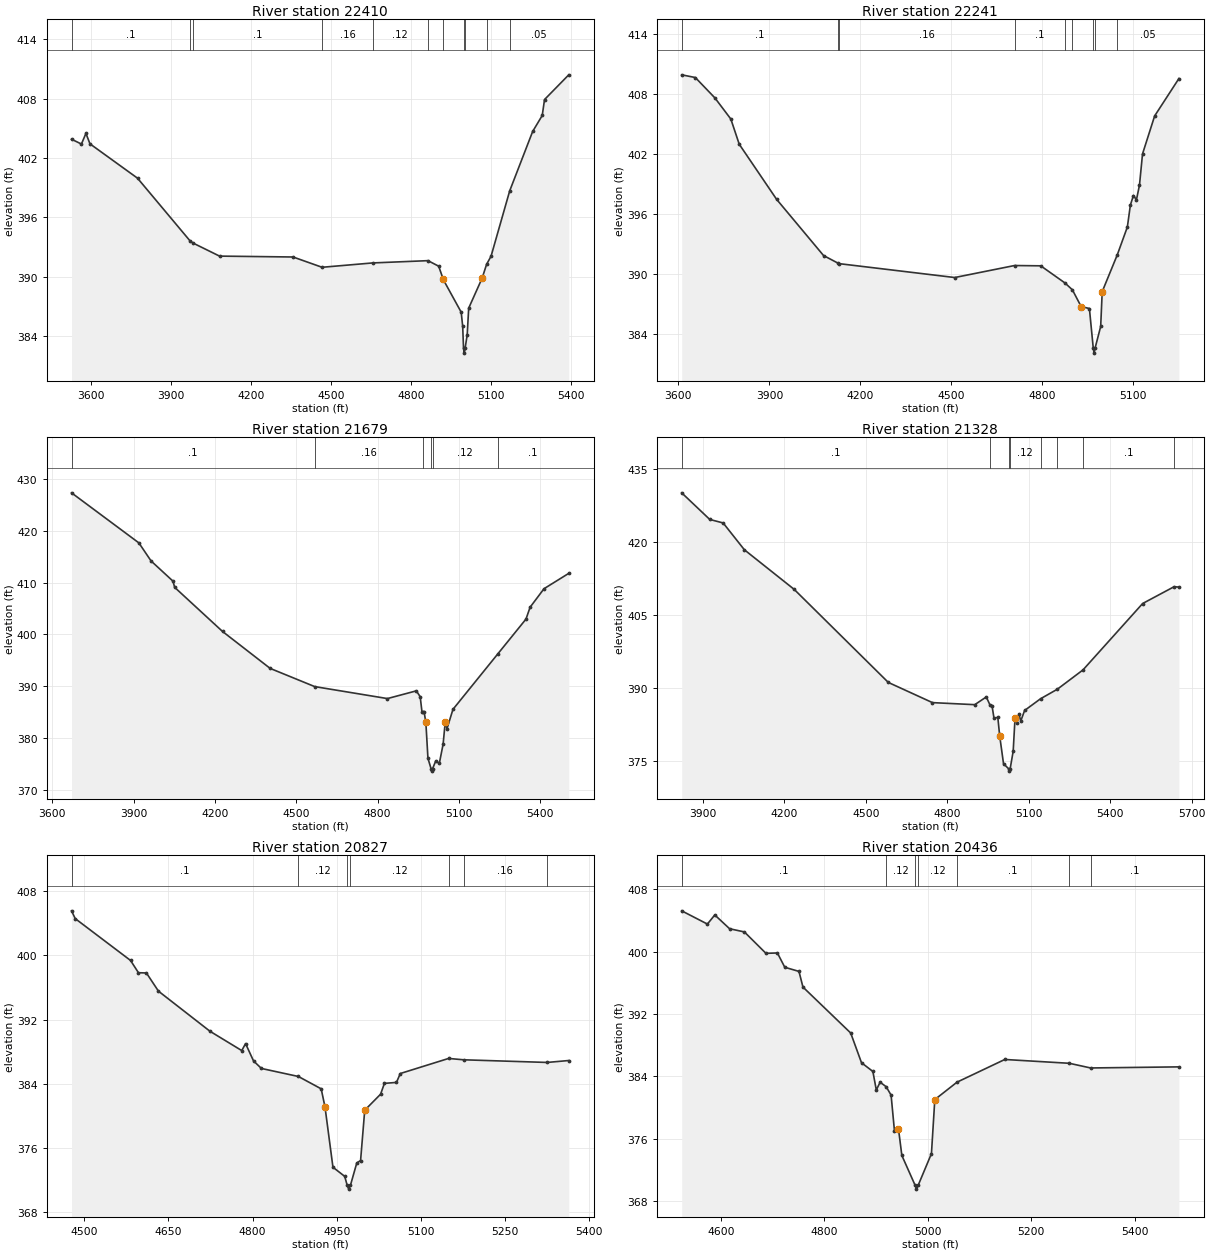
Type RM Length L Ch R = 1 ,22410   ,169,169,169
BEGIN DESCRIPTION:
PALO AMARILLO CREEK 35.0
END DESCRIPTION:
XS GIS Cut Line= 2
      2200615.59     13184066.26      2202289.25      13183246.8
#Sta/Elev= 30
  3527.9   403.9    3565  403.41  3581.9  404.49  3597.1  403.43  3775.2  399.96
  3971.4  393.64    3984  393.39  4082.6  392.08  4358.2  391.99  4466.9  390.95
  4656.7  391.39  4863.9  391.62  4903.9  391.06  4919.9  389.82  4920.8  389.72
  4988.3  386.41  4993.9  384.97    4997  382.77  4999.7  382.27    5003  382.77
  5010.8  384.12  5016.4  386.82    5067  389.87  5083.5  391.25  5100.2  392.07
  5170.1  398.68  5256.1  404.68    5292   406.3  5300.6  407.91  5391.4  410.41
#Mann= 11 ,-1 , 0
  3527.9      .1       0  3971.4     .16       0    3984      .1       0
  4466.9     .16       0  4656.7     .12       0  4863.9      .1       0
  4919.9     .12       0    4997     .07       0    5003     .12       0
  5083.5      .1       0  5170.1     .05       0
Bank Sta=4920.8,5067
XS Rating Curve= 0 ,0
Exp/Cntr=0.3,0.1

Type RM Length L Ch R = 1 ,22241   ,562,562,562
BEGIN DESCRIPTION:
PALO AMARILLO CREEK 34.0
END DESCRIPTION:
XS GIS Cut Line= 3
      2200837.76     13184246.83      2202037.72     13183546.85
      2202287.72     13183546.85
#Sta/Elev= 30
  3610.8  409.92  3655.8  409.65  3720.3  407.61  3772.8   405.5  3800.5  402.98
  3923.7  397.47  4078.4  391.85    4126  391.09  4129.2  391.04  4510.9  389.65
  4708.1  390.85  4794.5  390.82  4874.6   389.1  4898.8  388.42  4927.6  386.75
  4954.9  386.55  4967.6  382.59  4970.4  382.09  4973.6  382.59  4992.1  384.76
  4997.1  388.24  5046.7  391.91    5080   394.7    5090   396.9    5100  397.85
    5110  397.43    5120  398.89    5130  402.01    5170  405.81    5250  409.55
#Mann= 9 ,-1 , 0
  3610.8      .1       0    4126     .12       0  4129.2     .16       0
  4708.1      .1       0  4874.6     .12       0  4898.8      .1       0
  4967.6     .07       0  4973.6      .1       0  5046.7     .05       0
Bank Sta=4927.6,4997.1
XS Rating Curve= 0 ,0
Exp/Cntr=0.3,0.1

Type RM Length L Ch R = 1 ,21679   ,351,351,351
BEGIN DESCRIPTION:
PALO AMARILLO CREEK 33.0
END DESCRIPTION:
XS GIS Cut Line= 4
      2201287.86     13185174.16       2201735.1     13184367.82
      2202299.87     13183891.19      2202374.94     13183734.53
#Sta/Elev= 30
  3670.9  427.33  3919.4  417.67  3964.5  414.18  4045.2  410.29  4051.5  409.09
  4228.1  400.58  4403.9  393.45  4568.3  389.94  4836.6  387.63  4943.2  389.12
  4957.5  387.99  4964.1  385.05  4967.4  385.07  4971.8  385.09  4978.4  383.03
  4986.1  376.11  4997.4  374.13  5000.2  373.63  5003.4  374.13  5014.7  375.57
  5028.2  375.15  5042.1  378.84  5049.8  383.08  5056.4  381.81  5078.4  385.55
  5243.1   396.2  5347.9  402.97  5363.1  405.26  5414.4  408.83  5505.7  411.79
#Mann= 6 ,-1 , 0
  3670.9      .1       0  4568.3     .16       0  4967.4     .12       0
  4997.4     .07       0  5003.4     .12       0  5243.1      .1       0
Bank Sta=4978.4,5049.8
XS Rating Curve= 0 ,0
Exp/Cntr=0.3,0.1

Type RM Length L Ch R = 1 ,21328   ,501,501,501
BEGIN DESCRIPTION:
PALO AMARILLO CREEK 32.0
END DESCRIPTION:
XS GIS Cut Line= 3
      2201451.09      13185226.4      2202450.04     13184165.42
      2202515.34     13183796.51
#Sta/Elev= 30
  3821.3  430.02  3924.7  424.56  3974.1  423.84  4052.2  418.34  4235.9  410.21
  4582.6  391.13  4745.2  386.99    4901  386.57  4943.5  388.15  4957.1  386.51
  4964.5   386.4  4971.8  383.83    4986  383.95  4992.9  380.16    5007  374.46
  5025.5  373.44  5028.2  372.94  5031.5  373.44  5042.6  377.03  5049.5  383.92
  5056.8  382.82  5063.7  384.69  5070.6  383.23  5084.7  385.38  5143.3  387.78
  5205.3  389.74  5299.8   393.7  5519.6  407.32  5635.3  410.76  5653.2  410.69
#Mann= 8 ,-1 , 0
  3821.3      .1       0  4957.1     .12       0  5025.5     .07       0
  5031.5     .12       0  5143.3      .1       0  5205.3     .16       0
  5299.8      .1       0  5635.3     .05       0
Bank Sta=4992.9,5049.5
XS Rating Curve= 0 ,0
Exp/Cntr=0.3,0.1

Type RM Length L Ch R = 1 ,20827   ,391,391,391
BEGIN DESCRIPTION:
PALO AMARILLO CREEK 31.0
END DESCRIPTION:
XS GIS Cut Line= 2
      2202165.63     13185113.89      2202769.25     13184463.83
#Sta/Elev= 30
    4477  405.56  4483.6  404.59  4582.3  399.37  4596.4  397.84  4610.6  397.81
  4632.1  395.54    4724  390.54  4780.7  388.13  4787.5     389  4801.7  386.84
  4815.8   385.9  4881.7   384.9  4922.4  383.36  4929.2  381.11  4943.4  373.58
  4964.4  372.44  4968.7  371.35  4971.5  370.85  4974.7  371.35  4985.9  374.11
  4992.7  374.42  5000.1  380.69  5028.4  382.69  5035.2  384.04  5056.7  384.16
  5063.6  385.27  5149.8  387.15  5176.5  386.98  5325.5  386.65  5364.1  386.89
#Mann= 7 ,-1 , 0
    4477      .1       0  4881.7     .12       0  4968.7     .07       0
  4974.7     .12       0  5149.8      .1       0  5176.5     .16       0
  5325.5      .1       0
Bank Sta=4929.2,5000.1
XS Rating Curve= 0 ,0
Exp/Cntr=0.3,0.1

Type RM Length L Ch R = 1 ,20436   ,516,516,516
BEGIN DESCRIPTION:
PALO AMARILLO CREEK 30.0
END DESCRIPTION:
XS GIS Cut Line= 2
        2202421.     13185400.27      2203040.14     13184665.04
#Sta/Elev= 30
  4524.4  405.26  4574.1  403.56  4588.4  404.73    4617  402.96  4645.6  402.55
  4687.3   399.8  4709.4  399.85  4723.7  398.01  4751.1  397.48  4758.8  395.47
  4851.1  389.57    4872  385.75    4894  384.63  4900.6  382.25    4908  383.25
  4919.7  382.67  4929.2  381.59  4935.7     377  4943.5  377.24    4950  373.84
  4975.6  370.02  4978.3  369.52  4981.6  370.02  5007.2  374.08  5013.7  381.02
  5056.7  383.26    5149  386.17  5273.8  385.68  5314.9  385.08  5485.6  385.22
#Mann= 7 ,-1 , 0
  4524.4      .1       0  4919.7     .12       0  4975.6     .07       0
  4981.6     .12       0  5056.7      .1       0  5273.8     .16       0
  5314.9      .1       0
Bank Sta=4943.5,5013.7
XS Rating Curve= 0 ,0
Exp/Cntr=0.3,0.1

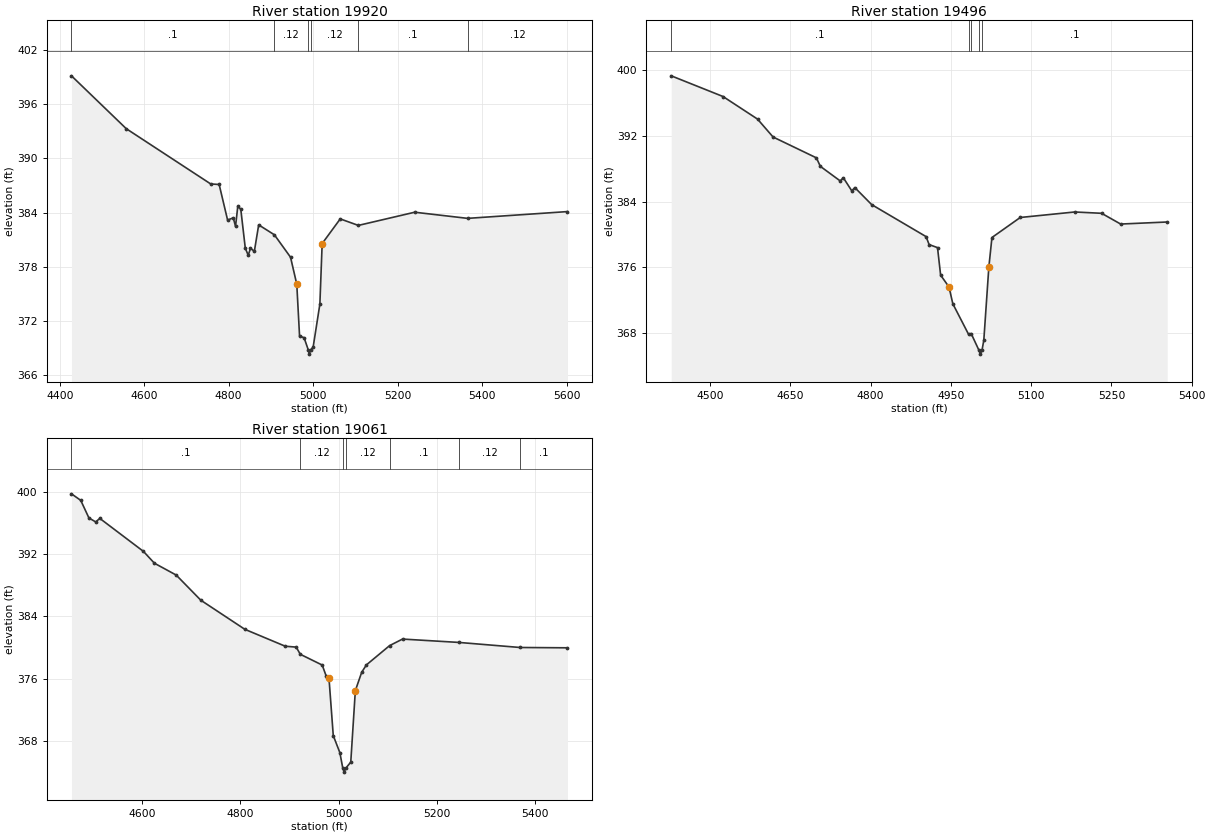
Type RM Length L Ch R = 1 ,19920   ,424,424,424
BEGIN DESCRIPTION:
PALO AMARILLO CREEK 29.0
END DESCRIPTION:
XS GIS Cut Line= 3
      2203055.64     13185806.58      2203059.51     13185423.47
        2203342.     13184684.34
#Sta/Elev= 30
  4427.8  399.14  4557.5  393.29  4757.5  387.17  4777.5  387.11  4797.5  383.17
  4810.9  383.42  4816.3  382.47  4821.6  384.69  4828.7  384.38  4839.4  380.06
  4846.4  379.27  4851.7  380.06  4860.8   379.7  4871.1  382.64  4908.3  381.54
  4946.5  379.06  4961.3  376.07  4967.9  370.32  4978.6  370.15  4988.3  368.83
  4991.1  368.33  4994.3  368.83    5000  369.09    5016  373.87  5021.4  380.57
  5064.2   383.3  5107.1  382.58  5240.5  384.04  5365.8  383.36  5602.2  384.11
#Mann= 6 ,-1 , 0
  4427.8      .1       0  4908.3     .12       0  4988.3     .07       0
  4994.3     .12       0  5107.1      .1       0  5365.8     .12       0
Bank Sta=4961.3,5021.4
XS Rating Curve= 0 ,0
Exp/Cntr=0.3,0.1

Type RM Length L Ch R = 1 ,19496   ,435,435,435
BEGIN DESCRIPTION:
PALO AMARILLO CREEK 28.0
END DESCRIPTION:
XS GIS Cut Line= 2
      2203241.37     13185791.11      2203709.08     13184990.98
#Sta/Elev= 30
  4427.5  399.34  4524.3  396.82  4588.8  394.07  4617.8  391.89  4698.8  389.35
  4706.1  388.32  4743.3  386.54  4749.1  386.93  4764.8  385.34  4770.6  385.73
    4802  383.66  4903.7  379.76  4909.4  378.79  4925.1  378.42  4930.9  375.07
  4946.6  373.62  4953.7  371.58  4983.2  367.85    4988  367.95  5002.3  365.95
  5005.1  365.45  5008.3  365.95  5011.6  367.14    5021  376.04  5026.8  379.65
  5079.7  382.09  5181.4  382.76  5231.7   382.6  5267.3  381.29  5354.3  381.54
#Mann= 5 ,-1 , 0
  4427.5      .1       0  4983.2     .12       0    4988      .1       0
  5002.3     .07       0  5008.3      .1       0
Bank Sta=4946.6,5021
XS Rating Curve= 0 ,0
Exp/Cntr=0.3,0.1

Type RM Length L Ch R = 1 ,19061   ,574,574,574
BEGIN DESCRIPTION:
Mapping XS ea0f79f0
END DESCRIPTION:
XS GIS Cut Line= 2
      2203605.12     13185980.72      2204065.62     13185082.93
#Sta/Elev= 30
  4456.2  399.71  4475.1  398.87  4491.7  396.62  4505.5  396.11  4513.9  396.56
  4602.7  392.33  4624.9  390.82  4669.3   389.3  4719.3  386.08  4808.9  382.35
  4891.2  380.18  4913.4  380.07  4921.7  379.15  4966.3  377.77  4974.4  376.36
    4980  376.16  4988.8  368.73  5002.2  366.55  5008.2  364.55    5011  364.05
  5014.2  364.55  5024.4  365.33  5033.7  374.49  5046.6  376.84  5056.2  377.79
  5103.4  380.26  5129.7   381.1  5244.1  380.67  5368.9  380.02  5465.2  379.98
#Mann= 7 ,-1 , 0
  4456.2      .1       0  4921.7     .12       0  5008.2     .07       0
  5014.2     .12       0  5103.4      .1       0  5244.1     .12       0
  5368.9      .1       0
Bank Sta=4980,5033.7
XS Rating Curve= 0 ,0
Exp/Cntr=0.3,0.1