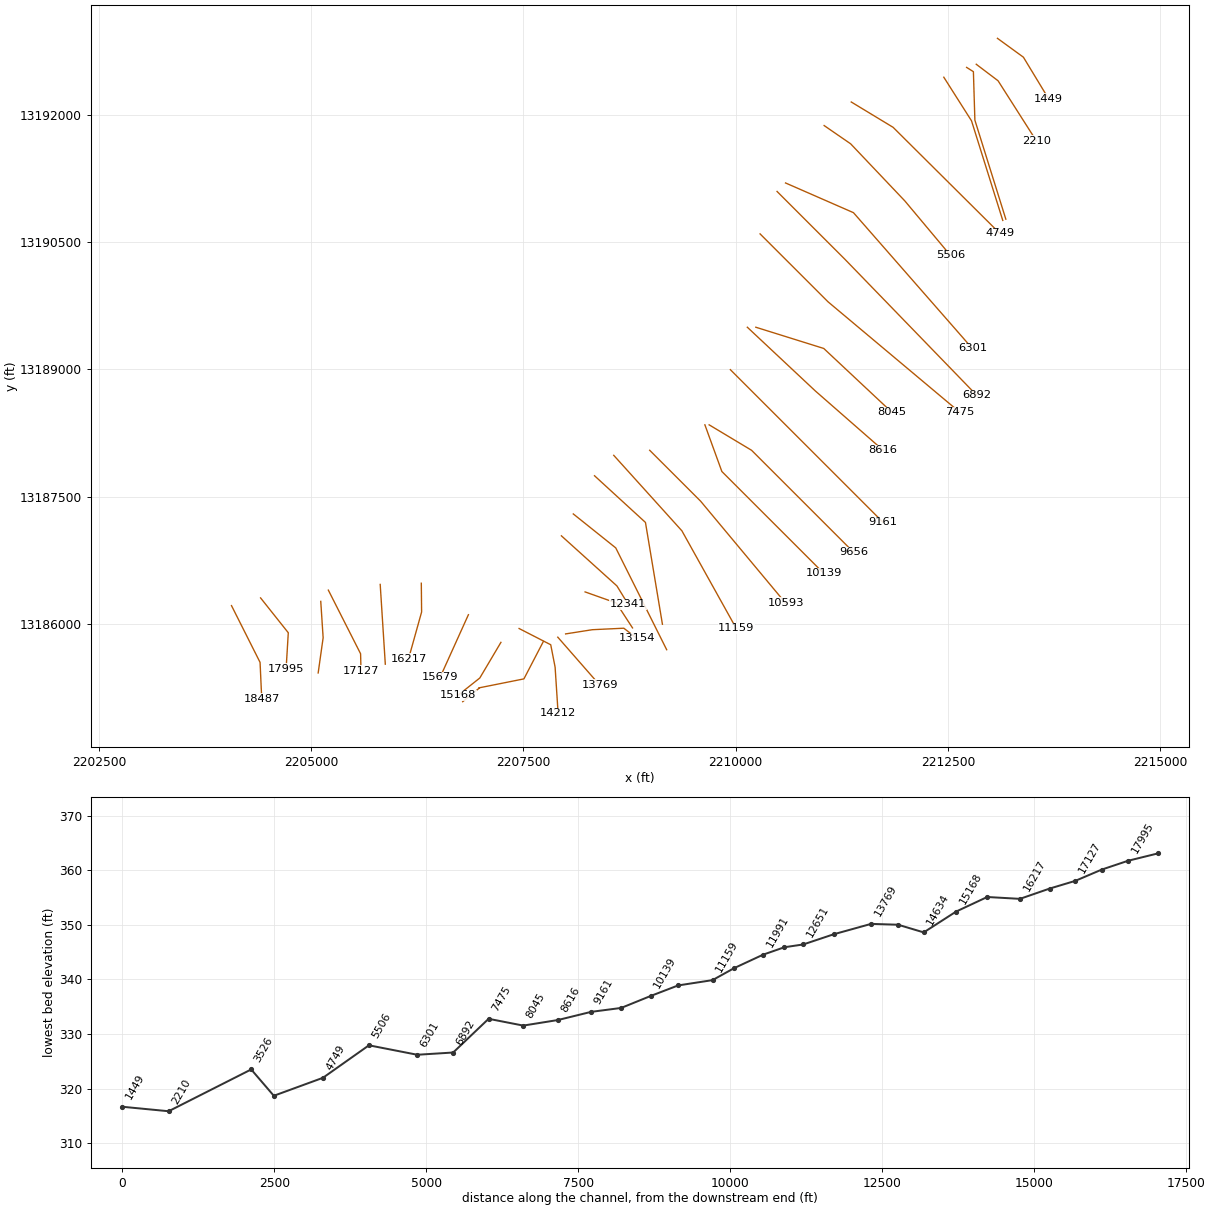
HEC-RAS study PALO AMARILLO CREEK.prj: PALO AMARILLO CREEK Base Level Engineering

--- PALO AMARILLO CREEK.g01 (geometry) --- (continued)

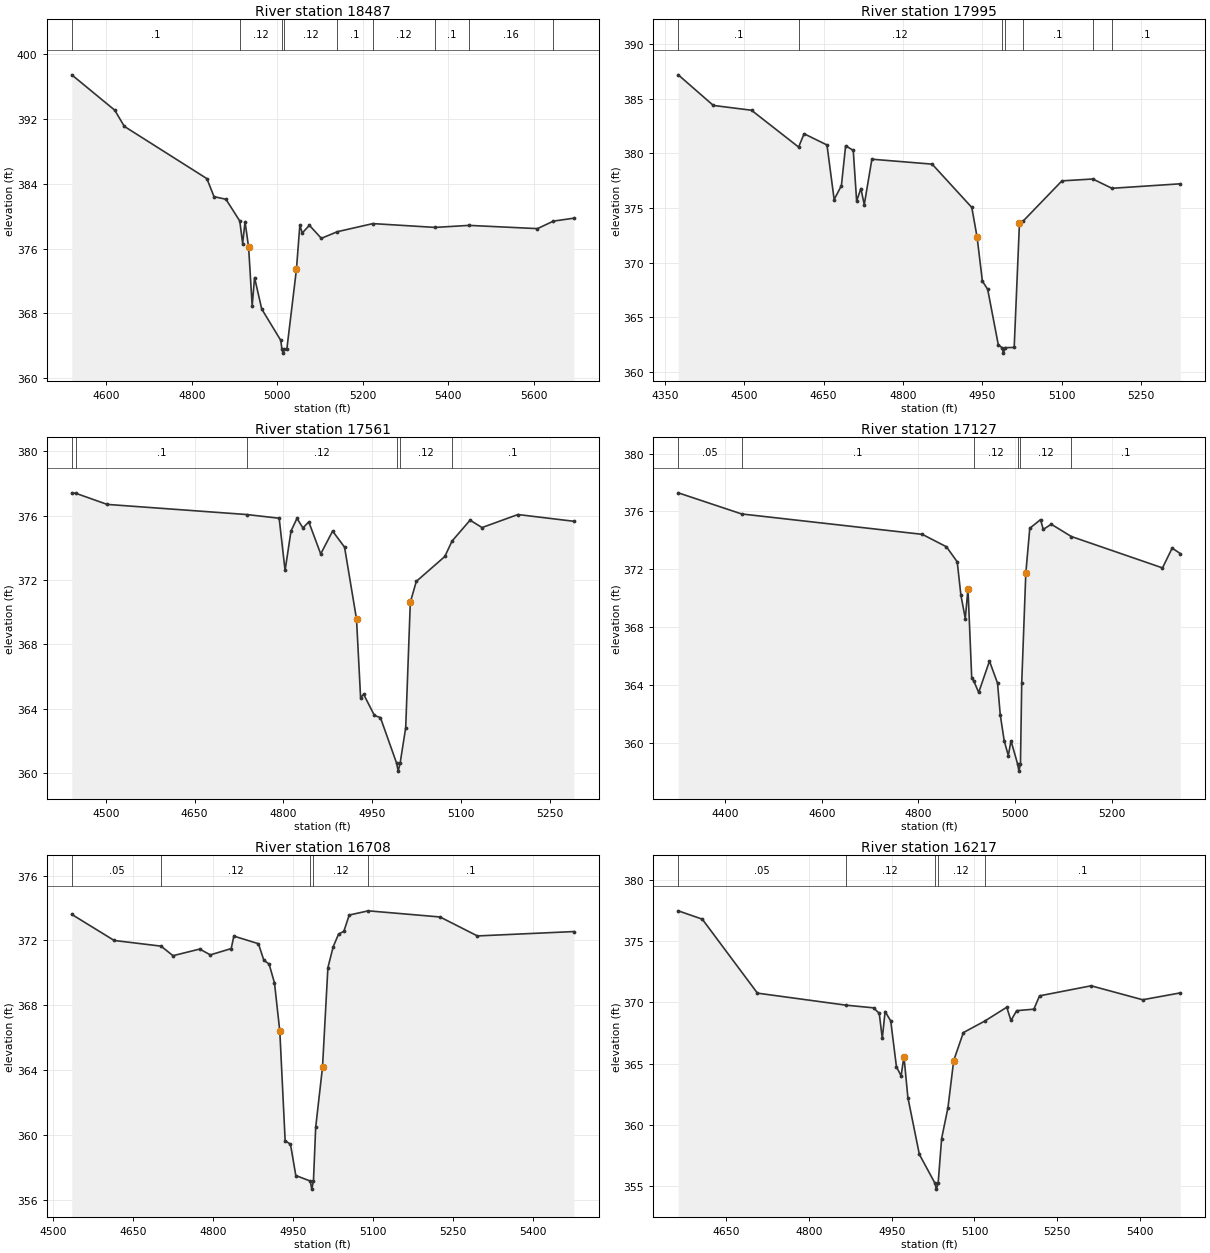
Type RM Length L Ch R = 1 ,18487   ,492,492,492
BEGIN DESCRIPTION:
PALO AMARILLO CREEK 27.0
END DESCRIPTION:
XS GIS Cut Line= 3
      2204061.76     13186216.72      2204398.41      13185547.3
      2204417.75     13185121.74
#Sta/Elev= 30
    4519  397.48  4619.6  393.11    4642  391.11  4835.3  384.65    4852  382.42
  4879.9   382.1  4912.3  379.41    4919  376.63  4924.6  379.32    4933  376.15
  4941.3  368.92  4946.9  372.42  4963.6  368.54  5008.3  364.65  5010.9  363.58
  5013.6  363.08  5016.9  363.58  5022.5  363.59  5044.9  373.42  5052.9   378.9
  5058.5  377.93  5075.3  378.88  5103.2  377.27  5140.7  378.09  5223.9  379.09
  5369.5  378.62    5449  378.87  5609.1  378.47  5646.6   379.4  5694.3  379.76
#Mann= 9 ,-1 , 0
    4519      .1       0  4912.3     .12       0  5010.9     .07       0
  5016.9     .12       0  5140.7      .1       0  5223.9     .12       0
  5369.5      .1       0    5449     .16       0  5646.6     .12       0
Bank Sta=4933,5044.9
XS Rating Curve= 0 ,0
Exp/Cntr=0.3,0.1

Type RM Length L Ch R = 1 ,17995   ,434,434,434
BEGIN DESCRIPTION:
PALO AMARILLO CREEK 26.0
END DESCRIPTION:
XS GIS Cut Line= 3
      2204404.35     13186307.35      2204730.72     13185896.83
      2204705.23     13185473.64
#Sta/Elev= 30
  4375.4  387.19  4441.7  384.39  4513.8  383.95  4602.8  380.58  4613.1   381.8
  4656.4  380.77  4669.9  375.78  4683.6  377.05  4691.6   380.7    4706  380.28
  4712.4  375.64  4720.4  376.79  4726.8  375.31  4741.2  379.47    4855  379.02
  4929.9  375.06  4939.9  372.35  4949.9  368.32  4959.9  367.57    4980  362.49
    4987  362.23  4989.7  361.73    4993  362.23    5010  362.25    5020  373.67
  5027.5  373.84  5100.2  377.49  5158.5  377.66  5194.6  376.81  5323.8  377.22
#Mann= 7 ,-1 , 0
  4375.4      .1       0  4602.8     .12       0    4987     .07       0
    4993     .12       0  5027.5      .1       0  5158.5     .12       0
  5194.6      .1       0
Bank Sta=4939.9,5020
XS Rating Curve= 0 ,0
Exp/Cntr=0.3,0.1

Type RM Length L Ch R = 1 ,17561   ,434,434,434
BEGIN DESCRIPTION:
PALO AMARILLO CREEK 25.0
END DESCRIPTION:
XS GIS Cut Line= 3
      2205113.15     13186266.51       2205141.2      13185838.2
      2205082.64     13185423.24
#Sta/Elev= 30
  4442.6  377.42  4449.5  377.39  4502.4   376.7  4738.1  376.07    4793  375.84
    4803  372.59    4813  375.04  4823.1  375.83  4833.1  375.24  4843.1  375.61
  4863.2  373.62  4883.3  375.04  4903.5  374.04  4923.7  369.57  4930.6  364.68
  4935.7  364.89    4954  363.57  4964.1  363.44  4991.4  360.61  4994.1  360.11
  4997.4  360.61  5006.8  362.81  5014.6  370.61  5024.7  371.91  5072.9  373.46
  5085.1  374.42  5115.6  375.72  5135.8  375.26  5196.4  376.07  5290.9  375.65
#Mann= 6 ,-1 , 0
  4442.6     .05       0  4449.5      .1       0  4738.1     .12       0
  4991.4     .07       0  4997.4     .12       0  5085.1      .1       0
Bank Sta=4923.7,5014.6
XS Rating Curve= 0 ,0
Exp/Cntr=0.3,0.1

Type RM Length L Ch R = 1 ,17127   ,419,419,419
BEGIN DESCRIPTION:
PALO AMARILLO CREEK 24.0
END DESCRIPTION:
XS GIS Cut Line= 3
      2205202.37     13186399.12      2205582.27     13185649.53
      2205587.32     13185449.95
#Sta/Elev= 30
  4302.4  377.29  4433.7  375.83  4807.9  374.42    4858  373.56  4880.3  372.52
  4887.9  370.22    4897   368.6  4902.6  370.66  4910.3  364.52  4914.8  364.26
  4924.8  363.49  4947.1  365.66  4963.8  364.13  4969.4  361.95  4977.6  360.15
  4986.1  359.13  4991.7  360.15  5005.3  358.55  5008.1  358.05  5011.3  358.55
  5013.9  364.14  5022.4  371.75  5030.6  374.84  5052.9  375.44  5058.5  374.76
  5075.1  375.12  5116.7  374.27  5305.5   372.1  5325.5  373.47  5342.4  373.09
#Mann= 6 ,-1 , 0
  4302.4     .05       0  4433.7      .1       0  4914.8     .12       0
  5005.3     .07       0  5011.3     .12       0  5116.7      .1       0
Bank Sta=4902.6,5022.4
XS Rating Curve= 0 ,0
Exp/Cntr=0.3,0.1

Type RM Length L Ch R = 1 ,16708   ,491,491,491
BEGIN DESCRIPTION:
PALO AMARILLO CREEK 23.0
END DESCRIPTION:
XS GIS Cut Line= 2
      2205813.39     13186466.34      2205873.46     13185526.36
#Sta/Elev= 30
  4534.9  373.61  4614.5     372  4702.4  371.65  4724.8  371.06  4774.9  371.47
  4794.9  371.11    4834   371.5    4839  372.27  4885.1   371.8  4895.1  370.79
  4905.1  370.54  4915.2  369.38  4925.2  366.39  4935.2  359.64  4945.2  359.42
  4955.2  357.49  4982.3  357.15  4985.1  356.65  4988.3  357.15  4992.5  360.47
  5005.3  364.18  5015.4  370.32  5025.4  371.62  5035.4  372.39  5045.4  372.57
  5055.4  373.57  5091.2  373.83  5225.8  373.45  5295.9  372.28  5476.8  372.55
#Mann= 5 ,-1 , 0
  4534.9     .05       0  4702.4     .12       0  4982.3     .07       0
  4988.3     .12       0  5091.2      .1       0
Bank Sta=4925.2,5005.3
XS Rating Curve= 0 ,0
Exp/Cntr=0.3,0.1

Type RM Length L Ch R = 1 ,16217   ,538,538,538
BEGIN DESCRIPTION:
PALO AMARILLO CREEK 22.0
END DESCRIPTION:
XS GIS Cut Line= 4
      2206297.51     13186480.43      2206301.05      13186141.2
       2206149.1     13185597.01       2206149.1     13185590.86
#Sta/Elev= 30
  4562.8  377.48  4606.4   376.8  4706.4  370.76  4866.7  369.78  4916.9  369.56
  4927.3  369.11  4932.8  367.06  4937.9  369.26  4948.1  368.49  4958.5  364.74
  4966.9  364.01  4972.1  365.58  4979.2  362.24    5000   357.6  5028.1  355.26
  5030.9  354.76  5034.1  355.26  5040.4  358.89  5051.9  361.42  5062.3  365.26
  5079.8  367.54  5118.2  368.47  5158.5  369.61  5166.1  368.53  5176.5  369.33
  5207.6  369.45    5218  370.54  5311.5  371.36  5404.9  370.22  5473.2  370.78
#Mann= 5 ,-1 , 0
  4562.8     .05       0  4866.7     .12       0  5028.1     .07       0
  5034.1     .12       0  5118.2      .1       0
Bank Sta=4972.1,5062.3
XS Rating Curve= 0 ,0
Exp/Cntr=0.3,0.1

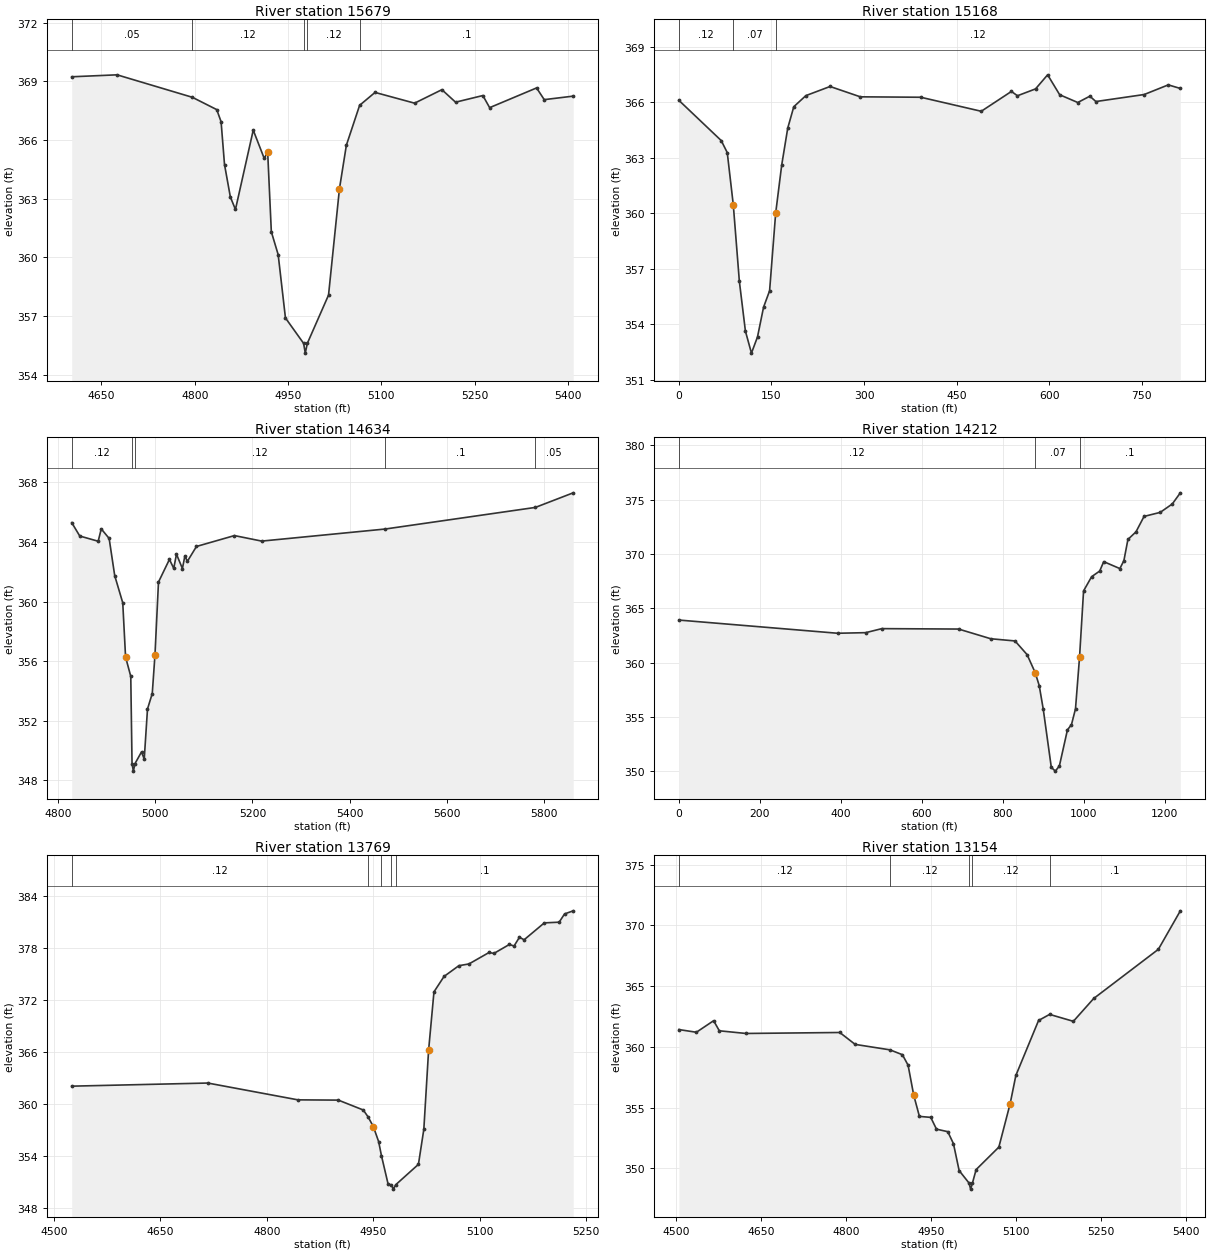
Type RM Length L Ch R = 1 ,15679   ,511,511,511
BEGIN DESCRIPTION:
PALO AMARILLO CREEK 21.0
END DESCRIPTION:
XS GIS Cut Line= 2
      2206852.29     13186109.36      2206520.15     13185374.42
#Sta/Elev= 30
  4602.2  369.24  4675.1  369.34  4796.2  368.19  4835.4  367.56  4842.4  366.94
  4847.9  364.75  4857.3  363.09  4865.5  362.45  4894.1  366.51  4911.8  365.06
  4917.3   365.4  4923.2  361.31  4934.2  360.14  4945.9   356.9  4975.1   355.6
  4977.8   355.1  4981.1   355.6  5015.2  358.07  5032.8  363.52  5043.9  365.74
  5065.2  367.78    5090  368.44  5153.6  367.89  5197.5  368.58  5219.5  367.94
  5263.4  368.28  5274.3  367.66  5349.8  368.67  5362.1  368.07  5408.7  368.25
#Mann= 5 ,-1 , 0
  4602.2     .05       0  4796.2     .12       0  4975.1     .07       0
  4981.1     .12       0  5065.2      .1       0
Bank Sta=4917.3,5032.8
XS Rating Curve= 0 ,0
Exp/Cntr=0.3,0.1

Type RM Length L Ch R = 1 ,15168   ,534,534,534
BEGIN DESCRIPTION:
PALO AMARILLO CREEK 20.0
END DESCRIPTION:
XS GIS Cut Line= 3
     2207235.318    13185783.687     2206986.586    13185363.785
     2206731.821    13185161.579
#Sta/Elev= 30
       0366.109768.60901363.934978.41029363.282988.21159360.451898.01287356.3234
107.8142353.6336117.6154352.4396127.4167353.3164 137.218354.9199147.0193355.8114
156.8206359.9946166.6219362.6072176.4232364.6066186.2245 365.764 205.827366.3649
245.0322366.8584294.0386366.2997392.0515366.2765490.0399 365.518538.9244366.5911
548.7013366.3572 578.032366.7282597.5858367.4891617.1395366.4115646.4702365.9923
 666.024366.3343675.8009366.0448 754.016366.4233793.1235366.9454812.6774366.7524
#Mann= 3 , 0 , 0
       0     .12       088.21159     .07       0156.8206     .12       0
Bank Sta=88.21159,156.8206
XS Rating Curve= 0 ,0
Exp/Cntr=0.3,0.1

Type RM Length L Ch R = 1 ,14634   ,422,422,422
BEGIN DESCRIPTION:
Mapping XS 382a861a
END DESCRIPTION:
XS GIS Cut Line= 5
      2207735.74     13185794.91      2207506.04     13185353.18
      2206975.98     13185247.17      2206983.05     13185247.17
      2206785.15     13185084.61
#Sta/Elev= 30
  4828.3   365.3  4844.8   364.4  4882.7  364.05    4889  364.88  4905.2  364.24
  4916.7  361.74  4933.2  359.92    4939  356.28  4949.7  354.98  4952.3  349.12
  4955.1  348.62  4958.3  349.12  4971.8  349.91  4977.4  349.43  4984.1  352.79
  4993.9  353.83  4999.5  356.43  5006.7  361.31  5029.2  362.83  5038.1  362.23
  5043.7  363.18  5055.9  362.22    5061  363.06  5066.1   362.7  5084.8   363.7
  5162.9  364.43    5219  364.06  5472.9  364.87  5781.7  366.32  5859.6   367.3
#Mann= 5 ,-1 , 0
  4828.3     .12       0  4952.3     .07       0  4958.3     .12       0
  5472.9      .1       0  5781.7     .05       0
Bank Sta=4939,4999.5
XS Rating Curve= 0 ,0
Exp/Cntr=0.3,0.1

Type RM Length L Ch R = 1 ,14212   ,443,443,443
BEGIN DESCRIPTION:
PALO AMARILLO CREEK 19.0
END DESCRIPTION:
XS GIS Cut Line= 4
     2207449.269    13185946.736     2207822.041    13185755.402
     2207873.548    13185490.999     2207908.885    13184946.807
#Sta/Elev= 30
       0363.9172392.2025362.7034461.5172362.7581501.4166363.1286690.9388363.0905
770.6289362.1972830.3964361.9967860.2802360.7348880.2027 359.083890.1639357.8951
900.1252355.7267920.0477350.3686930.0089350.0242939.9702350.4991959.8927353.8195
969.8539354.2996979.8152355.7586989.7764360.4969999.7377366.5987 1019.66367.9064
1039.583368.42411049.544369.28941089.389368.6524 1099.35369.38081109.312 371.332
1129.234372.02981149.156 373.4491189.001373.81971218.885 374.5921238.808375.6182
#Mann= 3 , 0 , 0
       0     .12       0880.2027     .07       0989.7764      .1       0
Bank Sta=880.2027,989.7764
XS Rating Curve= 0 ,0
Exp/Cntr=0.3,0.1

Type RM Length L Ch R = 1 ,13769   ,615,615,615
BEGIN DESCRIPTION:
PALO AMARILLO CREEK 18.0
END DESCRIPTION:
XS GIS Cut Line= 2
      2207905.32     13185844.41       2208398.8     13185280.43
#Sta/Elev= 30
  4525.1  362.06  4716.9  362.42    4844  360.48    4901  360.45  4936.1  359.31
  4942.8  358.53  4950.3   357.4  4957.8  355.66  4961.8  354.02  4971.2  350.74
  4975.8  350.68  4978.6  350.18  4981.8  350.68  5013.9  353.04  5021.5  357.08
  5028.2  366.18  5035.8  372.94    5050  374.72  5070.9  375.96  5085.1  376.16
  5113.6  377.49  5120.2  377.37  5142.1  378.41  5148.7  378.23  5156.3  379.24
  5162.9  378.95  5191.4   380.9  5212.3  380.98  5219.9  381.93  5232.1  382.29
#Mann= 5 ,-1 , 0
  4525.1     .12       0  4942.8     .12       0  4961.8      .1       0
  4975.8     .07       0  4981.8      .1       0
Bank Sta=4950.3,5028.2
XS Rating Curve= 0 ,0
Exp/Cntr=0.3,0.1

Type RM Length L Ch R = 1 ,13154   ,503,503,503
BEGIN DESCRIPTION:
PALO AMARILLO CREEK 17.0
END DESCRIPTION:
XS GIS Cut Line= 4
      2207997.19     13185883.23      2208311.73     13185932.71
      2208682.77     13185950.38      2208837.17     13185831.07
#Sta/Elev= 30
  4505.4  361.42  4536.3   361.2  4566.7  362.15  4576.8  361.32  4623.8   361.1
  4789.4  361.18  4816.5   360.2    4878  359.75  4899.9  359.35  4909.9  358.49
  4919.9  356.01  4929.9  354.27  4949.9  354.19    4960  353.22    4980  353.01
    4990  352.02    5000  349.81  5017.5  348.78  5020.3  348.28  5023.5  348.78
    5030  349.89  5070.1  351.74  5090.1  355.33  5100.1  357.64  5140.2  362.17
  5159.7  362.67  5201.6   362.1  5237.5  363.98  5351.6  368.03  5390.4   371.2
#Mann= 5 ,-1 , 0
  4505.4     .12       0    4878     .12       0  5017.5     .07       0
  5023.5     .12       0  5159.7      .1       0
Bank Sta=4919.9,5090.1
XS Rating Curve= 0 ,0
Exp/Cntr=0.3,0.1

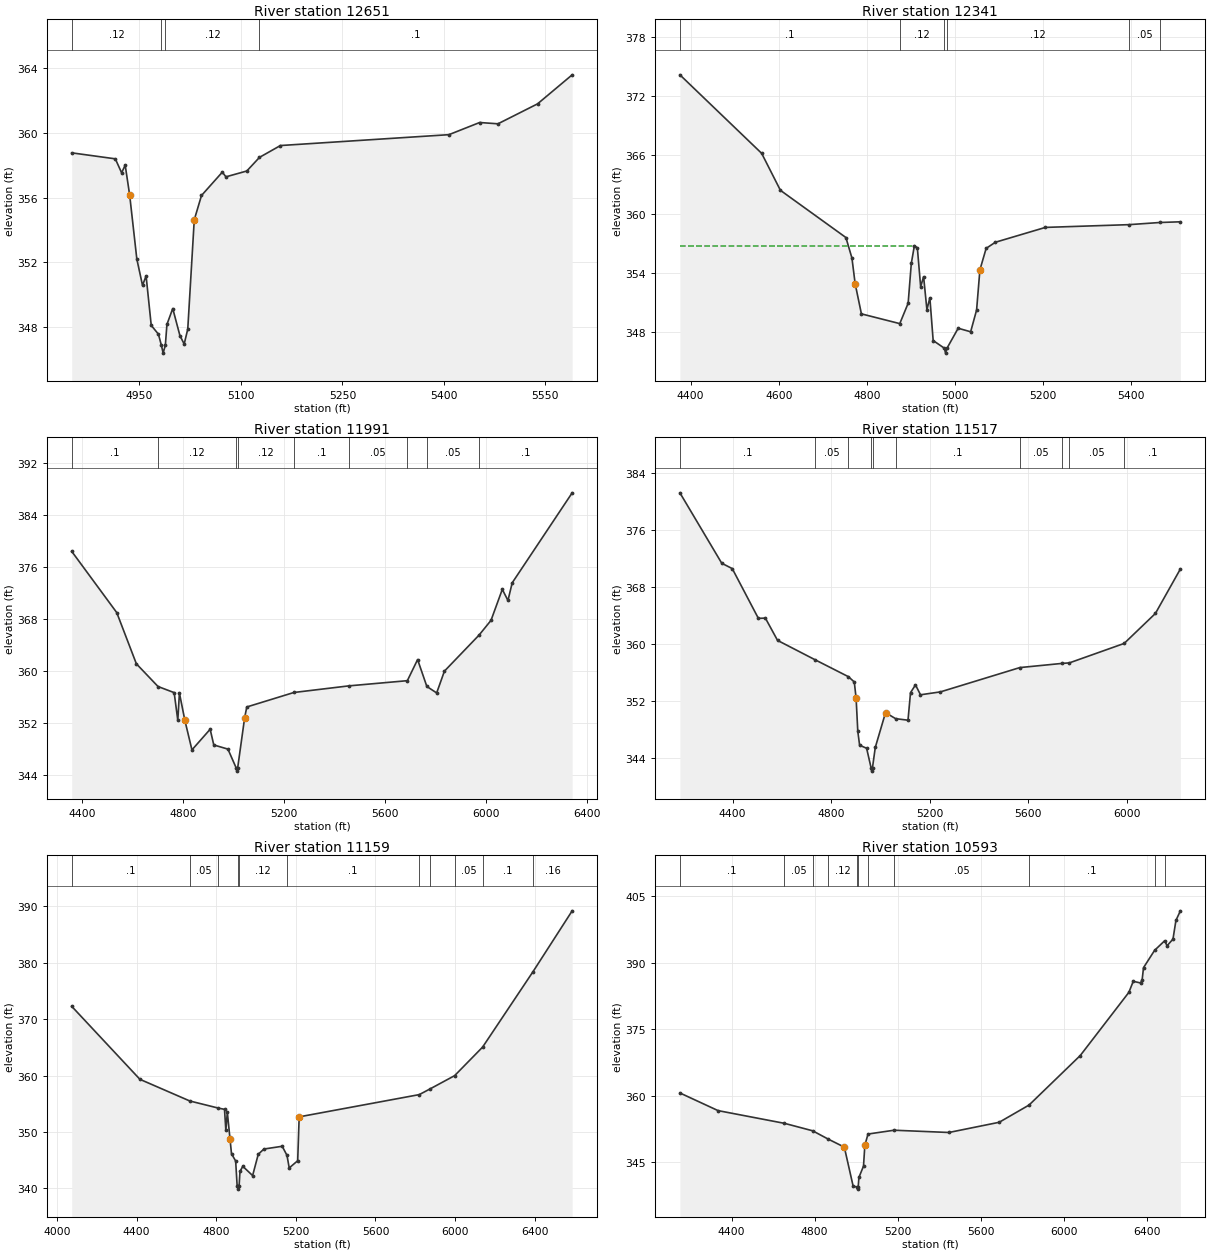
Type RM Length L Ch R = 1 ,12651   ,310,310,310
BEGIN DESCRIPTION:
PALO AMARILLO CREEK 16.0
END DESCRIPTION:
XS GIS Cut Line= 3
      2208226.96     13186377.95      2208594.43     13186247.21
      2208785.22     13185953.95
#Sta/Elev= 30
  4849.8  358.76  4914.3  358.39  4923.6  357.53  4928.9     358  4935.5  356.16
  4946.1  352.21  4954.5  350.59  4959.8  351.17  4967.4  348.12    4978  347.58
  4982.3  346.91    4985  346.41  4988.3  346.91  4990.6  348.18  4999.2  349.16
  5009.8  347.49  5016.1  346.97  5021.4  347.89    5031  354.63  5041.7  356.13
  5072.5  357.57  5077.8  357.28  5108.7  357.64  5127.4  358.48  5158.4  359.21
  5407.5  359.88  5452.9  360.63    5480  360.55  5538.5  361.78  5589.7  363.57
#Mann= 4 ,-1 , 0
  4849.8     .12       0  4982.3     .07       0  4988.3     .12       0
  5127.4      .1       0
Bank Sta=4935.5,5031
XS Rating Curve= 0 ,0
Exp/Cntr=0.3,0.1

Type RM Length L Ch R = 1 ,12341   ,350,350,350
BEGIN DESCRIPTION:
PALO AMARILLO CREEK 15.0
END DESCRIPTION:
XS GIS Cut Line= 3
      2207947.75     13187038.77      2208601.49     13186448.64
      2208735.06     13186230.71
#Sta/Elev= 30
  4375.6  374.19  4561.2  366.21  4603.8  362.45  4752.5  357.65  4766.2  355.56
  4773.5  352.95  4787.7  349.89  4874.8   348.9  4893.8  350.97    4901  355.03
    4908  356.83  4914.7   356.6  4922.2  352.65  4928.9  353.67  4936.4  350.31
  4943.1  351.53  4950.6  347.18    4976   346.4  4978.7   345.9    4982   346.4
  5007.4  348.43  5035.7  348.07  5049.2  350.28  5056.7  354.36  5070.9  356.55
  5091.8  357.17  5205.4  358.68  5395.2  358.96  5465.6  359.18  5511.9  359.25
#Mann= 6 ,-1 , 0
  4375.6      .1       0  4874.8     .12       0    4976     .07       0
    4982     .12       0  5395.2     .05       0  5465.6      .1       0
#XS Ineff= 2 , 0
         4907.95  356.83
Permanent Ineff=
       F       F
Bank Sta=4773.5,5056.7
XS Rating Curve= 0 ,0
Exp/Cntr=0.3,0.1

Type RM Length L Ch R = 1 ,11991   ,474,474,474
BEGIN DESCRIPTION:
PALO AMARILLO CREEK 14.0
END DESCRIPTION:
XS GIS Cut Line= 3
      2208087.73     13187296.85      2208587.72     13186896.86
       2209187.7     13185696.89
#Sta/Elev= 30
  4359.7  378.39  4538.2  368.95  4615.8  361.07  4701.6  357.57  4765.5  356.63
  4779.9  352.36  4786.3  356.57  4807.9  352.35  4835.9  347.81    4908  350.99
  4922.4  348.57  4978.4  347.93    5011  345.04  5013.7  344.54    5017  345.04
  5044.7  352.79  5053.1  354.42  5239.5  356.65  5457.2  357.67  5688.9  358.47
  5729.5  361.72  5766.1  357.58    5805  356.58  5835.7  359.94  5973.1   365.5
  6020.2  367.76  6064.9  372.53  6087.3  370.82  6104.1  373.54  6341.6   387.4
#Mann= 9 ,-1 , 0
  4359.7      .1       0  4701.6     .12       0    5011     .07       0
    5017     .12       0  5239.5      .1       0  5457.2     .05       0
  5688.9      .1       0  5766.1     .05       0  5973.1      .1       0
Bank Sta=4807.9,5044.7
XS Rating Curve= 0 ,0
Exp/Cntr=0.3,0.1

Type RM Length L Ch R = 1 ,11517   ,358,358,358
BEGIN DESCRIPTION:
PALO AMARILLO CREEK 13.0
END DESCRIPTION:
XS GIS Cut Line= 3
      2208337.75     13187746.83      2208937.72     13187196.85
      2209137.73     13185996.81
#Sta/Elev= 30
  4186.1  381.17  4355.9  371.28  4398.5  370.53  4504.5  363.54  4532.9  363.58
  4582.2  360.45    4735  357.72  4869.8  355.35  4893.6  354.61    4901  352.33
  4907.8  347.68  4915.2  345.73  4943.6   345.3  4961.5  342.59  4964.3  342.09
  4967.5  342.59  4978.7  345.41  5020.3   350.3  5061.2  349.46  5111.5  349.24
  5121.7  353.11  5141.9   354.2  5162.2  352.81  5243.3  353.22  5565.2  356.63
  5737.6  357.22  5766.2  357.29  5988.4  360.02  6115.2  364.23  6216.6  370.48
#Mann= 10 ,-1 , 0
  4186.1      .1       0    4735     .05       0  4869.8     .12       0
  4961.5     .07       0  4967.5     .12       0  5061.2      .1       0
  5565.2     .05       0  5737.6      .1       0  5766.2     .05       0
  5988.4      .1       0
Bank Sta=4901,5020.3
XS Rating Curve= 0 ,0
Exp/Cntr=0.3,0.1

Type RM Length L Ch R = 1 ,11159   ,566,566,566
BEGIN DESCRIPTION:
PALO AMARILLO CREEK 12.0
END DESCRIPTION:
XS GIS Cut Line= 3
      2208564.23     13187987.44      2209367.16     13187097.71
      2210007.35     13185947.54
#Sta/Elev= 30
  4073.6  372.26  4416.3  359.33  4667.2  355.49  4810.8  354.23  4841.5  354.01
  4848.2  350.29  4855.6   353.5  4869.1  348.77  4876.6  346.15  4897.5  344.86
    4905  340.42  4908.7  340.38  4911.5  339.88  4914.7  340.38  4919.2  343.01
  4933.4  343.92  4982.7  342.28  5011.1  346.06  5039.5  346.98  5131.4  347.47
  5155.4  345.86  5166.6  343.63  5209.2  344.91  5216.6  352.68  5820.1  356.62
  5875.4  357.65  5997.8  359.98  6138.2  365.03  6391.5  378.39  6588.4  389.17
#Mann= 11 ,-1 , 0
  4073.6      .1       0  4667.2     .05       0  4810.8     .12       0
  4908.7     .07       0  4914.7     .12       0  5155.4      .1       0
  5820.1     .05       0  5875.4      .1       0  5997.8     .05       0
  6138.2      .1       0  6391.5     .16       0
Bank Sta=4869.1,5216.6
XS Rating Curve= 0 ,0
Exp/Cntr=0.3,0.1

Type RM Length L Ch R = 1 ,10593   ,454,454,454
BEGIN DESCRIPTION:
PALO AMARILLO CREEK 11.0
END DESCRIPTION:
XS GIS Cut Line= 3
      2208987.74     13188046.84      2209587.72     13187446.85
      2210587.69     13186246.89
#Sta/Elev= 30
  4151.5  360.59  4335.3  356.61  4655.2  353.74  4790.9  352.06  4864.4  350.22
  4943.4  348.38  4985.9  339.57  5004.2  339.41  5006.9  338.91  5010.2  339.41
  5013.7  341.55  5035.8   344.1  5042.3  348.81  5057.6  351.33    5183  352.19
  5447.1  351.68  5689.3  353.98    5833  357.86  6079.8  369.03  6314.1  383.29
  6334.9  385.76    6370  385.39  6377.9  386.13  6384.4  388.84  6437.9  392.75
  6486.5  394.91  6497.6  393.77  6526.3  395.27  6540.6   399.5    6562  401.65
#Mann= 11 ,-1 , 0
  4151.5      .1       0  4655.2     .05       0  4790.9      .1       0
  4864.4     .12       0  5004.2     .07       0  5010.2     .12       0
  5057.6      .1       0    5183     .05       0    5833      .1       0
  6437.9     .05       0  6486.5     .08       0
Bank Sta=4943.4,5042.3
XS Rating Curve= 0 ,0
Exp/Cntr=0.3,0.1

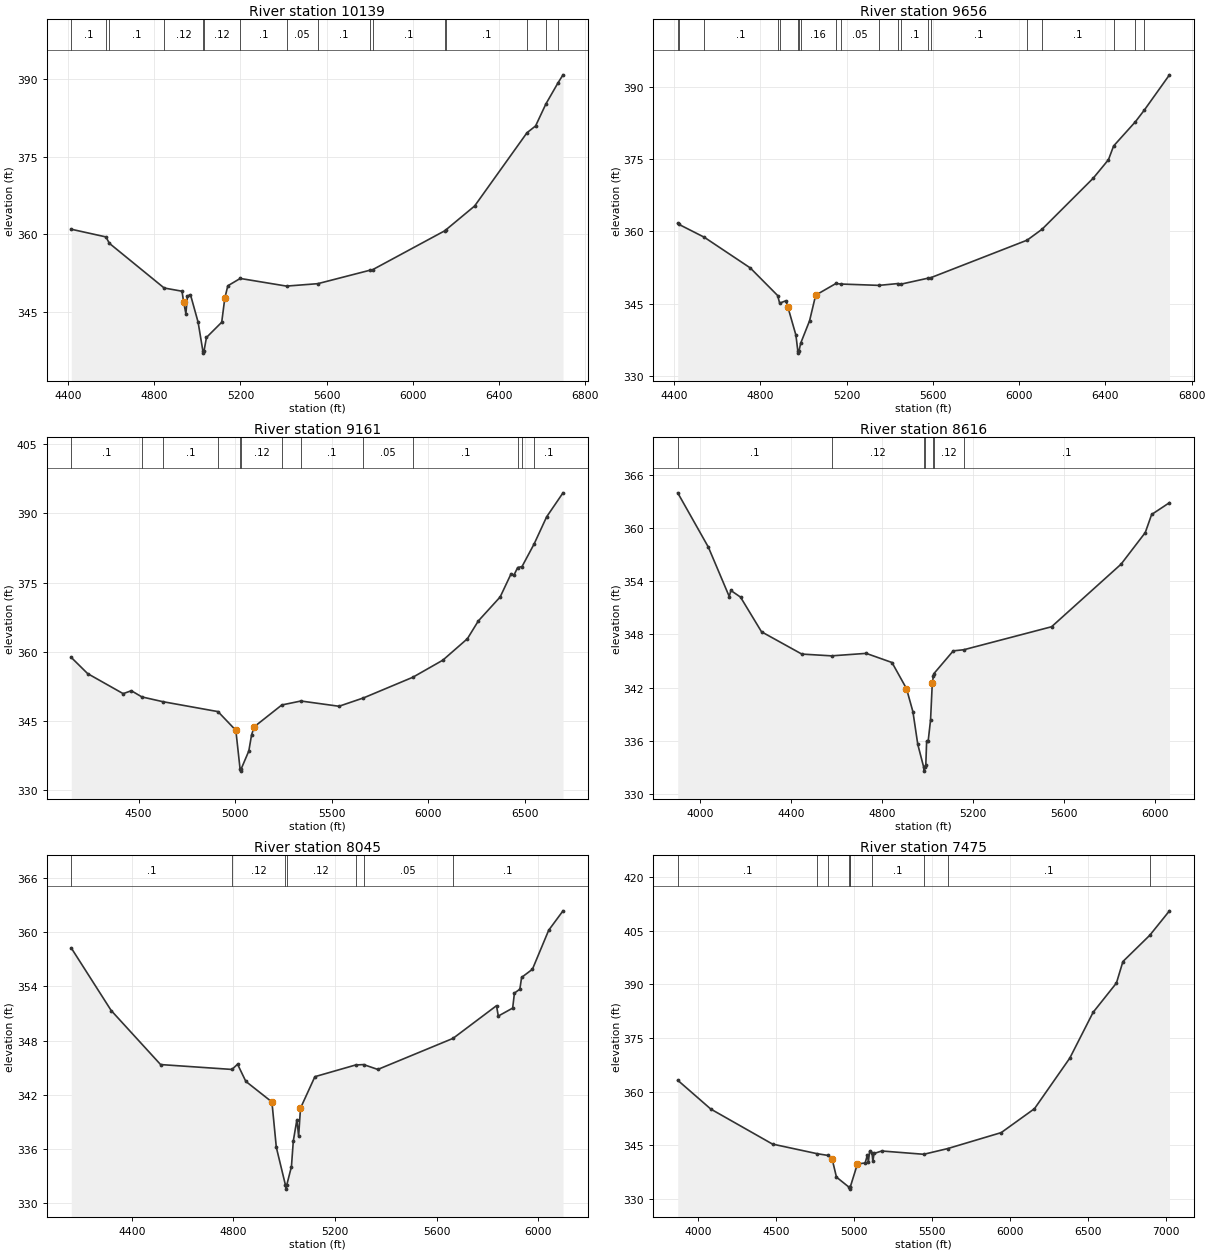
Type RM Length L Ch R = 1 ,10139   ,483,483,483
BEGIN DESCRIPTION:
PALO AMARILLO CREEK 10.0
END DESCRIPTION:
XS GIS Cut Line= 3
      2209637.73     13188346.82      2209837.72     13187796.85
      2211037.75     13186596.82
#Sta/Elev= 30
  4414.8  360.96    4576  359.47  4591.5  358.24    4846  349.58  4928.8  348.96
  4936.2  346.91  4946.8   344.6  4954.1  348.04  4968.1  348.29  5003.5  342.97
  5025.3  337.47    5028  336.97  5031.3  337.47  5042.4  340.01  5113.1  342.95
  5127.3  347.57  5141.4  350.01  5199.1  351.43  5413.8  349.95  5559.1  350.42
  5803.6  353.05  5814.7  353.15  6147.4  360.64  6152.7  360.81  6286.9  365.46
    6530  379.65  6569.8  380.96  6617.6  385.22  6673.1  389.25  6697.1  390.86
#Mann= 16 ,-1 , 0
  4414.8      .1       0    4576     .05       0  4591.5      .1       0
    4846     .12       0  5025.3     .07       0  5031.3     .12       0
  5199.1      .1       0  5413.8     .05       0  5559.1      .1       0
  5803.6     .05       0  5814.7      .1       0  6147.4     .05       0
  6152.7      .1       0    6530     .08       0  6617.6     .05       0
  6673.1      .1       0
Bank Sta=4936.2,5127.3
XS Rating Curve= 0 ,0
Exp/Cntr=0.3,0.1

Type RM Length L Ch R = 1 ,9656    ,495,495,495
BEGIN DESCRIPTION:
PALO AMARILLO CREEK 9.0
END DESCRIPTION:
XS GIS Cut Line= 3
      2209687.72     13188346.86      2210187.72     13188046.86
      2211387.75     13186846.82
#Sta/Elev= 30
  4416.9   361.7  4423.4  361.45  4539.9  358.81  4753.2  352.45  4880.4  346.72
  4889.5  345.14  4918.4  345.64  4928.1  344.28    4965  338.52  4973.7  335.29
  4976.4  334.79  4979.7  335.29  4986.9  336.82  5028.3  341.49  5056.6   346.8
  5150.5  349.22  5172.3  349.11  5350.2  348.83  5436.6   349.2  5453.9   349.1
  5579.7  350.34  5592.6  350.46  6037.1   358.2  6106.3  360.46  6343.5  371.04
  6414.2  374.87  6438.1  377.72  6539.2  382.74  6581.1  385.19  6697.1  392.46
#Mann= 20 ,-1 , 0
  4416.9      .1       0  4423.4     .05       0  4539.9      .1       0
  4880.4     .16       0  4889.5     .12       0  4973.7     .07       0
  4979.7     .12       0  4986.9     .16       0  5150.5     .12       0
  5172.3     .05       0  5350.2      .1       0  5436.6     .05       0
  5453.9      .1       0  5579.7     .05       0  5592.6      .1       0
  6037.1     .05       0  6106.3      .1       0  6438.1     .08       0
  6539.2     .05       0  6581.1      .1       0
Bank Sta=4928.1,5056.6
XS Rating Curve= 0 ,0
Exp/Cntr=0.3,0.1

Type RM Length L Ch R = 1 ,9161    ,545,545,545
BEGIN DESCRIPTION:
PALO AMARILLO CREEK 8.0
END DESCRIPTION:
XS GIS Cut Line= 3
      2209937.74     13188996.84      2210537.72     13188396.86
      2211737.75     13187196.82
#Sta/Elev= 30
  4151.5  358.75  4236.3  355.24  4420.2  350.89  4462.6  351.52  4516.9  350.18
    4625  349.15  4911.1  346.99  5003.5  342.93  5025.3  334.57    5028  334.07
  5031.3  334.57  5070.7  338.45  5084.9  341.94    5099  343.71  5241.5  348.43
  5340.3  349.29  5537.4  348.15  5664.2  349.96  5919.8  354.45  6074.8  358.15
  6202.1  362.81  6258.7  366.67  6371.8  371.88  6428.4  376.92  6442.5  376.57
  6462.5  378.27  6484.8  378.47  6548.1  383.43  6612.2  389.26  6697.1  394.48
#Mann= 13 ,-1 , 0
  4151.5      .1       0  4516.9     .16       0    4625      .1       0
  4911.1     .12       0  5025.3     .07       0  5031.3     .12       0
  5241.5     .05       0  5340.3      .1       0  5664.2     .05       0
  5919.8      .1       0  6462.5     .05       0  6484.8     .08       0
  6548.1      .1       0
Bank Sta=5003.5,5099
XS Rating Curve= 0 ,0
Exp/Cntr=0.3,0.1

Type RM Length L Ch R = 1 ,8616    ,571,571,571
BEGIN DESCRIPTION:
PALO AMARILLO CREEK 7.0
END DESCRIPTION:
XS GIS Cut Line= 3
      2210137.71     13189496.86      2210937.72     13188746.85
      2211737.71     13188046.86
#Sta/Elev= 30
  3903.4  363.94    4038  357.82  4129.8  352.25  4136.7  352.94  4179.2  352.19
  4271.5  348.28  4448.3  345.77    4579  345.57  4731.1  345.85  4844.4  344.82
  4907.9  341.89  4936.3  339.28  4957.7  335.59  4983.1  333.08  4985.8  332.58
  4989.1  333.08  4992.9  333.23  4996.6  335.96  5003.3  335.96  5013.8  338.35
  5021.4   342.5  5026.6  343.34  5028.9  343.58  5113.4  346.13  5160.1  346.26
  5545.3  348.85  5850.4   355.9  5956.7  359.46  5984.7   361.5    6063  362.83
#Mann= 7 ,-1 , 0
  3903.4      .1       0    4579     .12       0  4983.1     .07       0
  4989.1     .12       0  5026.6     .16       0  5028.9     .12       0
  5160.1      .1       0
Bank Sta=4907.9,5021.4
XS Rating Curve= 0 ,0
Exp/Cntr=0.3,0.1

Type RM Length L Ch R = 1 ,8045    ,570,570,570
BEGIN DESCRIPTION:
PALO AMARILLO CREEK 6.0
END DESCRIPTION:
XS GIS Cut Line= 3
      2210237.68     13189496.87      2211037.72     13189246.85
      2211837.73     13188496.85
#Sta/Elev= 30
  4161.8  358.26    4319  351.33  4513.3  345.35  4794.2  344.81  4816.1  345.39
  4848.6  343.49  4951.3  341.21  4968.6  336.19  5004.1  332.06  5006.8  331.56
  5010.1  332.06  5028.1  334.05  5035.4  336.88  5049.6  339.25  5056.4  337.41
  5063.7  340.52  5120.4  344.01  5280.2   345.3  5311.8  345.35    5368  344.81
  5663.9  348.25    5835  351.87  5841.9  350.72  5898.5   351.6  5905.4  353.26
  5926.8   353.7  5933.7     355  5976.2   355.9  6040.2  360.22  6096.6  362.37
#Mann= 7 ,-1 , 0
  4161.8      .1       0  4794.2     .12       0  5004.1     .07       0
  5010.1     .12       0  5280.2      .1       0  5311.8     .05       0
  5663.9      .1       0
Bank Sta=4951.3,5063.7
XS Rating Curve= 0 ,0
Exp/Cntr=0.3,0.1

Type RM Length L Ch R = 1 ,7475    ,583,583,583
BEGIN DESCRIPTION:
PALO AMARILLO CREEK 5.0
END DESCRIPTION:
XS GIS Cut Line= 3
       2210287.7     13190596.88      2211087.72     13189796.85
      2212637.73     13188496.85
#Sta/Elev= 30
  3868.6  363.24  4080.8  355.18  4476.7  345.39  4763.5   342.7  4834.1  342.21
  4858.6  341.31  4886.9  336.16  4968.7   333.3  4971.5   332.8  4974.7   333.3
  4975.2  333.36  5021.5  339.84  5070.9  340.11  5085.2  342.32  5091.7   340.4
  5099.5  343.38  5115.4  342.76  5120.4  340.57  5128.1  342.77  5177.6  343.46
    5447  342.54  5600.1  344.13  5943.9   348.6  6157.2  355.29  6383.6  369.42
  6533.2  382.22  6682.8  390.41  6724.4  396.42  6896.7  403.76    7023  410.59
#Mann= 10 ,-1 , 0
  3868.6      .1       0  4763.5     .16       0  4834.1      .1       0
  4968.7     .07       0  4974.7      .1       0  4975.2     .16       0
  5115.4      .1       0    5447     .12       0  5600.1      .1       0
  6896.7     .05       0
Bank Sta=4858.6,5021.5
XS Rating Curve= 0 ,0
Exp/Cntr=0.3,0.1

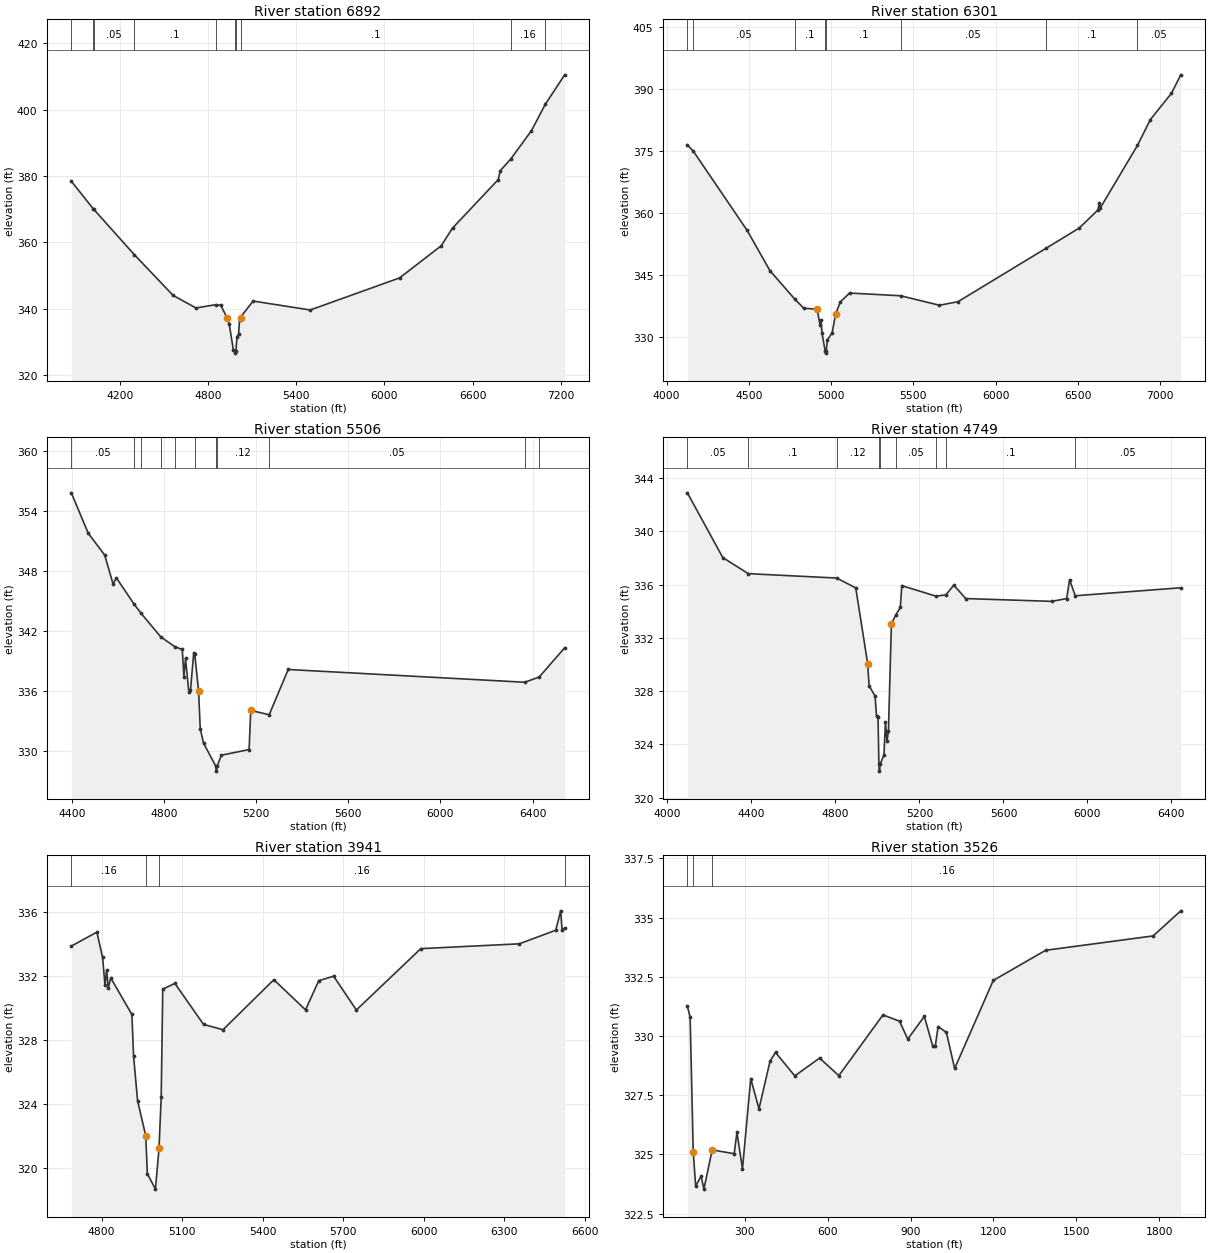
Type RM Length L Ch R = 1 ,6892    ,591,591,591
BEGIN DESCRIPTION:
PALO AMARILLO CREEK 4.0
END DESCRIPTION:
XS GIS Cut Line= 3
       2210487.7     13191096.88      2211287.72     13190296.85
      2212837.74     13188696.83
#Sta/Elev= 30
  3868.6  378.45  4018.9  370.08  4020.6  370.01  4297.3  356.32  4561.6  344.03
  4717.2  340.24    4854  341.25  4886.9     341  4929.3  337.23  4943.4  335.42
  4971.7  327.62  4982.9  327.13  4985.6  326.63  4988.9  327.13  4996.5  331.61
  5007.1  332.26    5014  336.61  5021.2  337.23  5022.8  337.58  5106.1  342.33
    5495  339.63  6103.2   349.3  6386.1  358.95  6463.8  364.31  6775.1  378.94
  6789.2  381.62  6861.4  385.21  7001.4  393.69  7095.8  401.65  7227.7  410.52
#Mann= 10 ,-1 , 0
  3868.6     .05       0  4018.9      .1       0  4020.6     .05       0
  4297.3      .1       0    4854     .16       0  4982.9     .07       0
  4988.9     .16       0  5022.8      .1       0  6861.4     .16       0
  7095.8      .1       0
Bank Sta=4929.3,5021.2
XS Rating Curve= 0 ,0
Exp/Cntr=0.3,0.1

Type RM Length L Ch R = 1 ,6301    ,795,795,795
BEGIN DESCRIPTION:
PALO AMARILLO CREEK 3.0
END DESCRIPTION:
XS GIS Cut Line= 3
      2210587.73     13191196.85      2211387.72     13190846.86
       2212787.7     13189246.88
#Sta/Elev= 30
  4126.8  376.46  4163.3  374.91  4490.5   355.8  4628.9   346.1  4779.7  339.25
  4834.3  337.05  4915.4  336.82  4933.3     333  4938.8  334.29  4945.4  330.97
  4964.6  326.72  4967.4  326.22  4970.6  326.72  4978.2  329.42  5007.1  331.16
    5028  335.68  5056.5   338.6  5113.4  340.71  5423.1  340.06  5659.2  337.77
  5772.1  338.63  6305.4  351.47  6509.6  356.41  6622.5  360.75  6630.1  362.36
  6636.8  361.24  6862.6  376.31  6941.4  382.56  7069.6   388.9    7126  393.35
#Mann= 8 ,-1 , 0
  4126.8      .1       0  4163.3     .05       0  4779.7      .1       0
  4964.6     .07       0  4970.6      .1       0  5423.1     .05       0
  6305.4      .1       0  6862.6     .05       0
Bank Sta=4915.4,5028
XS Rating Curve= 0 ,0
Exp/Cntr=0.3,0.1

Type RM Length L Ch R = 1 ,5506    ,757,757,757
BEGIN DESCRIPTION:
PALO AMARILLO CREEK 2.0
END DESCRIPTION:
XS GIS Cut Line= 4
      2211042.23     13191873.29      2211354.76     13191657.99
      2211993.65     13190984.38      2212528.34     13190345.53
#Sta/Elev= 30
  4398.4  355.85  4471.7   351.8  4543.3  349.61  4579.2  346.73  4594.1  347.32
  4671.3  344.67  4699.1  343.83  4786.5  341.41  4847.7  340.42  4879.8  340.15
    4887  337.42  4893.9  339.26  4908.1  335.92  4915.3  336.04  4929.5  339.79
  4933.8  339.71  4950.5  336.01  4957.8  332.22    4972  330.76  5025.2  328.45
    5028  327.95  5031.2  328.45  5049.6  329.55  5169.8  330.11  5177.1  334.04
  5256.9   333.6  5339.7  338.14  6366.3  336.86  6428.5  337.38  6539.4  340.32
#Mann= 11 ,-1 , 0
  4398.4     .05       0  4671.3     .12       0  4699.1     .05       0
  4786.5     .12       0  4847.7     .05       0  4933.8     .12       0
  5025.2     .07       0  5031.2     .12       0  5256.9     .05       0
  6366.3      .1       0  6428.5     .05       0
Bank Sta=4950.5,5177.1
XS Rating Curve= 0 ,0
Exp/Cntr=0.3,0.1

Type RM Length L Ch R = 1 ,4749    ,808,808,808
BEGIN DESCRIPTION:
Mapping XS 58179592
END DESCRIPTION:
XS GIS Cut Line= 3
      2211361.69     13192151.06      2211854.76     13191852.44
      2213111.68     13190602.46
#Sta/Elev= 30
    4095   342.9  4263.5  338.04  4384.9  336.83  4806.1   336.5  4896.7  335.76
  4953.3  330.08  4960.3   328.4  4988.6  327.64  4995.7  326.11  5002.8  326.07
  5006.8   322.5  5009.6     322  5012.8   322.5    5031  323.23  5038.1  325.69
  5045.2  324.23  5052.3     325  5066.4  333.06  5087.4  333.73  5108.8  334.29
  5115.9  335.93  5278.6  335.14  5326.2  335.24  5363.4  335.97    5420  334.96
  5830.1  334.75  5900.8  334.96  5914.9  336.37  5941.8  335.17  6444.1  335.77
#Mann= 9 ,-1 , 0
    4095     .05       0  4384.9      .1       0  4806.1     .12       0
  5006.8     .07       0  5012.8     .12       0  5087.4     .05       0
  5278.6     .12       0  5326.2      .1       0  5941.8     .05       0
Bank Sta=4953.3,5066.4
XS Rating Curve= 0 ,0
Exp/Cntr=0.3,0.1

Type RM Length L Ch R = 1 ,3941    ,372,372,372
BEGIN DESCRIPTION:
Mapping XS 46775ed1
END DESCRIPTION:
XS GIS Cut Line= 3
      2212451.98     13192442.72      2212778.37     13191928.83
      2213146.44     13190755.17
#Sta/Elev= 30
  4687.3  333.88  4782.5  334.75  4803.7  333.18  4812.7  331.46  4818.9   332.4
  4824.9  331.25  4834.2  331.89    4913  329.61  4919.3     327  4934.1  324.24
  4964.6  322.04  4970.6  319.67  5000.8  318.71  5014.1  321.25  5022.2  324.43
  5028.1  331.19  5073.3  331.55    5180  328.99  5252.6  328.66    5442  331.78
  5560.2   329.9  5609.4  331.72    5665     332  5749.6  329.89  5989.8  333.72
  6356.7  334.02  6492.9  334.87  6511.1  336.08  6516.4  334.88  6526.1  335.01
#Mann= 4 ,-1 , 0
  4687.3     .16       0  4964.6     .07       0  5014.1     .16       0
  6526.1      .1       0
#XS Ineff= 2 , 0
       0                 5073.86       0  331.52
Permanent Ineff=
       F       T
Bank Sta=4964.6,5014.1
XS Rating Curve= 0 ,0
Exp/Cntr=0.3,0.1

Type RM Length L Ch R = 1 ,3526    ,1359,1359,1359
XS GIS Cut Line= 4
     2212720.619    13192558.571      2212800.48    13192508.223
     2212817.841    13191937.043     2213182.425    13190770.376
#Sta/Elev= 30
91.73914331.2626101.7133330.7943  112.95   325.1121.6616323.6679141.6098324.0772
 151.584323.5318   181.5325.1882261.2996325.0275271.2737325.9365 291.222324.3827
321.1444328.1952351.0668326.9239390.9634328.9284410.9117329.3077480.7307328.3131
 570.498329.0666 640.317328.3251800.0594330.8901859.9764330.6227889.9348329.8688
949.8517330.8262979.8102329.5966989.7964329.5864999.7825330.39891029.741330.1507
1059.699328.62711199.506332.34461389.243333.61821778.703334.22531878.564 335.285
#Mann= 3 , 0 , 0
91.73914     .16       0  112.95     .07       0   181.5     .16       0
Bank Sta=112.95,181.5
XS Rating Curve= 0 ,0
Exp/Cntr=0.3,0.1

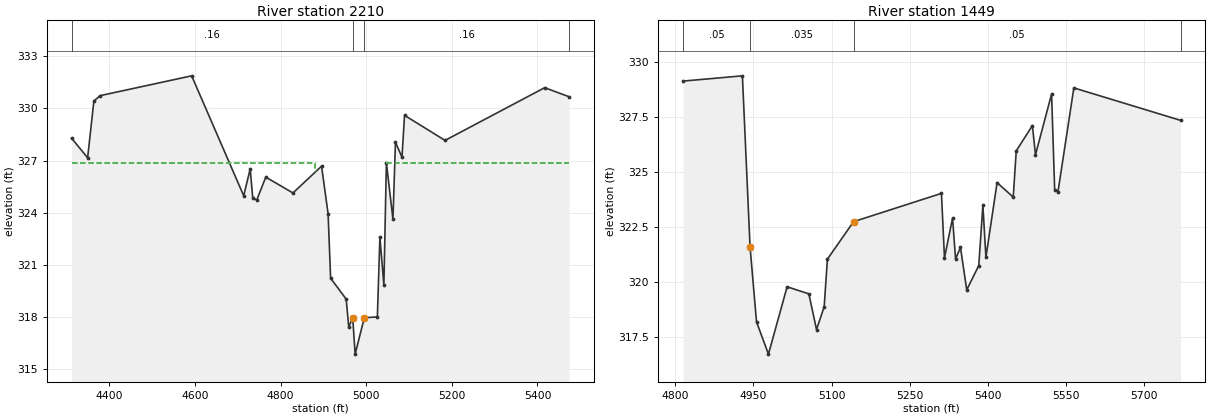
Type RM Length L Ch R = 1 ,2210    ,761,761,761
BEGIN DESCRIPTION:
Mapping XS 65025707
END DESCRIPTION:
XS GIS Cut Line= 3
      2212833.94     13192595.48      2213090.87     13192401.05
      2213542.24     13191692.74
#Sta/Elev= 30
  4311.5  328.29  4349.1  327.16  4363.7  330.42  4378.2  330.73  4592.1  331.87
  4713.7  324.98  4728.9  326.52  4734.8  324.87  4744.1  324.73  4765.3  326.05
  4828.8  325.14  4895.6  326.68  4910.9  323.95  4916.8  320.24  4953.2  319.04
  4959.1  317.44  4968.4  317.97  4974.1  315.88  4995.5  317.97    5026  318.02
  5031.9   322.6  5041.2  319.84  5047.1  326.87  5062.4  323.63  5068.3  328.06
  5083.5  327.19  5089.5   329.6  5184.1  328.16    5417  331.19  5473.6  330.67
#Mann= 4 ,-1 , 0
  4311.5     .16       0  4968.4     .07       0  4995.5     .16       0
  5473.6     .05       0
#XS Ineff= 2 , 0
       0 4880.11  326.89 5047.16       0  326.87
Permanent Ineff=
       T       T
Bank Sta=4968.4,4995.5
XS Rating Curve= 0 ,0
Exp/Cntr=0.3,0.1

Type RM Length L Ch R = 1 ,1449    ,0,0,0
BEGIN DESCRIPTION:
PALO AMARILLO CREEK 1.0
END DESCRIPTION:
XS GIS Cut Line= 3
      2213083.91     13192901.06      2213389.48     13192678.83
      2213688.11     13192185.74
#Sta/Elev= 30
  4815.3  329.15    4929  329.39  4943.7  321.59  4956.1  318.17    4979   316.7
  5014.8  319.77  5056.5  319.45  5071.2  317.82  5085.9  318.86  5092.1  321.03
  5142.3  322.74  5310.9  324.03  5316.7  321.09  5332.2   322.9    5338  321.04
  5347.4  321.57  5359.4  319.63  5382.5  320.74  5390.4  323.49  5396.2  321.11
  5417.6  324.52  5448.6  323.86  5454.4  325.97  5485.4  327.12  5491.3  325.79
  5522.2  328.56  5528.1   324.2  5534.5  324.11  5564.9  328.84  5769.6  327.36
#Mann= 4 ,-1 , 0
  4815.3     .05       0  4943.7    .035       0  5142.3     .05       0
  5769.6      .1       0
Bank Sta=4943.7,5142.3
XS Rating Curve= 0 ,0
Exp/Cntr=0.3,0.1

Chan Stop Cuts=-1
Use User Specified Reach Order=0
Composite Channel Slope=5