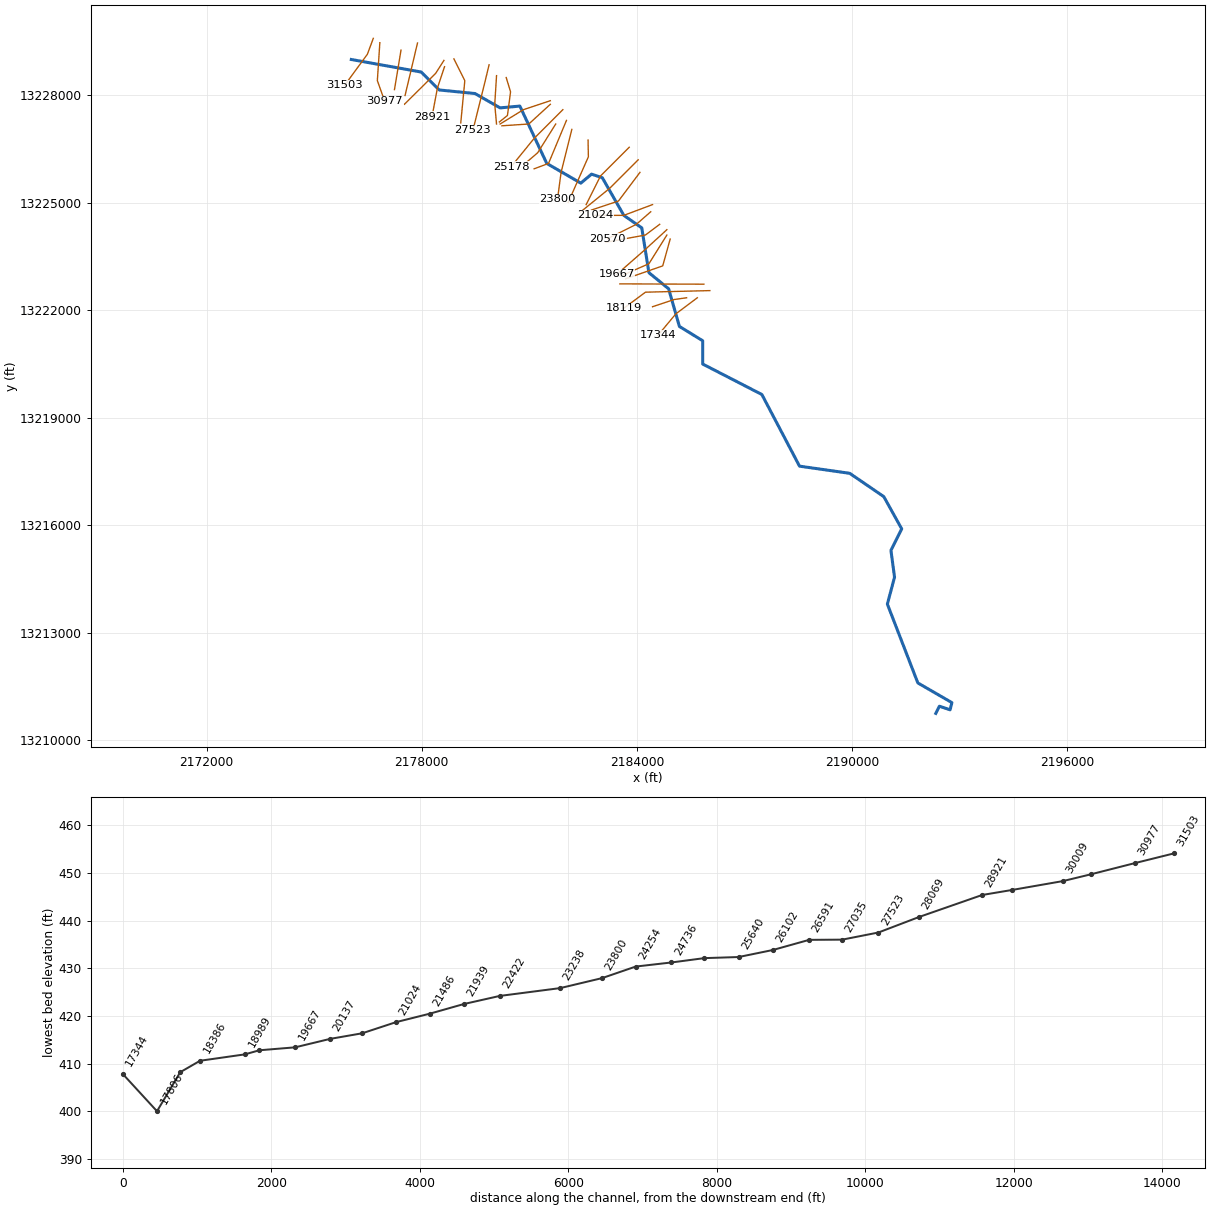
--- TEPECATE CREEK.prj (project) ---

Proj Title=TEPECATE CREEK Base Level Engineering
Current Plan=p01
Default Exp/Contr=0.3,0.1
English Units
Geom File=g01
Flow File=f01
Plan File=p01
Y Axis Title=Elevation
X Axis Title(PF)=Main Channel Distance
X Axis Title(XS)=Station
BEGIN DESCRIPTION:
TEPECATE CREEK
END DESCRIPTION:
DSS Export Rating Curves= 0
DSS Export Rating Curve Sorted= 0
DSS Export Volume Flow Curves= 0
DXF OffsetX= 0
DXF OffsetY= 0
DXF ScaleX= 1
DXF ScaleY= 10

--- TEPECATE CREEK.p01 (plan) ---

Plan Title=Multiple Run
Short Identifier=Multiple
Geom File=g01
Flow File=f01
Subcritical Flow
K Sum by GR= 0
Std Step Tol= 0.01
Critical Tol= 0.01
Num of Std Step Trials= 20
Max Error Tol= 0.3
Flow Tol Ratio= 0.001
Split Flow NTrial= 30
Split Flow Tol= 0.02
Split Flow Ratio= 0.02
Log Output Level= 0
Friction Slope Method= 1
Unsteady Friction Slope Method= 2
Unsteady Bridges Friction Slope Method= 1
Parabolic Critical Depth
Global Vel Dist=  1 , 1 , 1
Global Log Level= 0
CheckData=True
Encroach Param= -1, 0, 0, 0
BEGIN DESCRIPTION:
Multiple Run
END DESCRIPTION:

--- TEPECATE CREEK.f01 (steady flow) ---

Flow Title=Multiple
Program Version=4.10
Number of Profiles= 7
Profile Names=10-year,25-year,50-year,1pct_min,100-year,1pct_plu,500-year
River Rch & RM=TEPECATE CREEK,Reach-1         ,31503
     198     275     340     309     418     565     642
River Rch & RM=TEPECATE CREEK,Reach-1         ,30977
     290     411     513     471     636     861     996
River Rch & RM=TEPECATE CREEK,Reach-1         ,26102
     374     534     671     620     838    1134    1328
River Rch & RM=TEPECATE CREEK,Reach-1         ,23238
     416     595     748     689     932    1261    1475
River Rch & RM=TEPECATE CREEK,Reach-1         ,18386
     519     751     950     882    1193    1613    1913
River Rch & RM=TEPECATE CREEK,Reach-1         ,18119
     519     751     950     882    1193    1613    1913
River Rch & RM=TEPECATE CREEK,Reach-1         ,16206
     568     823    1043     969    1310    1772    2104
River Rch & RM=TEPECATE CREEK,Reach-1         ,8913
     682     994    1263    1178    1592    2154    2573
River Rch & RM=TEPECATE CREEK,Reach-1         ,8460
     682     994    1263    1178    1592    2154    2573
Boundary for River Rch & Prof#=TEPECATE CREEK,Reach-1         , 1
Up Type= 0
Dn Type= 3
Dn Slope=0.002
Boundary for River Rch & Prof#=TEPECATE CREEK,Reach-1         , 2
Up Type= 0
Dn Type= 3
Dn Slope=0.002
Boundary for River Rch & Prof#=TEPECATE CREEK,Reach-1         , 3
Up Type= 0
Dn Type= 3
Dn Slope=0.002
Boundary for River Rch & Prof#=TEPECATE CREEK,Reach-1         , 4
Up Type= 0
Dn Type= 3
Dn Slope=0.002
Boundary for River Rch & Prof#=TEPECATE CREEK,Reach-1         , 5
Up Type= 0
Dn Type= 3
Dn Slope=0.002
Boundary for River Rch & Prof#=TEPECATE CREEK,Reach-1         , 6
Up Type= 0
Dn Type= 3
Dn Slope=0.002
Boundary for River Rch & Prof#=TEPECATE CREEK,Reach-1         , 7
Up Type= 0
Dn Type= 3
Dn Slope=0.002
DSS Import GetInterval= 0
DSS Import GetPeak= 0
DSS Import FillOption= 0

--- TEPECATE CREEK.g01 (geometry) ---

Geom Title=Existing Conditions
Program Version=4.10

River Reach=TEPECATE CREEK  ,Reach-1
Reach XY= 30
      2176037.72     13228996.85      2177987.72     13228646.85
      2178487.72     13228146.85      2179487.72     13228046.85
      2180187.72     13227646.85      2180737.72     13227696.85
      2181487.72     13226096.86      2182437.72     13225546.85
      2182737.72     13225796.86      2183037.72     13225696.85
      2183637.72     13224646.86      2184137.72     13224296.86
      2184337.72     13223046.85      2184887.72     13222596.85
      2185187.72     13221546.85      2185837.72     13221146.85
      2185837.72     13220496.85      2187487.72     13219646.85
      2188537.72     13217646.85      2189937.72     13217446.85
      2190887.72     13216796.85      2191387.72     13215896.85
      2191087.72     13215296.86      2191187.72     13214546.85
      2190987.72     13213796.86      2191837.72     13211596.85
      2192787.72     13211046.85      2192737.72     13210846.86
      2192437.72     13210946.85      2192337.72     13210746.85

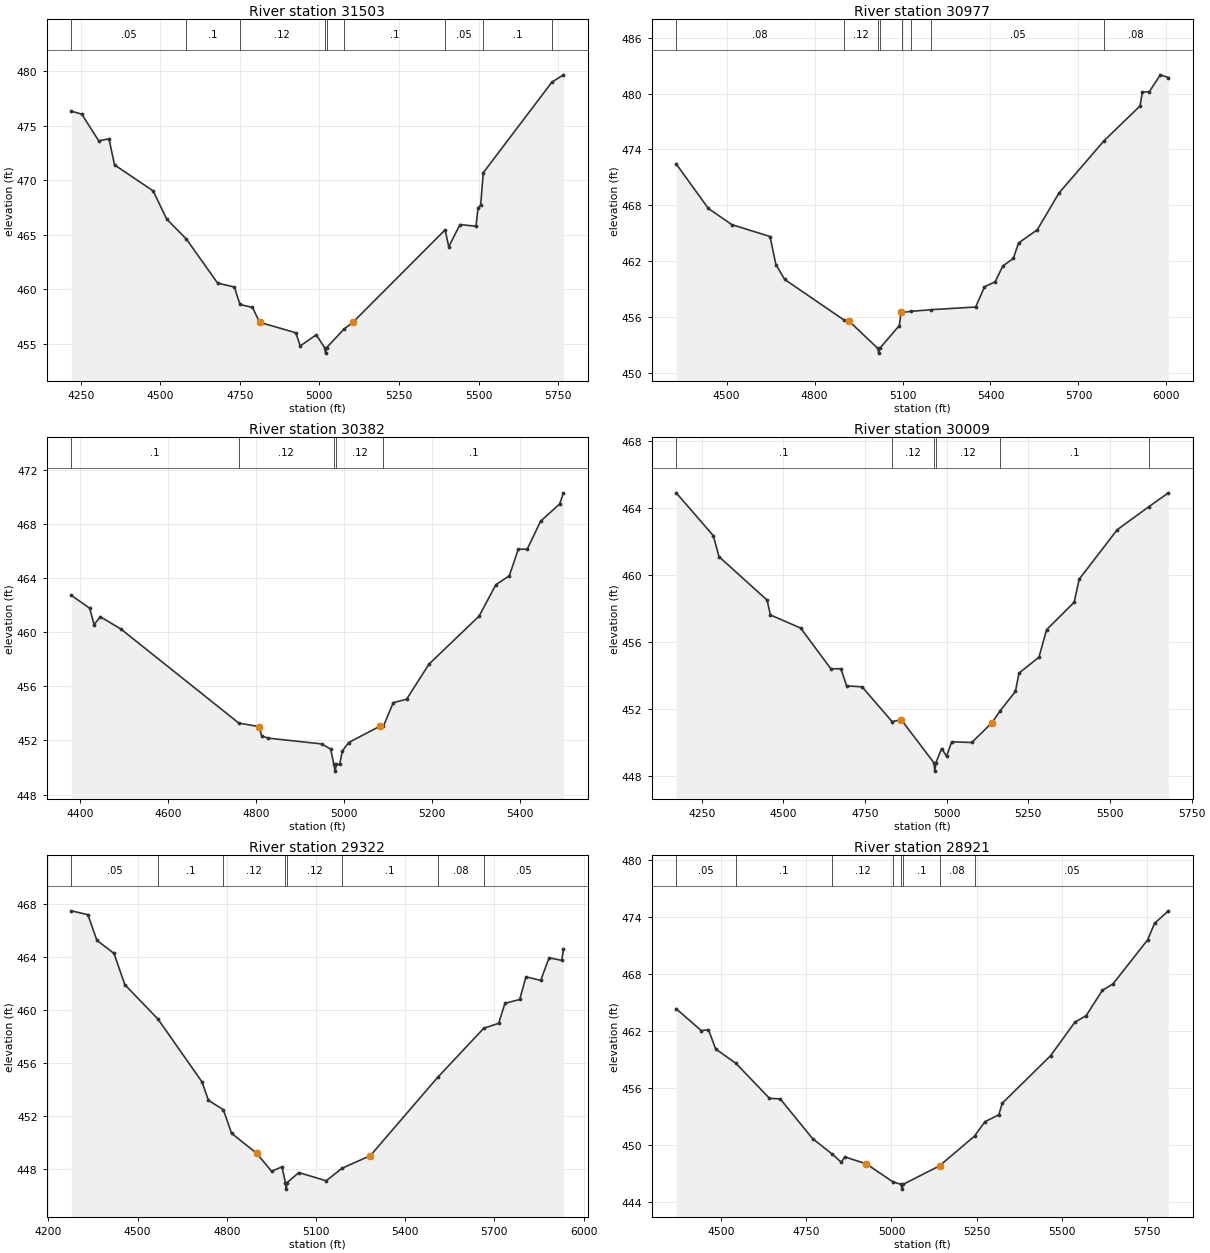
Type RM Length L Ch R = 1 ,31503   ,526,526,526
BEGIN DESCRIPTION:
TEPECATE CREEK 62.0
END DESCRIPTION:
XS GIS Cut Line= 3
       2176650.7     13229587.82      2176485.76     13229145.09
      2175852.38     13228277.44
#Sta/Elev= 30
  4220.2  476.35  4253.2  476.08  4306.6  473.62  4338.6  473.82  4356.1  471.42
  4477.5  469.03    4520  466.44  4582.1   464.6  4680.1  460.56  4732.8   460.2
  4750.3   458.6  4789.5  458.33  4812.3  456.96  4925.7     456  4939.8  454.79
    4990  455.81  5016.3  454.63  5019.1  454.13  5022.3  454.63  5078.1  456.36
  5105.1  456.96  5394.9  465.45  5406.3  463.91  5441.8  465.94    5492  465.78
  5498.2  467.42  5506.7  467.75  5514.9   470.7  5730.5  479.02  5766.9  479.69
#Mann= 9 ,-1 , 0
  4220.2     .05       0  4582.1      .1       0  4750.3     .12       0
  5016.3     .07       0  5022.3     .12       0  5078.1      .1       0
  5394.9     .05       0  5514.9      .1       0  5730.5     .05       0
Bank Sta=4812.3,5105.1
XS Rating Curve= 0 ,0
Exp/Cntr=0.3,0.1

Type RM Length L Ch R = 1 ,30977   ,595,595,595
BEGIN DESCRIPTION:
TEPECATE CREEK 60.0
END DESCRIPTION:
XS GIS Cut Line= 3
      2176832.98     13229466.23      2176763.54     13228407.24
      2176971.86     13227825.69
#Sta/Elev= 30
  4327.9  472.44  4437.5  467.65  4517.7  465.91    4648  464.63    4668  461.61
  4698.1  460.01    4899  455.68  4918.5  455.51  5015.8  452.59  5018.5  452.09
  5021.8  452.59  5088.9  455.05    5095  456.46  5097.4  456.46  5128.6  456.58
  5196.7  456.76  5349.5  457.05  5379.5  459.22  5416.3  459.78  5441.7  461.45
  5477.8  462.27  5495.8  463.94  5559.4  465.35  5633.9  469.32  5787.6  474.94
  5910.1  478.67  5917.9  480.15  5941.9  480.22  5979.5  482.02  6006.9  481.73
#Mann= 8 ,-1 , 0
  4327.9     .08       0    4899     .12       0  5015.8     .07       0
  5021.8     .12       0  5097.4     .05       0  5128.6      .1       0
  5196.7     .05       0  5787.6     .08       0
Bank Sta=4918.5,5095
XS Rating Curve= 0 ,0
Exp/Cntr=0.3,0.1

Type RM Length L Ch R = 1 ,30382   ,373,373,373
BEGIN DESCRIPTION:
TEPECATE CREEK 59.0
END DESCRIPTION:
XS GIS Cut Line= 2
      2177423.27     13229257.96      2177240.98     13228155.53
#Sta/Elev= 30
  4380.6  462.73  4422.3  461.78  4432.4  460.56  4446.4  461.15  4493.2  460.24
    4761  453.28  4807.4  453.02  4812.8  452.33  4827.7  452.17  4949.3  451.74
  4969.6  451.35  4976.7  450.23  4979.5  449.73  4982.7  450.23  4989.9  450.23
  4995.9  451.21  5010.1  451.84  5081.1  453.05  5089.2  453.05  5111.5  454.79
  5141.9  455.05  5192.6  457.64  5306.3  461.19  5344.6  463.52    5375  464.17
  5395.3  466.14  5415.6  466.14    5446  468.21  5489.4  469.49    5498  470.31
#Mann= 5 ,-1 , 0
  4380.6      .1       0    4761     .12       0  4976.7     .07       0
  4982.7     .12       0  5089.2      .1       0
Bank Sta=4807.4,5081.1
XS Rating Curve= 0 ,0
Exp/Cntr=0.3,0.1

Type RM Length L Ch R = 1 ,30009   ,687,687,687
BEGIN DESCRIPTION:
TEPECATE CREEK 58.0
END DESCRIPTION:
XS GIS Cut Line= 2
      2177883.33     13229457.57      2177536.26     13227991.18
#Sta/Elev= 30
  4171.9  464.93  4285.7  462.37  4302.9  461.12  4450.1  458.53  4460.4  457.64
  4552.9  456.86  4645.3  454.43  4676.2  454.43  4693.6  453.41    4741  453.35
  4832.6  451.28  4861.1  451.38  4960.9  448.82  4963.7  448.32  4966.9  448.82
  4984.5  449.67  4999.7  449.21  5015.3  450.07  5076.9  450.03  5138.6  451.21
  5164.1  451.93  5210.5  453.08  5221.3  454.17  5282.5  455.12  5305.8  456.76
  5390.3   458.4  5405.8  459.78  5522.2  462.73  5619.4  464.11  5678.8  464.93
#Mann= 6 ,-1 , 0
  4171.9      .1       0  4832.6     .12       0  4960.9     .07       0
  4966.9     .12       0  5164.1      .1       0  5619.4     .08       0
Bank Sta=4861.1,5138.6
XS Rating Curve= 0 ,0
Exp/Cntr=0.3,0.1

Type RM Length L Ch R = 1 ,29322   ,401,401,401
BEGIN DESCRIPTION:
TEPECATE CREEK 57.0
END DESCRIPTION:
XS GIS Cut Line= 3
      2178621.17     13228971.46      2178386.81      13228606.9
      2177518.75     13227747.52
#Sta/Elev= 30
  4277.3  467.45  4333.1  467.16  4363.5  465.22  4420.9  464.24  4457.3  461.88
  4568.9  459.28  4717.2  454.53  4738.3  453.15  4788.7  452.44  4816.2  450.66
    4901  449.15  4950.5   447.8  4985.9  448.13    4997  446.95  4999.8  446.45
    5003  446.95  5042.4   447.7  5134.3  447.08  5188.1  448.03  5282.9  448.98
    5509  454.88  5664.1  458.59  5714.2  458.96  5735.4  460.47  5784.9  460.76
  5806.1  462.47  5855.6   462.2  5883.9  463.91  5926.3  463.71  5932.2  464.57
#Mann= 8 ,-1 , 0
  4277.3     .05       0  4568.9      .1       0  4788.7     .12       0
    4997     .07       0    5003     .12       0  5188.1      .1       0
    5509     .08       0  5664.1     .05       0
Bank Sta=4901,5282.9
XS Rating Curve= 0 ,0
Exp/Cntr=0.3,0.1

Type RM Length L Ch R = 1 ,28921   ,852,852,852
BEGIN DESCRIPTION:
TEPECATE CREEK 56.0
END DESCRIPTION:
XS GIS Cut Line= 3
      2178637.73      13228796.9      2178437.72     13228196.85
      2178287.73      13227396.9
#Sta/Elev= 30
  4367.5  464.37  4441.3  462.07  4462.4  462.17  4483.5  460.14  4543.4  458.62
  4641.6  454.95  4673.2  454.89  4768.1  450.72  4826.4  449.07  4852.4  448.23
    4863  448.79  4926.2  448.06  5004.1  446.17  5028.4   445.9  5031.1   445.4
  5034.4   445.9  5142.4  447.87    5143   447.9  5244.1  450.98  5274.7  452.49
  5315.4  453.22  5325.6  454.43    5468  459.45  5539.2  462.96  5572.3  463.65
  5619.8  466.31  5651.2  466.99  5752.9  471.62  5773.2  473.36  5813.9  474.67
#Mann= 8 ,-1 , 0
  4367.5     .05       0  4543.4      .1       0  4826.4     .12       0
  5004.1      .1       0  5028.4     .07       0  5034.4      .1       0
    5143     .08       0  5244.1     .05       0
Bank Sta=4926.2,5142.4
XS Rating Curve= 0 ,0
Exp/Cntr=0.3,0.1

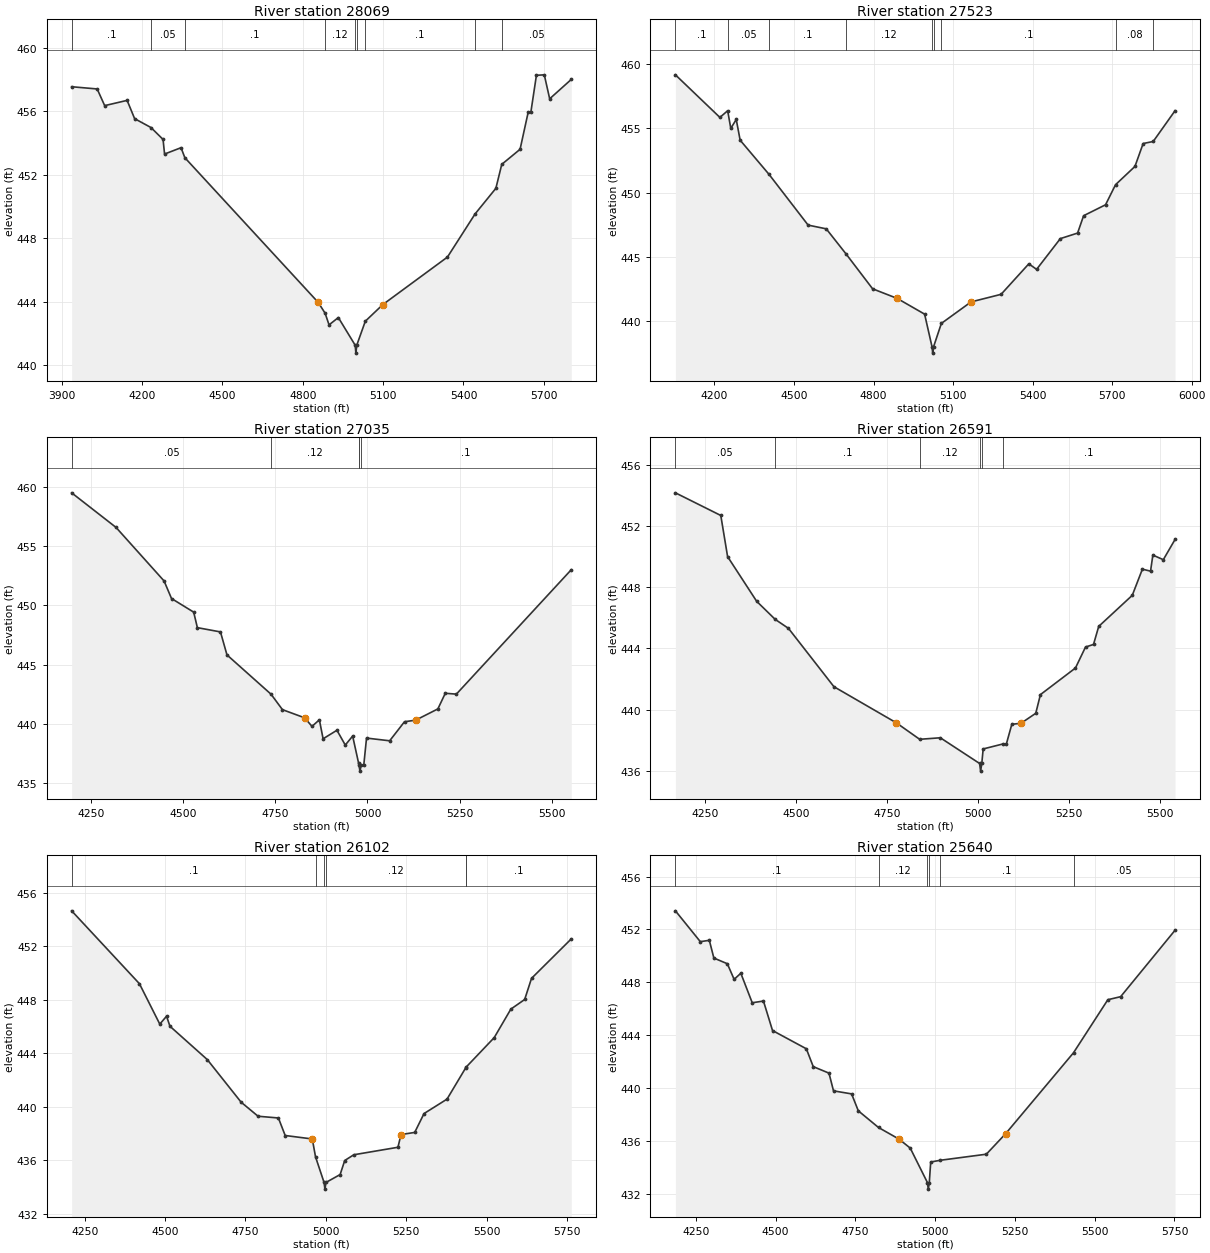
Type RM Length L Ch R = 1 ,28069   ,546,546,546
BEGIN DESCRIPTION:
TEPECATE CREEK 54.0
END DESCRIPTION:
XS GIS Cut Line= 3
      2178898.97     13229014.85      2179202.78     13228407.24
      2179089.93     13227226.66
#Sta/Elev= 30
  3937.1  457.55  4032.4  457.41  4060.4  456.36  4144.2  456.69  4172.2  455.54
  4233.3  454.98  4278.4  454.23    4284  453.31  4345.5  453.71  4359.7  453.08
  4857.9  443.96  4883.5  443.28  4898.1  442.55  4932.8  443.01  4995.6  441.27
  4998.3  440.77  5001.6  441.27  5033.5  442.78    5099  443.83  5340.1  446.82
  5443.4  449.54  5520.9  451.15  5542.9  452.66  5611.3  453.61  5641.5  455.94
  5651.5  455.94  5672.3  458.27  5701.7   458.3  5721.8  456.79  5802.4  458.01
#Mann= 9 ,-1 , 0
  3937.1      .1       0  4233.3     .05       0  4359.7      .1       0
  4883.5     .12       0  4995.6     .07       0  5001.6     .12       0
  5033.5      .1       0  5443.4     .08       0  5542.9     .05       0
Bank Sta=4857.9,5099
XS Rating Curve= 0 ,0
Exp/Cntr=0.3,0.1

Type RM Length L Ch R = 1 ,27523   ,488,488,488
BEGIN DESCRIPTION:
TEPECATE CREEK 53.0
END DESCRIPTION:
XS GIS Cut Line= 3
      2179879.86     13228849.92      2179758.33     13228346.48
       2179428.9     13227020.08
#Sta/Elev= 30
  4052.7  459.15  4220.5  455.84  4249.8  456.36  4261.6  454.99  4282.2  455.68
  4296.9  454.07    4406  451.41  4553.3  447.47  4621.7  447.18  4697.1  445.21
  4796.5  442.52  4889.6  441.77  4992.7  440.55  5020.6  438.02  5023.3  437.52
  5026.6  438.02  5055.9  439.83  5167.8   441.5  5281.2  442.09  5385.8  444.46
  5415.1  444.03  5504.7  446.42  5569.7  446.85  5592.5   448.2  5675.2  449.05
  5712.9  450.61  5786.1  452.03    5817  453.81    5855  453.97  5937.3  456.36
#Mann= 9 ,-1 , 0
  4052.7      .1       0  4249.8     .05       0    4406      .1       0
  4697.1     .12       0  5020.6     .07       0  5026.6     .12       0
  5055.9      .1       0  5712.9     .08       0    5855     .05       0
Bank Sta=4889.6,5167.8
XS Rating Curve= 0 ,0
Exp/Cntr=0.3,0.1

Type RM Length L Ch R = 1 ,27035   ,444,444,444
BEGIN DESCRIPTION:
TEPECATE CREEK 52.0
END DESCRIPTION:
XS GIS Cut Line= 3
      2180087.72     13228546.89      2180037.72     13227746.86
      2180087.72     13227196.82
#Sta/Elev= 30
  4198.4  459.51  4318.7  456.59  4448.9  452.07    4469  450.59  4529.1  449.44
  4539.1  448.13  4601.7  447.77  4619.3  445.83  4738.8  442.51  4769.6  441.21
  4829.7  440.52  4849.7   439.8  4869.7  440.35  4879.8  438.75  4917.3  439.47
  4939.9  438.22  4959.9  438.98  4975.8  436.72    4977  436.52  4979.7  436.02
    4983  436.52    4990  436.52  4997.5  438.81  5060.2  438.58  5100.4  440.19
  5130.5  440.32  5190.8  441.27  5210.9  442.59    5241  442.52  5552.3  453.02
#Mann= 5 ,-1 , 0
  4198.4     .05       0  4738.8     .12       0  4975.8      .1       0
    4977     .07       0    4983      .1       0
Bank Sta=4829.7,5130.5
XS Rating Curve= 0 ,0
Exp/Cntr=0.3,0.1

Type RM Length L Ch R = 1 ,26591   ,489,489,489
BEGIN DESCRIPTION:
TEPECATE CREEK 51.0
END DESCRIPTION:
XS GIS Cut Line= 4
      2180357.29     13228494.07      2180478.82     13228094.74
      2180392.01     13227435.02      2180166.35     13227252.75
#Sta/Elev= 30
  4168.2  454.17  4292.9  452.69  4311.6     450  4391.5  447.08  4442.3   445.9
  4478.9  445.31  4603.7   441.5  4775.1  439.14  4839.4  438.06  4896.2  438.16
  5004.1  436.48  5006.9  435.98  5010.1  436.48  5013.9  437.43  5067.2  437.75
  5077.7  437.76  5092.6  439.04    5118  439.11  5158.4  439.76  5171.2  440.98
  5267.5  442.72  5295.1  444.09  5317.1  444.26  5331.4  445.44  5423.6  447.47
  5451.4  449.18  5473.8  449.05  5480.2   450.1  5508.9   449.8  5541.1  451.12
#Mann= 6 ,-1 , 0
  4168.2     .05       0  4442.3      .1       0  4839.4     .12       0
  5004.1     .07       0  5010.1     .12       0  5067.2      .1       0
Bank Sta=4775.1,5118
XS Rating Curve= 0 ,0
Exp/Cntr=0.3,0.1

Type RM Length L Ch R = 1 ,26102   ,462,462,462
BEGIN DESCRIPTION:
TEPECATE CREEK 50.0
END DESCRIPTION:
XS GIS Cut Line= 3
      2181587.75     13227846.86      2180837.72     13227596.86
      2180187.73     13227196.86
#Sta/Elev= 30
  4209.4  454.66  4420.2  449.21  4483.5  446.19  4504.6  446.78  4515.1  446.03
  4631.1  443.54  4736.5  440.35  4789.2   439.3  4852.4  439.17  4873.5  437.86
  4957.8   437.6  4967.9  436.26  4994.4  434.35  4997.1  433.85  5000.4  434.35
  5044.4  434.94  5058.7  435.99    5087  436.42  5224.2  436.98  5233.7  437.93
  5276.3  438.09  5305.3   439.5  5376.8  440.58  5435.2  442.93  5436.9  442.99
  5523.6  445.18  5575.3  447.31  5618.3  448.03  5639.6  449.61  5763.2  452.56
#Mann= 6 ,-1 , 0
  4209.4      .1       0  4967.9     .12       0  4994.4     .07       0
  5000.4     .12       0  5435.2     .05       0  5436.9      .1       0
Bank Sta=4957.8,5233.7
XS Rating Curve= 0 ,0
Exp/Cntr=0.3,0.1

Type RM Length L Ch R = 1 ,25640   ,462,462,462
BEGIN DESCRIPTION:
TEPECATE CREEK 49.0
END DESCRIPTION:
XS GIS Cut Line= 3
      2181587.69     13227746.83      2180987.72     13227196.85
      2180237.69     13227146.85
#Sta/Elev= 30
  4186.1  453.41  4264.1  451.08  4292.4  451.18  4306.6  449.84  4348.8  449.41
  4370.1  448.23  4391.1  448.69  4426.8  446.46    4462  446.59  4490.4  444.36
  4596.4  442.98    4618  441.63  4667.3  441.14  4681.5   439.8  4738.2  439.57
  4759.2  438.29  4822.5  437.03  4886.9  436.15    4922  435.47  4975.7  432.87
  4978.5  432.37  4981.7  432.87  4986.1  434.42  5015.8  434.55  5160.4  435.01
  5220.5  436.55  5433.6  442.68  5541.2  446.69  5581.3  446.92  5751.7  451.94
#Mann= 6 ,-1 , 0
  4186.1      .1       0  4822.5     .12       0  4975.7     .07       0
  4981.7     .12       0  5015.8      .1       0  5433.6     .05       0
Bank Sta=4886.9,5220.5
XS Rating Curve= 0 ,0
Exp/Cntr=0.3,0.1

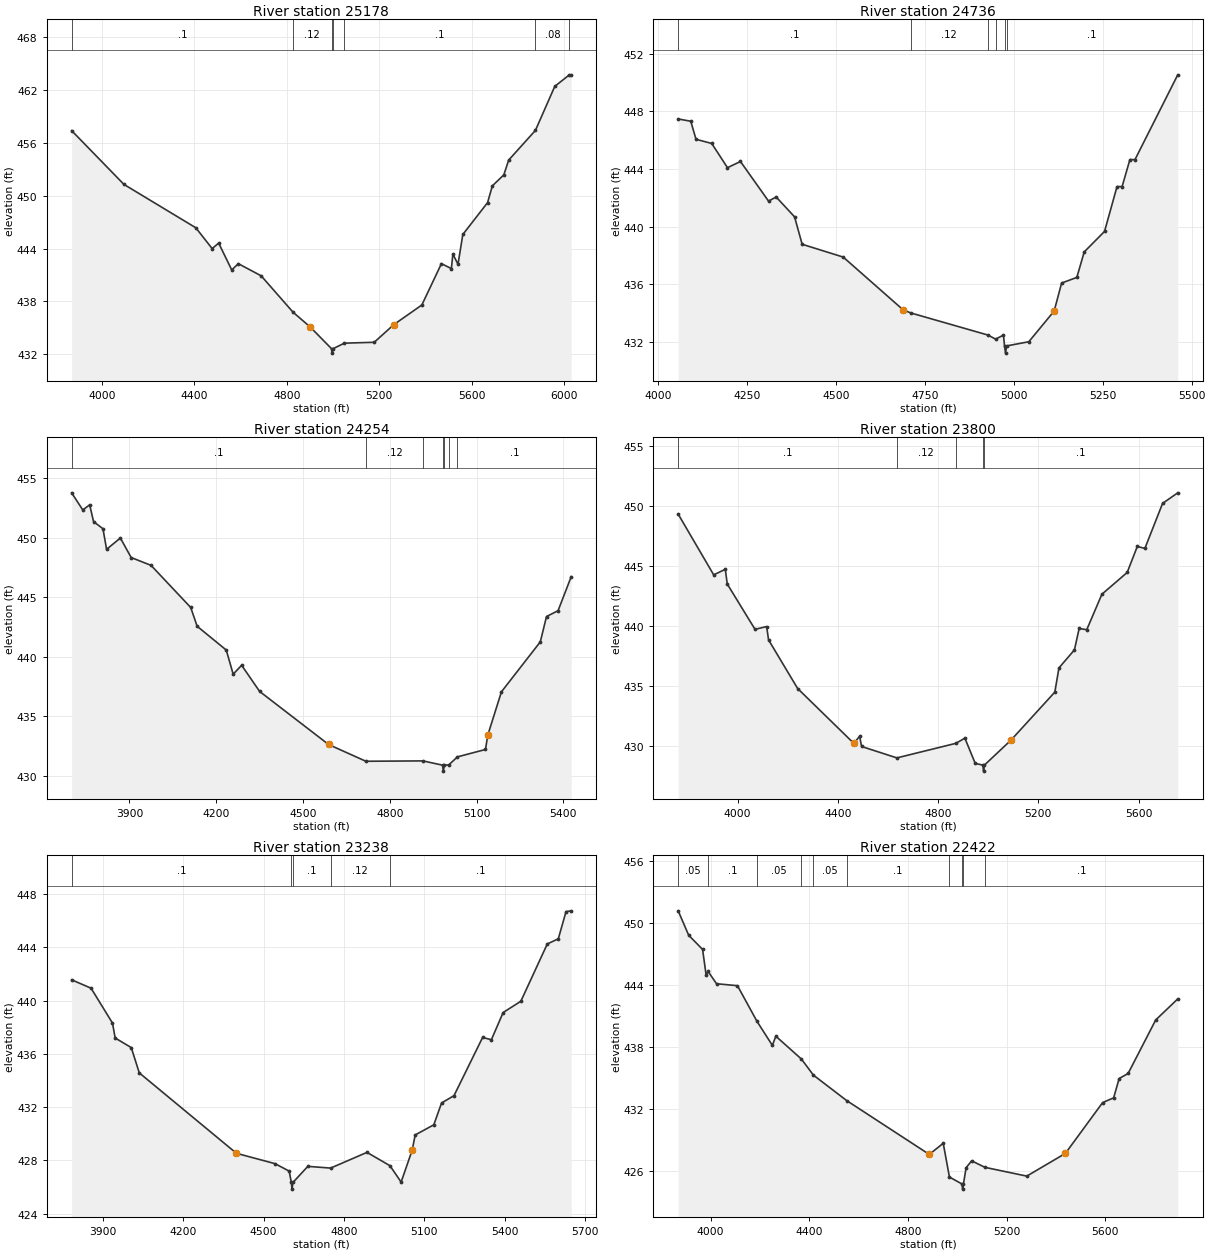
Type RM Length L Ch R = 1 ,25178   ,442,442,442
BEGIN DESCRIPTION:
TEPECATE CREEK 48.0
END DESCRIPTION:
XS GIS Cut Line= 3
      2181937.74     13227596.88      2181137.72     13226796.85
      2180487.71     13225996.84
#Sta/Elev= 30
  3868.6  457.38  4094.9  451.28    4406  446.36  4476.7     444    4505  444.62
  4561.6  441.57  4589.9  442.29  4688.9  440.91  4826.9  436.78    4901  435.11
  4993.5  432.64  4996.2  432.14  4999.5  432.64  5049.3  433.27  5178.2  433.37
  5262.9  435.37  5384.3   437.6  5469.1  442.29  5512.2  441.73  5518.6  443.37
  5540.9  442.22  5561.7   445.6  5668.8  449.21  5689.6  451.12  5739.1  452.36
  5760.2  454.04    5876  457.41  5959.7   462.4  6022.9  463.71  6030.8  463.71
#Mann= 7 ,-1 , 0
  3868.6      .1       0  4826.9     .12       0  4993.5     .07       0
  4999.5     .12       0  5049.3      .1       0    5876     .08       0
  6022.9     .05       0
Bank Sta=4901,5262.9
XS Rating Curve= 0 ,0
Exp/Cntr=0.3,0.1

Type RM Length L Ch R = 1 ,24736   ,482,482,482
BEGIN DESCRIPTION:
TEPECATE CREEK 47.0
END DESCRIPTION:
XS GIS Cut Line= 3
      2181737.72     13227196.86      2181237.72     13226396.85
       2180887.7     13226096.84
#Sta/Elev= 30
  4056.6  447.47    4092  447.31  4106.7  446.06  4150.9  445.77  4195.2  444.09
  4231.7  444.52  4310.7  441.77    4332  442.06  4383.8  440.68  4405.1  438.78
  4520.6  437.89  4688.1  434.25    4710  434.02  4927.9  432.48  4948.9   432.2
  4971.1  432.48    4974  431.73  4976.8  431.23    4980  431.73  5042.3  432.02
  5113.6  434.15  5134.5  436.09  5177.3  436.48  5198.1  438.25  5255.2  439.67
  5290.3  442.78  5304.6  442.78  5326.5  444.65  5340.8  444.65    5461  450.53
#Mann= 6 ,-1 , 0
  4056.6      .1       0    4710     .12       0  4927.9     .16       0
  4948.9      .1       0    4974     .07       0    4980      .1       0
Bank Sta=4688.1,5113.6
XS Rating Curve= 0 ,0
Exp/Cntr=0.3,0.1

Type RM Length L Ch R = 1 ,24254   ,454,454,454
BEGIN DESCRIPTION:
TEPECATE CREEK 46.0
END DESCRIPTION:
XS GIS Cut Line= 3
      2182037.72     13227296.86      2181537.72     13226096.86
      2181137.72     13225946.86
#Sta/Elev= 30
    3700  453.77  3738.5  452.33  3762.3  452.76  3775.8  451.35  3808.3  450.75
  3820.8  449.02  3868.5  449.97  3905.8  448.33  3974.6  447.67  4111.7  444.13
  4133.9  442.55  4234.6  440.55  4258.5  438.52  4287.7  439.27    4350  437.07
  4588.3  432.61  4717.2   431.2  4914.8  431.23  4982.4  430.87  4985.1  430.37
  4988.4  430.87  5003.7  430.89  5033.9  431.57  5130.8  432.19  5138.8   433.4
    5186  437.04  5320.4  441.24  5341.8  443.37  5381.8  443.86  5427.2  446.72
#Mann= 7 ,-1 , 0
    3700      .1       0  4717.2     .12       0  4914.8      .1       0
  4982.4     .07       0  4988.4      .1       0  5003.7     .16       0
  5033.9      .1       0
Bank Sta=4588.3,5138.8
XS Rating Curve= 0 ,0
Exp/Cntr=0.3,0.1

Type RM Length L Ch R = 1 ,23800   ,562,562,562
BEGIN DESCRIPTION:
TEPECATE CREEK 45.0
END DESCRIPTION:
XS GIS Cut Line= 3
      2182187.71     13227046.82      2181887.72     13225846.85
      2181787.73     13225096.89
#Sta/Elev= 30
  3763.1  449.31  3904.8  444.26  3951.2  444.72  3958.9   443.5  4069.7  439.73
  4116.1  439.96  4123.8  438.85  4239.8  434.81    4464  430.25  4487.2  430.84
  4494.9  429.99  4635.8  429.04  4871.1  430.25  4907.2  430.68  4948.5  428.58
    4979  428.44  4981.7  427.94    4985  428.44  5090.8  430.51  5266.1  434.51
  5282.5  436.52  5344.3  438.02  5363.2   439.8  5393.5   439.7    5454  442.65
  5554.9  444.46  5595.2  446.62  5625.5  446.46  5696.1   450.2  5756.6  451.08
#Mann= 5 ,-1 , 0
  3763.1      .1       0  4635.8     .12       0  4871.1      .1       0
    4979     .07       0    4985      .1       0
Bank Sta=4464,5090.8
XS Rating Curve= 0 ,0
Exp/Cntr=0.3,0.1

Type RM Length L Ch R = 1 ,23238   ,816,816,816
BEGIN DESCRIPTION:
TEPECATE CREEK 44.0
END DESCRIPTION:
XS GIS Cut Line= 3
      2182640.28     13226749.22      2182648.96     13226280.51
      2182084.73     13225004.48
#Sta/Elev= 30
  3783.7  441.57  3856.1  440.94  3936.1  438.32  3946.1   437.2  4006.1  436.48
  4036.1  434.58  4398.6  428.54  4543.1  427.76  4595.4   427.2  4603.4  426.35
  4606.1  425.85  4609.4  426.35    4665  427.56    4750  427.43  4885.7  428.61
  4971.4  427.61  5013.1  426.38  5054.2  428.77  5065.6  429.92    5135  430.68
    5164  432.32  5210.4  432.87  5317.1  437.24  5349.9  437.07  5393.6  439.11
  5459.8  439.96  5558.4  444.26  5599.6  444.65  5628.3  446.69  5647.7  446.75
#Mann= 5 ,-1 , 0
  3783.7      .1       0  4603.4     .07       0  4609.4      .1       0
    4750     .12       0  4971.4      .1       0
Bank Sta=4398.6,5054.2
XS Rating Curve= 0 ,0
Exp/Cntr=0.3,0.1

Type RM Length L Ch R = 1 ,22422   ,483,483,483
BEGIN DESCRIPTION:
TEPECATE CREEK 42.0
END DESCRIPTION:
XS GIS Cut Line= 3
      2183787.74     13226546.88      2182987.72     13225746.85
      2182587.73     13224946.88
#Sta/Elev= 30
  3868.6  451.15  3911.1  448.79  3967.6  447.41  3981.8  444.95  3989.8  445.28
  4024.2  444.09    4109   443.9  4188.1  440.45  4250.5  438.12  4264.6  439.01
  4368.2   436.8    4417  435.24  4552.2  432.77  4886.9  427.56  4943.4  428.64
  4968.6  425.37  5019.4   424.7  5022.1   424.2  5025.4   424.7  5036.3  426.28
  5058.7  426.94  5112.5  426.31  5282.3  425.46  5438.8  427.66  5589.8  432.58
  5634.5  433.04  5656.8  434.91  5693.2   435.4    5805  440.58  5894.4  442.62
#Mann= 10 ,-1 , 0
  3868.6     .05       0  3989.8      .1       0  4188.1     .05       0
  4368.2      .1       0    4417     .05       0  4552.2      .1       0
  4968.6     .12       0  5019.4     .07       0  5025.4     .12       0
  5112.5      .1       0
Bank Sta=4886.9,5438.8
XS Rating Curve= 0 ,0
Exp/Cntr=0.3,0.1

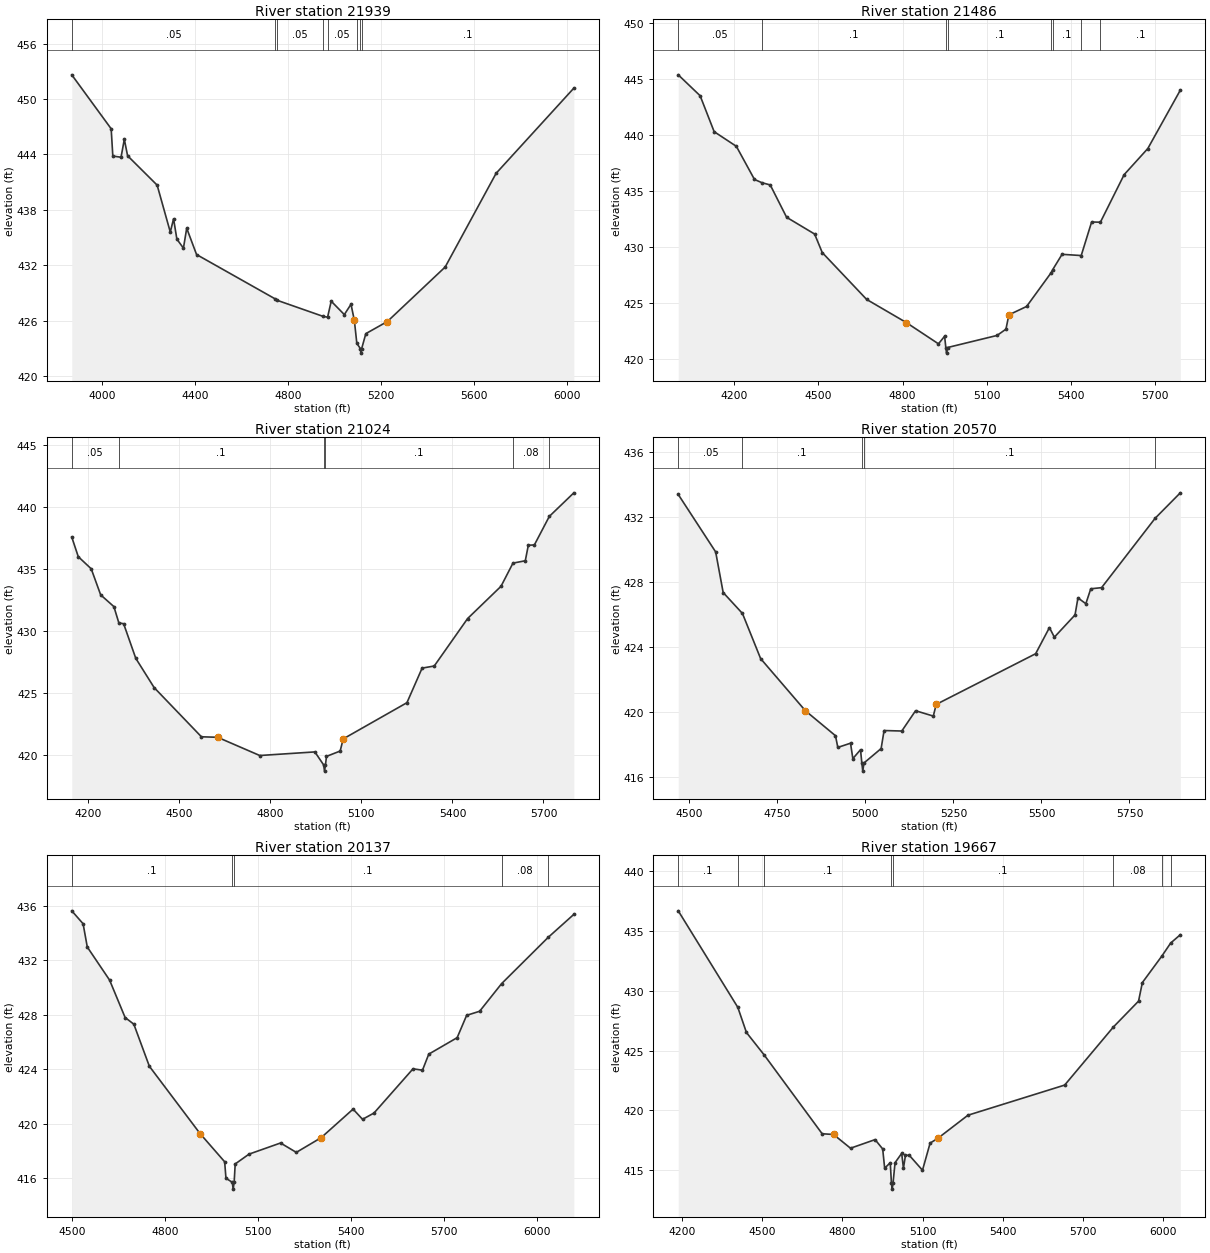
Type RM Length L Ch R = 1 ,21939   ,453,453,453
BEGIN DESCRIPTION:
TEPECATE CREEK 41.0
END DESCRIPTION:
XS GIS Cut Line= 3
      2184037.74     13226196.88      2183237.72     13225396.85
       2182437.7     13224746.84
#Sta/Elev= 30
  3868.6  452.62  4038.3  446.78  4045.4  443.83  4080.8   443.7  4094.9  445.64
    4109  443.86  4236.3  440.68  4292.9   435.6    4307  437.04  4321.2  434.84
  4349.5  433.86  4363.6  436.02    4406  433.17  4744.6  428.37  4752.8  428.22
  4949.5  426.49  4970.3  426.39  4985.9  428.12  5042.4  426.67  5071.1  427.79
  5085.5  426.05  5096.2  423.56  5111.2     423    5114   422.5  5117.2     423
    5135  424.61  5227.7  425.92  5476.7  431.82    5696  441.96  6030.8  451.18
#Mann= 8 ,-1 , 0
  3868.6     .05       0  4744.6      .1       0  4752.8     .05       0
  4949.5      .1       0  4970.3     .05       0  5096.2      .1       0
  5111.2     .03       0  5117.2      .1       0
Bank Sta=5085.5,5227.7
XS Rating Curve= 0 ,0
Exp/Cntr=0.3,0.1

Type RM Length L Ch R = 1 ,21486   ,462,462,462
BEGIN DESCRIPTION:
TEPECATE CREEK 40.0
END DESCRIPTION:
XS GIS Cut Line= 3
      2184087.72     13225846.85      2183487.72     13225046.85
      2182737.69     13224796.85
#Sta/Elev= 30
    4000  445.37  4078.1   443.5  4128.1  440.29  4207.3  438.98  4271.9  436.02
  4298.4  435.73  4328.1  435.53  4386.5  432.64  4486.5  431.14  4513.5  429.49
  4671.9   425.3  4813.5  423.23  4928.1  421.33    4950  422.01  4954.3     421
    4957   420.5  4960.3     421    5137  422.08  5168.7  422.64  5179.2  423.92
  5242.4  424.67  5329.8  427.68  5335.5  427.96  5368.9  429.33  5437.2  429.22
  5474.3  432.22  5505.6   432.2  5590.3  436.45  5674.6  438.78  5790.6     444
#Mann= 8 ,-1 , 0
    4000     .05       0  4298.4      .1       0  4954.3     .07       0
  4960.3      .1       0  5329.8     .08       0  5335.5      .1       0
  5437.2     .08       0  5505.6      .1       0
Bank Sta=4813.5,5179.2
XS Rating Curve= 0 ,0
Exp/Cntr=0.3,0.1

Type RM Length L Ch R = 1 ,21024   ,454,454,454
BEGIN DESCRIPTION:
TEPECATE CREEK 39.0
END DESCRIPTION:
XS GIS Cut Line= 3
      2184437.72     13224946.85      2183637.72     13224646.86
      2182837.72     13224646.85
#Sta/Elev= 30
  4145.6  437.57    4167  435.99  4209.7  435.01  4240.8  432.91  4284.4  431.96
  4300.7  430.65  4316.5  430.58  4356.5  427.79    4417  425.43  4572.8  421.46
  4626.2  421.42    4765  419.95  4946.6  420.24  4975.6  419.19  4978.4  418.69
  4981.6  419.19  4984.9  419.88    5030  420.31    5040  421.29    5250  424.21
    5300     427    5340  427.17    5450     431    5560   433.6  5599.4  435.47
    5640  435.66    5650  436.91    5670  436.94  5719.2  439.24    5800  441.14
#Mann= 6 ,-1 , 0
  4145.6     .05       0  4300.7      .1       0  4975.6     .07       0
  4981.6      .1       0  5599.4     .08       0  5719.2      .1       0
Bank Sta=4626.2,5040
XS Rating Curve= 0 ,0
Exp/Cntr=0.3,0.1

Type RM Length L Ch R = 1 ,20570   ,433,433,433
BEGIN DESCRIPTION:
TEPECATE CREEK 38.0
END DESCRIPTION:
XS GIS Cut Line= 3
      2184387.71     13224746.85      2183987.72     13224396.85
      2183187.74     13223996.87
#Sta/Elev= 30
  4468.5   433.4  4574.8  429.86  4596.1  427.36  4650.9  426.07  4702.5  423.29
  4829.6  420.08  4915.1  418.54  4921.7  417.82  4957.8  418.08  4964.4  417.13
  4986.2  417.68  4989.9  416.86  4992.6  416.36  4995.9  416.86  5044.7  417.75
  5053.1  418.86  5103.4  418.83  5142.5  420.08  5192.9  419.75  5201.2  420.47
  5483.5  423.59  5522.7   425.2  5536.7  424.61  5595.4  425.98  5603.7  427.03
  5626.1  426.67  5640.1  427.59  5670.8  427.66  5822.8  431.93  5894.4   433.5
#Mann= 5 ,-1 , 0
  4468.5     .05       0  4650.9      .1       0  4989.9     .07       0
  4995.9      .1       0  5822.8     .08       0
Bank Sta=4829.6,5201.2
XS Rating Curve= 0 ,0
Exp/Cntr=0.3,0.1

Type RM Length L Ch R = 1 ,20137   ,470,470,470
BEGIN DESCRIPTION:
TEPECATE CREEK 37.0
END DESCRIPTION:
XS GIS Cut Line= 3
      2184637.72     13224396.85      2184237.72     13224096.85
      2183137.75     13223896.86
#Sta/Elev= 30
    4500  435.63  4536.5  434.68    4550  432.97  4621.9  430.54  4671.9  427.79
    4700   427.3    4750  424.21  4913.5  419.26  4992.7  417.19  4996.9  415.98
  5017.3  415.68  5020.1  415.18  5023.3  415.68  5026.7  417.03  5071.1  417.75
  5172.8  418.57  5223.6  417.88  5303.6  418.96  5406.6  421.06    5437  420.31
  5473.9  420.77  5599.7  424.02  5630.2  423.92  5650.5   425.1    5742  426.31
  5772.5  427.95  5814.4  428.25  5885.2  430.28  6035.3  433.68    6118  435.37
#Mann= 5 ,-1 , 0
    4500      .1       0  5017.3     .07       0  5023.3      .1       0
  5885.2     .08       0  6035.3      .1       0
Bank Sta=4913.5,5303.6
XS Rating Curve= 0 ,0
Exp/Cntr=0.3,0.1

Type RM Length L Ch R = 1 ,19667   ,483,483,483
BEGIN DESCRIPTION:
TEPECATE CREEK 36.0
END DESCRIPTION:
XS GIS Cut Line= 3
      2184837.69     13224246.83      2184237.72     13223696.85
      2183437.73     13222996.86
#Sta/Elev= 30
  4186.1  436.68  4408.8  428.61    4441  426.51    4507  424.64  4724.1  418.04
  4766.6  417.98  4830.1  416.83    4922  417.55  4950.4  416.77  4957.8  415.16
  4978.7  415.62  4983.1  413.91  4985.9  413.41  4989.1  413.91  4996.6  415.62
  5021.4   416.4    5028  415.16  5035.6  416.24  5049.8  416.24  5099.2  414.99
  5127.7  417.26  5156.1  417.65  5269.1  419.59  5630.7  422.11    5813  426.97
  5906.9  429.13  5921.1  430.68  5994.1   432.9  6027.1  433.99    6063  434.68
#Mann= 8 ,-1 , 0
  4186.1      .1       0  4408.8     .05       0    4507      .1       0
  4983.1     .07       0  4989.1      .1       0    5813     .08       0
  5994.1      .1       0  6027.1     .08       0
Bank Sta=4766.6,5156.1
XS Rating Curve= 0 ,0
Exp/Cntr=0.3,0.1

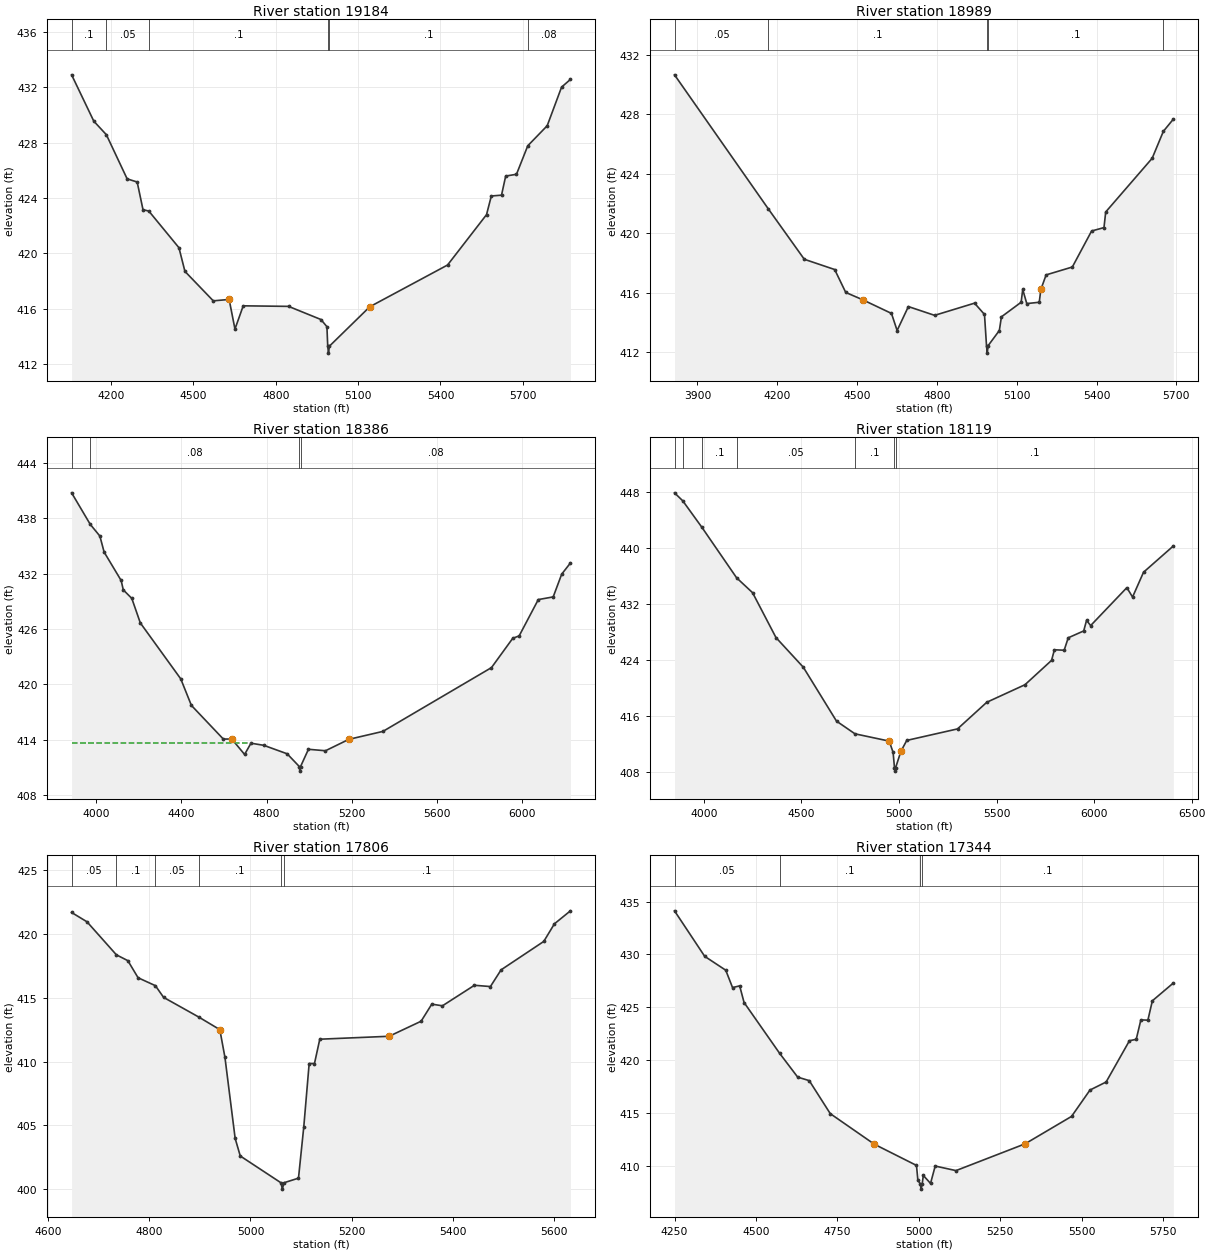
Type RM Length L Ch R = 1 ,19184   ,195,195,195
BEGIN DESCRIPTION:
TEPECATE CREEK 35.0
END DESCRIPTION:
XS GIS Cut Line= 3
      2184837.72     13224096.86      2184337.72     13223296.85
      2183537.73     13222946.86
#Sta/Elev= 30
  4056.6  432.91  4137.4  429.56  4183.2  428.58  4258.8  425.39  4295.4  425.16
  4316.6  423.16  4337.8  423.06  4447.5  420.41  4469.3   418.7  4572.5  416.57
  4630.3  416.67  4651.5  414.53  4681.6  416.21  4846.7  416.17  4964.6  415.22
  4986.4   414.7  4989.3  413.29  4992.1  412.79  4995.3  413.29  5142.3  416.14
  5425.7  419.16  5567.6   422.8  5585.1  424.15  5622.2  424.21  5637.4  425.59
  5676.7  425.72  5717.8  427.78  5788.6  429.23  5840.9  432.02  5873.2  432.58
#Mann= 6 ,-1 , 0
  4056.6      .1       0  4183.2     .05       0  4337.8      .1       0
  4989.3     .07       0  4995.3      .1       0  5717.8     .08       0
Bank Sta=4630.3,5142.3
XS Rating Curve= 0 ,0
Exp/Cntr=0.3,0.1

Type RM Length L Ch R = 1 ,18989   ,603,603,603
BEGIN DESCRIPTION:
Mapping XS 9fa86954
END DESCRIPTION:
XS GIS Cut Line= 3
      2184930.87     13223986.79      2184722.53     13223236.76
      2183687.76     13222875.63
#Sta/Elev= 30
    3814  430.64  4166.4  421.63  4301.7  418.24  4415.9  417.55  4457.4  416.01
  4520.9  415.52  4629.3   414.6  4650.5  413.45  4692.8  415.06  4791.4  414.47
  4941.4  415.29  4978.8  414.53  4986.4  412.43  4989.2  411.93  4992.4  412.43
  5034.6  413.45  5042.4  414.37  5116.5  415.35  5122.5  416.21  5137.7  415.26
  5184.6  415.35  5190.6  416.21  5210.4  417.19  5308.9  417.72  5381.3  420.14
  5427.8  420.37  5434.3  421.42  5608.9  425.03  5650.9  426.84  5688.4  427.66
#Mann= 5 ,-1 , 0
    3814     .05       0  4166.4      .1       0  4986.4     .07       0
  4992.4      .1       0  5650.9     .08       0
Bank Sta=4520.9,5190.6
XS Rating Curve= 0 ,0
Exp/Cntr=0.3,0.1

Type RM Length L Ch R = 1 ,18386   ,267,267,267
BEGIN DESCRIPTION:
TEPECATE CREEK 34.0
END DESCRIPTION:
XS GIS Cut Line= 2
      2185870.53     13222725.91      2183526.74     13222734.59
#Sta/Elev= 30
    3884  440.78  3971.6  437.36  4016.8  436.09  4036.8  434.35  4116.8  431.27
  4126.8  430.25  4166.8  429.33  4206.8  426.67  4396.8   420.6  4446.8  417.72
  4596.8  414.07  4636.8  414.07  4696.8   412.4  4726.8  413.62  4786.8  413.39
  4896.8  412.47  4953.8  411.09  4956.6  410.59  4959.8  411.09  4996.8  412.96
  5076.8   412.8  5186.8  414.04  5346.8   414.9  5856.8  421.82  5956.8     425
  5986.8  425.26  6076.8   429.2  6146.8  429.49  6186.8  431.96  6227.8  433.17
#Mann= 4 ,-1 , 0
    3884      .1       0  3971.6     .08       0  4953.8     .07       0
  4959.8     .08       0
#XS Ineff= 2 , 0
         4727.27  413.64
Permanent Ineff=
       F       F
Bank Sta=4636.8,5186.8
XS Rating Curve= 0 ,0
Exp/Cntr=0.3,0.1

Type RM Length L Ch R = 1 ,18119   ,313,313,313
BEGIN DESCRIPTION:
TEPECATE CREEK 33.0
END DESCRIPTION:
XS GIS Cut Line= 3
      2186037.67     13222546.85      2184241.43     13222502.78
      2183631.87     13222049.51
#Sta/Elev= 30
  3849.7  447.87    3892  446.73  3990.1  442.95  4168.1  435.75  4249.8  433.63
  4369.8  427.23  4509.9     423  4679.9  415.32  4774.5  413.51    4950  412.47
    4970  410.86    4977  408.69  4979.7  408.19    4983  408.69    5010  411.02
    5040  412.57  5300.1  414.21  5450.1  418.01  5645.8  420.51    5782  423.98
  5796.6  425.49  5846.7  425.43  5867.5   427.2  5946.8  428.18  5961.4  429.69
  5982.3  428.94  6167.9  434.35  6197.1  433.01  6253.4  436.55  6406.1  440.29
#Mann= 7 ,-1 , 0
  3849.7     .08       0    3892     .05       0  3990.1      .1       0
  4168.1     .05       0  4774.5      .1       0    4977     .07       0
    4983      .1       0
Bank Sta=4950,5010
XS Rating Curve= 0 ,0
Exp/Cntr=0.3,0.1

Type RM Length L Ch R = 1 ,17806   ,462,462,462
BEGIN DESCRIPTION:
TEPECATE CREEK 32.0
END DESCRIPTION:
XS GIS Cut Line= 3
      2185387.77     13222346.86      2185037.72     13222296.85
      2184437.68     13222096.84
#Sta/Elev= 30
  4646.4  421.69  4676.8  420.96  4734.9  418.37  4757.6  417.91  4777.8  416.57
    4812  415.95  4828.3  415.03  4897.7  413.49  4939.4   412.5  4949.5  410.33
  4969.7  403.97  4979.8  402.59  5060.2  400.49    5063  399.99  5066.2  400.49
  5094.9  400.85  5105.4  404.89    5116  409.84  5126.5  409.84    5137  411.75
  5274.1  411.98  5337.3  413.16  5358.4   414.5  5379.5  414.37  5442.7  415.98
  5474.3  415.88  5495.4  417.19  5579.8  419.42  5600.8   420.8  5632.5  421.82
#Mann= 6 ,-1 , 0
  4646.4     .05       0  4734.9      .1       0    4812     .05       0
  4897.7      .1       0  5060.2     .07       0  5066.2      .1       0
Bank Sta=4939.4,5274.1
XS Rating Curve= 0 ,0
Exp/Cntr=0.3,0.1

Type RM Length L Ch R = 1 ,17344   ,462,462,462
BEGIN DESCRIPTION:
TEPECATE CREEK 31.0
END DESCRIPTION:
XS GIS Cut Line= 3
      2185687.72     13222346.85      2185087.72     13221896.85
      2184587.74     13221296.87
#Sta/Elev= 30
    4250  434.12  4342.7  429.82  4407.3  428.51  4428.1  426.87    4450  427.03
  4463.5  425.46  4572.4  420.67  4628.1  418.41  4663.5  418.08  4728.1  414.96
  4863.5  412.07  4992.7  410.07  4996.9  408.69  5004.2  408.33  5006.9  407.83
  5010.2  408.33  5013.7  409.12  5035.8  408.37  5050.1  410.01  5113.9  409.58
  5326.1  412.11  5468.6   414.7  5525.2  417.19  5574.7  417.95  5646.3  421.85
  5667.1  421.98  5681.4  423.82  5702.9  423.79  5716.6  425.62    5781   427.3
#Mann= 4 ,-1 , 0
    4250     .05       0  4572.4      .1       0  5004.2     .07       0
  5010.2      .1       0
Bank Sta=4863.5,5326.1
XS Rating Curve= 0 ,0
Exp/Cntr=0.3,0.1