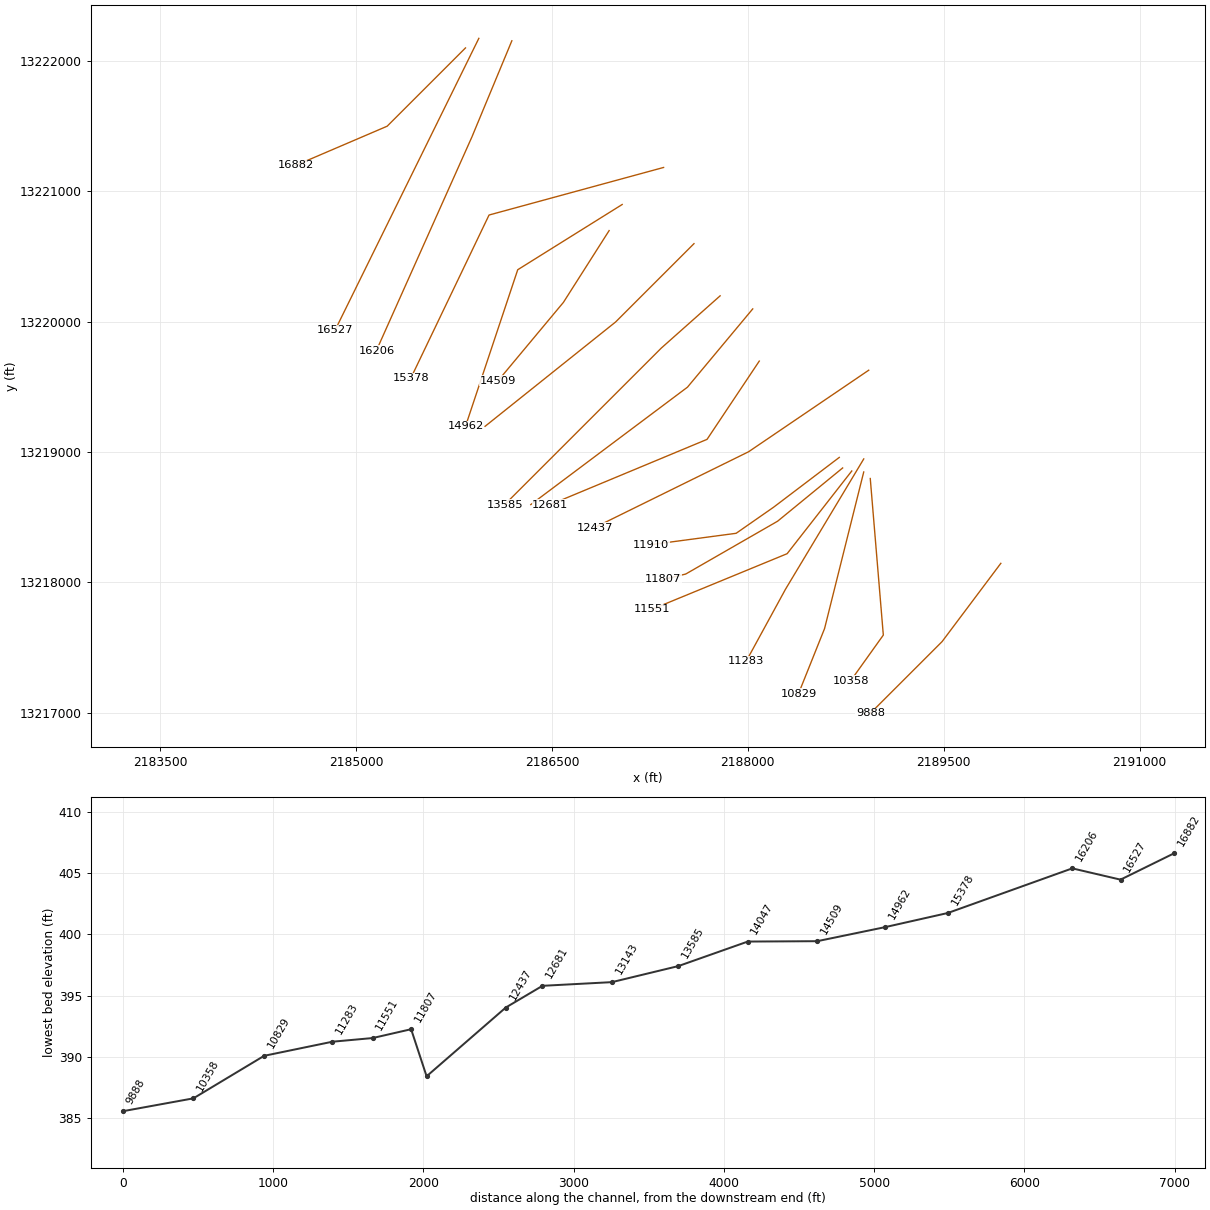
HEC-RAS study TEPECATE CREEK.prj: TEPECATE CREEK Base Level Engineering

--- TEPECATE CREEK.g01 (geometry) --- (continued)

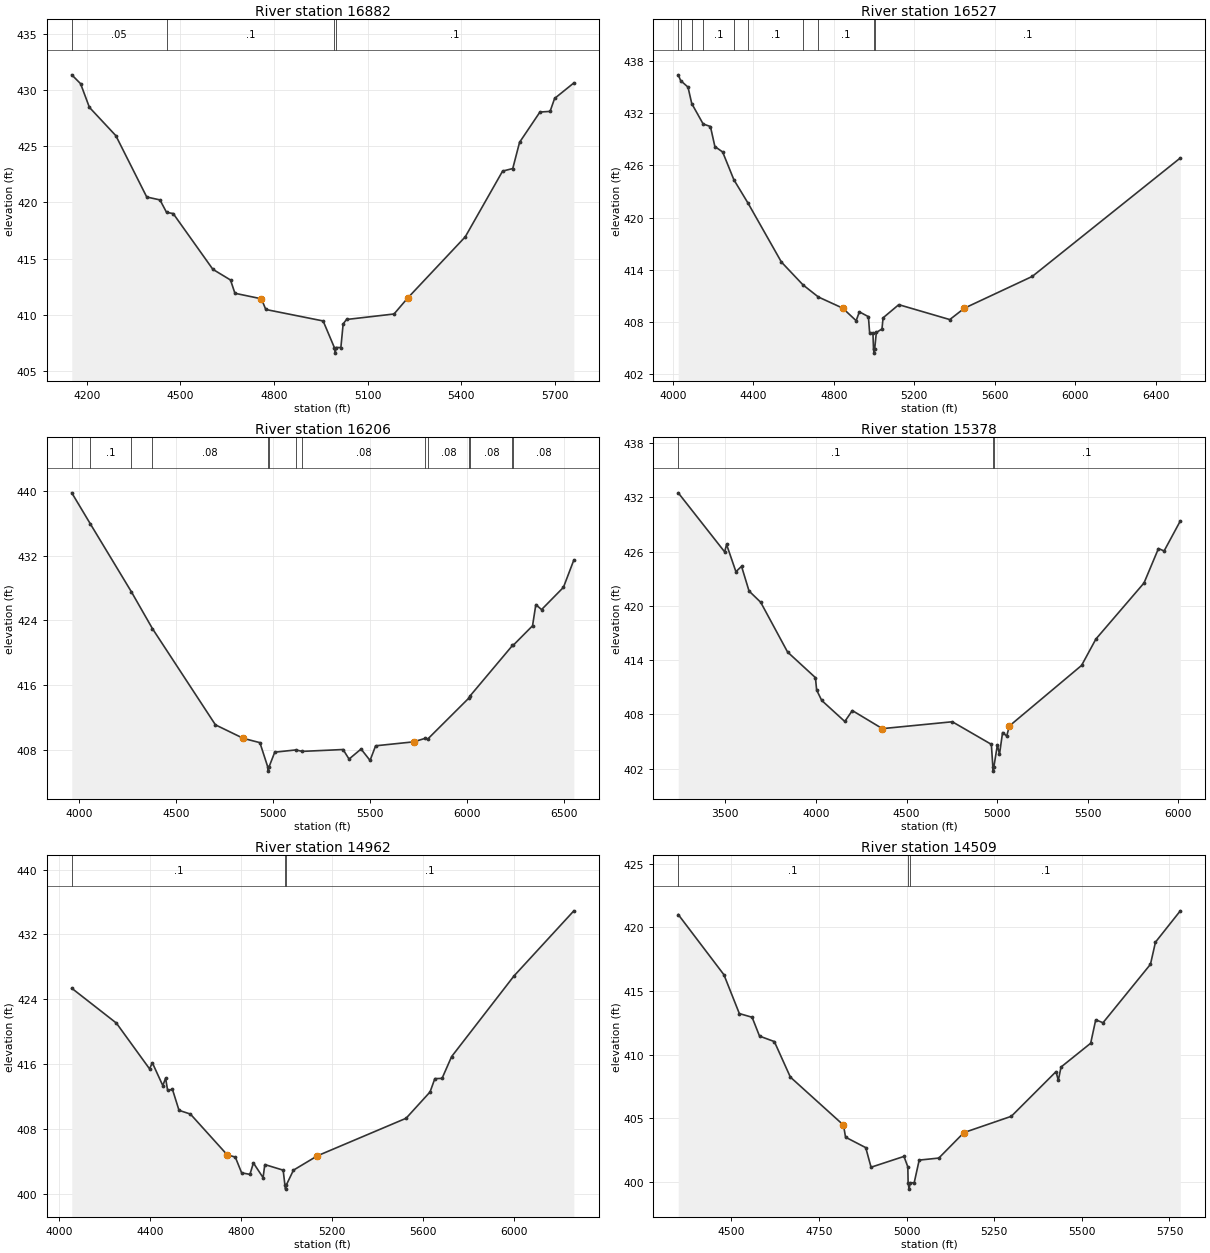
Type RM Length L Ch R = 1 ,16882   ,355,355,355
BEGIN DESCRIPTION:
TEPECATE CREEK 30.0
END DESCRIPTION:
XS GIS Cut Line= 3
       2185837.7     13222096.84      2185237.72     13221496.86
       2184537.7     13221196.85
#Sta/Elev= 30
  4151.5  431.33  4179.8  430.54    4208  428.44  4292.9  425.92  4391.9  420.47
  4434.3  420.21  4455.5   419.1  4476.7     419    4604  414.04  4660.6  413.09
  4674.7  411.91  4759.6  411.42  4773.7  410.47  4957.6  409.45  4993.5  407.09
  4996.2  406.59  4999.5  407.09  5014.5  407.09  5021.8  409.19  5032.6  409.58
    5185  410.07  5228.5  411.48  5413.4  416.93  5533.1  422.77  5565.7     423
  5587.5  425.33  5652.8  428.02  5685.4  428.08  5699.9  429.23  5761.6  430.61
#Mann= 4 ,-1 , 0
  4151.5     .05       0  4455.5      .1       0  4993.5     .07       0
  4999.5      .1       0
Bank Sta=4759.6,5228.5
XS Rating Curve= 0 ,0
Exp/Cntr=0.3,0.1

Type RM Length L Ch R = 1 ,16527   ,321,321,321
BEGIN DESCRIPTION:
TEPECATE CREEK 29.0
END DESCRIPTION:
XS GIS Cut Line= 2
      2185939.98     13222170.36      2184837.82     13219931.33
#Sta/Elev= 30
  4026.4  436.38  4038.4  435.72  4074.9  434.97  4093.6  433.08  4150.2  430.74
  4186.4  430.45  4208.6  428.15  4247.1  427.53    4303  424.34  4373.8  421.64
  4539.2   414.9    4647  412.27    4723  410.89    4844  409.61  4910.8  408.17
  4926.7  409.19  4971.7  408.63  4977.7  406.79  4994.1  406.79    4997  404.95
  4999.8  404.45    5003  404.95    5011  406.82  5039.1  407.22  5044.6   408.5
  5122.6  410.01  5376.1   408.3  5449.1  409.61  5786.1  413.25    6522  426.84
#Mann= 10 ,-1 , 0
  4026.4     .08       0  4038.4      .1       0  4093.6     .05       0
  4150.2      .1       0    4303     .05       0  4373.8      .1       0
    4647     .08       0    4723      .1       0    4997     .07       0
    5003      .1       0
Bank Sta=4844,5449.1
XS Rating Curve= 0 ,0
Exp/Cntr=0.3,0.1

Type RM Length L Ch R = 1 ,16206   ,828,828,828
BEGIN DESCRIPTION:
TEPECATE CREEK 28.0
END DESCRIPTION:
XS GIS Cut Line= 3
      2186192.76     13222151.53      2185886.48     13221413.66
      2185155.57     13219777.83
#Sta/Elev= 30
  3962.2  439.76  4058.1  435.92  4269.8  427.53  4378.2  422.99  4703.5  411.09
  4847.3  409.42  4932.9  408.89  4973.7  405.87  4976.4  405.37  4979.7  405.87
  5009.5  407.71  5118.5  407.99  5151.7  407.81  5362.1  408.04  5392.9  406.86
  5454.9   408.1  5501.3  406.69    5530   408.5  5726.6  408.99  5785.4  409.42
  5799.6  409.35  6010.8  414.39    6019  414.71  6236.2   420.9  6239.1   420.9
  6339.7  423.33  6356.7  425.95  6386.2  425.33  6499.1  428.08  6552.8  431.46
#Mann= 14 ,-1 , 0
  3962.2     .05       0  4058.1      .1       0  4269.8     .05       0
  4378.2     .08       0  4973.7     .07       0  4979.7     .08       0
  5118.5      .1       0  5151.7     .08       0  5785.4      .1       0
  5799.6     .08       0  6010.8      .1       0    6019     .08       0
  6236.2      .1       0  6239.1     .08       0
Bank Sta=4847.3,5726.6
XS Rating Curve= 0 ,0
Exp/Cntr=0.3,0.1

Type RM Length L Ch R = 1 ,15378   ,416,416,416
BEGIN DESCRIPTION:
TEPECATE CREEK 27.0
END DESCRIPTION:
XS GIS Cut Line= 3
      2187354.86     13221180.76       2186018.1     13220816.19
      2185419.13     13219566.16
#Sta/Elev= 30
  3239.8  432.51    3496  425.98  3506.6   426.8  3558.2  423.79  3589.3  424.38
  3630.7  421.65  3694.9  420.41  3843.5   414.9  3997.2  412.07  4003.9   410.7
  4031.8  409.55  4159.3  407.22  4200.8  408.43  4366.6  406.43  4752.9  407.19
  4968.4  404.69  4976.5  402.23  4979.2  401.73  4982.5  402.23  5001.7  404.63
  5013.2  403.58  5030.3     406    5053  405.61  5068.2  406.73  5466.4  413.42
  5545.5  416.34  5811.1  422.54  5890.9  426.35    5922  426.08  6011.5   429.4
#Mann= 3 ,-1 , 0
  3239.8      .1       0  4976.5     .07       0  4982.5      .1       0
Bank Sta=4366.6,5068.2
XS Rating Curve= 0 ,0
Exp/Cntr=0.3,0.1

Type RM Length L Ch R = 1 ,14962   ,453,453,453
BEGIN DESCRIPTION:
TEPECATE CREEK 26.0
END DESCRIPTION:
XS GIS Cut Line= 3
      2187037.72     13220896.86      2186237.72     13220396.85
      2185837.72     13219196.87
#Sta/Elev= 30
  4056.6  425.36  4252.9  421.06  4398.6  415.42    4411  416.17    4457  413.35
  4469.3  414.27  4478.2  412.76  4499.4  412.89  4528.3   410.3  4578.4  409.84
    4740  404.82  4775.9  404.53  4803.7  402.59  4840.2   402.4  4855.5  403.81
    4898     402  4905.7  403.61  4986.4  402.92  4994.1  401.08  4996.8  400.58
  5000.1  401.08  5031.6  402.92    5137  404.69    5527  409.32  5632.5  412.57
  5653.5  414.21  5685.2  414.24  5727.3  416.93  6001.4  426.87  6264.9  434.91
#Mann= 3 ,-1 , 0
  4056.6      .1       0  4994.1     .07       0  5000.1      .1       0
Bank Sta=4740,5137
XS Rating Curve= 0 ,0
Exp/Cntr=0.3,0.1

Type RM Length L Ch R = 1 ,14509   ,462,462,462
BEGIN DESCRIPTION:
TEPECATE CREEK 25.0
END DESCRIPTION:
XS GIS Cut Line= 3
      2186937.71     13220696.84      2186587.72     13220146.85
      2186087.74     13219546.87
#Sta/Elev= 30
  4348.1     421  4478.5  416.27  4522.5  413.22  4558.9  412.93  4580.1  411.45
  4622.4  411.02  4668.1  408.23  4819.7  404.46  4825.6  403.51  4883.2  402.69
  4898.4  401.15  4992.4     402  5003.3  401.18  5004.2  399.93  5006.9  399.43
  5010.2  399.93  5021.5  399.93  5035.8  401.71  5091.8  401.87  5163.4  403.87
  5298.7  405.15  5426.3  408.66  5432.8  407.97  5440.6  409.02  5525.2  410.89
  5539.6  412.73  5560.4   412.5  5695.8  417.09  5710.1  418.83    5781  421.29
#Mann= 3 ,-1 , 0
  4348.1      .1       0  5004.2     .07       0  5010.2      .1       0
Bank Sta=4819.7,5163.4
XS Rating Curve= 0 ,0
Exp/Cntr=0.3,0.1

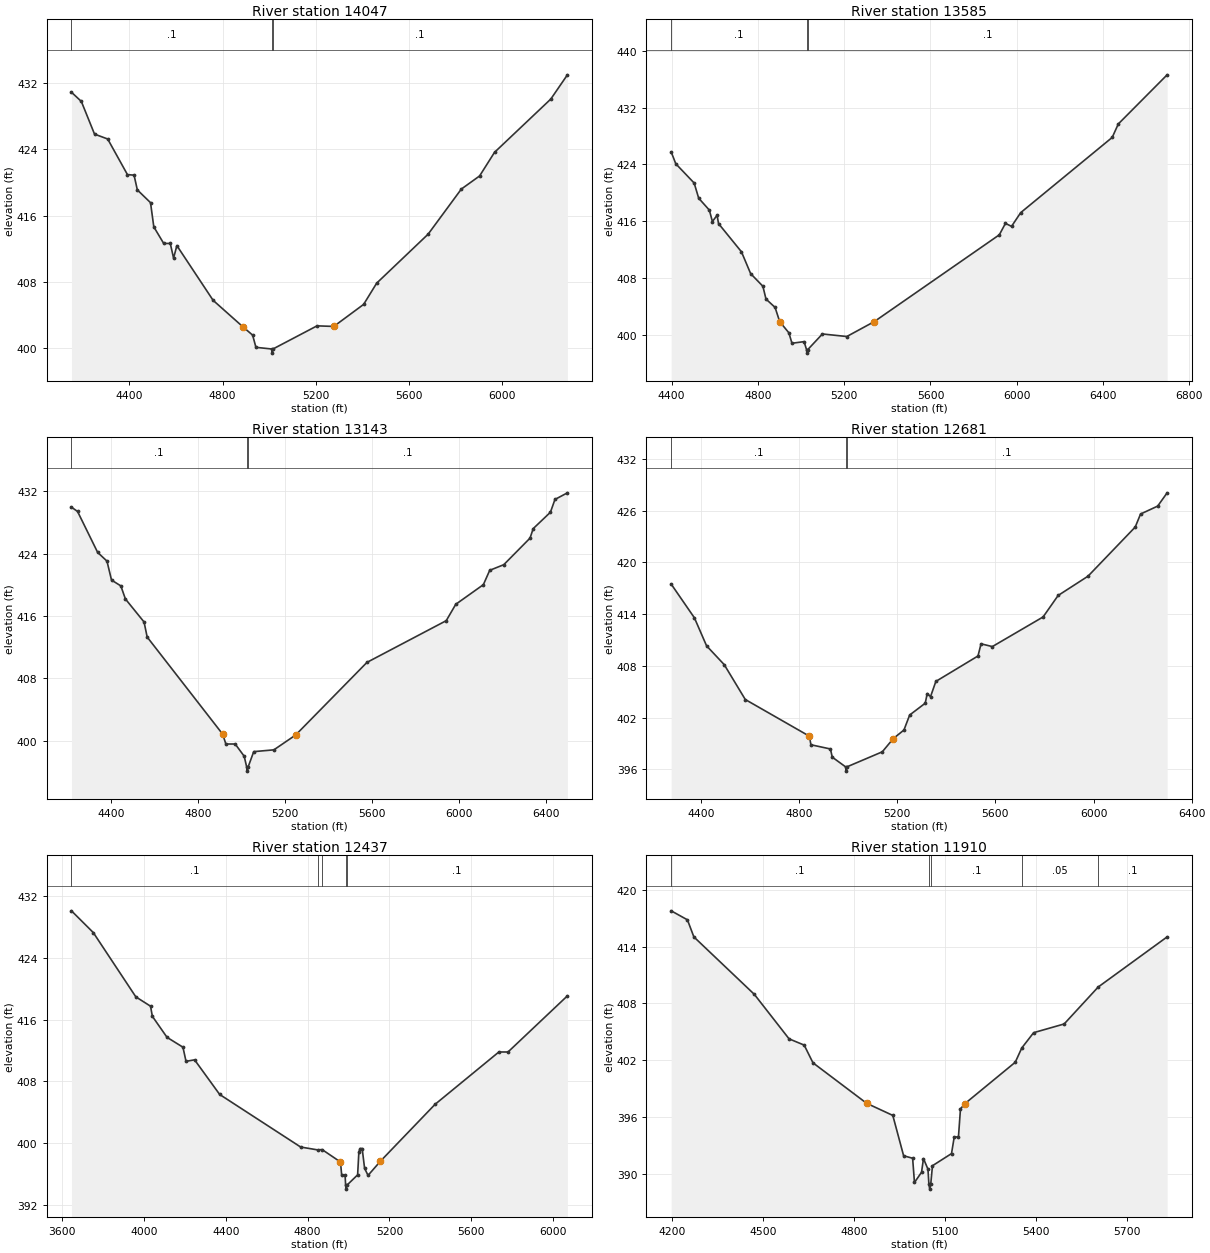
Type RM Length L Ch R = 1 ,14047   ,462,462,462
BEGIN DESCRIPTION:
TEPECATE CREEK 24.0
END DESCRIPTION:
XS GIS Cut Line= 3
       2187587.7     13220596.83      2186987.72     13219996.85
      2185987.74     13219196.87
#Sta/Elev= 30
  4151.5  430.87  4193.9  429.76  4250.5  425.82    4307  425.23  4391.9  420.93
  4420.2  420.87  4434.3  419.09  4490.9  417.55    4505  414.63  4547.5  412.63
  4575.7  412.63  4589.9  410.86    4604  412.37  4759.6  405.77  4886.9  402.59
  4929.3  401.57  4943.4   400.1  5010.6   399.9  5013.4   399.4  5016.6   399.9
  5205.7  402.69  5277.7  402.62  5405.8  405.28  5461.8  407.84  5682.7  413.75
  5825.2  419.19  5903.6  420.77  5967.7  423.62  6209.4  430.05  6280.6  432.97
#Mann= 3 ,-1 , 0
  4151.5      .1       0  5010.6     .07       0  5016.6      .1       0
Bank Sta=4886.9,5277.7
XS Rating Curve= 0 ,0
Exp/Cntr=0.3,0.1

Type RM Length L Ch R = 1 ,13585   ,442,442,442
BEGIN DESCRIPTION:
TEPECATE CREEK 23.0
END DESCRIPTION:
XS GIS Cut Line= 3
      2187787.74     13220196.87      2187337.72     13219796.85
      2186137.69     13218596.82
#Sta/Elev= 30
  4397.9  425.75  4419.2  424.08  4504.5  421.36  4525.4  419.23  4574.8  417.55
    4589  415.94  4610.7  416.83  4617.4  415.65  4723.6  411.68  4766.3   408.6
  4823.1  406.82  4837.4  405.02  4879.6  403.84  4900.9  401.84  4943.6  400.26
  4957.8  398.79  5014.1  399.02  5025.3   397.9    5028   397.4  5031.3   397.9
    5099   400.1  5212.1  399.74  5339.4  401.84  5919.2  414.07  5947.5  415.68
  5975.8  415.26  6018.2  417.19  6442.5  427.79  6470.8  429.69  6697.1  436.61
#Mann= 3 ,-1 , 0
  4397.9      .1       0  5025.3     .07       0  5031.3      .1       0
Bank Sta=4900.9,5339.4
XS Rating Curve= 0 ,0
Exp/Cntr=0.3,0.1

Type RM Length L Ch R = 1 ,13143   ,462,462,462
BEGIN DESCRIPTION:
TEPECATE CREEK 22.0
END DESCRIPTION:
XS GIS Cut Line= 3
       2188037.7     13220096.84      2187537.72     13219496.85
      2186337.72     13218596.85
#Sta/Elev= 30
    4219  429.95    4247   429.4  4339.4  424.15  4382.3  423.03  4403.2   420.6
  4446.1  419.85    4467  418.18  4552.9  415.22  4567.2  413.29  4914.7  400.82
  4929.1  399.57    4972  399.57  5013.5     398  5025.1  396.59  5027.9  396.09
  5031.1  396.59  5057.3  398.59    5150  398.82    5250  400.72  5578.1  410.04
  5942.7  415.39  5986.5  417.49  6113.5  420.01  6142.7  421.85  6207.3  422.57
  6328.1  425.98  6342.7   427.2  6421.9   429.3  6442.7  430.94    6500  431.79
#Mann= 3 ,-1 , 0
    4219      .1       0  5025.1     .07       0  5031.1      .1       0
Bank Sta=4914.7,5250
XS Rating Curve= 0 ,0
Exp/Cntr=0.3,0.1

Type RM Length L Ch R = 1 ,12681   ,244,244,244
BEGIN DESCRIPTION:
TEPECATE CREEK 21.0
END DESCRIPTION:
XS GIS Cut Line= 3
      2188087.71     13219696.85      2187687.72     13219096.85
      2186487.72     13218596.85
#Sta/Elev= 30
  4278.9  417.49  4373.5  413.58  4423.1  410.33  4495.2  408.14  4580.9   404.1
  4842.3  399.84  4848.3  398.85  4927.9  398.36  4935.4  397.41  4989.5  396.29
  4992.2  395.79  4995.5  396.29  5139.2  398.03  5184.2  399.57  5227.5  400.56
  5250.8   402.3  5314.2  403.67  5322.3  404.79  5335.8  404.43  5357.5   406.2
  5529.2  409.15  5541.7  410.56  5587.7  410.24  5794.6  413.68  5855.8  416.17
  5977.7  418.41    6170  424.11  6191.7  425.62  6261.5  426.54    6300  428.08
#Mann= 3 ,-1 , 0
  4278.9      .1       0  4989.5     .07       0  4995.5      .1       0
Bank Sta=4842.3,5184.2
XS Rating Curve= 0 ,0
Exp/Cntr=0.3,0.1

Type RM Length L Ch R = 1 ,12437   ,527,527,527
BEGIN DESCRIPTION:
Mapping XS 68c82ebb
END DESCRIPTION:
XS GIS Cut Line= 3
      2188926.08     13219626.95      2188005.95     13219001.95
      2186826.89     13218421.09
#Sta/Elev= 30
  3644.4  430.12  3751.2   427.3  3959.4  418.96  4031.3  417.75  4040.2  416.44
    4112  413.71  4189.9  412.43  4204.9   410.6  4246.9  410.79  4369.6   406.3
  4765.9  399.48  4848.8  399.11  4870.9  399.15  4960.8  397.54  4966.6  395.83
  4983.3  395.83  4985.9  394.52  4988.6  394.02  4991.9  394.52  5044.6  395.87
  5050.6  398.79  5056.2  399.28  5066.9  399.28  5078.7  396.72  5095.6   395.8
  5156.1  397.64  5423.6  405.02  5735.7  411.81  5780.6  411.81  6071.1  419.09
#Mann= 5 ,-1 , 0
  3644.4      .1       0  4848.8     .05       0  4870.9      .1       0
  4985.9     .07       0  4991.9      .1       0
Bank Sta=4960.8,5156.1
XS Rating Curve= 0 ,0
Exp/Cntr=0.3,0.1

Type RM Length L Ch R = 1 ,11910   ,103,103,103
BEGIN DESCRIPTION:
TEPECATE CREEK 20.0
END DESCRIPTION:
XS GIS Cut Line= 4
       2188700.4     13218958.55      2188196.92      13218576.6
      2187910.47     13218376.95      2187261.05     13218290.36
#Sta/Elev= 30
  4196.4  417.78    4250  416.83  4271.2  415.03  4470.9  408.96  4585.3  404.27
  4635.2  403.61  4664.2  401.74  4841.2  397.47  4927.6  396.19  4963.3  391.93
    4993  391.67  4999.1  389.11  5022.4  390.19  5028.8  391.63  5043.6  390.52
  5046.7  388.91  5049.5  388.41  5052.7  388.91  5058.5  390.88  5121.3  392.16
    5130  393.86  5144.3  393.96  5150.9  396.88  5165.8  397.44  5331.6   401.8
  5353.2  403.31  5392.2  404.92    5493  405.84  5605.3  409.74  5832.7  415.03
#Mann= 5 ,-1 , 0
  4196.4      .1       0  5046.7     .07       0  5052.7      .1       0
  5353.2     .05       0  5605.3      .1       0
Bank Sta=4841.2,5165.8
XS Rating Curve= 0 ,0
Exp/Cntr=0.3,0.1

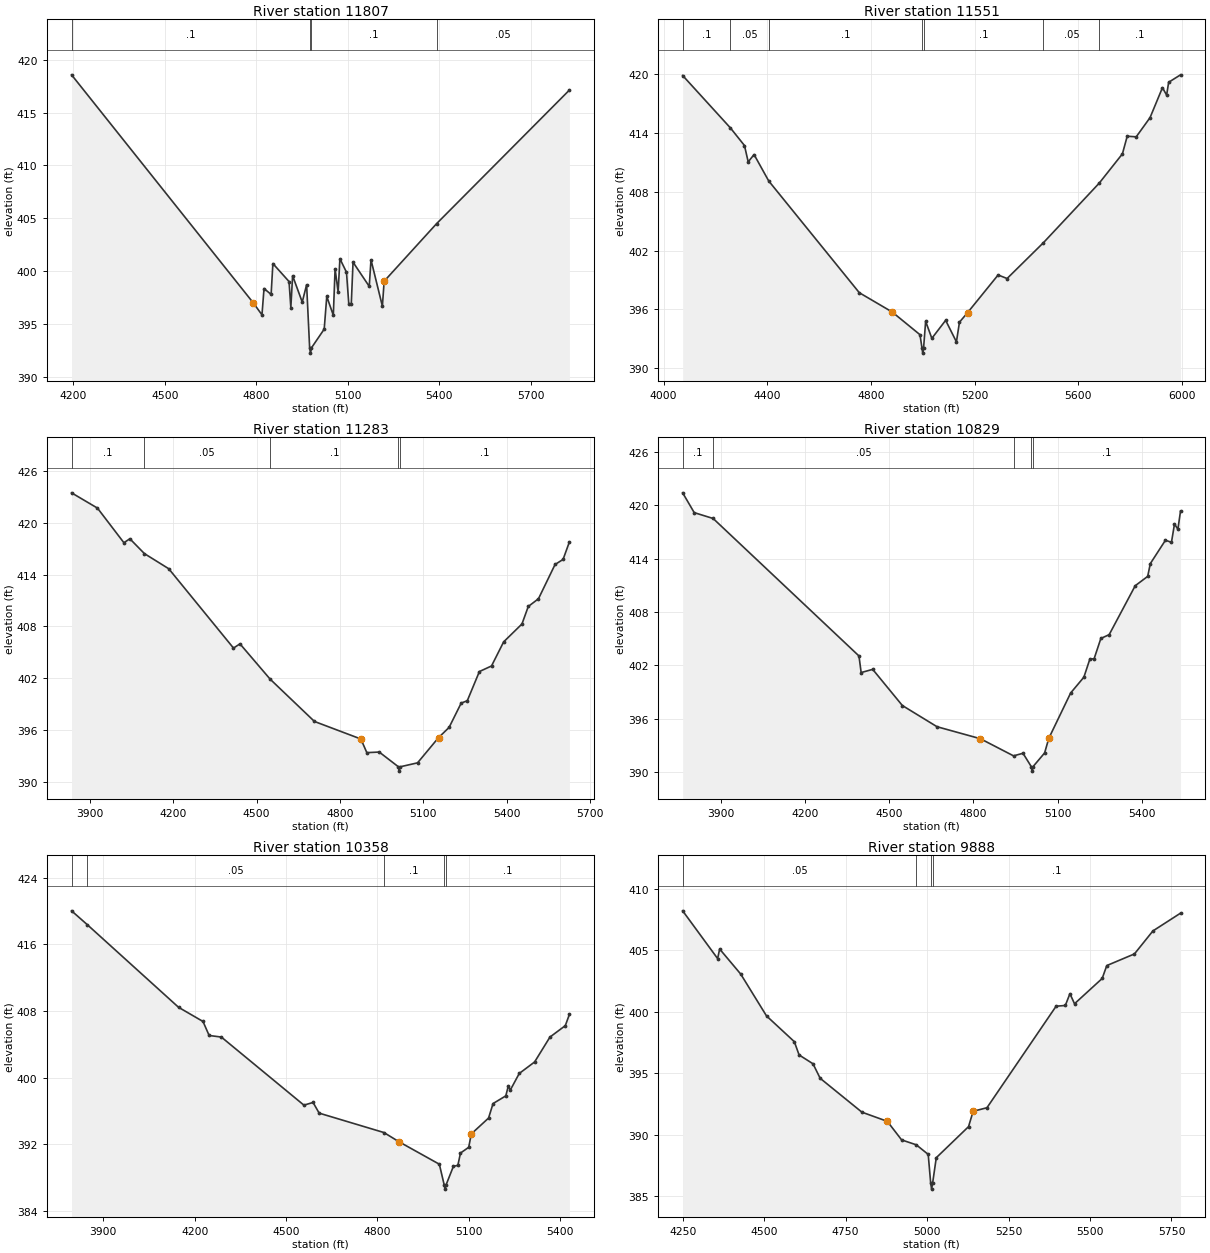
Type RM Length L Ch R = 1 ,11807   ,256,256,256
BEGIN DESCRIPTION:
TEPECATE CREEK 19.0
END DESCRIPTION:
XS GIS Cut Line= 4
      2188726.19     13218877.75      2188228.01     13218469.57
      2187524.08     13218064.57      2187351.58     13218023.04
#Sta/Elev= 30
  4194.1  418.57  4790.2  397.01  4818.9  395.87  4825.6  398.36  4848.9   397.8
  4854.7  400.72  4907.7  399.02  4913.6  396.56  4919.4  399.57    4951  397.08
  4965.4  398.72  4975.3  392.75  4978.1  392.25  4981.3  392.75  5023.1  394.52
  5031.5  397.61    5053  395.83  5058.8  400.23  5068.8  398.03  5074.6  401.18
  5096.2   399.9  5103.8  396.88  5111.9  396.88  5117.7  400.85  5170.9  398.56
  5176.6  401.08    5214  396.69  5219.8  399.05  5391.7  404.49  5827.7  417.13
#Mann= 4 ,-1 , 0
  4194.1      .1       0  4975.3     .07       0  4981.3      .1       0
  5391.7     .05       0
Bank Sta=4790.2,5219.8
XS Rating Curve= 0 ,0
Exp/Cntr=0.3,0.1

Type RM Length L Ch R = 1 ,11551   ,268,268,268
BEGIN DESCRIPTION:
Mapping XS eaa0ec6b
END DESCRIPTION:
XS GIS Cut Line= 3
       2188795.9      13218854.4      2188301.09      13218220.7
      2187268.13     13217795.36
#Sta/Elev= 30
  4073.4  419.88  4257.6  414.53  4311.9  412.73  4326.3  411.06  4348.9  411.81
  4405.5  409.11    4755   397.7  4881.9  395.73  4989.2  393.41    4997  392.03
  4999.8  391.53    5003  392.03    5011  394.78  5034.9  393.04  5088.2  394.88
  5129.8  392.68  5141.5  394.69    5173  395.67  5290.6  399.51  5325.3  399.15
  5465.6  402.81  5680.8  408.89  5770.3  411.88  5788.8  413.68  5823.6  413.62
  5876.9  415.58  5924.8  418.64  5940.9  417.88  5948.7  419.19  5994.5  419.95
#Mann= 7 ,-1 , 0
  4073.4      .1       0  4257.6     .05       0  4405.5      .1       0
    4997     .07       0    5003      .1       0  5465.6     .05       0
  5680.8      .1       0
Bank Sta=4881.9,5173
XS Rating Curve= 0 ,0
Exp/Cntr=0.3,0.1

Type RM Length L Ch R = 1 ,11283   ,454,454,454
BEGIN DESCRIPTION:
TEPECATE CREEK 18.0
END DESCRIPTION:
XS GIS Cut Line= 3
      2188887.73     13218946.86      2188287.72     13217946.85
      2187987.72     13217396.85
#Sta/Elev= 30
  3833.8  423.46  3927.1  421.69  4022.3  417.68  4043.7  418.14  4096.2  416.42
  4183.7  414.67  4416.9  405.48  4440.2  405.97  4548.9  401.88  4708.5  396.98
  4875.6  394.95    4897  393.37  4941.7  393.44  5010.8  391.73  5013.5  391.23
  5016.8  391.73  5079.7  392.19  5155.2  395.11  5193.2  396.29  5236.8  399.11
  5258.7  399.38  5302.3  402.76    5346  403.41  5389.7   406.2  5455.6  408.27
  5478.4   410.3    5515  411.19  5574.8  415.16  5603.7  415.75  5626.5  417.78
#Mann= 5 ,-1 , 0
  3833.8      .1       0  4096.2     .05       0  4548.9      .1       0
  5010.8     .07       0  5016.8      .1       0
Bank Sta=4875.6,5155.2
XS Rating Curve= 0 ,0
Exp/Cntr=0.3,0.1

Type RM Length L Ch R = 1 ,10829   ,471,471,471
BEGIN DESCRIPTION:
TEPECATE CREEK 17.0
END DESCRIPTION:
XS GIS Cut Line= 3
      2188887.71     13218846.82      2188587.72     13217646.85
      2188387.73     13217146.87
#Sta/Elev= 30
  3763.1  421.42  3804.3  419.19  3871.8  418.53  4391.8  403.05  4399.6  401.18
  4440.8  401.54  4546.5  397.47  4670.2  395.08  4824.8  393.73    4943   391.8
  4976.8  392.09  5006.4  390.58  5009.2  390.08  5012.4  390.58  5053.9  392.13
  5068.7  393.77  5146.7  398.88  5193.9  400.66  5215.4  402.72  5230.2  402.72
  5254.4  405.02  5284.1  405.45    5377  410.96  5421.4  412.01  5430.8  413.45
  5484.7  416.08  5506.2  415.85    5517  417.91  5529.1  417.32  5538.5  419.36
#Mann= 5 ,-1 , 0
  3763.1      .1       0  3871.8     .05       0    4943      .1       0
  5006.4     .07       0  5012.4      .1       0
Bank Sta=4824.8,5068.7
XS Rating Curve= 0 ,0
Exp/Cntr=0.3,0.1

Type RM Length L Ch R = 1 ,10358   ,470,470,470
BEGIN DESCRIPTION:
TEPECATE CREEK 16.0
END DESCRIPTION:
XS GIS Cut Line= 3
      2188937.72      13218796.9      2189037.72     13217596.86
      2188787.73     13217246.87
#Sta/Elev= 30
  3795.8  420.01  3847.4  418.35  4147.1  408.43  4227.3  406.73  4247.4  405.05
  4287.5  404.86  4558.5  396.69  4588.6  397.01  4608.6  395.73  4821.3   393.4
  4869.5  392.32  5003.1   389.6  5019.1  387.11  5021.9  386.61  5025.1  387.11
  5049.2  389.34  5063.9  389.47  5072.5  390.94  5099.5  391.63  5108.1  393.24
  5164.7  395.14  5179.4  396.88  5221.2   397.8  5229.8  399.02  5235.9  398.49
  5265.4  400.49  5315.8  401.87  5366.2  404.86  5416.6  406.23  5430.1  407.58
#Mann= 5 ,-1 , 0
  3795.8      .1       0  3847.4     .05       0  4821.3      .1       0
  5019.1     .07       0  5025.1      .1       0
Bank Sta=4869.5,5108.1
XS Rating Curve= 0 ,0
Exp/Cntr=0.3,0.1

Type RM Length L Ch R = 1 ,9888    ,492,492,492
BEGIN DESCRIPTION:
TEPECATE CREEK 15.0
END DESCRIPTION:
XS GIS Cut Line= 3
      2189937.72     13218146.85      2189487.72     13217546.85
      2188937.73     13216996.87
#Sta/Elev= 30
    4250  408.23  4357.3  404.34  4363.5  405.12  4428.1  403.08  4507.3  399.67
  4592.7  397.57  4607.3  396.49    4650  395.77  4671.9  394.59    4800  391.83
  4878.1  391.08  4921.9  389.57  4966.9  389.17  5003.5  388.39  5011.1  386.06
  5013.9  385.56  5017.1  386.06  5028.3  388.12  5127.3  390.65  5141.4   391.9
  5183.8  392.19    5396  400.46  5424.3  400.52  5438.4  401.48  5452.5  400.66
  5537.4  402.72  5551.5  403.77  5636.4  404.72    5693  406.59  5777.8  408.04
#Mann= 4 ,-1 , 0
    4250     .05       0  4966.9      .1       0  5011.1     .07       0
  5017.1      .1       0
Bank Sta=4878.1,5141.4
XS Rating Curve= 0 ,0
Exp/Cntr=0.3,0.1