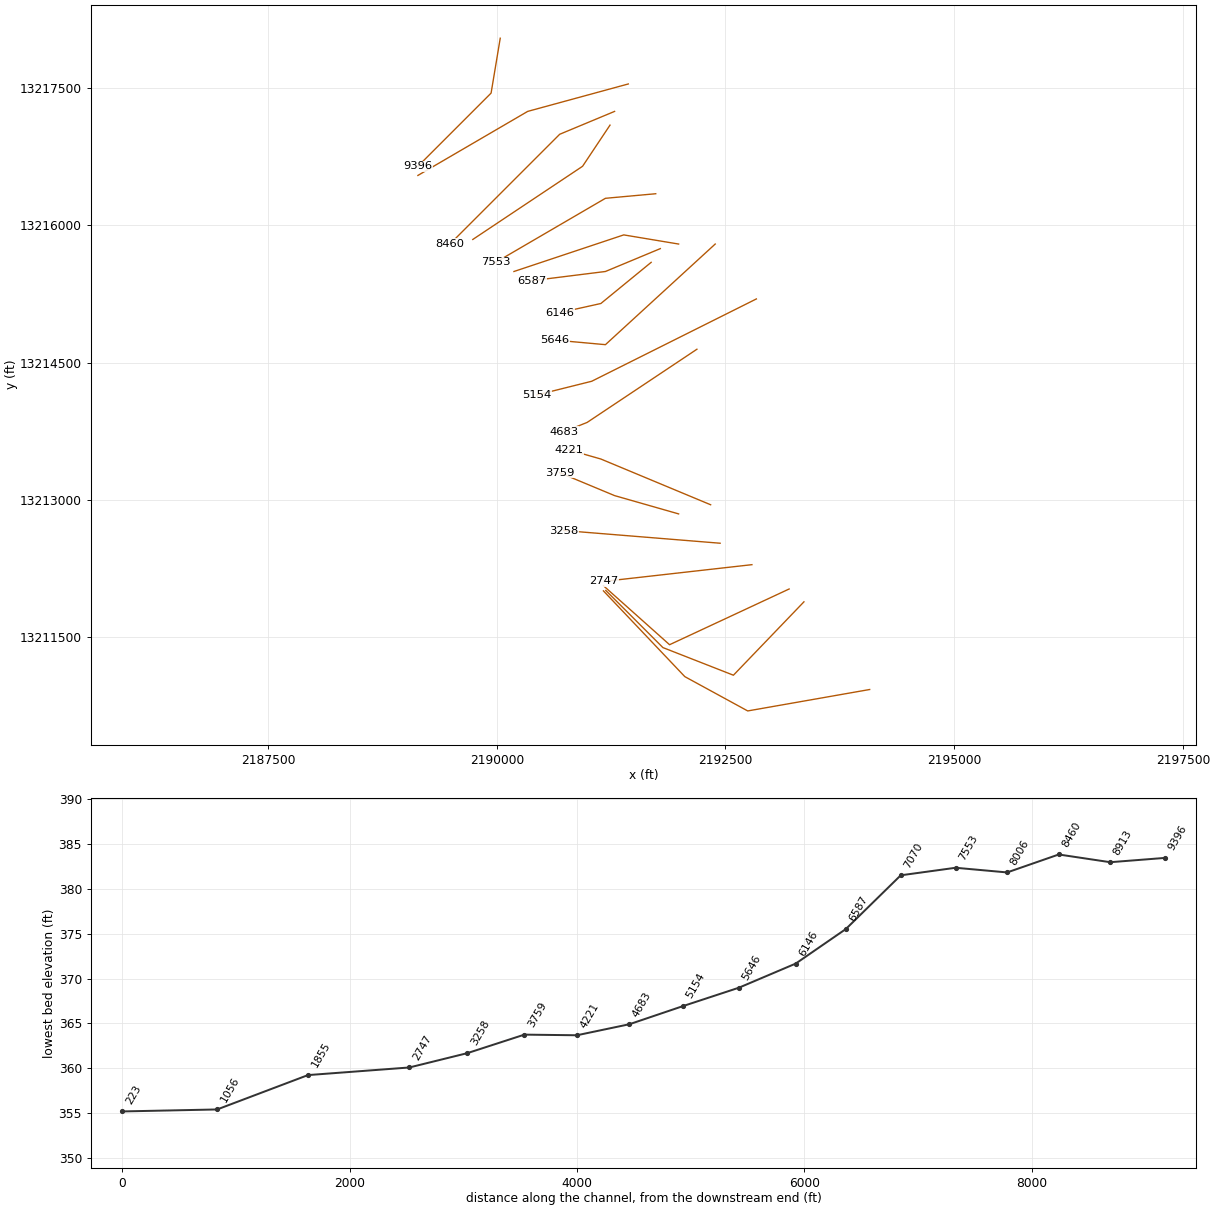
HEC-RAS study TEPECATE CREEK.prj: TEPECATE CREEK Base Level Engineering

--- TEPECATE CREEK.g01 (geometry) --- (continued)

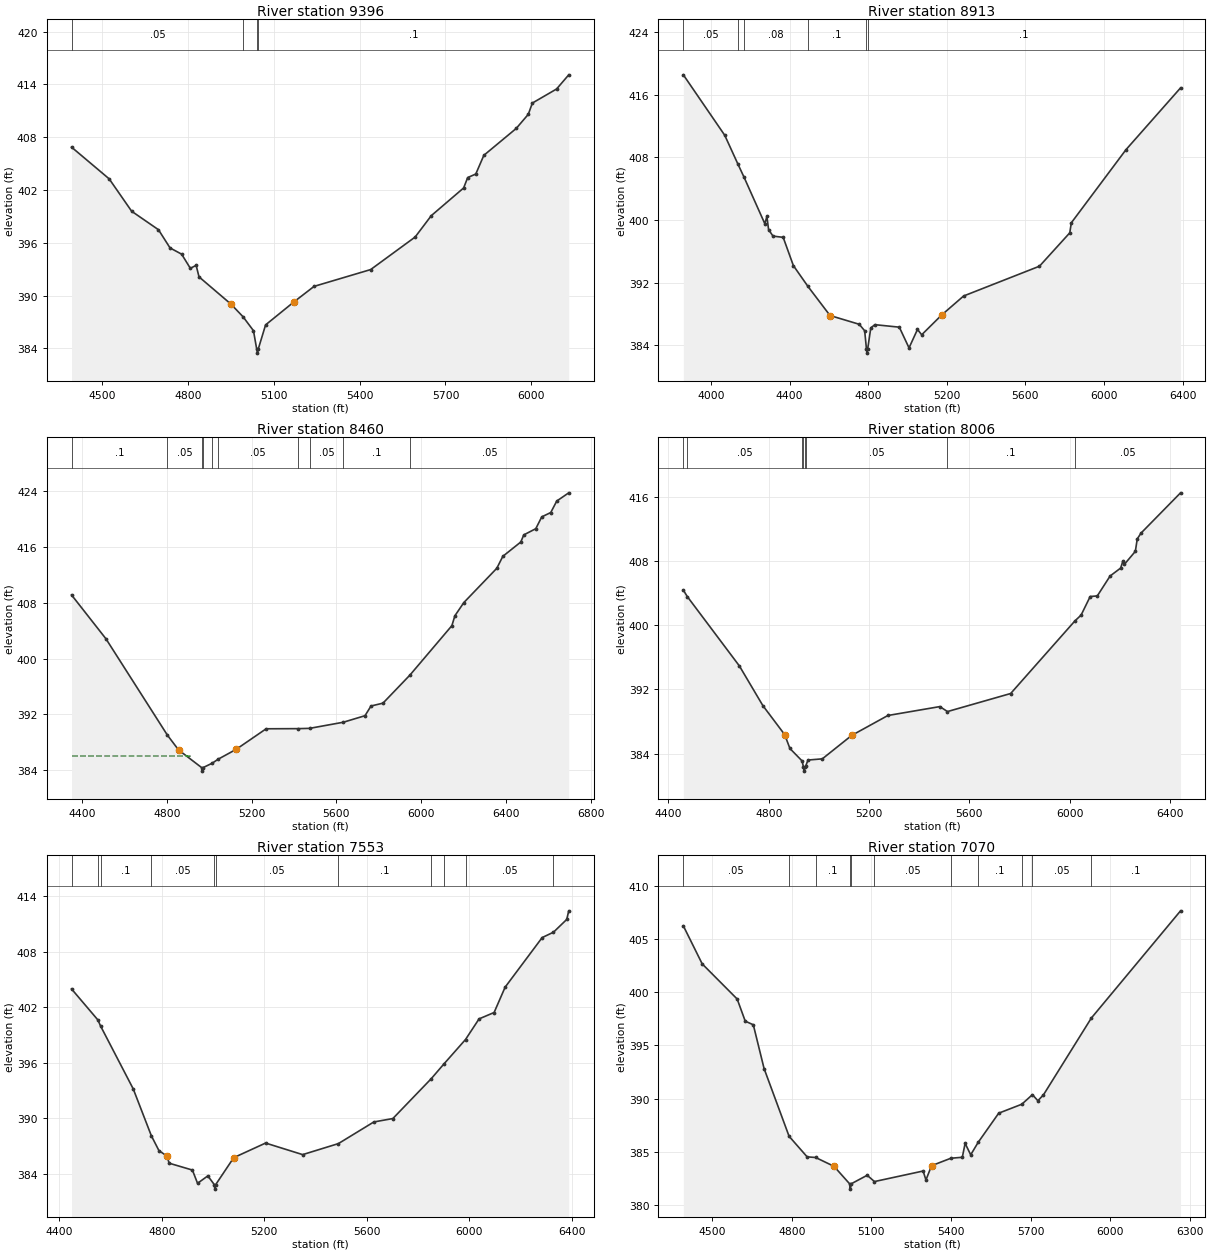
Type RM Length L Ch R = 1 ,9396    ,483,483,483
BEGIN DESCRIPTION:
TEPECATE CREEK 14.0
END DESCRIPTION:
XS GIS Cut Line= 3
      2190037.72     13218046.88      2189937.72     13217446.85
       2189137.7     13216646.83
#Sta/Elev= 30
  4391.7  406.87  4523.5  403.26  4602.1  399.58  4695.9  397.48  4736.4  395.41
    4777   394.7  4807.4  393.09  4827.7  393.43  4837.8  392.12  4949.3  389.03
  4992.2  387.57  5028.3     386  5039.4  383.95  5042.2  383.45  5045.4  383.95
  5070.7  386.66  5169.7  389.27  5240.4  391.04  5438.4  392.95    5594  396.65
  5650.5  399.08  5763.7  402.23  5777.8  403.41  5806.1  403.81  5834.4  405.94
  5947.5  408.99  5989.9   410.6  6004.1  411.88  6088.9  413.48  6131.4  415.09
#Mann= 4 ,-1 , 0
  4391.7     .05       0  4992.2      .1       0  5039.4     .07       0
  5045.4      .1       0
Bank Sta=4949.3,5169.7
XS Rating Curve= 0 ,0
Exp/Cntr=0.3,0.1

Type RM Length L Ch R = 1 ,8913    ,453,453,453
BEGIN DESCRIPTION:
TEPECATE CREEK 13.0
END DESCRIPTION:
XS GIS Cut Line= 3
      2191437.74     13217546.86      2190337.72     13217246.86
      2189137.76     13216546.88
#Sta/Elev= 30
  3859.8  418.57  4070.6  410.83  4137.3  407.16  4168.7  405.47  4274.4  399.52
  4284.8  400.45  4293.4  398.77  4315.9  397.94  4367.7  397.78  4419.5  394.17
  4493.2  391.52  4606.1  387.78  4754.7  386.66  4782.3  385.83  4791.4  383.47
  4794.2  382.97  4797.4  383.47  4813.4   386.2  4834.2  386.61  4958.5  386.29
  5007.9  383.64  5050.9     386  5072.4  385.32  5174.1  387.85  5285.7  390.28
  5671.5  394.09  5825.7  398.36  5833.5  399.64  6111.4  408.99  6389.2   416.9
#Mann= 6 ,-1 , 0
  3859.8     .05       0  4137.3      .1       0  4168.7     .08       0
  4493.2      .1       0  4791.4     .07       0  4797.4      .1       0
Bank Sta=4606.1,5174.1
XS Rating Curve= 0 ,0
Exp/Cntr=0.3,0.1

Type RM Length L Ch R = 1 ,8460    ,454,454,454
BEGIN DESCRIPTION:
TEPECATE CREEK 12.0
END DESCRIPTION:
XS GIS Cut Line= 3
      2191287.72     13217246.85      2190687.72     13216996.85
      2189487.69     13215796.82
#Sta/Elev= 30
    4350  409.13  4512.5  402.83  4802.5     389  4855.4  386.87  4964.5  384.33
  4967.3  383.83  4970.5  384.33  5014.3  384.97  5041.4  385.53  5127.3  386.96
  5268.7  389.91  5418.6  389.93  5473.7  389.97    5633  390.85  5735.4  391.79
  5763.7  393.18  5820.2  393.59  5947.7  397.63  6145.5  404.72  6159.7  406.14
  6202.1  408.04  6357.6  412.96  6385.9  414.67  6470.8  416.73  6484.9  417.75
  6541.5  418.64  6569.8  420.34  6612.2  420.96  6640.5  422.61  6697.1  423.79
#Mann= 10 ,-1 , 0
    4350      .1       0  4802.5     .05       0  4964.5     .03       0
  4970.5     .05       0  5014.3      .1       0  5041.4     .05       0
  5418.6      .1       0  5473.7     .05       0    5633      .1       0
  5947.7     .05       0
#XS Ineff= 2 , 0
         4908.21     386
Permanent Ineff=
       F       F
Bank Sta=4855.4,5127.3
XS Rating Curve= 0 ,0
Exp/Cntr=0.3,0.1

Type RM Length L Ch R = 1 ,8006    ,453,453,453
BEGIN DESCRIPTION:
TEPECATE CREEK 11.0
END DESCRIPTION:
XS GIS Cut Line= 3
       2191237.7     13217096.83      2190937.72     13216646.85
      2189737.74     13215846.87
#Sta/Elev= 30
  4459.2  404.38  4474.9  403.58    4683  394.92  4776.2     390  4863.3  386.38
  4884.3  384.65  4932.8   383.1  4938.4  382.33  4941.2  381.83  4944.4  382.33
  4947.7  382.51  4956.4  383.21  5013.5  383.36  5130.7  386.28  5274.9  388.76
  5482.2  389.87  5512.6  389.25  5764.7   391.5  6020.8  400.54  6045.6  401.27
  6081.7  403.58  6110.2  403.66  6161.3  406.14  6203.4  407.13  6212.4  408.02
  6218.4   407.6  6261.9  409.21  6269.5  410.76  6284.5  411.48  6442.2   416.5
#Mann= 8 ,-1 , 0
  4459.2      .1       0  4474.9     .05       0  4932.8      .1       0
  4938.4     .03       0  4944.4      .1       0  4947.7     .05       0
  5512.6      .1       0  6020.8     .05       0
Bank Sta=4863.3,5130.7
XS Rating Curve= 0 ,0
Exp/Cntr=0.3,0.1

Type RM Length L Ch R = 1 ,7553    ,483,483,483
BEGIN DESCRIPTION:
TEPECATE CREEK 10.0
END DESCRIPTION:
XS GIS Cut Line= 3
      2191737.75     13216346.86      2191187.72     13216296.85
      2189987.76     13215596.88
#Sta/Elev= 30
  4447.7  403.99  4550.5  400.64  4561.3  399.97  4688.7  393.18  4759.5  388.11
  4789.1  386.51  4819.3  385.94  4829.3  385.15  4919.7  384.41  4939.8  382.98
  4979.9  383.78  5004.9  382.85  5007.6  382.35  5010.9  382.85    5081  385.75
  5205.5  387.33  5350.2  386.08  5489.7  387.27  5628.1  389.61  5702.5  389.98
  5852.4  394.29  5901.5  395.87  5986.1  398.52    6039  400.75  6097.8  401.44
  6140.8  404.18  6285.5  409.54  6329.6  410.12  6381.4   411.5  6389.2  412.43
#Mann= 11 ,-1 , 0
  4447.7      .1       0  4550.5     .05       0  4561.3      .1       0
  4759.5     .05       0  5004.9     .03       0  5010.9     .05       0
  5489.7      .1       0  5852.4     .05       0  5901.5      .1       0
  5986.1     .05       0  6329.6      .1       0
Bank Sta=4819.3,5081
XS Rating Curve= 0 ,0
Exp/Cntr=0.3,0.1

Type RM Length L Ch R = 1 ,7070    ,483,483,483
BEGIN DESCRIPTION:
TEPECATE CREEK 9.0
END DESCRIPTION:
XS GIS Cut Line= 3
      2191987.74     13215796.85      2191387.72     13215896.85
      2190187.73     13215496.86
#Sta/Elev= 30
  4391.7  406.23  4462.7  402.66  4594.5  399.36  4624.9  397.28  4655.3  396.94
  4695.9  392.83  4790.1  386.47  4858.1  384.54  4890.1  384.48  4959.4  383.65
  5018.1  382.01  5020.8  381.51  5024.1  382.01  5084.3  382.81  5111.7  382.22
  5295.1  383.21  5305.7  382.37  5326.8  383.71  5399.6  384.41  5442.7   384.5
  5453.3  385.81  5474.3  384.73  5502.1  385.89  5579.8  388.64  5666.7  389.48
  5706.9  390.38  5727.3  389.81  5748.4  390.36  5928.7  397.57  6264.9  407.64
#Mann= 11 ,-1 , 0
  4391.7     .05       0  4790.1     .08       0  4890.1      .1       0
  5018.1     .07       0  5024.1      .1       0  5111.7     .05       0
  5399.6     .08       0  5502.1      .1       0  5666.7     .08       0
  5706.9     .05       0  5928.7      .1       0
Bank Sta=4959.4,5326.8
XS Rating Curve= 0 ,0
Exp/Cntr=0.3,0.1

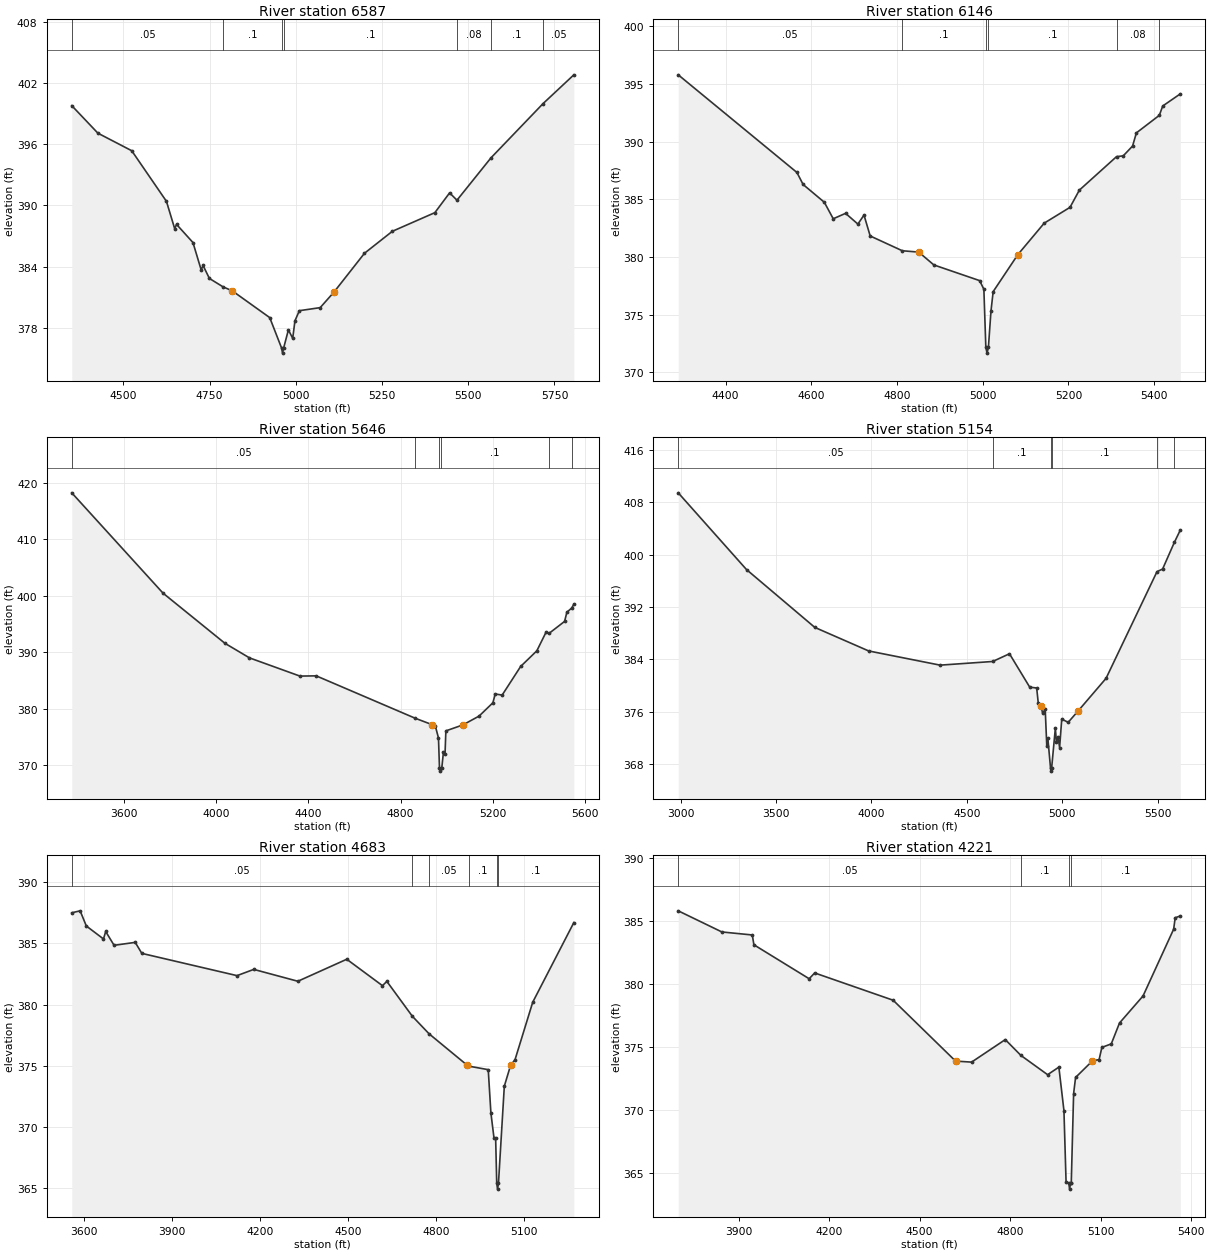
Type RM Length L Ch R = 1 ,6587    ,441,441,441
BEGIN DESCRIPTION:
TEPECATE CREEK 8.0
END DESCRIPTION:
XS GIS Cut Line= 3
      2191787.72     13215746.85      2191187.72     13215496.85
      2190387.75     13215396.86
#Sta/Elev= 30
    4350  399.78  4425.8  397.08  4523.9  395.36  4624.6   390.4  4648.5  387.72
  4653.9  388.14  4701.5  386.36  4725.4  383.67  4730.8  384.11  4749.2  382.84
  4788.6  382.02  4815.8  381.62  4924.2     379  4958.5  376.02  4961.3  375.52
  4964.5  376.02  4978.3   377.8  4990.8  376.97  4997.3  378.69  5010.1  379.68
  5070.5  379.98  5110.9  381.52    5199  385.31  5279.7  387.46  5403.1  389.29
  5445.9  391.23  5467.2  390.51  5565.8  394.66  5716.9  399.98  5806.2   402.8
#Mann= 7 ,-1 , 0
    4350     .05       0  4788.6      .1       0  4958.5     .07       0
  4964.5      .1       0  5467.2     .08       0  5565.8      .1       0
  5716.9     .05       0
Bank Sta=4815.8,5110.9
XS Rating Curve= 0 ,0
Exp/Cntr=0.3,0.1

Type RM Length L Ch R = 1 ,6146    ,500,500,500
BEGIN DESCRIPTION:
TEPECATE CREEK 7.0
END DESCRIPTION:
XS GIS Cut Line= 3
      2191687.69     13215596.83      2191137.72     13215146.85
       2190687.7     13215046.85
#Sta/Elev= 30
  4289.4  395.78  4566.4  387.32  4580.8  386.28  4630.3  384.74  4651.1  383.31
  4679.9  383.78  4708.6  382.85  4722.9  383.63  4737.3  381.82  4812.2  380.54
  4850.7  380.42  4885.9  379.31  4992.8  377.95  5002.6   377.2  5007.2  372.17
    5010  371.67  5013.2  372.17  5019.2  375.32  5024.3     377    5082  380.21
  5143.4  382.93  5203.6   384.3  5225.4  385.79  5312.1  388.69  5327.8  388.76
  5349.6  389.61  5358.5  390.75    5412  392.27    5420  393.08    5461  394.13
#Mann= 6 ,-1 , 0
  4289.4     .05       0  4812.2      .1       0  5007.2     .07       0
  5013.2      .1       0  5312.1     .08       0    5412      .1       0
Bank Sta=4850.7,5082
XS Rating Curve= 0 ,0
Exp/Cntr=0.3,0.1

Type RM Length L Ch R = 1 ,5646    ,492,492,492
BEGIN DESCRIPTION:
TEPECATE CREEK 6.0
END DESCRIPTION:
XS GIS Cut Line= 3
      2192387.73     13215796.87      2191187.72     13214696.85
      2190637.69     13214746.86
#Sta/Elev= 30
  3372.1   418.2  3768.3  400.46  4037.1  391.59  4143.8  389.01  4362.7  385.79
  4433.6  385.83  4863.6  378.33  4936.2  377.21  4950.4  377.02  4964.5  374.84
  4968.9  369.48  4971.7  368.98  4974.9  369.48  4978.7  369.49  4986.1  372.36
  4992.9  371.98  4996.6   376.1  5070.3  377.15  5140.6  378.71  5200.8  381.07
  5210.9  382.62    5241  382.43  5321.3  387.49  5391.6  390.26  5431.8  393.57
  5444.3  393.33  5512.1  395.46  5522.1  397.09  5543.2  397.83  5552.3   398.5
#Mann= 6 ,-1 , 0
  3372.1     .05       0  4863.6      .1       0  4968.9     .07       0
  4974.9      .1       0  5444.3     .08       0  5543.2      .1       0
Bank Sta=4936.2,5070.3
XS Rating Curve= 0 ,0
Exp/Cntr=0.3,0.1

Type RM Length L Ch R = 1 ,5154    ,471,471,471
BEGIN DESCRIPTION:
TEPECATE CREEK 5.0
END DESCRIPTION:
XS GIS Cut Line= 3
      2192837.76     13215196.87      2191037.72     13214296.86
      2190437.69     13214146.85
#Sta/Elev= 30
  2987.5  409.47  3345.3  397.74  3703.1   388.9  3985.4   385.3  4359.9  383.13
  4635.3  383.69  4723.3  384.87  4829.5  379.76  4865.8  379.64  4874.2  377.32
  4888.2  376.95  4896.6  375.82  4910.6  376.36  4918.9  370.71  4924.5  371.92
  4938.3  367.43  4941.1  366.93  4944.3  367.43  4963.7  373.49  4969.3  371.38
  4977.6   372.2    4986  370.54  4997.2  374.88  5030.9  374.39  5082.5  376.11
  5229.3  381.11  5496.3  397.42  5525.7  397.82    5587  401.88  5618.5  403.78
#Mann= 6 ,-1 , 0
  2987.5     .05       0  4635.3      .1       0  4938.3     .07       0
  4944.3      .1       0  5496.3     .08       0    5587      .1       0
Bank Sta=4888.2,5082.5
XS Rating Curve= 0 ,0
Exp/Cntr=0.3,0.1

Type RM Length L Ch R = 1 ,4683    ,462,462,462
BEGIN DESCRIPTION:
TEPECATE CREEK 4.0
END DESCRIPTION:
XS GIS Cut Line= 3
       2192187.7     13214646.84      2190987.72     13213846.85
      2190737.68     13213746.84
#Sta/Elev= 30
  3557.8  387.51  3586.3  387.67  3607.4  386.43  3665.9  385.37  3673.5  385.98
    3702  384.85  3774.1  385.09  3796.6  384.19  4121.1  382.37  4178.2  382.88
  4328.5  381.91  4495.2  383.71  4616.9  381.55  4631.9   381.9  4718.7  379.05
  4775.9  377.61  4905.4  375.05  4910.6  374.97  4977.5  374.68  4986.5  371.15
    4997  369.11  5002.7  369.11  5006.4  365.41  5009.2  364.91  5012.4  365.41
  5032.3  373.33  5053.9  375.05  5068.7  375.49  5129.2   380.2  5269.3  386.71
#Mann= 6 ,-1 , 0
  3557.8     .05       0  4718.7      .1       0  4775.9     .05       0
  4910.6      .1       0  5006.4     .07       0  5012.4      .1       0
Bank Sta=4905.4,5053.9
XS Rating Curve= 0 ,0
Exp/Cntr=0.3,0.1

Type RM Length L Ch R = 1 ,4221    ,462,462,462
BEGIN DESCRIPTION:
TEPECATE CREEK 3.0
END DESCRIPTION:
XS GIS Cut Line= 3
      2192337.72     13212946.85      2191137.72     13213446.85
      2190787.73     13213546.85
#Sta/Elev= 30
    3700  385.81  3844.6  384.13  3945.4  383.89  3950.8  383.11  4133.9  380.41
  4152.3  380.87  4412.3   378.7  4619.2  373.86  4672.3  373.78  4783.9  375.57
  4835.8  374.31  4924.2  372.78  4961.5  373.38  4978.3  369.93  4985.4  364.24
  4994.3  364.18    4997  363.68  5000.3  364.18  5002.6  364.18  5010.4  371.28
  5016.9  372.56  5072.8  373.88  5094.9  373.98    5104  374.95  5135.2  375.23
  5162.5  376.89  5240.5  379.04  5341.9  384.35  5347.1  385.26    5364   385.4
#Mann= 4 ,-1 , 0
    3700     .05       0  4835.8      .1       0  4994.3     .07       0
  5000.3      .1       0
Bank Sta=4619.2,5072.8
XS Rating Curve= 0 ,0
Exp/Cntr=0.3,0.1

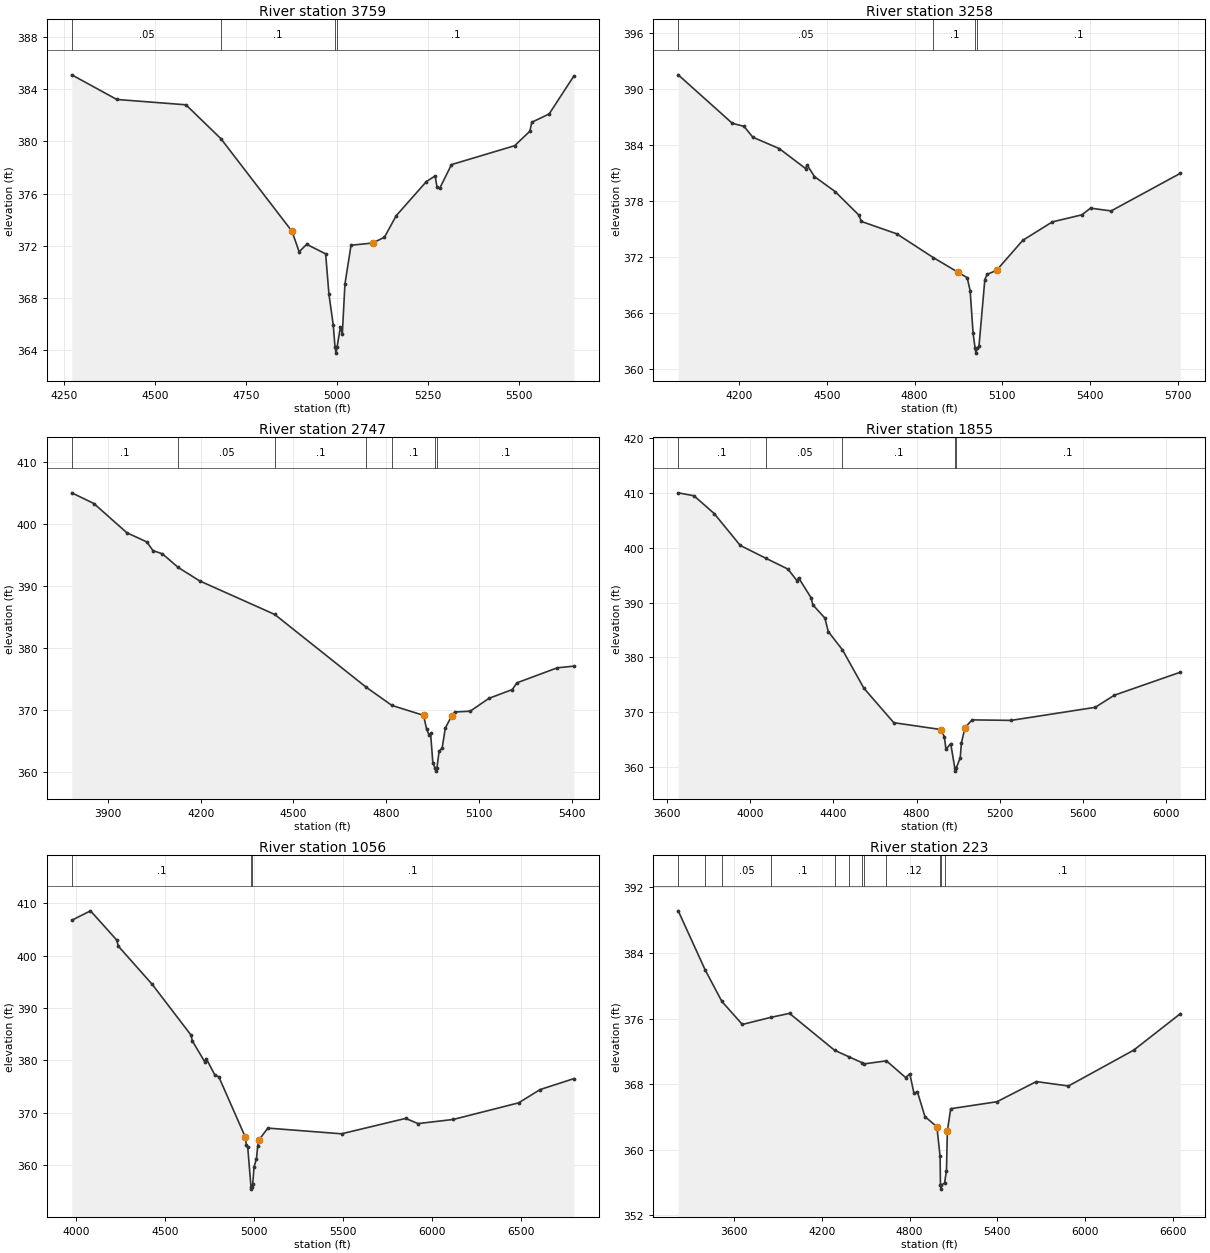
Type RM Length L Ch R = 1 ,3759    ,501,501,501
BEGIN DESCRIPTION:
TEPECATE CREEK 2.0
END DESCRIPTION:
XS GIS Cut Line= 3
      2191987.71     13212846.86      2191287.72     13213046.85
      2190687.72     13213296.85
#Sta/Elev= 30
    4272  385.11  4395.5  383.22  4585.3  382.81  4681.3  380.21  4876.5   373.1
    4896  371.53  4916.8   372.1  4968.8  371.37  4977.9  368.25  4989.6  365.92
  4994.4  364.25  4997.2  363.75  5000.4  364.25  5009.2  365.74  5014.6  365.23
  5021.7  369.05  5038.5  372.03  5097.5   372.2    5130  372.64  5162.5   374.3
  5245.4  376.92  5269.2  377.35  5274.6  376.48  5281.7  376.39  5314.2  378.22
  5487.5  379.67  5529.2  380.78  5534.6  381.47  5582.3  382.11    5650  385.02
#Mann= 4 ,-1 , 0
    4272     .05       0  4681.3      .1       0  4994.4     .07       0
  5000.4      .1       0
Bank Sta=4876.5,5097.5
XS Rating Curve= 0 ,0
Exp/Cntr=0.3,0.1

Type RM Length L Ch R = 1 ,3258    ,511,511,511
BEGIN DESCRIPTION:
Mapping XS e269f8c4
END DESCRIPTION:
XS GIS Cut Line= 2
      2192441.71     13212526.26      2190732.14      13212665.1
#Sta/Elev= 30
  3992.7   391.5  4177.3  386.31  4217.4  385.98  4247.5  384.82  4337.8   383.6
  4427.8  381.46  4432.8  381.85  4458.2   380.6  4528.5     379  4608.7  376.51
  4618.7  375.79  4739.1  374.47  4864.3  371.92  4949.8  370.33  4979.9  369.77
    4990  368.36    5000  363.82    5007  362.19  5009.8  361.69    5013  362.19
  5020.1  362.42  5040.1  369.57  5047.6  370.12  5080.3  370.56  5169.6  373.77
  5270.9  375.75  5371.2   376.5  5401.3  377.22  5471.5  376.92  5707.9  380.95
#Mann= 4 ,-1 , 0
  3992.7     .05       0  4864.3      .1       0    5007     .07       0
    5013      .1       0
Bank Sta=4949.8,5080.3
XS Rating Curve= 0 ,0
Exp/Cntr=0.3,0.1

Type RM Length L Ch R = 1 ,2747    ,892,892,892
BEGIN DESCRIPTION:
Mapping XS 85d2d875
END DESCRIPTION:
XS GIS Cut Line= 2
      2192788.98     13212291.89      2191174.34     13212109.59
#Sta/Elev= 30
  3782.6  405.05  3854.3  403.32  3960.6  398.61  4025.4  397.12  4045.4  395.72
  4075.7   395.2  4127.3  392.99  4196.5  390.82  4439.5   385.4  4736.4  373.61
    4819   370.7  4921.1   369.1  4931.1  366.86  4938.9  365.93  4943.9  366.19
  4951.2  361.42  4958.3  360.59  4961.1  360.09  4964.3  360.59  4971.4  363.27
  4981.4  363.85  4991.5  367.04  5011.6  368.97  5021.7  369.64    5072  369.77
  5132.4  371.84  5208.4  373.27    5223  374.35  5353.8  376.78  5407.5  377.05
#Mann= 7 ,-1 , 0
  3782.6      .1       0  4127.3     .05       0  4439.5      .1       0
  4736.4     .05       0    4819      .1       0  4958.3     .07       0
  4964.3      .1       0
Bank Sta=4921.1,5011.6
XS Rating Curve= 0 ,0
Exp/Cntr=0.3,0.1

Type RM Length L Ch R = 1 ,1855    ,799,799,799
BEGIN DESCRIPTION:
Mapping XS 7b881101
END DESCRIPTION:
XS GIS Cut Line= 3
      2193196.22      13212026.2      2191888.96     13211416.84
       2191165.5     13212062.23
#Sta/Elev= 30
  3654.6  410.02  3730.2  409.48  3827.3  406.24  3952.6  400.42  4077.3  398.05
  4181.3  396.11  4226.7  393.91  4232.6  394.52  4292.9  390.86  4301.2  389.58
  4359.1  387.17  4375.3   384.7  4443.6  381.37  4546.6  374.36    4690  368.08
  4917.8  366.82  4932.8  365.49  4940.7  363.23  4963.5  364.26  4983.4  359.74
  4986.1  359.24  4989.4  359.74  5009.3  361.69  5014.8  364.37  5032.1   367.2
    5066  368.59  5253.7   368.5  5657.5  370.88  5749.4  373.09  6066.4  377.29
#Mann= 5 ,-1 , 0
  3654.6      .1       0  4077.3     .05       0  4443.6      .1       0
  4983.4     .07       0  4989.4      .1       0
Bank Sta=4917.8,5032.1
XS Rating Curve= 0 ,0
Exp/Cntr=0.3,0.1

Type RM Length L Ch R = 1 ,1056    ,833,833,833
BEGIN DESCRIPTION:
Mapping XS 257909b9
END DESCRIPTION:
XS GIS Cut Line= 4
      2193357.72      13211885.6      2192586.88     13211083.51
      2191816.04     13211385.59      2191191.86     13212009.78
#Sta/Elev= 30
  3975.4  406.73  4080.7  408.53  4229.1  402.92  4236.3  401.82  4427.2  394.52
  4646.4  384.79  4653.3   383.7  4724.1  379.66  4731.3  380.33  4780.7  377.15
  4802.1  376.85  4950.5   365.4  4957.7  363.75  4964.6  363.49    4983  355.91
  4985.8  355.41    4989  355.91  4992.9  356.32    5000  359.58    5014  361.25
  5021.2  363.71  5028.2  364.81  5077.9  367.06  5492.1  365.97  5852.8  368.91
  5922.5  367.92  6120.5  368.71  6488.2  371.88  6608.4  374.41  6798.5   376.5
#Mann= 3 ,-1 , 0
  3975.4      .1       0    4983     .07       0    4989      .1       0
Bank Sta=4950.5,5028.2
XS Rating Curve= 0 ,0
Exp/Cntr=0.3,0.1

Type RM Length L Ch R = 1 ,223     ,0,0,0
BEGIN DESCRIPTION:
TEPECATE CREEK 1.0
END DESCRIPTION:
XS GIS Cut Line= 4
      2194076.43     13210927.26      2192743.13     13210692.89
      2192055.63     13211067.89       2191165.7      13212005.4
#Sta/Elev= 30
  3220.3  389.14    3404  381.94  3518.6  378.08  3658.2  375.28  3854.2  376.15
  3980.5  376.63  4288.3  372.13  4387.5  371.32  4475.4  370.62  4486.7  370.46
  4642.5  370.84  4773.8   368.8    4802  369.26  4830.8  366.86  4853.6  367.09
  4905.4  364.04  4987.1   362.8  5008.9  359.19  5011.6  355.69  5014.3  355.19
  5017.6  355.69  5039.3  355.92  5052.6  357.46  5058.6   362.3  5081.4     365
  5397.2  365.85  5666.2  368.31  5885.4  367.77  6331.2  372.14  6649.8  376.59
#Mann= 12 ,-1 , 0
  3220.3     .05       0    3404      .1       0  3518.6     .05       0
  3854.2      .1       0  4288.3     .08       0  4387.5      .1       0
  4475.4     .08       0  4486.7      .1       0  4642.5     .12       0
  5011.6     .07       0  5017.6     .12       0  5039.3      .1       0
Bank Sta=4987.1,5058.6
XS Rating Curve= 0 ,0
Exp/Cntr=0.3,0.1

Chan Stop Cuts=-1
Use User Specified Reach Order=0
Composite Channel Slope=5