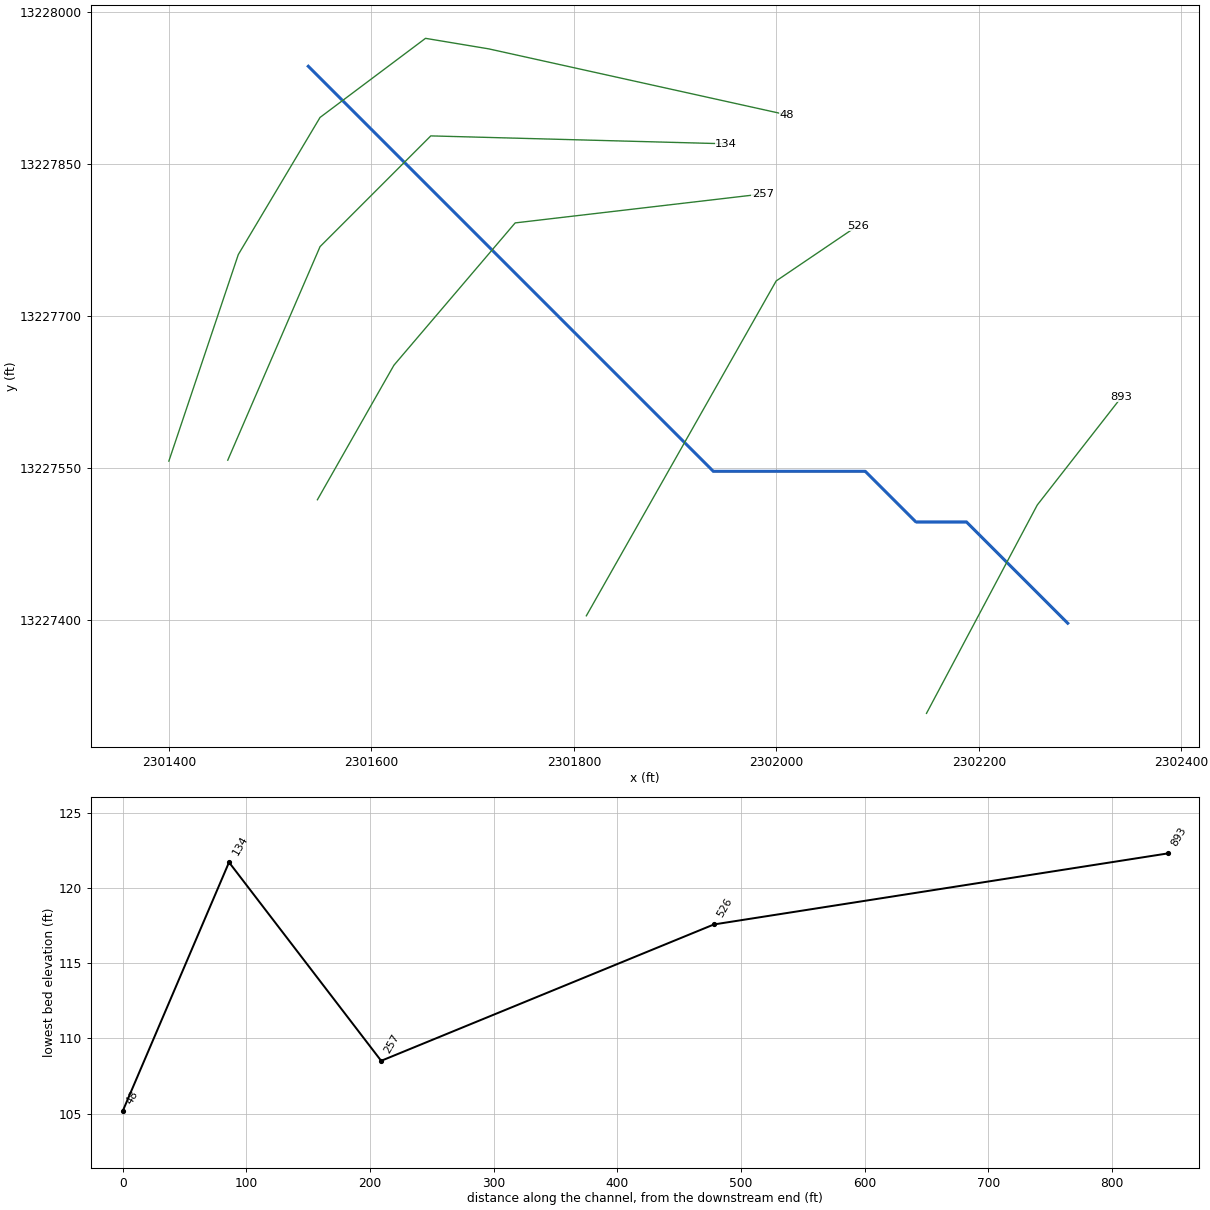
--- UNT 001 IN LACR.prj (project) ---

Proj Title=UNT 001 IN LACR Base Level Engineering
Current Plan=p01
Default Exp/Contr=0.3,0.1
English Units
Geom File=g01
Flow File=f01
Plan File=p01
BEGIN DESCRIPTION:
UNT 001 IN LACR
END DESCRIPTION:

--- UNT 001 IN LACR.p01 (plan) ---

Plan Title=Multiple Run
Short Identifier=Multiple
Geom File=g01
Flow File=f01
Subcritical Flow
K Sum by GR= 0
Std Step Tol= 0.01
Critical Tol= 0.01
Num of Std Step Trials= 20
Max Error Tol= 0.3
Flow Tol Ratio= 0.001
Split Flow NTrial= 30
Split Flow Tol= 0.02
Split Flow Ratio= 0.02
Log Output Level= 0
Friction Slope Method= 1
Unsteady Friction Slope Method= 2
Unsteady Bridges Friction Slope Method= 1
Parabolic Critical Depth
Global Vel Dist=  1 , 1 , 1
Global Log Level= 0
CheckData=True
Encroach Param= -1, 0, 0, 0
BEGIN DESCRIPTION:
Multiple Run
END DESCRIPTION:

--- UNT 001 IN LACR.f01 (steady flow) ---

Flow Title=Multiple
Number of Profiles=7
Profile Names=10-year,25-year,50-year,1pct_min,100-year,1pct_plu,500-year
River Rch & RM= UNT 001 IN LACR,Reach-1,893
     152     197     232     201     272     367     372
Boundary for River Rch & Prof#=UNT 001 IN LACR,Reach-1,1
Up Type=0
Dn Type=3
Dn Slope=0.005
Boundary for River Rch & Prof#=UNT 001 IN LACR,Reach-1,2
Up Type=0
Dn Type=3
Dn Slope=0.005
Boundary for River Rch & Prof#=UNT 001 IN LACR,Reach-1,3
Up Type=0
Dn Type=3
Dn Slope=0.005
Boundary for River Rch & Prof#=UNT 001 IN LACR,Reach-1,4
Up Type=0
Dn Type=3
Dn Slope=0.005
Boundary for River Rch & Prof#=UNT 001 IN LACR,Reach-1,5
Up Type=0
Dn Type=3
Dn Slope=0.005
Boundary for River Rch & Prof#=UNT 001 IN LACR,Reach-1,6
Up Type=0
Dn Type=3
Dn Slope=0.005
Boundary for River Rch & Prof#=UNT 001 IN LACR,Reach-1,7
Up Type=0
Dn Type=3
Dn Slope=0.005

--- UNT 001 IN LACR.g01 (geometry) ---

Geom Title=Existing Conditions

River Reach=UNT 001 IN LACR,Reach-1
Reach XY= 16
      2302287.72     13227396.85      2302237.72     13227446.85
      2302187.72     13227496.85      2302137.72     13227496.85
      2302087.72     13227546.85      2302037.72     13227546.85
      2301987.72     13227546.85      2301937.72     13227546.85
      2301887.72     13227596.86      2301837.72     13227646.85
      2301787.72     13227696.85      2301737.72     13227746.86
      2301687.72     13227796.85      2301637.72     13227846.85
      2301587.72     13227896.86      2301537.72     13227946.85

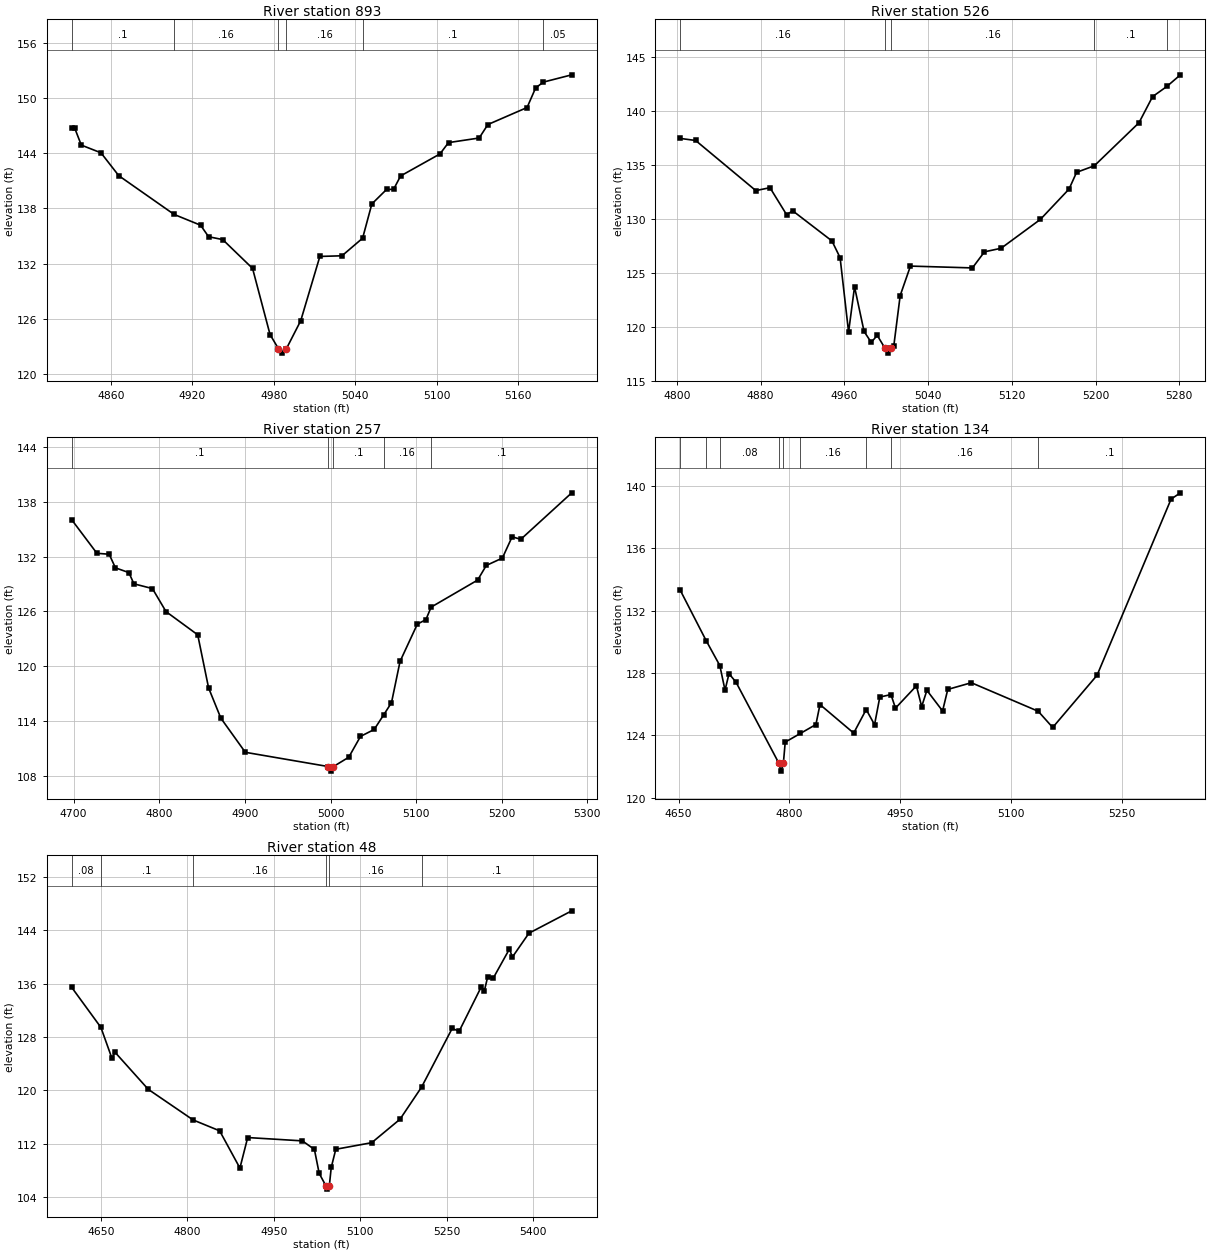
Type RM Length L Ch R = 1,893,367,367,367
BEGIN DESCRIPTION:
UNT 001 IN LACR 1.0
END DESCRIPTION:
XS GIS Cut Line= 3
      2302148.24     13227307.78      2302257.63     13227513.54
      2302340.98     13227620.33
#Sta/Elev= 30
  4831.0  146.70  4833.3  146.70  4838.1  144.88  4852.6  144.04  4865.7  141.56
  4906.5  137.35  4926.0  136.18  4931.9  134.93  4942.3  134.62  4964.3  131.49
  4977.2  124.30  4983.3  122.79  4986.0  122.29  4989.3  122.79  4999.8  125.81
  5013.9  132.79  5030.2  132.86  5045.4  134.77  5052.2  138.49  5063.1  140.07
  5068.2  140.07  5073.4  141.53  5102.4  143.92  5108.7  145.15  5131.3  145.65
  5137.7  147.11  5166.6  148.96  5172.9  151.09  5178.6  151.72  5199.5  152.51
#Mann=6,-1,0
  4831.0     0.1       0  4906.5    0.16       0  4983.3    0.07       0
  4989.3    0.16       0  5045.4     0.1       0  5178.6    0.05       0
Bank Sta=4983.3,4989.3
Exp/Cntr=0.3,0.1

Type RM Length L Ch R = 1,526,269,269,269
BEGIN DESCRIPTION:
Mapping XS 47860ade
END DESCRIPTION:
XS GIS Cut Line= 3
      2301812.31     13227404.14      2301999.82     13227734.89
      2302080.54     13227789.57
#Sta/Elev= 30
  4803.3  137.45  4817.9  137.26  4875.4  132.62  4888.9  132.89  4904.8  130.39
  4910.6  130.75  4948.1  127.96  4955.9  126.41  4964.0  119.52  4969.7  123.71
  4978.8  119.58  4985.6  118.57  4991.4  119.21  4998.5  118.07  5001.2  117.57
  5004.5  118.07  5007.2  118.24  5013.3  122.90  5023.1  125.63  5082.3  125.46
  5093.8  126.95  5109.7  127.28  5147.2  129.95  5174.6  132.76  5181.8  134.31
  5198.8  134.92  5241.4  138.90  5254.4  141.32  5268.0  142.26  5281.0  143.34
#Mann=5,-1,0
  4803.3    0.16       0  4998.5    0.07       0  5004.5    0.16       0
  5198.8     0.1       0  5268.0    0.05       0
Bank Sta=4998.5,5004.5
Exp/Cntr=0.3,0.1

Type RM Length L Ch R = 1,257,123,123,123
BEGIN DESCRIPTION:
Mapping XS 50563408
END DESCRIPTION:
XS GIS Cut Line= 4
      2301546.70     13227518.76      2301622.22     13227651.56
      2301742.01     13227792.18      2301986.84     13227820.83
#Sta/Elev= 30
  4697.7  136.03  4727.2  132.35  4741.5  132.25  4748.8  130.76  4764.5  130.24
  4770.4  129.01  4792.0  128.49  4807.9  125.97  4844.9  123.43  4857.6  117.62
  4871.9  114.31  4900.5  110.57  4997.4  109.01  5000.2  108.51  5003.4  109.01
  5021.3  110.03  5035.0  112.31  5051.0  113.07  5061.9  114.64  5071.2  116.00
  5081.2  120.52  5101.4  124.60  5111.4  125.09  5117.5  126.46  5171.8  129.42
  5181.9  131.02  5200.7  131.83  5212.1  134.16  5222.2  133.88  5281.7  138.97
#Mann=5,-1,0
  4697.7     0.1       0  4997.4    0.07       0  5003.4     0.1       0
  5061.9    0.16       0  5117.5     0.1       0
Bank Sta=4997.4,5003.4
Exp/Cntr=0.3,0.1

Type RM Length L Ch R = 1,134,86,86,86
BEGIN DESCRIPTION:
Mapping XS 342c04a9
END DESCRIPTION:
XS GIS Cut Line= 4
      2301458.17     13227557.85      2301549.30     13227768.74
      2301658.67     13227878.12      2301950.35     13227870.31
#Sta/Elev= 30
  4652.5  133.29  4687.5  130.06  4705.9  128.47  4712.9  126.89  4718.3  127.95
  4727.7  127.41  4785.8  122.20  4788.6  121.70  4791.8  122.20  4794.3  123.56
  4814.9  124.12  4835.8  124.69  4841.3  125.97  4886.9  124.14  4903.8  125.65
  4915.1  124.68  4922.2  126.45  4937.3  126.61  4943.4  125.74  4971.7  127.17
  4978.8  125.84  4985.9  126.88  5007.1  125.56  5014.1  126.94  5046.0  127.37
  5136.4  125.54  5156.0  124.50  5216.0  127.85  5316.1  139.15  5328.7  139.55
#Mann=9,-1,0
  4652.5    0.08       0  4687.5     0.1       0  4705.9    0.08       0
  4785.8    0.07       0  4791.8    0.08       0  4814.9    0.16       0
  4903.8     0.1       0  4937.3    0.16       0  5136.4     0.1       0
Bank Sta=4785.8,4791.8
Exp/Cntr=0.3,0.1

Type RM Length L Ch R = 1,48,0,0,0
BEGIN DESCRIPTION:
UNT 001 IN LACR 2.0
END DESCRIPTION:
XS GIS Cut Line= 6
      2301399.98     13227556.91      2301468.57     13227760.93
      2301549.30     13227896.35      2301653.47     13227974.47
      2301715.97     13227964.06      2302010.28     13227898.94
#Sta/Elev= 30
  4599.3  135.44  4650.0  129.43  4669.2  124.79  4674.5  125.70  4732.3  120.13
  4810.1  115.54  4856.1  113.91  4891.3  108.32  4904.8  112.90  4999.8  112.40
  5020.6  111.11  5028.9  107.52  5040.5  105.66  5043.3  105.16  5046.5  105.66
  5049.8  108.41  5057.7  111.14  5120.1  112.13  5169.2  115.65  5206.6  120.47
  5259.7  129.27  5271.8  128.85  5310.3  135.53  5315.5  134.90  5321.2  136.96
  5331.4  136.88  5359.1  141.19  5364.2  139.98  5392.9  143.56  5467.2  146.92
#Mann=6,-1,0
  4599.3    0.08       0  4650.0     0.1       0  4810.1    0.16       0
  5040.5    0.07       0  5046.5    0.16       0  5206.6     0.1       0
Bank Sta=5040.5,5046.5
Exp/Cntr=0.3,0.1

Chan Stop Cuts=-1