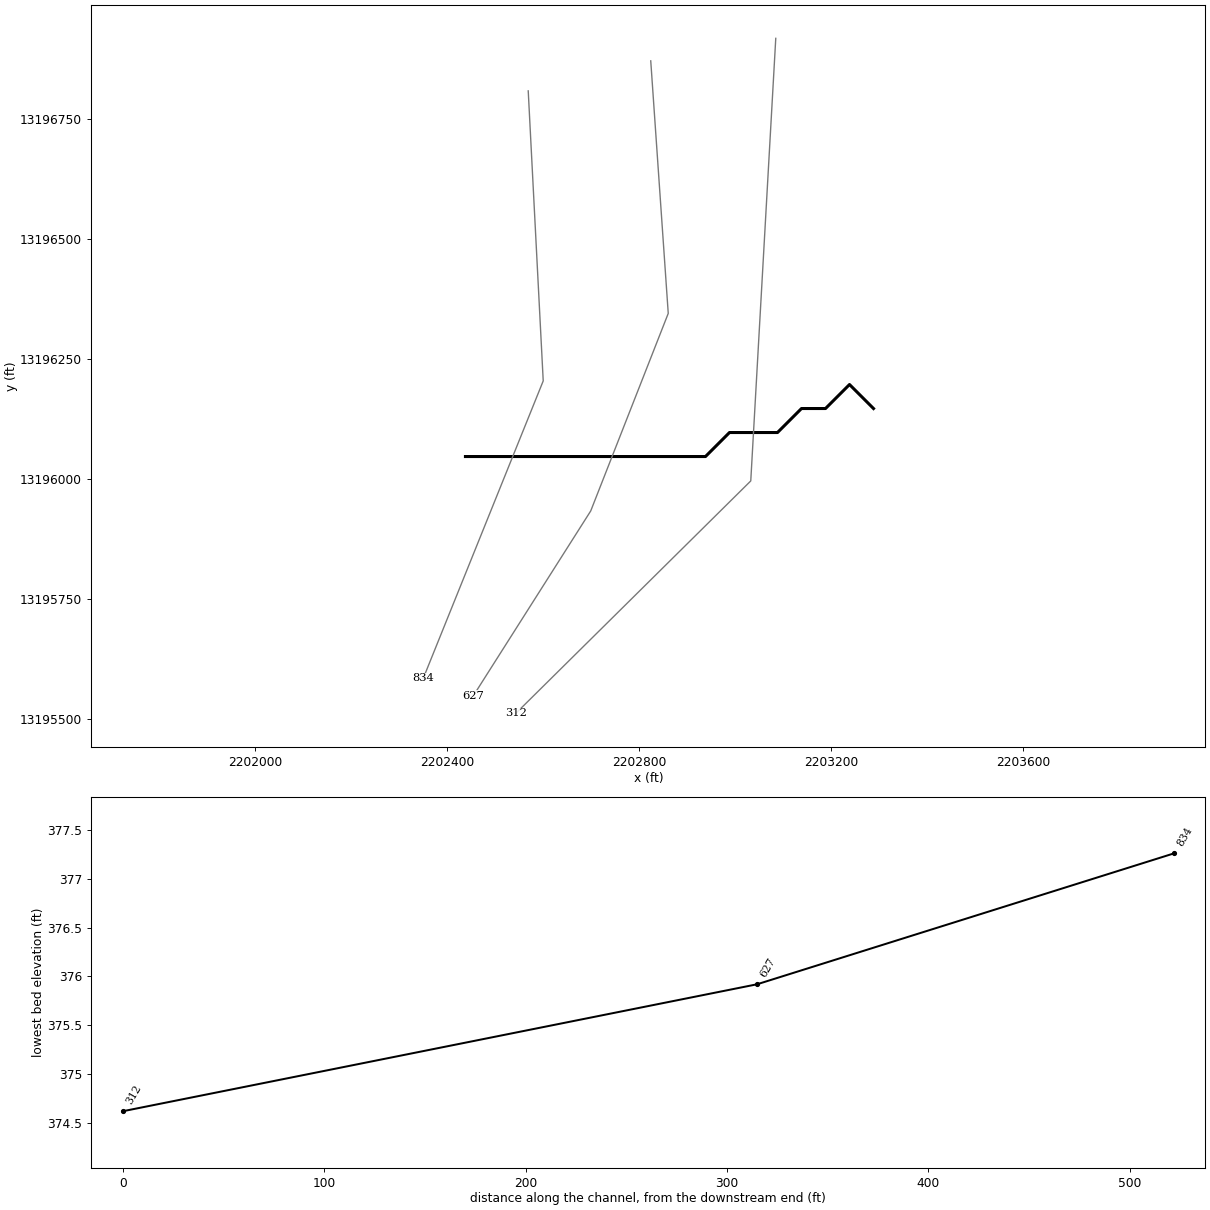
--- UNT 002 IN LACR.prj (project) ---

Proj Title=UNT 002 IN LACR Base Level Engineering
Current Plan=p01
Default Exp/Contr=0.3,0.1
English Units
Geom File=g01
Flow File=f01
Plan File=p01
BEGIN DESCRIPTION:
UNT 002 IN LACR
END DESCRIPTION:

--- UNT 002 IN LACR.p01 (plan) ---

Plan Title=Multiple Run
Short Identifier=Multiple
Geom File=g01
Flow File=f01
Subcritical Flow
K Sum by GR= 0
Std Step Tol= 0.01
Critical Tol= 0.01
Num of Std Step Trials= 20
Max Error Tol= 0.3
Flow Tol Ratio= 0.001
Split Flow NTrial= 30
Split Flow Tol= 0.02
Split Flow Ratio= 0.02
Log Output Level= 0
Friction Slope Method= 1
Unsteady Friction Slope Method= 2
Unsteady Bridges Friction Slope Method= 1
Parabolic Critical Depth
Global Vel Dist=  1 , 1 , 1
Global Log Level= 0
CheckData=True
Encroach Param= -1, 0, 0, 0
BEGIN DESCRIPTION:
Multiple Run
END DESCRIPTION:

--- UNT 002 IN LACR.f01 (steady flow) ---

Flow Title=Multiple
Number of Profiles=7
Profile Names=10-year,25-year,50-year,1pct_min,100-year,1pct_plu,500-year
River Rch & RM= UNT 002 IN LACR,Reach-1,834
      66      85     100      87     117     159     164
Boundary for River Rch & Prof#=UNT 002 IN LACR,Reach-1,1
Up Type=0
Dn Type=3
Dn Slope=0.005
Boundary for River Rch & Prof#=UNT 002 IN LACR,Reach-1,2
Up Type=0
Dn Type=3
Dn Slope=0.005
Boundary for River Rch & Prof#=UNT 002 IN LACR,Reach-1,3
Up Type=0
Dn Type=3
Dn Slope=0.005
Boundary for River Rch & Prof#=UNT 002 IN LACR,Reach-1,4
Up Type=0
Dn Type=3
Dn Slope=0.005
Boundary for River Rch & Prof#=UNT 002 IN LACR,Reach-1,5
Up Type=0
Dn Type=3
Dn Slope=0.005
Boundary for River Rch & Prof#=UNT 002 IN LACR,Reach-1,6
Up Type=0
Dn Type=3
Dn Slope=0.005
Boundary for River Rch & Prof#=UNT 002 IN LACR,Reach-1,7
Up Type=0
Dn Type=3
Dn Slope=0.005

--- UNT 002 IN LACR.g01 (geometry) ---

Geom Title=Existing Conditions

River Reach=UNT 002 IN LACR,Reach-1
Reach XY= 8
      2202437.72     13196046.85      2202937.72     13196046.85
      2202987.72     13196096.86      2203087.72     13196096.86
      2203137.72     13196146.85      2203187.72     13196146.85
      2203237.72     13196196.85      2203287.72     13196146.85

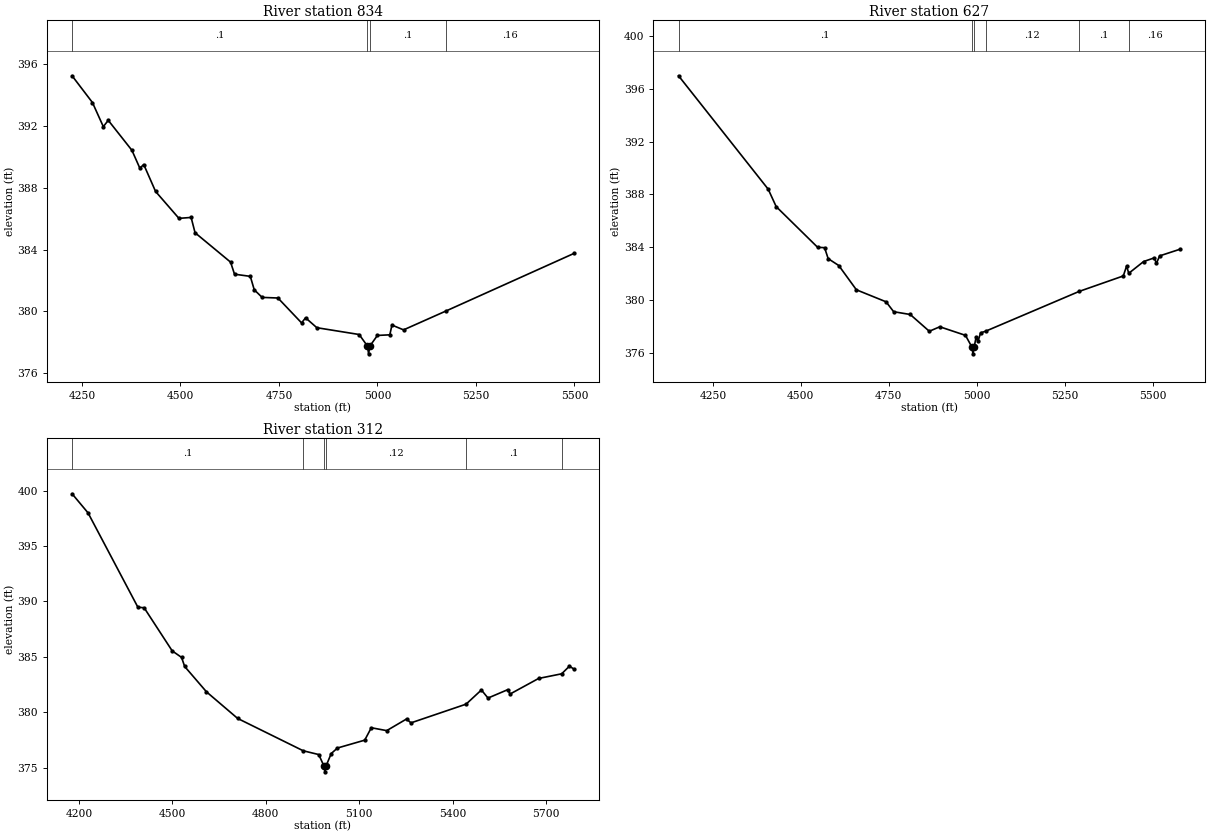
Type RM Length L Ch R = 1,834,207,207,207
BEGIN DESCRIPTION:
UNT 002 IN LACR 1.0
END DESCRIPTION:
XS GIS Cut Line= 3
      2202568.50     13196808.52      2202599.74     13196204.37
      2202349.73     13195584.55
#Sta/Elev= 30
  4225.2  395.24  4276.9  393.51  4304.5  391.95  4317.0  392.36  4377.1  390.42
  4397.1  389.27  4407.1  389.50  4437.1  387.76  4496.4  386.02  4527.3  386.08
  4537.3  385.09  4627.4  383.19  4637.4  382.41  4677.5  382.27  4687.5  381.40
  4707.5  380.91  4747.6  380.87  4807.6  379.26  4817.7  379.59  4846.3  378.95
  4953.7  378.51  4974.8  377.76  4977.6  377.26  4980.8  377.76  5000.0  378.45
  5031.5  378.49  5036.9  379.12  5066.4  378.81  5174.0  380.03  5498.5  383.75
#Mann=4,-1,0
  4225.2     0.1       0  4974.8    0.07       0  4980.8     0.1       0
  5174.0    0.16       0
Bank Sta=4974.8,4980.8
Exp/Cntr=0.3,0.1

Type RM Length L Ch R = 1,627,315,315,315
BEGIN DESCRIPTION:
Mapping XS a5e51fff
END DESCRIPTION:
XS GIS Cut Line= 4
      2202823.70     13196871.06      2202860.16     13196345.00
      2202698.70     13195933.54      2202453.92     13195548.13
#Sta/Elev= 30
  4152.4  396.98  4407.2  388.39  4429.9  387.07  4547.6  383.99  4567.4  383.96
  4577.6  383.13  4607.7  382.61  4657.8  380.77  4742.2  379.86  4763.7  379.11
  4810.8  378.90  4865.0  377.63  4894.8  377.97  4967.8  377.32  4986.3  376.42
  4989.0  375.92  4992.3  376.42  4997.9  377.17  5003.3  376.86  5010.7  377.51
  5024.7  377.63  5291.0  380.65  5416.3  381.82  5425.6  382.57  5431.8  382.02
  5473.9  382.91  5504.4  383.19  5510.3  382.77  5519.6  383.34  5578.3  383.85
#Mann=6,-1,0
  4152.4     0.1       0  4986.3    0.07       0  4992.3     0.1       0
  5024.7    0.12       0  5291.0     0.1       0  5431.8    0.16       0
Bank Sta=4986.3,4992.3
Exp/Cntr=0.3,0.1

Type RM Length L Ch R = 1,312,0,0,0
BEGIN DESCRIPTION:
UNT 002 IN LACR 2.0
END DESCRIPTION:
XS GIS Cut Line= 3
      2203084.12     13196917.95      2203032.04     13195996.04
      2202542.65     13195511.86
#Sta/Elev= 30
  4177.6  399.72  4228.8  398.00  4389.0  389.48  4409.1  389.43  4499.2  385.54
  4529.3  384.95  4539.3  384.13  4609.4  381.84  4709.5  379.44  4920.2  376.52
  4970.0  376.18  4987.0  375.12  4989.7  374.62  4993.0  375.12  5010.0  376.27
  5030.0  376.77  5117.6  377.48  5138.8  378.60  5188.3  378.34  5251.9  379.39
  5266.1  379.04  5443.2  380.73  5492.4  382.01  5513.6  381.28  5577.2  382.04
  5584.3  381.64  5676.2  383.05  5750.3  383.47  5775.2  384.16  5789.4  383.90
#Mann=6,-1,0
  4177.6     0.1       0  4920.2    0.12       0  4987.0    0.07       0
  4993.0    0.12       0  5443.2     0.1       0  5750.3    0.16       0
Bank Sta=4987,4993
Exp/Cntr=0.3,0.1

Chan Stop Cuts=-1