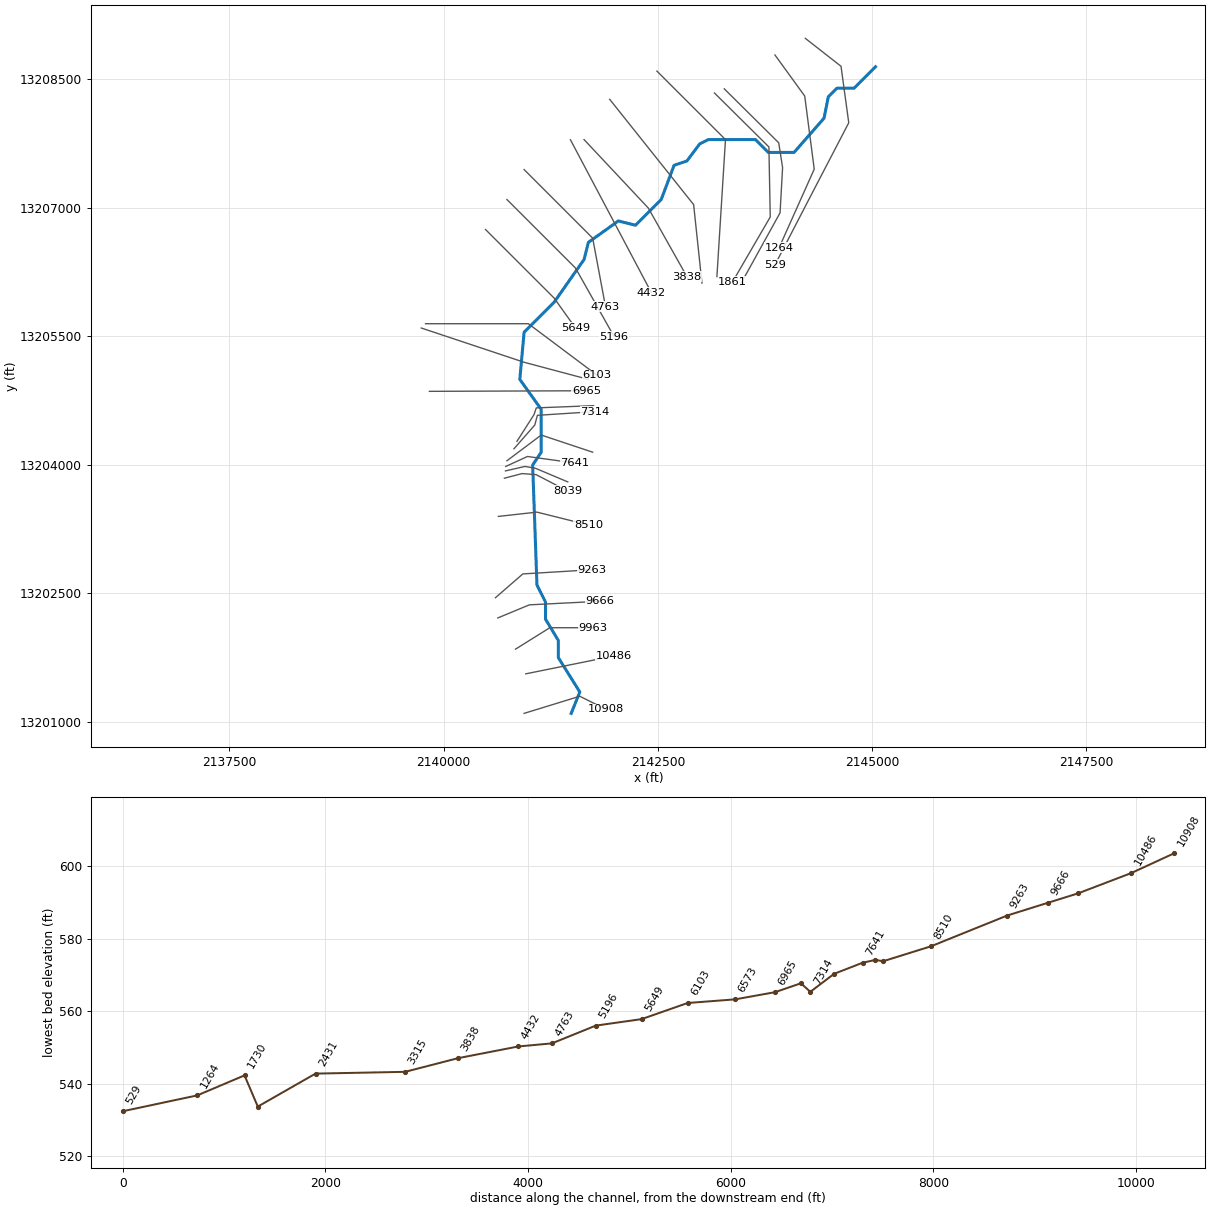
--- UNT 003 IN LACR.prj (project) ---

Proj Title=UNT 003 IN LACR Base Level Engineering
Current Plan=p01
Default Exp/Contr=0.3,0.1
English Units
Geom File=g01
Flow File=f01
Plan File=p01
Y Axis Title=Elevation
X Axis Title(PF)=Main Channel Distance
X Axis Title(XS)=Station
BEGIN DESCRIPTION:
UNT 003 IN LACR
END DESCRIPTION:
DSS Export Rating Curves= 0
DSS Export Rating Curve Sorted= 0
DSS Export Volume Flow Curves= 0
DXF OffsetX= 0
DXF OffsetY= 0
DXF ScaleX= 1
DXF ScaleY= 10

--- UNT 003 IN LACR.p01 (plan) ---

Plan Title=Multiple Run
Short Identifier=Multiple
Geom File=g01
Flow File=f01
Subcritical Flow
K Sum by GR= 0
Std Step Tol= 0.01
Critical Tol= 0.01
Num of Std Step Trials= 20
Max Error Tol= 0.3
Flow Tol Ratio= 0.001
Split Flow NTrial= 30
Split Flow Tol= 0.02
Split Flow Ratio= 0.02
Log Output Level= 0
Friction Slope Method= 1
Unsteady Friction Slope Method= 2
Unsteady Bridges Friction Slope Method= 1
Parabolic Critical Depth
Global Vel Dist=  1 , 1 , 1
Global Log Level= 0
CheckData=True
Encroach Param= -1, 0, 0, 0
BEGIN DESCRIPTION:
Multiple Run
END DESCRIPTION:

--- UNT 003 IN LACR.f01 (steady flow) ---

Flow Title=Multiple
Program Version=4.10
Number of Profiles= 7
Profile Names=10-year,25-year,50-year,1pct_min,100-year,1pct_plu,500-year
River Rch & RM=UNT 003 IN LACR,Reach-1         ,10908
     135     185     227     204     276     373     417
River Rch & RM=UNT 003 IN LACR,Reach-1         ,6965
     270     384     481     442     598     809     942
River Rch & RM=UNT 003 IN LACR,Reach-1         ,6573
     270     384     481     442     598     809     942
Boundary for River Rch & Prof#=UNT 003 IN LACR,Reach-1         , 1
Up Type= 0
Dn Type= 3
Dn Slope=0.008
Boundary for River Rch & Prof#=UNT 003 IN LACR,Reach-1         , 2
Up Type= 0
Dn Type= 3
Dn Slope=0.008
Boundary for River Rch & Prof#=UNT 003 IN LACR,Reach-1         , 3
Up Type= 0
Dn Type= 3
Dn Slope=0.008
Boundary for River Rch & Prof#=UNT 003 IN LACR,Reach-1         , 4
Up Type= 0
Dn Type= 3
Dn Slope=0.008
Boundary for River Rch & Prof#=UNT 003 IN LACR,Reach-1         , 5
Up Type= 0
Dn Type= 3
Dn Slope=0.008
Boundary for River Rch & Prof#=UNT 003 IN LACR,Reach-1         , 6
Up Type= 0
Dn Type= 3
Dn Slope=0.008
Boundary for River Rch & Prof#=UNT 003 IN LACR,Reach-1         , 7
Up Type= 0
Dn Type= 3
Dn Slope=0.008
DSS Import GetInterval= 0
DSS Import GetPeak= 0
DSS Import FillOption= 0

--- UNT 003 IN LACR.g01 (geometry) ---

Geom Title=Existing Conditions
Program Version=4.10

River Reach=UNT 003 IN LACR ,Reach-1
Reach XY= 30
      2141487.72     13201096.85      2141587.72     13201346.86
      2141337.72     13201746.85      2141337.72     13201946.85
      2141187.72     13202196.85      2141187.72     13202396.85
      2141087.72     13202596.85      2141037.72     13203996.85
      2141137.72     13204146.86      2141137.72     13204646.85
      2140887.72     13204996.85      2140937.72     13205546.85
      2141287.72     13205896.85      2141637.72     13206396.85
      2141687.72     13206596.86      2142037.72     13206846.85
      2142237.72     13206796.85      2142537.72     13207096.86
      2142687.72     13207496.85      2142837.72     13207546.85
      2142987.72     13207746.86      2143087.72     13207796.85
      2143637.72     13207796.85      2143787.72     13207646.85
      2144087.72     13207646.85      2144437.72     13208046.86
      2144487.72     13208296.85      2144587.72     13208396.86
      2144787.72     13208396.86      2145037.72     13208646.85

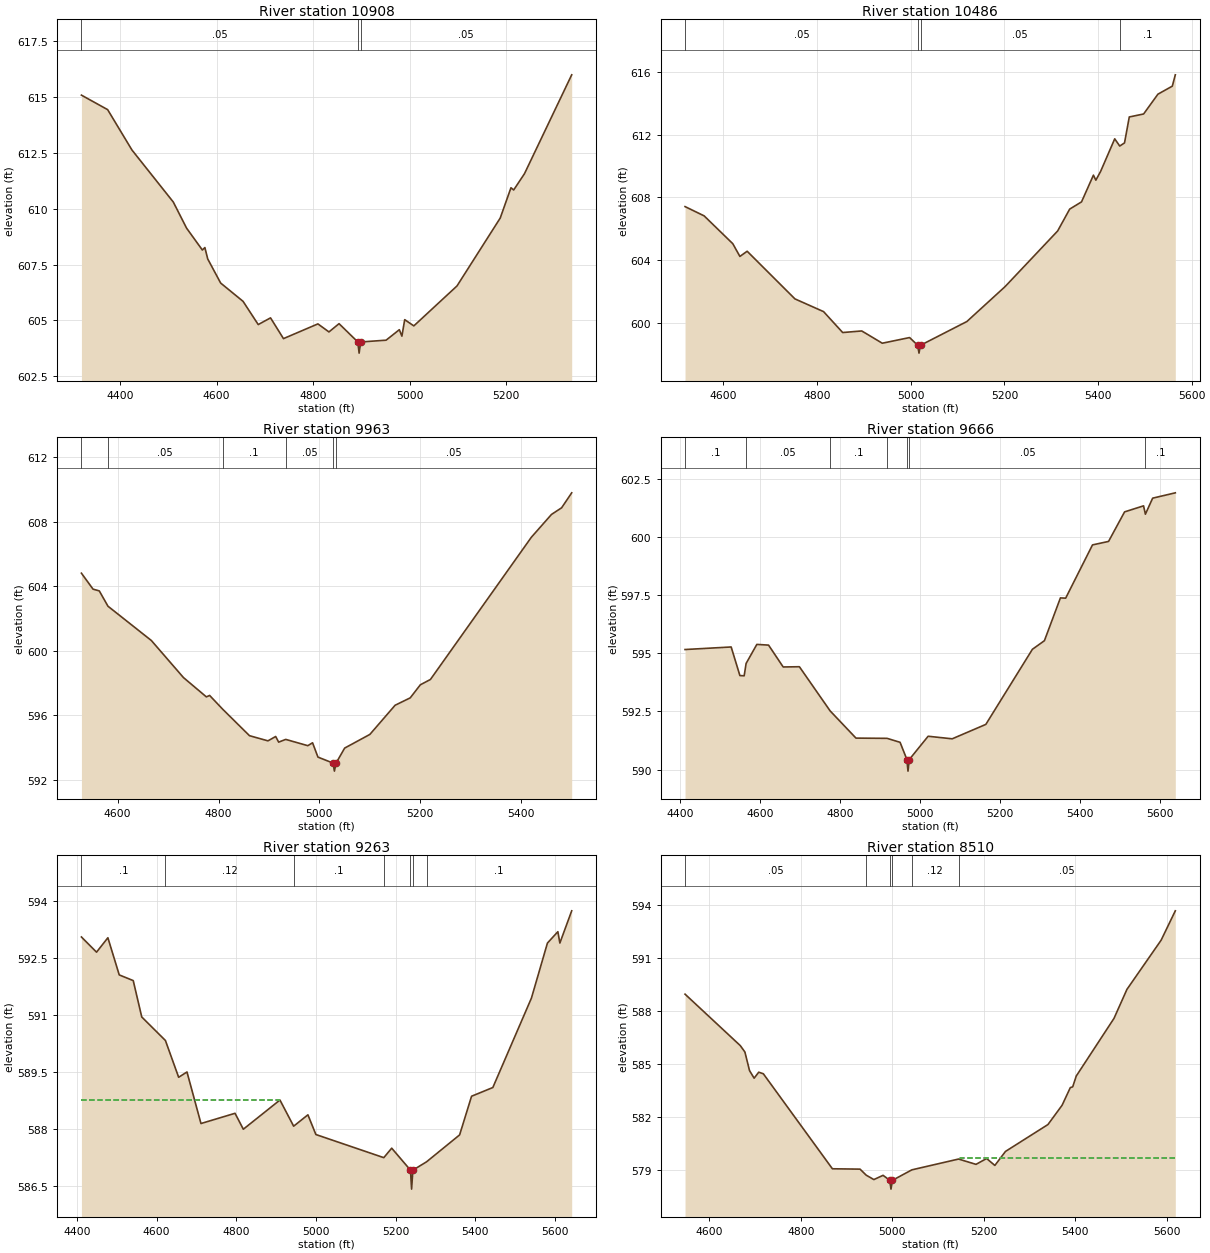
Type RM Length L Ch R = 1 ,10908   ,422,422,422
BEGIN DESCRIPTION:
UNT 003 IN LACR 20.0
END DESCRIPTION:
XS GIS Cut Line= 3
       2140937.7     13201096.85      2141587.72     13201296.85
      2141887.71     13201146.86
#Sta/Elev= 30
  4319.9  615.09  4374.2  614.44  4424.6  612.63  4510.2   610.3  4537.7  609.13
  4570.4  608.15  4575.6  608.26  4581.5  607.75  4608.3  606.67  4654.7  605.85
  4686.1  604.81  4711.6  605.11  4738.4  604.18  4809.7  604.84  4832.6  604.48
  4853.5  604.85  4892.4  604.03  4895.1  603.53  4898.4  604.03    4951  604.11
  4978.4  604.58  4983.7  604.29  4989.5  605.03  5008.4  604.75  5097.8  606.54
  5187.3  609.58  5209.6  610.94  5215.2  610.84  5237.6  611.57  5335.4     616
#Mann= 3 ,-1 , 0
  4319.9     .05       0  4892.4     .04       0  4898.4     .05       0
Bank Sta=4892.4,4898.4
XS Rating Curve= 0 ,0
Exp/Cntr=0.3,0.1

Type RM Length L Ch R = 1 ,10486   ,523,523,523
BEGIN DESCRIPTION:
UNT 003 IN LACR 19.0
END DESCRIPTION:
XS GIS Cut Line= 2
      2140957.71      13201558.6      2141984.04     13201766.64
#Sta/Elev= 30
  4517.9  607.42  4558.7  606.83  4619.9  605.06  4635.1  604.25  4650.6  604.58
  4752.6  601.55  4813.8  600.74  4854.6  599.41  4895.4  599.51  4939.2  598.73
  4997.5  599.09  5014.9   598.6  5017.6   598.1  5020.9   598.6  5119.9  600.11
  5201.5  602.33  5313.8  605.87  5339.5  607.26  5364.8  607.72  5390.2  609.42
  5395.4   609.1  5405.6  609.66  5435.7  611.73  5446.4  611.27  5456.6  611.47
  5466.8  613.12  5497.4  613.31    5528  614.57  5558.7  615.08  5565.1   615.8
#Mann= 4 ,-1 , 0
  4517.9     .05       0  5014.9     .03       0  5020.9     .05       0
  5446.4      .1       0
Bank Sta=5014.9,5020.9
XS Rating Curve= 0 ,0
Exp/Cntr=0.3,0.1

Type RM Length L Ch R = 1 ,9963    ,297,297,297
BEGIN DESCRIPTION:
UNT 003 IN LACR 18.0
END DESCRIPTION:
XS GIS Cut Line= 3
      2140837.72     13201846.85      2141237.72     13202096.85
      2141737.72     13202096.85
#Sta/Elev= 30
  4528.3  604.81  4551.3  603.82  4563.7  603.71  4580.9  602.76  4666.9  600.63
  4730.5  598.33  4775.9  597.13  4782.4  597.22  4808.1  596.37  4861.4  594.72
    4898   594.4  4913.3  594.67  4919.2  594.32  4933.2  594.49    4977   594.1
  4986.4  594.28  4997.1  593.39    5027  593.02  5029.7  592.52    5033  593.02
    5050  593.95    5100   594.8    5150  596.61    5180  597.07    5200  597.88
    5220  598.21    5420  607.04    5460  608.46    5480  608.87    5500   609.8
#Mann= 6 ,-1 , 0
  4528.3      .1       0  4580.9     .05       0  4808.1      .1       0
  4933.2     .05       0    5027     .03       0    5033     .05       0
Bank Sta=5027,5033
XS Rating Curve= 0 ,0
Exp/Cntr=0.3,0.1

Type RM Length L Ch R = 1 ,9666    ,403,403,403
BEGIN DESCRIPTION:
UNT 003 IN LACR 17.0
END DESCRIPTION:
XS GIS Cut Line= 3
      2140631.31     13202211.38      2140999.34     13202364.15
      2141824.21     13202405.74
#Sta/Elev= 30
  4412.9  595.16  4528.1  595.27  4549.9  594.04  4560.6  594.03  4565.4  594.56
  4592.2  595.38  4621.5  595.35    4658  594.41  4698.5  594.42  4775.3  592.52
  4839.8  591.35  4917.4  591.34  4949.9  591.17    4967  590.43  4969.7  589.93
    4973  590.43    5020  591.43  5080.1  591.32  5164.1  591.94  5280.4  595.17
  5310.4  595.54  5350.4  597.38  5363.5  597.37  5430.5  599.66  5470.6  599.81
  5510.6  601.08    5558  601.34  5562.6  600.98  5580.7  601.67  5637.3   601.9
#Mann= 7 ,-1 , 0
  4412.9      .1       0  4565.4     .05       0  4775.3      .1       0
  4917.4     .05       0    4967     .05       0    4973     .05       0
  5562.6      .1       0
Bank Sta=4967,4973
XS Rating Curve= 0 ,0
Exp/Cntr=0.3,0.1

Type RM Length L Ch R = 1 ,9263    ,753,753,753
BEGIN DESCRIPTION:
UNT 003 IN LACR 16.0
END DESCRIPTION:
XS GIS Cut Line= 3
       2140603.5     13202447.48      2140922.95     13202725.26
      2141728.55     13202773.87
#Sta/Elev= 30
  4411.6  593.06  4449.5  592.66    4478  593.04  4506.5  592.06  4541.6  591.91
    4563  590.95  4622.4  590.33  4655.6  589.36  4676.5   589.5  4711.6  588.14
  4797.1  588.41  4817.9  587.99  4909.8  588.76  4944.2  588.07    4980  588.37
    5000  587.85  5170.4  587.24  5190.3  587.49  5237.4  586.91  5240.2  586.41
  5243.4  586.91  5277.7  587.13  5360.7  587.84  5390.7  588.86  5444.1  589.09
    5541  591.45  5581.1   592.9  5607.3   593.2  5612.3   592.9    5642  593.75
#Mann= 7 ,-1 , 0
  4411.6      .1       0  4622.4     .12       0  4944.2      .1       0
  5170.4      .1       0  5237.4     .07       0  5243.4      .1       0
  5277.7      .1       0
#XS Ineff= 2 , 0
         4909.89  588.76
Permanent Ineff=
       F       F
Bank Sta=5237.4,5243.4
XS Rating Curve= 0 ,0
Exp/Cntr=0.3,0.1

Type RM Length L Ch R = 1 ,8510    ,471,471,471
BEGIN DESCRIPTION:
UNT 003 IN LACR 15.0
END DESCRIPTION:
XS GIS Cut Line= 3
      2140637.69     13203396.85      2141087.72     13203446.85
      2141687.75     13203296.85
#Sta/Elev= 30
  4547.2  588.94    4668  586.03    4678  585.67  4688.1  584.62  4698.2  584.19
  4708.2  584.53  4718.3  584.44  4869.2  579.07  4929.6  579.05    4943  578.71
  4959.8  578.46  4979.9   578.7  4994.5  578.42  4997.2  577.92  5000.5  578.42
  5042.9  579.01  5144.9  579.62    5183  579.32  5206.2  579.65  5224.2  579.26
  5247.4  580.05  5340.2  581.57  5371.1  582.66  5389.1  583.66  5394.3   583.7
    5402  584.31  5484.5  587.57  5512.8  589.21  5587.5  591.99  5618.5  593.65
#Mann= 6 ,-1 , 0
  4547.2     .05       0    4943      .1       0  4994.5     .07       0
  5000.5      .1       0  5042.9     .12       0  5144.9     .05       0
#XS Ineff= 2 , 0
                         5146.93          579.67
Permanent Ineff=
       F       F
Bank Sta=4994.5,5000.5
XS Rating Curve= 0 ,0
Exp/Cntr=0.3,0.1

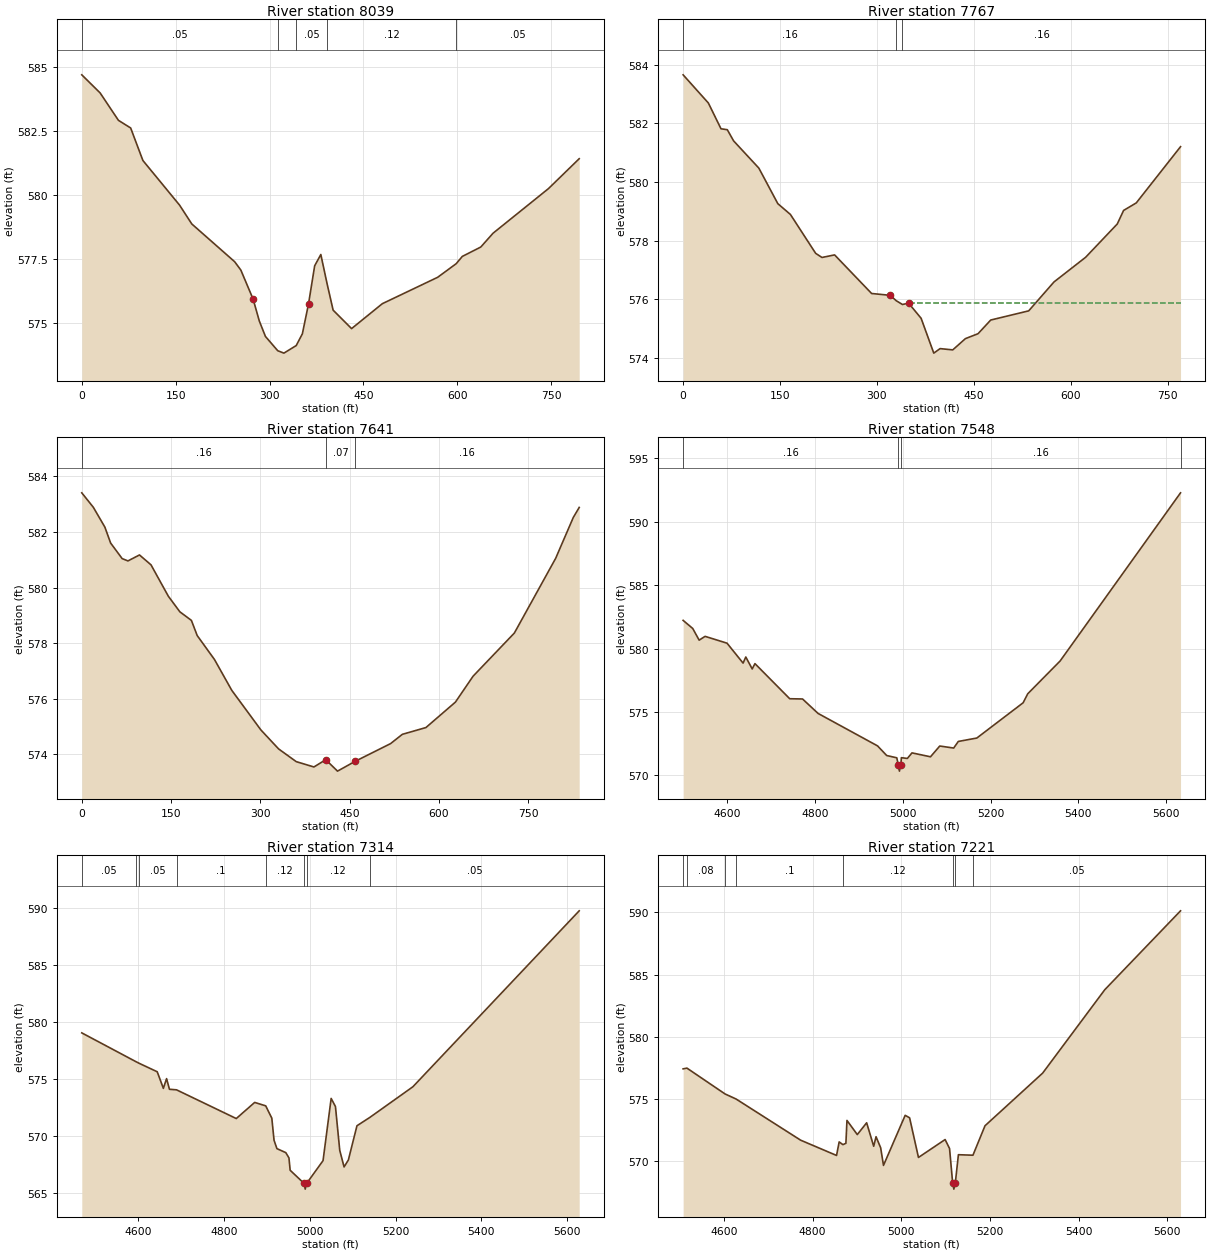
Type RM Length L Ch R = 1 ,8039    ,77,77,77
BEGIN DESCRIPTION:
UNT 003 IN LACR 14.0
END DESCRIPTION:
XS GIS Cut Line= 4
     2140708.049    13203843.082     2140914.646    13203896.902
     2141077.841    13203884.749      2141444.16    13203693.777
#Sta/Elev= 30
       0584.682729.28749 583.97658.57497582.905278.09997582.606997.62496 581.338
156.1999579.5958175.7249578.8606244.2648577.3847254.0947577.0597273.7546575.9221
283.5846 575.073293.4145574.4676313.0744573.9097322.9044573.8163342.5643 574.111
352.3942574.5699362.2242575.7353372.0541577.2254381.8841 577.667391.7123576.5463
401.5406575.4941431.0253574.7735480.1666575.7468568.6208576.7779598.1057577.3078
607.9339577.5926637.4186577.9586657.0751578.4988745.5294 580.239794.6707581.4071
#Mann= 5 ,-1 , 0
       0     .05       0313.0744     .03       0342.5643     .05       0
391.7123     .12       0598.1057     .05       0
#XS Ineff= 2 , 0
       0                  381.82       0  577.66
Permanent Ineff=
       F       T
Bank Sta=273.7546,362.2242
XS Rating Curve= 0 ,0
Exp/Cntr=0.3,0.1

Type RM Length L Ch R = 1 ,7767    ,126,126,126
XS GIS Cut Line= 4
     2140720.202    13203928.152     2140947.633    13203980.235
      2141069.16    13203959.402     2141447.633     13203799.68
#Sta/Elev= 30
       0583.648539.09276582.688358.63914581.810868.41234581.779778.18552581.3988
117.2783 580.471146.5979579.2621166.1442578.8935 205.237 577.569215.0102577.4292
234.5566577.5167291.8594576.2024320.5109576.1403330.0614575.9553339.6118575.8281
349.1623575.8726368.5098575.3581388.1037574.1718397.9007574.3255417.4947574.2824
437.0886574.6654456.6826574.8337476.2765575.2987535.0583 575.611574.2463576.5955
623.2311577.4358 672.216578.5696 682.013 579.031701.6069579.2866770.1858581.2016
#Mann= 3 ,-1 , 0
       0     .16       0330.0614     .07       0339.6118     .16       0
#XS Ineff= 2 , 0
       0                  349.55       0  575.88
Permanent Ineff=
       F       T
Bank Sta=320.5109,349.1623
XS Rating Curve= 0 ,0
Exp/Cntr=0.3,0.1

Type RM Length L Ch R = 1 ,7641    ,282,282,282
XS GIS Cut Line= 3
     2140723.674    13203980.235     2140977.146    13204096.555
     2141530.966    13204020.166
#Sta/Elev= 30
       0583.406819.39249582.886838.78497582.174448.48122581.6013 67.8737 581.041
77.56995580.958196.96243581.1731116.3549580.8164145.4436579.6894164.8361 579.128
184.2286578.8191193.9249 578.276223.0136577.4126252.1023576.3036 301.004574.8803
330.7235574.1986 360.443  573.74390.1625573.5486409.9755573.8109429.7884573.3992
459.5079573.7523518.9468574.3884538.7598574.7226578.3858574.9662627.9183575.8808
657.6378576.8133726.9832 578.365796.3287581.0484826.0482582.5215835.9546582.8809
#Mann= 3 , 0 , 0
       0     .16       0409.9755     .07       0459.5079     .16       0
Bank Sta=409.9755,459.5079
XS Rating Curve= 0 ,0
Exp/Cntr=0.3,0.1

Type RM Length L Ch R = 1 ,7548    ,234,234,234
BEGIN DESCRIPTION:
UNT 003 IN LACR 13.0
END DESCRIPTION:
XS GIS Cut Line= 3
      2140737.72     13204046.85      2141137.72     13204346.85
      2141737.76     13204146.84
#Sta/Elev= 30
    4500  582.22  4521.9  581.58  4536.5  580.66    4550  580.96    4600  580.42
  4636.5  578.85  4642.7  579.33  4657.3  578.39  4663.5  578.81  4742.7  576.04
  4771.9  576.02  4807.3  574.88  4942.7  572.32  4963.5  571.56  4986.5  571.38
  4989.7  570.83  4992.5  570.33  4995.7  570.83  4996.9  571.39  5010.5  571.33
  5021.1  571.77  5063.2  571.46  5084.3  572.31    5116  572.15  5126.5  572.67
  5168.7  572.94  5274.1  575.72  5284.6  576.43  5358.4  579.02  5632.5  592.28
#Mann= 4 ,-1 , 0
    4500     .16       0  4989.7     .07       0  4995.7     .16       0
  5632.5     .05       0
Bank Sta=4989.7,4995.7
XS Rating Curve= 0 ,0
Exp/Cntr=0.3,0.1

Type RM Length L Ch R = 1 ,7314    ,93,93,93
BEGIN DESCRIPTION:
Mapping XS 1da02f1e
END DESCRIPTION:
XS GIS Cut Line= 4
      2140819.63     13204186.62      2141062.65     13204464.36
      2141093.03     13204577.21      2141764.22     13204620.51
#Sta/Elev= 30
  4469.3  579.04  4596.1  576.51  4602.4  576.39    4645  575.64  4659.3  574.19
  4666.8  575.04  4673.5  574.11    4690  574.06  4829.1  571.55    4872  572.96
  4897.7  572.66  4911.9  571.58  4917.1  569.65  4923.8  568.92  4944.5  568.57
  4951.8  568.11  4954.6  567.03    4987  565.88  4989.7  565.38    4993  565.88
  5031.2  567.87  5050.1  573.31  5060.1   572.6  5070.1  568.77  5080.2  567.32
  5090.2  567.93  5110.2  570.92  5140.2  571.65  5240.5  574.33  5627.8  589.71
#Mann= 8 ,-1 , 0
  4469.3     .05       0  4596.1     .08       0  4602.4     .05       0
    4690      .1       0  4897.7     .12       0    4987     .07       0
    4993     .12       0  5140.2     .05       0
Bank Sta=4987,4993
XS Rating Curve= 0 ,0
Exp/Cntr=0.3,0.1

Type RM Length L Ch R = 1 ,7221    ,256,256,256
BEGIN DESCRIPTION:
Mapping XS 4ff0dbce
END DESCRIPTION:
XS GIS Cut Line= 4
      2140854.34     13204273.42      2141053.97     13204585.89
      2141080.01     13204664.01      2141748.46     13204690.06
#Sta/Elev= 30
  4507.8  577.41  4516.4  577.47  4602.4  575.39  4627.4  574.98  4772.9  571.67
  4853.9  570.44  4859.8  571.53  4868.3  571.31    4875  571.42  4877.4  573.26
  4900.7  572.12  4921.8  573.07  4937.7  571.18    4943  571.95  4953.4  571.06
  4959.8  569.64  5008.7  573.67  5018.7  573.47  5038.7  570.28  5098.8  571.72
  5108.8     571  5115.8  568.23  5118.5  567.73  5121.8  568.23  5128.8   570.5
  5161.6  570.46  5188.8  572.83  5318.9  577.07    5459  583.78  5629.9  590.13
#Mann= 8 ,-1 , 0
  4507.8     .05       0  4516.4     .08       0  4602.4     .05       0
  4627.4      .1       0  4868.3     .12       0  5115.8     .07       0
  5121.8     .12       0  5161.6     .05       0
Bank Sta=5115.8,5121.8
XS Rating Curve= 0 ,0
Exp/Cntr=0.3,0.1

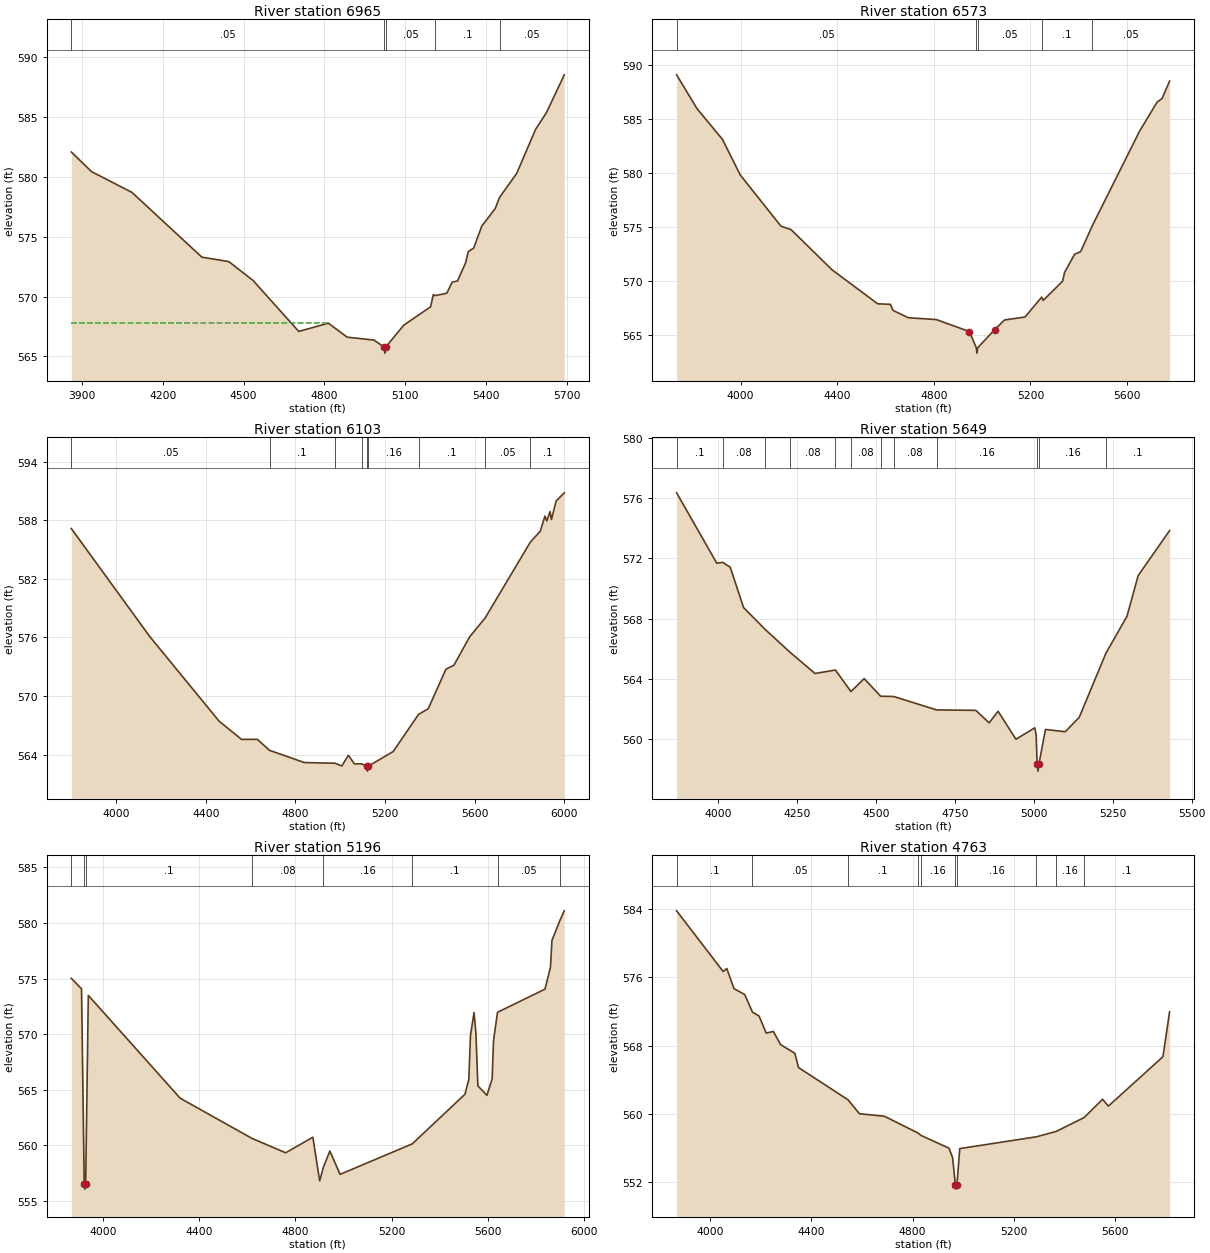
Type RM Length L Ch R = 1 ,6965    ,392,392,392
BEGIN DESCRIPTION:
UNT 003 IN LACR 12.0
END DESCRIPTION:
XS GIS Cut Line= 2
      2139832.66      13204857.2      2141664.35     13204864.14
#Sta/Elev= 30
  3859.6  582.07  3934.7  580.43  4084.7   578.7  4344.7  573.29  4444.7  572.92
  4534.7  571.35  4704.7  567.09  4814.7  567.78  4884.7  566.61  4984.7  566.37
  5021.7  565.78  5024.4  565.28  5027.7  565.78  5094.7  567.61  5194.7  569.15
  5204.7  570.17  5211.2  570.08  5254.7  570.28  5274.7   571.2  5294.7  571.31
  5324.7  572.82  5334.7  573.76  5354.7  574.05  5384.7  575.88  5434.7  577.35
  5450.6  578.27  5514.7  580.29  5584.7  583.96  5624.7  585.34  5691.3  588.51
#Mann= 5 ,-1 , 0
  3859.6     .05       0  5021.7     .03       0  5027.7     .05       0
  5211.2      .1       0  5450.6     .05       0
#XS Ineff= 2 , 0
         4814.74  567.78
Permanent Ineff=
       F       F
Bank Sta=5021.7,5027.7
XS Rating Curve= 0 ,0
Exp/Cntr=0.3,0.1

Type RM Length L Ch R = 1 ,6573    ,470,470,470
BEGIN DESCRIPTION:
UNT 003 IN LACR 11.0
END DESCRIPTION:
XS GIS Cut Line= 3
      2139737.73     13205596.85      2140937.72     13205196.85
      2141687.71     13204996.86
#Sta/Elev= 30
  3735.1   589.1  3819.4  585.97  3924.8  583.12  3998.6  579.82  4167.3  575.07
  4209.4  574.75  4378.1  571.04  4567.8  567.88  4620.5  567.83  4631.1  567.27
  4694.3  566.59  4810.3  566.42  4947.3  565.31  4975.9  563.81  4978.7  563.31
  4981.9  563.81  5051.7  565.48  5092.5  566.38  5177.9  566.66  5246.6   568.5
  5252.9   568.2  5333.1  569.97  5341.5  570.79  5382.9  572.47  5408.2  572.72
    5456  575.11    5652  583.88  5724.5  586.57  5745.2  586.91  5776.2  588.52
#Mann= 5 ,-1 , 0
  3735.1     .05       0  4975.9     .03       0  4981.9     .05       0
  5246.6      .1       0    5456     .05       0
Bank Sta=4947.3,5051.7
XS Rating Curve= 0 ,0
Exp/Cntr=0.3,0.1

Type RM Length L Ch R = 1 ,6103    ,454,454,454
BEGIN DESCRIPTION:
UNT 003 IN LACR 10.0
END DESCRIPTION:
XS GIS Cut Line= 3
      2139787.72     13205646.85      2140987.72     13205646.85
      2141787.72     13205046.85
#Sta/Elev= 30
    3800  587.17    4150   576.1    4460  567.41    4560  565.55    4630  565.56
  4684.8  564.43    4840  563.18  4976.4  563.11  5007.3  562.83  5036.5  563.93
  5063.5  563.04  5095.4  563.05  5118.9   562.8  5121.6   562.3  5124.9   562.8
  5236.5  564.31  5349.7  568.12  5392.7  568.69  5471.9  572.75  5507.3  573.15
  5578.1  576.08  5646.8     578  5848.6  585.78  5892.7  586.89  5913.5  588.44
  5921.9  587.95  5936.5  588.91  5942.7  588.09  5963.5  589.99    6000  590.83
#Mann= 9 ,-1 , 0
    3800     .05       0  4684.8      .1       0  4976.4     .05       0
  5095.4     .16       0  5118.9     .04       0  5124.9     .16       0
  5349.7      .1       0  5646.8     .05       0  5848.6      .1       0
Bank Sta=5118.9,5124.9
XS Rating Curve= 0 ,0
Exp/Cntr=0.3,0.1

Type RM Length L Ch R = 1 ,5649    ,453,453,453
BEGIN DESCRIPTION:
UNT 003 IN LACR 9.0
END DESCRIPTION:
XS GIS Cut Line= 3
       2140487.7     13206746.88      2141287.72     13205946.86
      2141537.71     13205596.87
#Sta/Elev= 30
  3868.6  576.36  3995.9  571.68    4014  571.74  4038.3  571.42  4080.8  568.73
  4149.6  567.27  4228.5  565.75    4307  564.35  4371.6  564.58  4420.8  563.15
  4462.6  564.01  4514.8  562.84  4556.3  562.82  4691.9  561.93  4816.2   561.9
  4858.6  561.07  4886.9  561.84  4943.4  559.98  5003.1  560.74  5007.4  560.28
  5010.5  558.36  5013.3  557.86  5016.5  558.36  5036.9  560.63  5099.5  560.48
  5143.8  561.43  5228.4   565.7  5294.9  568.14  5330.6  570.86  5430.1  573.85
#Mann= 12 ,-1 , 0
  3868.6      .1       0    4014     .08       0  4149.6      .1       0
  4228.5     .08       0  4371.6      .1       0  4420.8     .08       0
  4514.8     .16       0  4556.3     .08       0  4691.9     .16       0
  5010.5     .07       0  5016.5     .16       0  5228.4      .1       0
Bank Sta=5010.5,5016.5
XS Rating Curve= 0 ,0
Exp/Cntr=0.3,0.1

Type RM Length L Ch R = 1 ,5196    ,433,433,433
BEGIN DESCRIPTION:
UNT 003 IN LACR 8.0
END DESCRIPTION:
XS GIS Cut Line= 3
       2140737.7     13207096.88      2141537.72     13206296.85
      2141987.73     13205496.84
#Sta/Elev= 30
  3868.6  575.03  3911.1  574.08  3922.2  556.56  3924.9  556.06  3928.2  556.56
  3939.3  573.49  4321.2  564.24  4619.3  560.63  4759.6  559.33  4872.7  560.73
    4901  556.81  4916.7  558.04  4943.4  559.49  4985.9  557.39  5285.8  560.13
  5505.2   564.6  5521.1  565.94  5527.8  569.86  5542.8  571.95  5550.7  570.07
  5558.7  565.35  5596.3   564.5    5618  565.97  5623.7  569.41  5640.3  571.97
  5837.6  574.05  5860.5  576.03  5866.6  578.44  5900.8  580.29  5917.9   581.1
#Mann= 8 ,-1 , 0
  3868.6      .1       0  3922.2     .07       0  3928.2      .1       0
  4619.3     .08       0  4916.7     .16       0  5285.8      .1       0
  5640.3     .05       0  5900.8      .1       0
Bank Sta=3922.2,3928.2
XS Rating Curve= 0 ,0
Exp/Cntr=0.3,0.1

Type RM Length L Ch R = 1 ,4763    ,331,331,331
BEGIN DESCRIPTION:
UNT 003 IN LACR 7.0
END DESCRIPTION:
XS GIS Cut Line= 3
       2140937.7     13207446.88      2141737.72     13206646.85
      2141887.71      13205846.9
#Sta/Elev= 30
  3868.6  583.79  4052.5  576.67  4066.6  577.03  4094.9  574.67  4137.3  573.98
    4168  571.91  4193.9  571.46  4222.2  569.46  4250.5  569.65  4278.8  568.11
  4335.3  567.09  4349.5  565.42  4545.1  561.64  4589.9  560.01  4688.9  559.71
    4821  557.75  4832.8  557.47  4943.4  555.97  4957.6  554.86  4968.7  551.67
  4971.5  551.17  4974.7  551.67  4985.9  555.92  5287.8   557.3  5367.1  557.94
  5476.6  559.56  5549.4   561.7  5572.3   560.9  5787.7  566.69  5813.9  571.96
#Mann= 10 ,-1 , 0
  3868.6      .1       0    4168     .05       0  4545.1      .1       0
    4821     .12       0  4832.8     .16       0  4968.7     .07       0
  4974.7     .16       0  5287.8     .08       0  5367.1     .16       0
  5476.6      .1       0
Bank Sta=4968.7,4974.7
XS Rating Curve= 0 ,0
Exp/Cntr=0.3,0.1

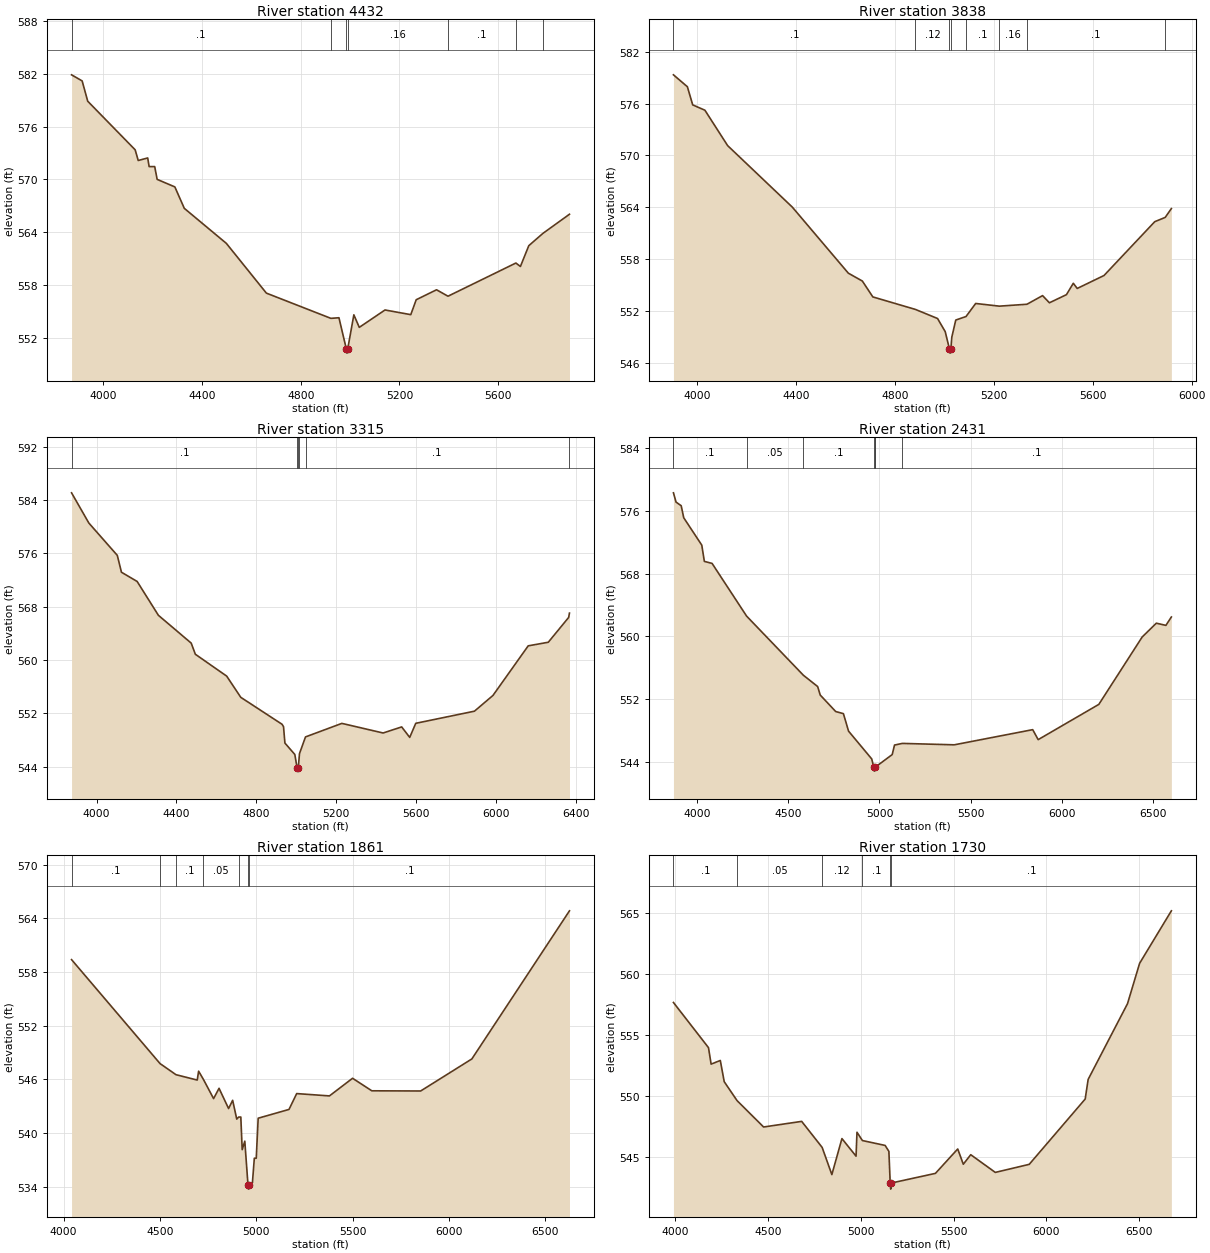
Type RM Length L Ch R = 1 ,4432    ,594,594,594
BEGIN DESCRIPTION:
UNT 003 IN LACR 6.0
END DESCRIPTION:
XS GIS Cut Line= 2
      2141478.48     13207794.75      2142422.36     13206011.09
#Sta/Elev= 30
    3871  581.86  3913.9  581.17  3936.5  578.87  4128.8  573.36  4141.2  572.15
  4179.6  572.44  4185.4  571.46    4208  571.46  4217.9  570.01  4289.6  569.16
  4327.9  566.73  4498.3  562.76  4660.6  557.12  4922.1  554.26  4954.7  554.33
  4984.4  550.82  4987.2  550.32  4990.4  550.82  5015.1  554.66  5037.1  553.24
  5141.4  555.21  5245.8  554.68  5267.8  556.37  5350.2   557.5  5396.7  556.77
  5671.8  560.53  5690.1  560.14  5724.2   562.5  5781.8   563.9    5889  566.06
#Mann= 7 ,-1 , 0
    3871      .1       0  4922.1     .16       0  4984.4     .07       0
  4990.4     .16       0  5396.7      .1       0  5671.8     .08       0
  5781.8      .1       0
Bank Sta=4984.4,4990.4
XS Rating Curve= 0 ,0
Exp/Cntr=0.3,0.1

Type RM Length L Ch R = 1 ,3838    ,523,523,523
BEGIN DESCRIPTION:
UNT 003 IN LACR 5.0
END DESCRIPTION:
XS GIS Cut Line= 3
      2141637.71     13207796.87      2142387.72     13206996.85
      2142837.73     13206196.84
#Sta/Elev= 30
  3903.4  579.33  3959.8  577.95  3981.3  575.85  4030.7  575.23  4122.7  571.13
  4384.3  564.01  4610.9  556.36  4667.6  555.45  4710.1  553.61  4882.5  552.16
  4971.9  551.11  5002.9  549.59  5019.9   547.6  5022.7   547.1  5025.9   547.6
  5029.6  548.95  5045.6  550.93  5087.1  551.34  5126.2  552.85    5222  552.54
  5333.6  552.76  5396.8  553.76  5424.5  552.93  5493.4  553.87  5521.1  555.19
    5537  554.59  5645.4  556.09  5850.6  562.32    5893  562.82  5917.9  563.84
#Mann= 8 ,-1 , 0
  3903.4      .1       0  4882.5     .12       0  5019.9     .07       0
  5025.9     .12       0  5087.1      .1       0    5222     .16       0
  5333.6      .1       0    5893     .08       0
Bank Sta=5019.9,5025.9
XS Rating Curve= 0 ,0
Exp/Cntr=0.3,0.1

Type RM Length L Ch R = 1 ,3315    ,884,884,884
BEGIN DESCRIPTION:
UNT 003 IN LACR 4.0
END DESCRIPTION:
XS GIS Cut Line= 3
      2141936.82     13208266.95      2142916.01     13207037.76
      2143013.19     13206121.43
#Sta/Elev= 30
  3875.1  585.07  3961.6  580.54  4104.1  575.69  4124.9  573.16  4203.4  571.78
  4309.9   566.7  4474.1  562.53  4494.9  560.86  4651.8  557.58  4722.3   554.4
  4928.9  550.36  4936.4     550  4943.3  547.54  4992.9  545.83  5004.4  543.83
  5007.1  543.33  5010.4  543.83  5016.3  545.96  5046.4  548.46  5228.4  550.49
    5435  549.05    5528  549.96  5568.2  548.39  5598.4   550.5  5892.3  552.32
    5985  554.68  6161.5  562.12  6262.1  562.66    6364  566.38  6368.1  567.03
#Mann= 6 ,-1 , 0
  3875.1      .1       0  5004.4     .07       0  5010.4      .1       0
  5016.3     .12       0  5046.4      .1       0    6364     .08       0
Bank Sta=5004.4,5010.4
XS Rating Curve= 0 ,0
Exp/Cntr=0.3,0.1

Type RM Length L Ch R = 1 ,2431    ,570,570,570
BEGIN DESCRIPTION:
UNT 003 IN LACR 2.0
END DESCRIPTION:
XS GIS Cut Line= 3
       2142487.7     13208596.88      2143287.72     13207796.85
      2143187.72     13206196.88
#Sta/Elev= 30
  3868.6  578.28  3882.8   577.1  3911.1  576.64  3925.2   575.1  4024.2  571.62
  4038.3  569.55  4080.8  569.29  4270.4  562.58  4582.2  555.05  4660.6  553.61
  4674.7  552.53  4759.6  550.43    4802  550.16  4830.3  547.93  4957.6  544.39
  4968.7  543.34  4971.5  542.84  4974.7  543.34  4976.7  543.34  5070.1  544.95
  5082.7  546.16  5125.5  546.37  5410.8  546.19  5841.6  548.12  5871.7  546.85
  6204.8  551.34  6442.8  559.92  6520.5  561.68  6573.1   561.4  6603.1  562.47
#Mann= 7 ,-1 , 0
  3868.6      .1       0  4270.4     .05       0  4582.2      .1       0
  4968.7     .07       0  4974.7      .1       0  4976.7     .12       0
  5125.5      .1       0
Bank Sta=4968.7,4974.7
XS Rating Curve= 0 ,0
Exp/Cntr=0.3,0.1

Type RM Length L Ch R = 1 ,1861    ,131,131,131
BEGIN DESCRIPTION:
Mapping XS 42b7c20c11
END DESCRIPTION:
XS GIS Cut Line= 4
        2143159.     13208341.11      2143794.42     13207710.89
      2143810.05     13206893.18      2143371.95     13206138.54
#Sta/Elev= 30
    4041  559.38  4500.5  547.77  4583.2  546.53  4693.6  545.93  4700.7  546.92
  4725.7     546  4778.5  543.86  4806.8  545.01  4856.3  542.75  4877.5  543.67
  4898.7  541.57  4908.8   541.8  4919.9   541.8    4927  538.16  4940.5  539.11
    4957  534.25  4959.7  533.75    4963  534.25    4980  534.45    4990   537.2
    5000   537.2    5010  541.67    5170  542.65    5210  544.42  5380.1  544.16
  5500.1  546.13  5600.1  544.73  5853.7  544.71  6119.6  548.29  6626.4  564.83
#Mann= 7 ,-1 , 0
    4041      .1       0  4500.5     .05       0  4583.2      .1       0
  4725.7     .05       0  4908.8      .1       0    4957     .07       0
    4963      .1       0
Bank Sta=4957,4963
XS Rating Curve= 0 ,0
Exp/Cntr=0.3,0.1

Type RM Length L Ch R = 1 ,1730    ,466,466,466
BEGIN DESCRIPTION:
Mapping XS 42b7c20c
END DESCRIPTION:
XS GIS Cut Line= 5
      2143273.62     13208389.68      2143909.01      13207759.5
      2143954.16     13207469.86      2143924.63     13206941.79
      2143457.44     13206096.65
#Sta/Elev= 30
  3991.1  557.64  4179.9  553.94    4194  552.59  4243.5  552.89  4264.7  551.15
  4333.9   549.6  4476.8  547.44  4681.9   547.9  4792.2  545.77  4844.5  543.54
  4898.8  546.49  4974.9  545.05  4979.9  547.01  5009.1  546.33  5131.6  545.93
  5151.8  545.44  5158.9  542.85  5161.7  542.35  5164.9  542.85  5402.5  543.64
  5522.7  545.64  5552.7  544.39  5592.8  545.17  5725.1  543.72  5907.9  544.38
  6209.4  549.73  6225.4  551.34  6437.3  557.54  6502.6  560.85  6673.7  565.15
#Mann= 6 ,-1 , 0
  3991.1      .1       0  4333.9     .05       0  4792.2     .12       0
  5009.1      .1       0  5158.9     .07       0  5164.9      .1       0
Bank Sta=5158.9,5164.9
XS Rating Curve= 0 ,0
Exp/Cntr=0.3,0.1

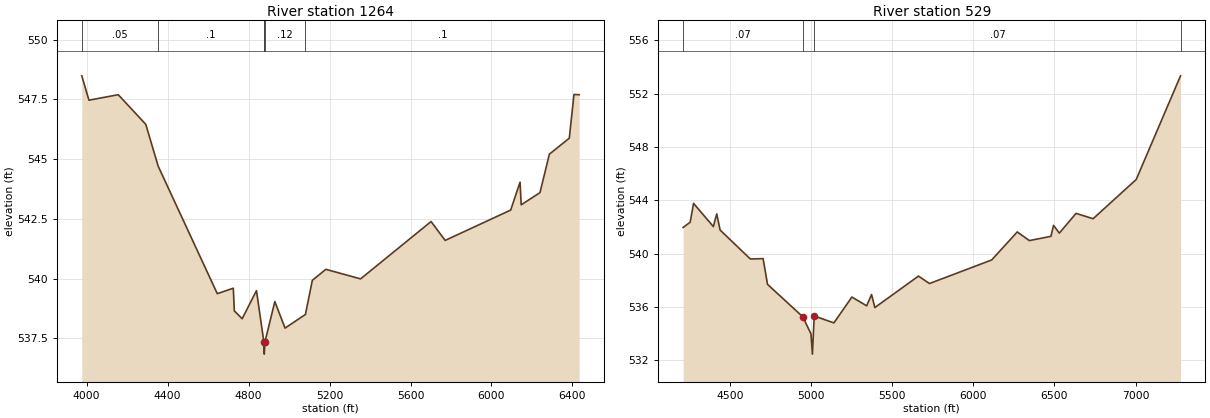
Type RM Length L Ch R = 1 ,1264    ,735,735,735
BEGIN DESCRIPTION:
Mapping XS 8f8e51d4
END DESCRIPTION:
XS GIS Cut Line= 4
      2143865.05     13208784.88       2144212.3     13208305.67
      2144323.41     13207451.51       2143913.7     13206534.86
#Sta/Elev= 30
  3976.1  548.49  4011.5  547.47  4156.2   547.7  4292.2  546.46  4353.4  544.71
  4645.5  539.37  4724.6   539.6  4729.6  538.65  4768.4  538.32    4839   539.5
  4873.9  537.45  4874.7  537.34  4877.5  536.84  4880.7  537.34  4929.7  539.04
  4980.2  537.93  5080.8   538.5    5115  539.93  5181.8  540.39  5353.3  539.99
  5701.6  542.39  5771.2   541.6  6094.8  542.87  6141.2  544.04  6146.7  543.09
  6239.5   543.6    6286  545.21  6384.3  545.88  6407.5  547.71  6433.3   547.7
#Mann= 6 ,-1 , 0
  3976.1     .05       0  4353.4      .1       0  4873.9     .12       0
  4874.7     .07       0  4880.7     .12       0  5080.8      .1       0
Bank Sta=4874.7,4880.7
XS Rating Curve= 0 ,0
Exp/Cntr=0.3,0.1

Type RM Length L Ch R = 1 ,529     ,0,0,0
BEGIN DESCRIPTION:
UNT 003 IN LACR 1.0
END DESCRIPTION:
XS GIS Cut Line= 5
      2144219.25     13208979.28      2144635.91     13208652.89
      2144726.19     13207993.17       2144274.8     13207125.12
      2143865.06     13206333.41
#Sta/Elev= 30
  4212.3  541.96  4255.8  542.36  4276.6  543.77  4398.6  542.03  4419.4  542.98
  4440.3  541.77  4626.5   539.6  4705.1  539.63  4732.3   537.7  4949.5  535.27
    5000  533.99  5008.8  532.47  5020.2  535.33  5141.3  534.81  5252.3  536.75
  5343.2  536.09  5373.4  536.94  5393.6  535.96  5662.5  538.32  5730.2  537.76
  6113.8  539.53  6271.2  541.63  6345.7  540.98  6478.5   541.3    6495  542.12
  6530.3  541.54  6633.5  543.02  6738.5  542.62  7004.2  545.56  7277.3  553.33
#Mann= 4 ,-1 , 0
  4212.3     .07       0  4949.5    .035       0  5020.2     .07       0
  7277.3      .1       0
Bank Sta=4949.5,5020.2
XS Rating Curve= 0 ,0
Exp/Cntr=0.3,0.1

Chan Stop Cuts=-1
Use User Specified Reach Order=0
Composite Channel Slope=5