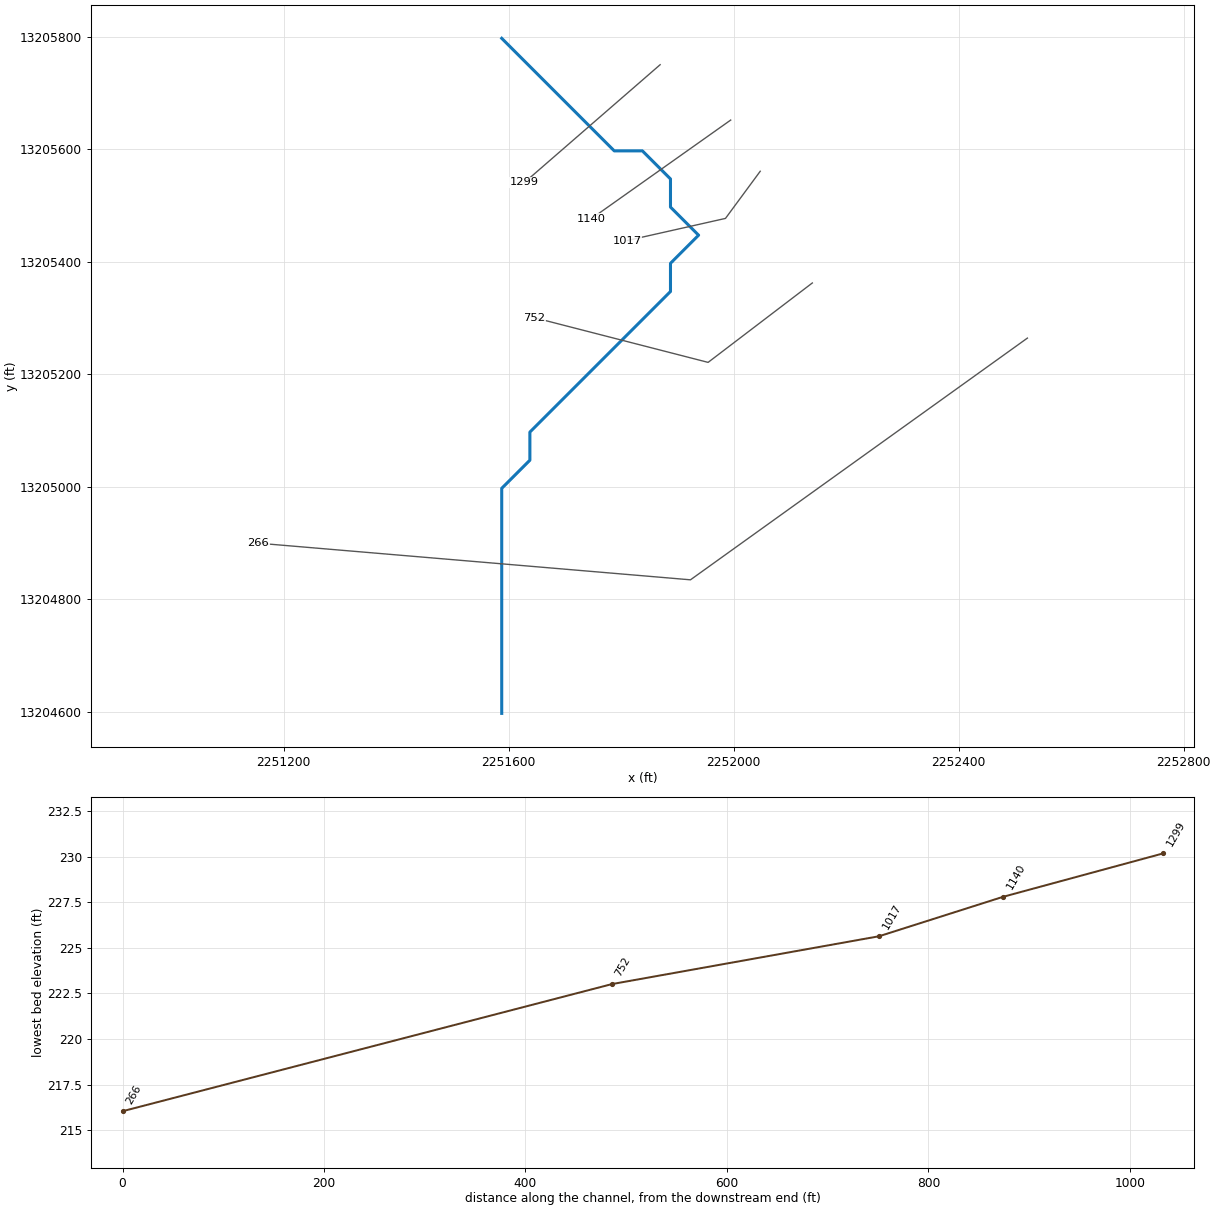
--- UNT 004 IN LACR.prj (project) ---

Proj Title=UNT 004 IN LACR Base Level Engineering
Current Plan=p01
Default Exp/Contr=0.3,0.1
English Units
Geom File=g01
Flow File=f01
Plan File=p01
BEGIN DESCRIPTION:
UNT 004 IN LACR
END DESCRIPTION:

--- UNT 004 IN LACR.p01 (plan) ---

Plan Title=Multiple Run
Short Identifier=Multiple
Geom File=g01
Flow File=f01
Subcritical Flow
K Sum by GR= 0
Std Step Tol= 0.01
Critical Tol= 0.01
Num of Std Step Trials= 20
Max Error Tol= 0.3
Flow Tol Ratio= 0.001
Split Flow NTrial= 30
Split Flow Tol= 0.02
Split Flow Ratio= 0.02
Log Output Level= 0
Friction Slope Method= 1
Unsteady Friction Slope Method= 2
Unsteady Bridges Friction Slope Method= 1
Parabolic Critical Depth
Global Vel Dist=  1 , 1 , 1
Global Log Level= 0
CheckData=True
Encroach Param= -1, 0, 0, 0
BEGIN DESCRIPTION:
Multiple Run
END DESCRIPTION:

--- UNT 004 IN LACR.f01 (steady flow) ---

Flow Title=Multiple
Number of Profiles=7
Profile Names=10-year,25-year,50-year,1pct_min,100-year,1pct_plu,500-year
River Rch & RM= UNT 004 IN LACR,Reach-1,1299
      59      75      87      75     102     137     139
Boundary for River Rch & Prof#=UNT 004 IN LACR,Reach-1,1
Up Type=0
Dn Type=3
Dn Slope=0.005
Boundary for River Rch & Prof#=UNT 004 IN LACR,Reach-1,2
Up Type=0
Dn Type=3
Dn Slope=0.005
Boundary for River Rch & Prof#=UNT 004 IN LACR,Reach-1,3
Up Type=0
Dn Type=3
Dn Slope=0.005
Boundary for River Rch & Prof#=UNT 004 IN LACR,Reach-1,4
Up Type=0
Dn Type=3
Dn Slope=0.005
Boundary for River Rch & Prof#=UNT 004 IN LACR,Reach-1,5
Up Type=0
Dn Type=3
Dn Slope=0.005
Boundary for River Rch & Prof#=UNT 004 IN LACR,Reach-1,6
Up Type=0
Dn Type=3
Dn Slope=0.005
Boundary for River Rch & Prof#=UNT 004 IN LACR,Reach-1,7
Up Type=0
Dn Type=3
Dn Slope=0.005

--- UNT 004 IN LACR.g01 (geometry) ---

Geom Title=Existing Conditions

River Reach=UNT 004 IN LACR,Reach-1
Reach XY= 26
      2251587.72     13205796.85      2251637.72     13205746.85
      2251687.72     13205696.85      2251737.72     13205646.85
      2251787.72     13205596.86      2251837.72     13205596.86
      2251887.72     13205546.85      2251887.72     13205496.85
      2251937.72     13205446.86      2251887.72     13205396.85
      2251887.72     13205346.85      2251837.72     13205296.85
      2251787.72     13205246.85      2251737.72     13205196.85
      2251687.72     13205146.85      2251637.72     13205096.86
      2251637.72     13205046.85      2251587.72     13204996.85
      2251587.72     13204946.86      2251587.72     13204896.85
      2251587.72     13204846.85      2251587.72     13204796.86
      2251587.72     13204746.85      2251587.72     13204696.85
      2251587.72     13204646.85      2251587.72     13204596.85

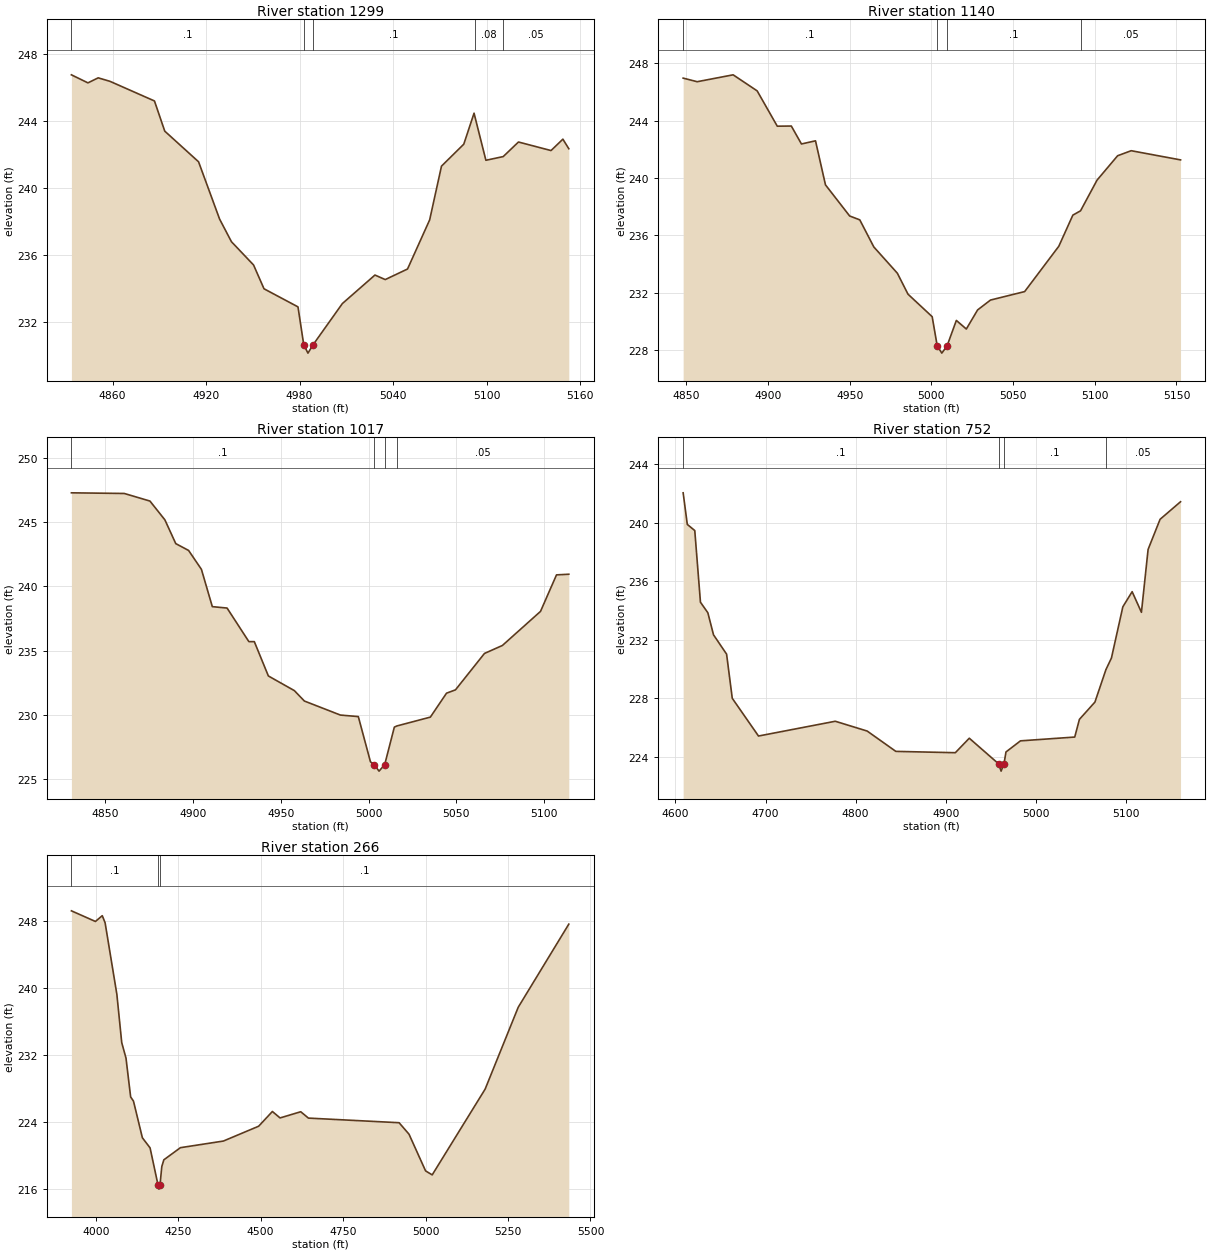
Type RM Length L Ch R = 1,1299,159,159,159
BEGIN DESCRIPTION:
UNT 004 IN LACR 3.0
END DESCRIPTION:
XS GIS Cut Line= 2
      2251869.34     13205749.97      2251628.29     13205540.73
#Sta/Elev= 30
  4833.6  246.78  4844.2  246.30  4850.8  246.60  4858.4  246.39  4886.9  245.22
  4893.5  243.42  4915.2  241.59  4928.7  238.17  4936.3  236.82  4950.5  235.43
  4957.2  234.01  4979.0  232.93  4982.7  230.67  4985.4  230.17  4988.7  230.67
  5007.5  233.13  5028.4  234.83  5035.0  234.56  5049.3  235.19  5063.5  238.12
  5071.1  241.33  5085.4  242.64  5092.0  244.49  5092.8  244.19  5099.6  241.68
  5110.7  241.90  5120.5  242.77  5141.4  242.26  5149.0  242.94  5152.8  242.37
#Mann=5,-1,0
  4833.6     0.1       0  4982.7    0.07       0  4988.7     0.1       0
  5092.8    0.08       0  5110.7    0.05       0
Bank Sta=4982.7,4988.7
Exp/Cntr=0.3,0.1

Type RM Length L Ch R = 1,1140,123,123,123
BEGIN DESCRIPTION:
Mapping XS e8ee9166
END DESCRIPTION:
XS GIS Cut Line= 2
      2251994.76     13205651.56      2251746.31     13205475.68
#Sta/Elev= 30
  4848.1  246.96  4856.7  246.71  4878.7  247.19  4893.4  246.07  4905.7  243.61
  4914.3  243.62  4920.5  242.37  4929.1  242.59  4935.2  239.52  4950.0  237.35
  4956.2  237.08  4964.8  235.19  4979.2  233.36  4985.7  231.90  5000.5  230.33
  5003.6  228.29  5006.4  227.79  5009.6  228.29  5015.3  230.07  5021.4  229.47
  5028.3  230.80  5036.2  231.49  5057.1  232.08  5078.0  235.24  5086.6  237.41
  5091.3  237.71  5101.4  239.85  5114.0  241.55  5122.3  241.90  5152.5  241.26
#Mann=4,-1,0
  4848.1     0.1       0  5003.6    0.07       0  5009.6     0.1       0
  5091.3    0.05       0
Bank Sta=5003.6,5009.6
Exp/Cntr=0.3,0.1

Type RM Length L Ch R = 1,1017,265,265,265
BEGIN DESCRIPTION:
Mapping XS 45a2e291
END DESCRIPTION:
XS GIS Cut Line= 3
      2252047.26     13205560.57      2251985.48     13205476.73
      2251810.89     13205437.44
#Sta/Elev= 30
  4830.9  247.27  4861.0  247.22  4875.6  246.63  4884.1  245.17  4890.3  243.32
  4897.6  242.79  4904.9  241.32  4911.1  238.42  4919.5  238.31  4931.9  235.70
  4935.0  235.70  4943.0  233.03  4957.8  231.89  4963.5  231.08  4984.0  229.99
  4994.2  229.87  5001.1  226.36  5003.2  226.13  5006.0  225.63  5009.2  226.13
  5014.7  229.05  5016.1  229.14  5035.2  229.83  5044.4  231.69  5049.5  231.95
  5066.0  234.78  5076.2  235.40  5097.9  238.05  5107.0  240.89  5114.0  240.94
#Mann=4,-1,0
  4830.9     0.1       0  5003.2    0.07       0  5009.2     0.1       0
  5016.1    0.05       0
Bank Sta=5003.2,5009.2
Exp/Cntr=0.3,0.1

Type RM Length L Ch R = 1,752,486,486,486
BEGIN DESCRIPTION:
UNT 004 IN LACR 2.0
END DESCRIPTION:
XS GIS Cut Line= 3
      2252139.89     13205361.99      2251954.60     13205220.81
      2251645.69     13205300.24
#Sta/Elev= 30
  4608.6  242.04  4613.2  239.88  4621.5  239.46  4627.8  234.56  4636.0  233.84
  4642.3  232.33  4656.8  231.01  4663.1  227.99  4692.2  225.41  4777.4  226.42
  4812.8  225.75  4844.6  224.36  4910.6  224.27  4926.1  225.26  4958.6  223.51
  4961.4  223.01  4964.6  223.51  4966.8  224.32  4982.9  225.08  5043.1  225.34
  5048.3  226.55  5065.5  227.73  5077.7  229.95  5083.8  230.74  5096.5  234.25
  5106.8  235.28  5117.1  233.87  5124.5  238.17  5137.8  240.23  5160.5  241.43
#Mann=4,-1,0
  4608.6     0.1       0  4958.6    0.07       0  4964.6     0.1       0
  5077.7    0.05       0
Bank Sta=4958.6,4964.6
Exp/Cntr=0.3,0.1

Type RM Length L Ch R = 1,266,0,0,0
BEGIN DESCRIPTION:
UNT 004 IN LACR 1.0
END DESCRIPTION:
XS GIS Cut Line= 3
      2252522.22     13205263.99      2251923.24     13204834.28
      2251154.97     13204899.39
#Sta/Elev= 30
  3926.1  249.27  3998.9  248.00  4019.7  248.69  4028.3  247.84  4063.9  239.31
  4078.7  233.53  4091.6  231.69  4105.7  227.05  4114.3  226.55  4141.3  222.17
  4164.6  220.97  4188.7  216.54  4191.4  216.04  4194.7  216.54  4200.2  218.74
  4206.4  219.54  4256.7  220.99  4386.9  221.78  4493.8  223.55  4535.5  225.31
  4558.8  224.54  4621.5  225.28  4644.8  224.52  4919.7  223.97  4949.8  222.60
  5000.0  218.22  5020.1  217.74  5180.6  227.98  5281.0  237.76  5434.3  247.68
#Mann=3,-1,0
  3926.1     0.1       0  4188.7    0.07       0  4194.7     0.1       0
Bank Sta=4188.7,4194.7
Exp/Cntr=0.3,0.1

Chan Stop Cuts=-1