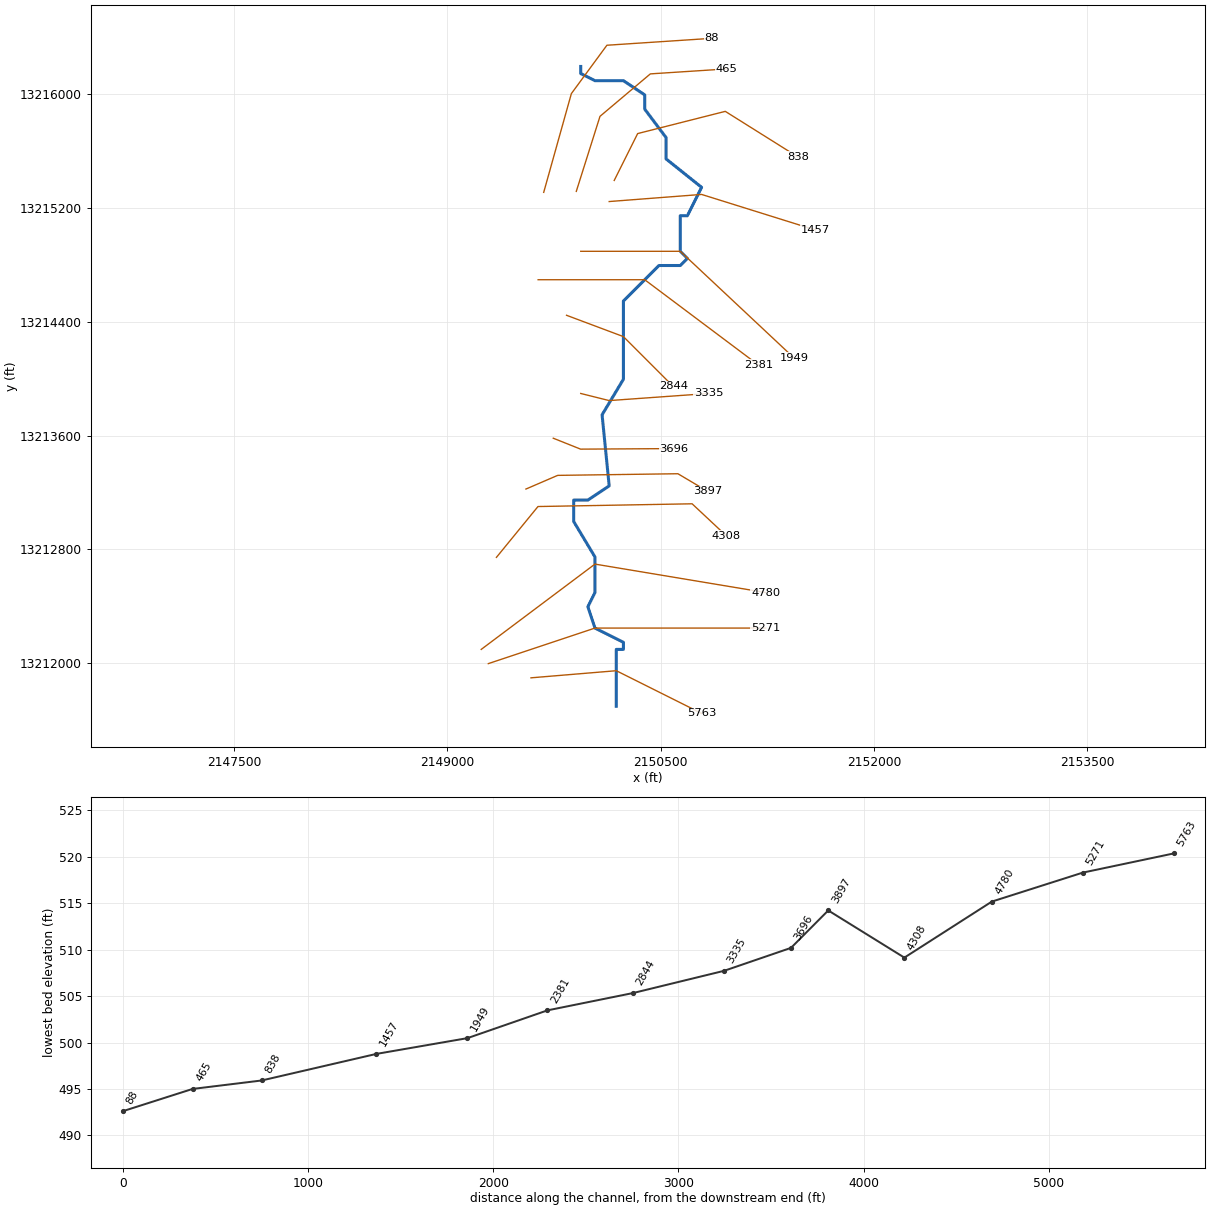
--- UNT 005 IN LACR.prj (project) ---

Proj Title=UNT 005 IN LACR Base Level Engineering
Current Plan=p01
Default Exp/Contr=0.3,0.1
English Units
Geom File=g01
Flow File=f01
Plan File=p01
BEGIN DESCRIPTION:
UNT 005 IN LACR
END DESCRIPTION:

--- UNT 005 IN LACR.p01 (plan) ---

Plan Title=Multiple Run
Short Identifier=Multiple
Geom File=g01
Flow File=f01
Subcritical Flow
K Sum by GR= 0
Std Step Tol= 0.01
Critical Tol= 0.01
Num of Std Step Trials= 20
Max Error Tol= 0.3
Flow Tol Ratio= 0.001
Split Flow NTrial= 30
Split Flow Tol= 0.02
Split Flow Ratio= 0.02
Log Output Level= 0
Friction Slope Method= 1
Unsteady Friction Slope Method= 2
Unsteady Bridges Friction Slope Method= 1
Parabolic Critical Depth
Global Vel Dist=  1 , 1 , 1
Global Log Level= 0
CheckData=True
Encroach Param= -1, 0, 0, 0
BEGIN DESCRIPTION:
Multiple Run
END DESCRIPTION:

--- UNT 005 IN LACR.f01 (steady flow) ---

Flow Title=Multiple
Number of Profiles=7
Profile Names=10-year,25-year,50-year,1pct_min,100-year,1pct_plu,500-year
River Rch & RM= UNT 005 IN LACR,Reach-1,5763
     187     261     324     295     399     540     618
River Rch & RM= UNT 005 IN LACR,Reach-1,5271
     224     315     391     357     483     654     751
Boundary for River Rch & Prof#=UNT 005 IN LACR,Reach-1,1
Up Type=0
Dn Type=3
Dn Slope=0.005
Boundary for River Rch & Prof#=UNT 005 IN LACR,Reach-1,2
Up Type=0
Dn Type=3
Dn Slope=0.005
Boundary for River Rch & Prof#=UNT 005 IN LACR,Reach-1,3
Up Type=0
Dn Type=3
Dn Slope=0.005
Boundary for River Rch & Prof#=UNT 005 IN LACR,Reach-1,4
Up Type=0
Dn Type=3
Dn Slope=0.005
Boundary for River Rch & Prof#=UNT 005 IN LACR,Reach-1,5
Up Type=0
Dn Type=3
Dn Slope=0.005
Boundary for River Rch & Prof#=UNT 005 IN LACR,Reach-1,6
Up Type=0
Dn Type=3
Dn Slope=0.005
Boundary for River Rch & Prof#=UNT 005 IN LACR,Reach-1,7
Up Type=0
Dn Type=3
Dn Slope=0.005

--- UNT 005 IN LACR.g01 (geometry) ---

Geom Title=Existing Conditions

River Reach=UNT 005 IN LACR,Reach-1
Reach XY= 30
      2150187.72     13211696.85      2150187.72     13212096.85
      2150237.72     13212096.85      2150237.72     13212146.86
      2150037.72     13212246.85      2149987.72     13212396.85
      2150037.72     13212496.86      2150037.72     13212746.85
      2149887.72     13212996.86      2149887.72     13213146.86
      2149987.72     13213146.86      2150137.72     13213246.85
      2150087.72     13213746.85      2150237.72     13213996.85
      2150237.72     13214546.85      2150487.72     13214796.86
      2150637.72     13214796.86      2150687.72     13214846.85
      2150637.72     13214896.85      2150637.72     13215146.85
      2150687.72     13215146.85      2150787.72     13215346.85
      2150537.72     13215546.85      2150537.72     13215696.85
      2150387.72     13215896.85      2150387.72     13215996.85
      2150237.72     13216096.86      2150037.72     13216096.86
      2149937.72     13216146.85      2149937.72     13216196.85

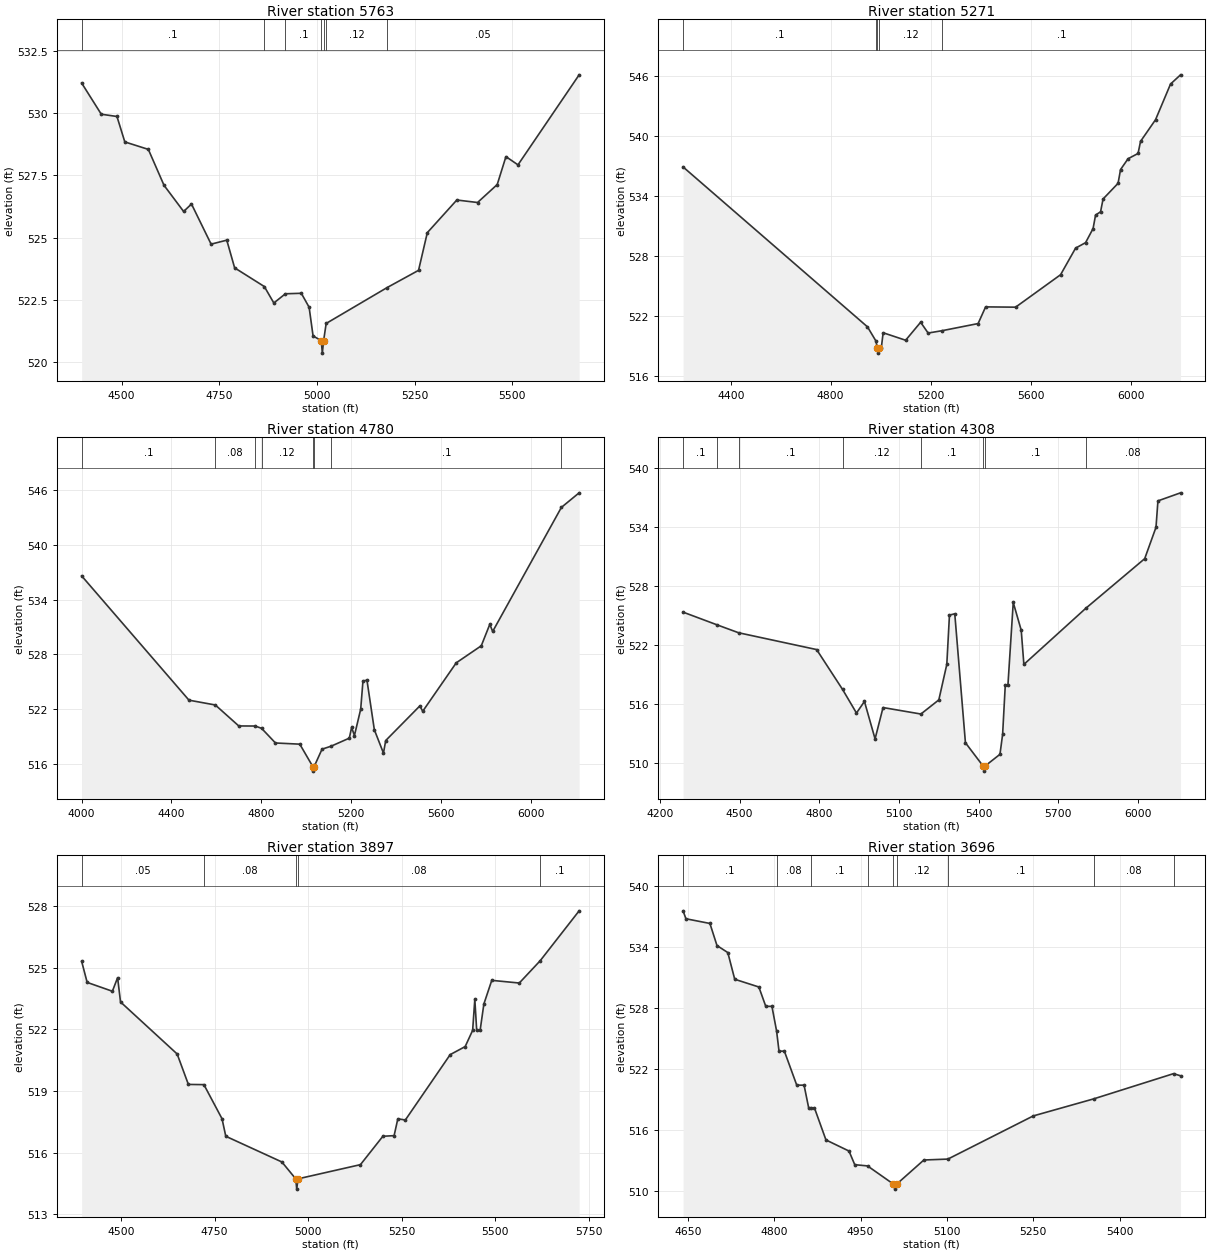
Type RM Length L Ch R = 1,5763,492,492,492
BEGIN DESCRIPTION:
UNT 005 IN LACR 11.0
END DESCRIPTION:
XS GIS Cut Line= 3
      2149587.70     13211896.85      2150187.72     13211946.85
      2150787.70     13211646.86
#Sta/Elev= 30
  4397.9  531.20  4448.1  529.95  4488.2  529.86  4508.3  528.84  4568.5  528.54
  4608.6  527.10  4658.8  526.05  4678.9  526.35  4729.1  524.74  4769.2  524.90
  4789.3  523.79  4865.3  523.04  4889.6  522.38  4919.2  522.75  4959.9  522.77
  4979.9  522.21  4990.0  521.06  5011.0  520.87  5013.7  520.37  5017.0  520.87
  5023.5  521.56  5179.6  523.00  5259.9  523.69  5282.3  525.20  5357.8  526.51
  5410.9  526.41  5461.2  527.13  5483.5  528.25  5514.3  527.92  5670.8  531.53
#Mann=7,-1,0
  4397.9     0.1       0  4865.3    0.12       0  4919.2     0.1       0
  5011.0    0.07       0  5017.0     0.1       0  5023.5    0.12       0
  5179.6    0.05       0
Bank Sta=5011,5017
Exp/Cntr=0.3,0.1

Type RM Length L Ch R = 1,5271,491,491,491
BEGIN DESCRIPTION:
UNT 005 IN LACR 10.0
END DESCRIPTION:
XS GIS Cut Line= 3
      2149287.69     13211996.85      2150037.72     13212246.85
      2151237.72     13212246.85
#Sta/Elev= 30
  4209.4  536.94  4947.3  520.93  4981.2  519.51  4986.5  518.80  4989.2  518.30
  4992.5  518.80  5002.5  518.80  5010.0  520.34  5100.0  519.59  5160.0  521.39
  5190.0  520.31  5246.7  520.55  5390.0  521.26  5420.0  522.93  5540.0  522.90
  5720.0  526.15  5780.0  528.81  5820.0  529.36  5850.0  530.77  5860.0  532.12
  5880.0  532.45  5890.0  533.73  5950.0  535.30  5960.0  536.68  5990.0  537.76
  6030.0  538.29  6040.0  539.50  6100.0  541.67  6160.0  545.24  6200.0  546.16
#Mann=5,-1,0
  4209.4     0.1       0  4981.2    0.12       0  4986.5    0.07       0
  4992.5    0.12       0  5246.7     0.1       0
Bank Sta=4986.5,4992.5
Exp/Cntr=0.3,0.1

Type RM Length L Ch R = 1,4780,472,472,472
BEGIN DESCRIPTION:
UNT 005 IN LACR 9.0
END DESCRIPTION:
XS GIS Cut Line= 3
      2149237.72     13212096.85      2150037.72     13212696.85
      2151237.77     13212496.85
#Sta/Elev= 30
  4000.0  536.61  4478.1  522.97  4595.6  522.44  4700.0  520.14  4773.1  520.13
  4801.6  519.88  4863.5  518.27  4971.9  518.14  5029.9  515.68  5032.7  515.18
  5035.9  515.68  5071.0  517.59  5111.7  517.92  5192.6  518.80  5202.8  519.98
  5215.4  519.09  5243.3  521.98  5253.4  525.07  5271.2  525.16  5304.1  519.72
  5344.7  517.16  5354.8  518.54  5506.9  522.34  5519.6  521.75  5669.1  527.07
  5780.6  528.94  5818.6  531.30  5831.3  530.51  6137.5  544.13  6216.6  545.73
#Mann=8,-1,0
  4000.0     0.1       0  4595.6    0.08       0  4773.1     0.1       0
  4801.6    0.12       0  5029.9    0.07       0  5035.9    0.12       0
  5111.7     0.1       0  6137.5    0.08       0
Bank Sta=5029.9,5035.9
Exp/Cntr=0.3,0.1

Type RM Length L Ch R = 1,4308,411,411,411
BEGIN DESCRIPTION:
Mapping XS e41df55a
END DESCRIPTION:
XS GIS Cut Line= 4
      2149344.62     13212744.13      2149636.82     13213101.68
      2150720.98     13213120.91      2150959.35     13212897.92
#Sta/Elev= 30
  4287.3  525.33  4416.8  524.02  4496.4  523.23  4790.0  521.52  4887.7  517.46
  4940.0  515.06  4970.0  516.24  5010.0  512.43  5040.0  515.62  5182.5  514.96
  5250.0  516.40  5280.0  520.01  5290.0  525.03  5310.0  525.16  5350.1  512.04
  5417.1  509.65  5419.8  509.15  5423.1  509.65  5480.1  510.86  5490.1  512.89
  5500.1  517.91  5510.1  517.91  5530.1  526.31  5560.1  523.49  5570.1  520.01
  5803.2  525.72  6024.9  530.77  6067.4  533.96  6074.7  536.65  6159.8  537.47
#Mann=8,-1,0
  4287.3     0.1       0  4416.8    0.05       0  4496.4     0.1       0
  4887.7    0.12       0  5182.5     0.1       0  5417.1    0.07       0
  5423.1     0.1       0  5803.2    0.08       0
Bank Sta=5417.1,5423.1
Exp/Cntr=0.3,0.1

Type RM Length L Ch R = 1,3897,201,201,201
BEGIN DESCRIPTION:
UNT 005 IN LACR 8.0
END DESCRIPTION:
XS GIS Cut Line= 4
      2149552.28     13213224.73      2149775.22     13213320.82
      2150621.02     13213332.36      2150828.66     13213209.31
#Sta/Elev= 30
  4394.7  525.30  4409.4  524.28  4476.8  523.85  4490.8  524.51  4498.6  523.33
  4650.0  520.80  4680.0  519.32  4721.5  519.31  4770.0  517.65  4780.0  516.80
  4930.0  515.55  4967.0  514.73  4969.7  514.23  4973.0  514.73  5140.0  515.42
  5200.0  516.80  5230.0  516.83  5240.0  517.65  5260.0  517.59  5380.0  520.77
  5420.0  521.16  5440.0  521.95  5445.8  523.46  5450.8  521.95  5460.0  521.95
  5470.0  523.23  5491.1  524.38  5564.7  524.25  5620.4  525.33  5724.7  527.76
#Mann=5,-1,0
  4394.7    0.05       0  4721.5    0.08       0  4967.0    0.07       0
  4973.0    0.08       0  5620.4     0.1       0
Bank Sta=4967,4973
Exp/Cntr=0.3,0.1

Type RM Length L Ch R = 1,3696,361,361,361
BEGIN DESCRIPTION:
UNT 005 IN LACR 7.0
END DESCRIPTION:
XS GIS Cut Line= 3
      2149744.43     13213582.26      2149936.69     13213505.36
      2150593.41     13213509.20
#Sta/Elev= 30
  4641.9  537.53  4646.9  536.75  4688.5  536.29  4700.8  534.12  4719.6  533.43
  4731.6  530.81  4773.5  530.05  4785.5  528.15  4796.2  528.15  4804.3  525.72
  4808.5  523.75  4817.8  523.75  4839.3  520.41  4852.0  520.41  4860.0  518.18
  4864.1  518.18  4870.0  518.18  4890.0  515.03  4930.0  513.94  4940.0  512.60
  4962.2  512.48  5007.0  510.70  5009.7  510.20  5013.0  510.70  5060.0  513.06
  5101.7  513.15  5250.0  517.39  5354.7  519.06  5493.5  521.54  5505.7  521.33
#Mann=9,-1,0
  4641.9     0.1       0  4804.3    0.08       0  4864.1     0.1       0
  4962.2    0.12       0  5007.0    0.07       0  5013.0    0.12       0
  5101.7     0.1       0  5354.7    0.08       0  5493.5     0.1       0
Bank Sta=5007,5013
Exp/Cntr=0.3,0.1

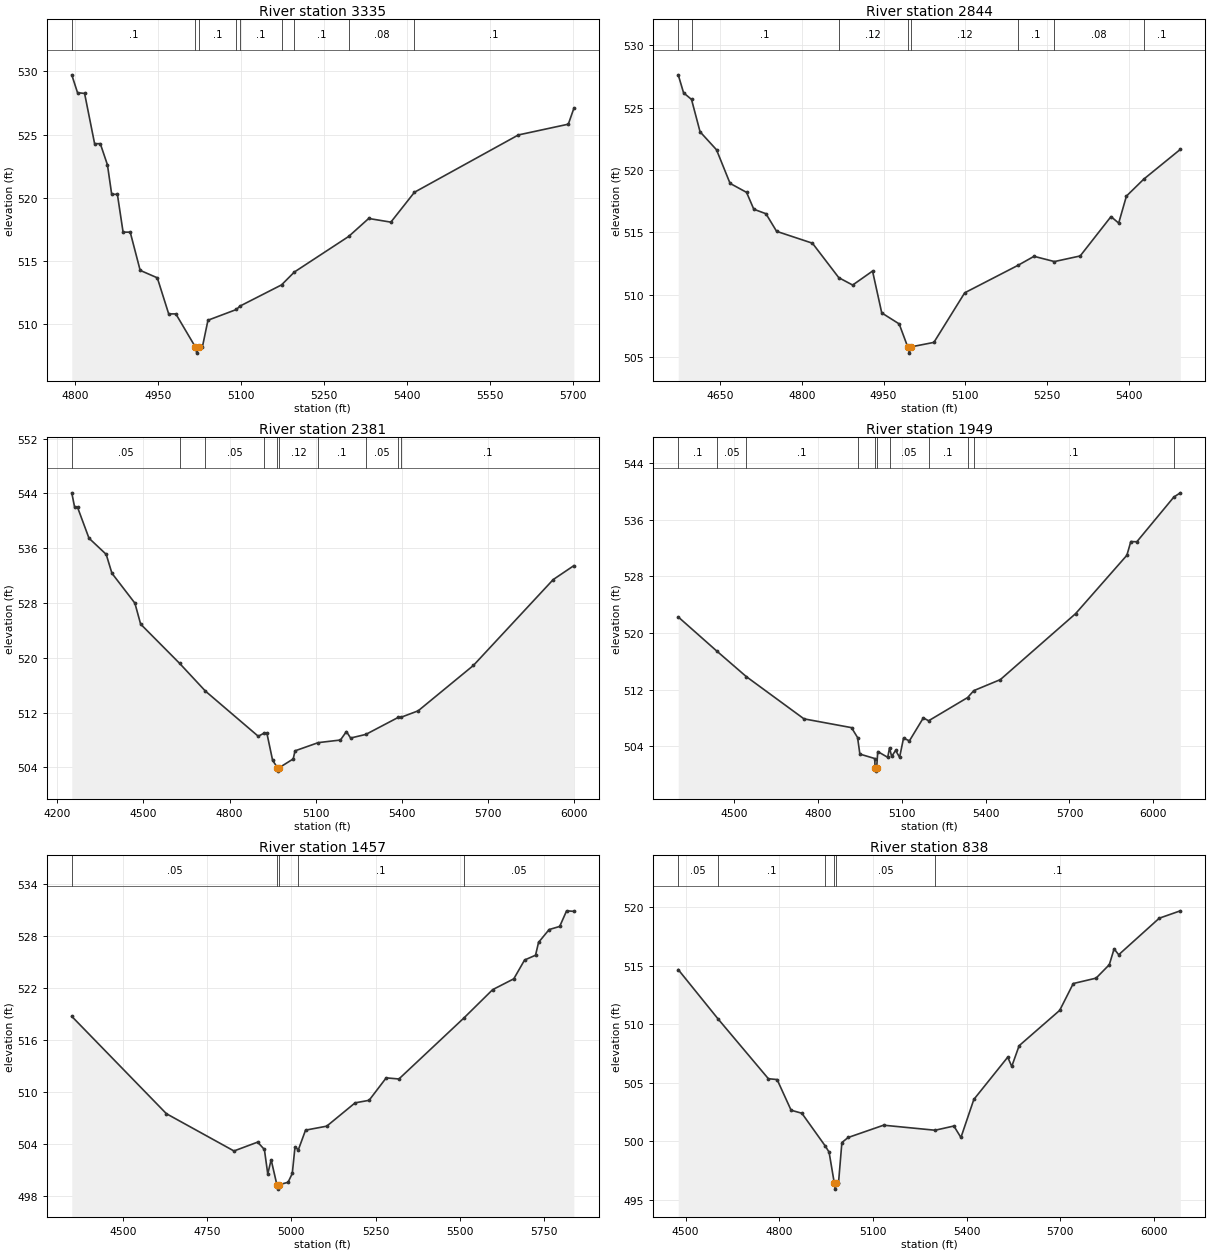
Type RM Length L Ch R = 1,3335,491,491,491
BEGIN DESCRIPTION:
UNT 005 IN LACR 6.0
END DESCRIPTION:
XS GIS Cut Line= 3
      2149937.68     13213896.87      2150137.72     13213846.85
      2150837.74     13213896.86
#Sta/Elev= 30
  4793.8  529.72  4804.2  528.31  4817.0  528.25  4835.1  524.28  4845.4  524.28
  4858.3  522.61  4866.0  520.28  4876.3  520.28  4886.6  517.29  4899.5  517.29
  4917.5  514.27  4948.5  513.68  4969.1  510.83  4982.0  510.83  5017.1  508.23
  5019.8  507.73  5023.1  508.23  5030.1  508.23  5040.1  510.33  5091.7  511.18
  5097.7  511.44  5173.1  513.12  5196.4  514.14  5294.6  516.95  5330.8  518.37
  5370.9  518.08  5413.5  520.44  5601.5  524.97  5691.8  525.82  5701.8  527.07
#Mann=9,-1,0
  4793.8     0.1       0  5017.1    0.07       0  5023.1     0.1       0
  5091.7    0.12       0  5097.7     0.1       0  5173.1    0.12       0
  5196.4     0.1       0  5294.6    0.08       0  5413.5     0.1       0
Bank Sta=5017.1,5023.1
Exp/Cntr=0.3,0.1

Type RM Length L Ch R = 1,2844,463,463,463
BEGIN DESCRIPTION:
UNT 005 IN LACR 5.0
END DESCRIPTION:
XS GIS Cut Line= 3
      2149837.72     13214446.85      2150237.72     13214296.86
      2150587.74     13213946.84
#Sta/Elev= 30
  4572.8  527.62  4582.6  526.18  4597.2  525.65  4612.9  523.06  4643.1  521.62
  4668.0  518.93  4698.3  518.21  4711.6  516.86  4733.9  516.50  4753.5  515.09
  4819.3  514.14  4867.7  511.38  4893.2  510.79  4929.7  511.91  4946.6  508.56
  4978.6  507.68  4994.3  505.84  4997.1  505.34  5000.3  505.84  5042.4  506.20
  5099.0  510.17  5196.9  512.37  5226.3  513.09  5263.8  512.67  5311.1  513.12
  5367.7  516.27  5381.8  515.75  5396.0  517.91  5427.9  519.27  5495.0  521.65
#Mann=8,-1,0
  4572.8    0.05       0  4597.2     0.1       0  4867.7    0.12       0
  4994.3    0.07       0  5000.3    0.12       0  5196.9     0.1       0
  5263.8    0.08       0  5427.9     0.1       0
Bank Sta=4994.3,5000.3
Exp/Cntr=0.3,0.1

Type RM Length L Ch R = 1,2381,432,432,432
BEGIN DESCRIPTION:
UNT 005 IN LACR 4.0
END DESCRIPTION:
XS GIS Cut Line= 3
      2149637.72     13214696.85      2150387.72     13214696.85
      2151187.72     13214096.85
#Sta/Elev= 30
  4250.0  544.09  4260.0  541.99  4270.0  541.99  4310.0  537.47  4370.0  535.11
  4390.0  532.35  4470.0  527.99  4490.0  524.93  4626.1  519.19  4716.1  515.14
  4900.0  508.56  4920.6  509.02  4930.0  509.02  4950.0  505.05  4967.0  503.97
  4969.8  503.47  4973.0  503.97  5021.9  505.25  5028.1  506.43  5109.2  507.63
  5186.5  508.01  5207.3  509.25  5221.9  508.30  5275.0  508.83  5388.2  511.32
  5397.0  511.32  5457.3  512.27  5650.0  518.90  5928.1  531.43  6000.0  533.46
#Mann=10,-1,0
  4250.0    0.05       0  4626.1     0.1       0  4716.1    0.05       0
  4920.6    0.12       0  4967.0    0.07       0  4973.0    0.12       0
  5109.2     0.1       0  5275.0    0.05       0  5388.2    0.08       0
  5397.0     0.1       0
Bank Sta=4967,4973
Exp/Cntr=0.3,0.1

Type RM Length L Ch R = 1,1949,492,492,492
BEGIN DESCRIPTION:
UNT 005 IN LACR 3.0
END DESCRIPTION:
XS GIS Cut Line= 3
      2149937.72     13214896.85      2150637.72     13214896.85
      2151437.73     13214146.84
#Sta/Elev= 30
  4300.0  522.28  4439.3  517.41  4543.7  513.84  4750.0  507.87  4920.0  506.63
  4941.7  505.23  4950.0  502.89  5003.4  502.26  5004.1  500.98  5006.8  500.48
  5010.1  500.98  5013.9  503.25  5049.6  502.43  5056.0  503.76  5063.7  502.56
  5077.9  503.41  5092.1  502.43  5106.2  505.15  5127.2  504.76  5177.1  508.01
  5195.9  507.60  5335.8  510.89  5357.5  511.86  5452.6  513.42  5721.7  522.74
  5905.4  531.00  5919.5  532.94  5941.0  532.91  6073.4  539.23  6096.6  539.83
#Mann=11,-1,0
  4300.0     0.1       0  4439.3    0.05       0  4543.7     0.1       0
  4941.7    0.12       0  5004.1    0.07       0  5010.1    0.12       0
  5056.0    0.05       0  5195.9     0.1       0  5335.8    0.05       0
  5357.5     0.1       0  6073.4    0.05       0
Bank Sta=5004.1,5010.1
Exp/Cntr=0.3,0.1

Type RM Length L Ch R = 1,1457,619,619,619
BEGIN DESCRIPTION:
UNT 005 IN LACR 2.0
END DESCRIPTION:
XS GIS Cut Line= 3
      2150137.74     13215246.86      2150787.72     13215296.86
      2151587.77     13215046.84
#Sta/Elev= 30
  4348.1  518.70  4628.9  507.48  4829.5  503.18  4899.7  504.20  4919.8  503.35
  4929.8  500.52  4939.8  502.17  4956.9  499.28  4959.6  498.78  4962.9  499.28
  4990.0  499.57  5002.6  500.59  5010.5  503.61  5020.7  503.33  5041.9  505.58
  5104.8  506.04  5189.1  508.73  5230.5  509.02  5281.3  511.61  5319.0  511.48
  5511.8  518.51  5597.2  521.78  5660.0  523.03  5692.0  525.20  5724.5  525.75
  5733.4  527.23  5764.8  528.71  5796.2  529.07  5816.7  530.87  5838.2  530.81
#Mann=5,-1,0
  4348.1    0.05       0  4956.9    0.03       0  4962.9    0.05       0
  5020.7     0.1       0  5511.8    0.05       0
Bank Sta=4956.9,4962.9
Exp/Cntr=0.3,0.1

Type RM Length L Ch R = 1,838,373,373,373
BEGIN DESCRIPTION:
Mapping XS 86f485aa
END DESCRIPTION:
XS GIS Cut Line= 5
      2150173.03     13215394.97      2150337.97     13215724.85
      2150954.29     13215881.10      2151397.00     13215603.32
      2151464.86     13215560.90
#Sta/Elev= 30
  4476.7  514.67  4603.8  510.47  4765.3  505.35  4793.2  505.28  4838.0  502.66
  4872.5  502.40  4947.2  499.61  4959.6  499.08  4976.4  496.42  4979.1  495.92
  4982.4  496.42  4989.7  496.42  5000.6  499.90  5020.6  500.33  5134.1  501.38
  5299.0  500.95  5359.1  501.31  5381.7  500.33  5423.0  503.58  5531.5  507.19
  5544.4  506.40  5568.0  508.17  5697.9  511.19  5741.3  513.48  5814.3  513.94
  5856.7  515.09  5872.0  516.44  5886.8  515.94  6016.6  519.06  6084.0  519.69
#Mann=6,-1,0
  4476.7    0.05       0  4603.8     0.1       0  4947.2    0.05       0
  4976.4    0.03       0  4982.4    0.05       0  5299.0     0.1       0
Bank Sta=4976.4,4982.4
Exp/Cntr=0.3,0.1

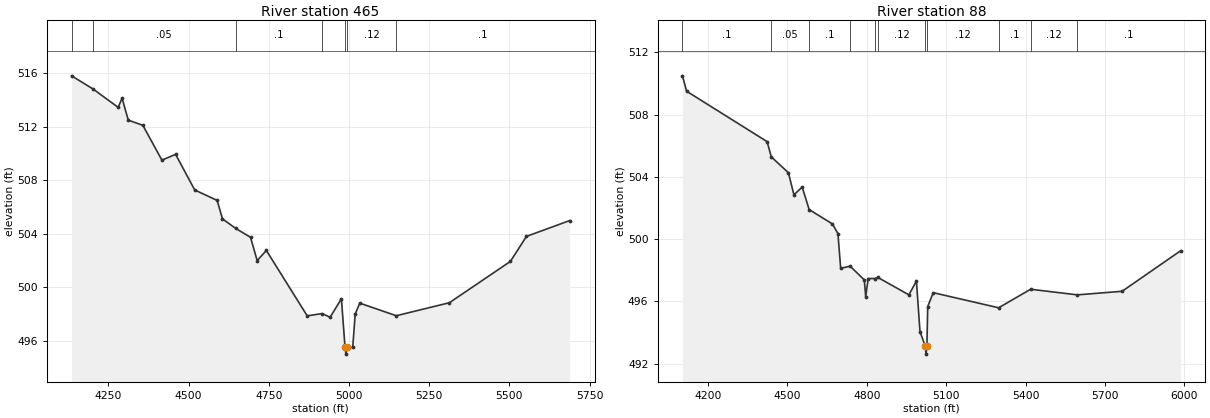
Type RM Length L Ch R = 1,465,377,377,377
BEGIN DESCRIPTION:
Mapping XS ae433219
END DESCRIPTION:
XS GIS Cut Line= 4
      2149906.35     13215318.32      2150073.02     13215846.12
      2150427.19     13216144.73      2150961.92     13216179.45
#Sta/Elev= 30
  4135.1  515.81  4201.9  514.83  4280.4  513.45  4292.6  514.14  4311.8  512.50
  4357.3  512.11  4416.7  509.51  4459.5  509.94  4518.9  507.28  4588.9  506.50
  4605.5  505.12  4646.4  504.41  4693.0  503.74  4713.7  502.00  4742.3  502.76
  4869.7  497.87  4915.8  498.04  4941.2  497.77  4976.3  499.15  4987.6  495.51
  4990.4  495.01  4993.6  495.51  5011.5  495.51  5019.2  498.00  5033.5  498.82
  5147.4  497.88  5312.7  498.85  5503.1  501.94  5553.2  503.81  5687.7  504.99
#Mann=7,-1,0
  4135.1     0.1       0  4201.9    0.05       0  4646.4     0.1       0
  4915.8    0.12       0  4987.6    0.07       0  4993.6    0.12       0
  5147.4     0.1       0
Bank Sta=4987.6,4993.6
Exp/Cntr=0.3,0.1

Type RM Length L Ch R = 1,88,0,0,0
BEGIN DESCRIPTION:
UNT 005 IN LACR 1.0
END DESCRIPTION:
XS GIS Cut Line= 4
      2149677.20     13215311.43      2149871.63     13216005.84
      2150121.63     13216346.12      2150857.77     13216394.73
#Sta/Elev= 30
  4103.9  510.50  4119.6  509.51  4423.7  506.27  4439.4  505.29  4504.1  504.27
  4524.9  502.85  4556.1  503.35  4582.5  501.90  4670.3  500.98  4691.1  500.36
  4701.5  498.13  4737.5  498.26  4790.8  497.38  4796.0  496.29  4805.3  497.47
  4832.2  497.47  4841.8  497.54  4959.3  496.42  4987.6  497.31  5001.0  494.06
  5021.1  493.11  5023.8  492.61  5027.1  493.11  5030.3  495.67  5051.1  496.56
  5298.0  495.59  5418.9  496.78  5595.4  496.42  5764.5  496.65  5985.0  499.25
#Mann=11,-1,0
  4103.9     0.1       0  4439.4    0.05       0  4582.5     0.1       0
  4737.5    0.12       0  4832.2     0.1       0  4841.8    0.12       0
  5021.1    0.07       0  5027.1    0.12       0  5298.0     0.1       0
  5418.9    0.12       0  5595.4     0.1       0
Bank Sta=5021.1,5027.1
Exp/Cntr=0.3,0.1

Chan Stop Cuts=-1