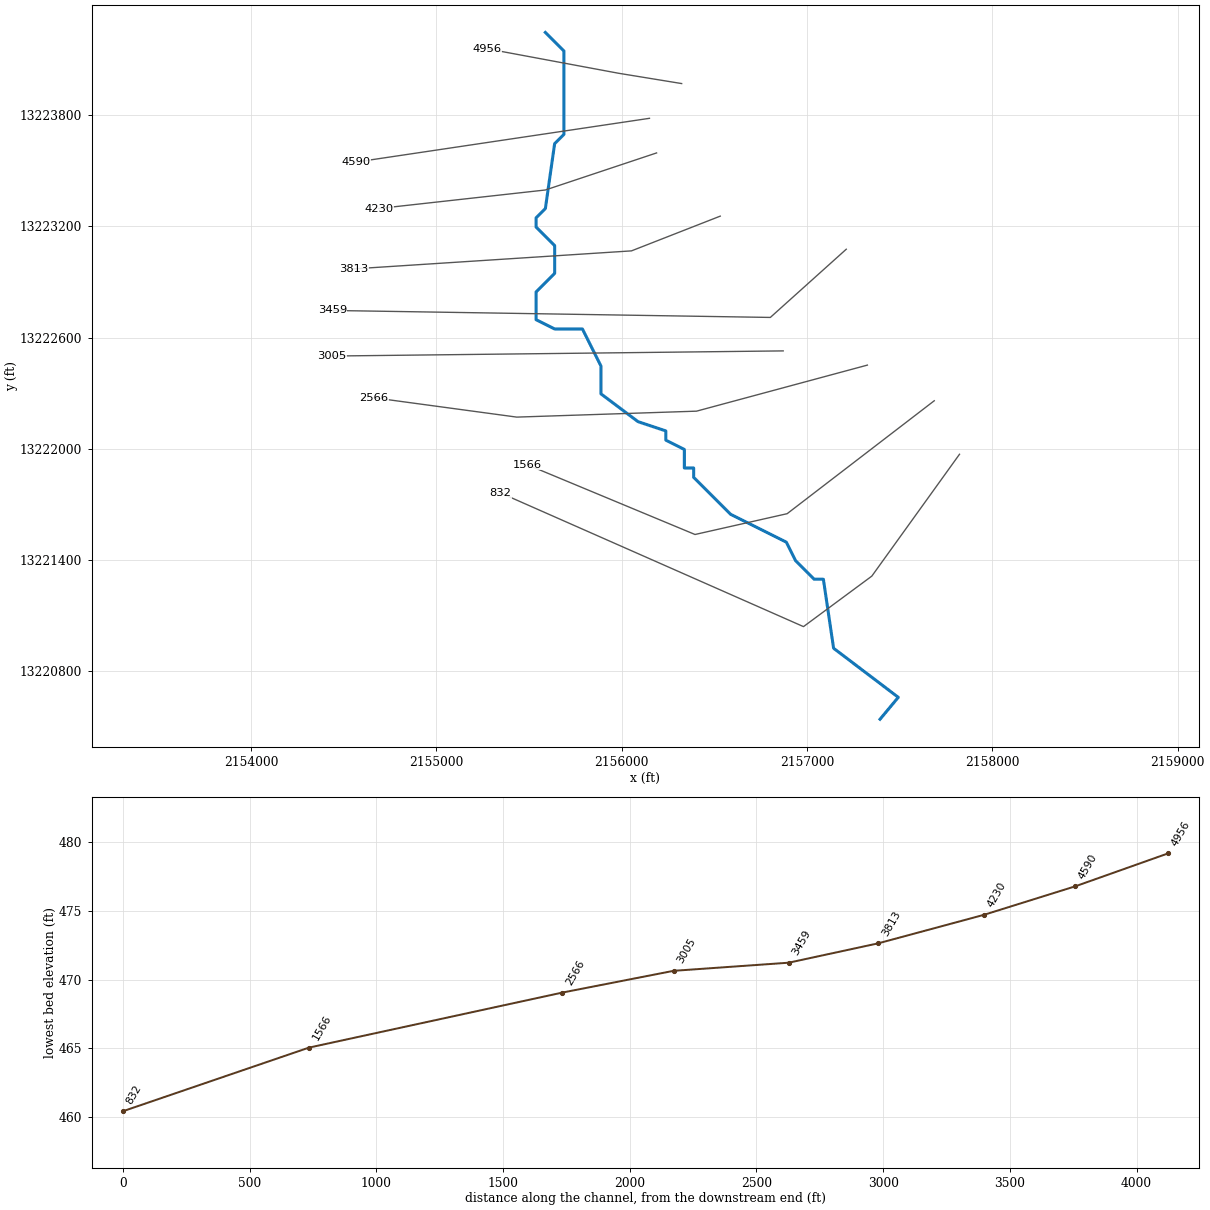
--- UNT 006 IN LACR.prj (project) ---

Proj Title=UNT 006 IN LACR Base Level Engineering
Current Plan=p01
Default Exp/Contr=0.3,0.1
English Units
Geom File=g01
Flow File=f01
Plan File=p01
Y Axis Title=Elevation
X Axis Title(PF)=Main Channel Distance
X Axis Title(XS)=Station
BEGIN DESCRIPTION:
UNT 006 IN LACR
END DESCRIPTION:
DSS Export Rating Curves= 0
DSS Export Rating Curve Sorted= 0
DSS Export Volume Flow Curves= 0
DXF OffsetX= 0
DXF OffsetY= 0
DXF ScaleX= 1
DXF ScaleY= 10

--- UNT 006 IN LACR.p01 (plan) ---

Plan Title=Multiple Run
Short Identifier=Multiple
Geom File=g01
Flow File=f01
Subcritical Flow
K Sum by GR= 0
Std Step Tol= 0.01
Critical Tol= 0.01
Num of Std Step Trials= 20
Max Error Tol= 0.3
Flow Tol Ratio= 0.001
Split Flow NTrial= 30
Split Flow Tol= 0.02
Split Flow Ratio= 0.02
Log Output Level= 0
Friction Slope Method= 1
Unsteady Friction Slope Method= 2
Unsteady Bridges Friction Slope Method= 1
Parabolic Critical Depth
Global Vel Dist=  1 , 1 , 1
Global Log Level= 0
CheckData=True
Encroach Param= -1, 0, 0, 0
BEGIN DESCRIPTION:
Multiple Run
END DESCRIPTION:

--- UNT 006 IN LACR.f01 (steady flow) ---

Flow Title=Multiple
Program Version=4.10
Number of Profiles= 7
Profile Names=10-year,25-year,50-year,1pct_min,100-year,1pct_plu,500-year
River Rch & RM=UNT 006 IN LACR,Reach-1         ,4956
     113     152     183     162     220     297     322
River Rch & RM=UNT 006 IN LACR,Reach-1         ,4590
     192     267     328     298     403     544     615
River Rch & RM=UNT 006 IN LACR,Reach-1         ,3813
     192     267     328     298     403     544     615
River Rch & RM=UNT 006 IN LACR,Reach-1         ,3005
     209     291     359     326     441     596     676
Boundary for River Rch & Prof#=UNT 006 IN LACR,Reach-1         , 1
Up Type= 0
Dn Type= 3
Dn Slope=0.005
Boundary for River Rch & Prof#=UNT 006 IN LACR,Reach-1         , 2
Up Type= 0
Dn Type= 3
Dn Slope=0.005
Boundary for River Rch & Prof#=UNT 006 IN LACR,Reach-1         , 3
Up Type= 0
Dn Type= 3
Dn Slope=0.005
Boundary for River Rch & Prof#=UNT 006 IN LACR,Reach-1         , 4
Up Type= 0
Dn Type= 3
Dn Slope=0.005
Boundary for River Rch & Prof#=UNT 006 IN LACR,Reach-1         , 5
Up Type= 0
Dn Type= 3
Dn Slope=0.005
Boundary for River Rch & Prof#=UNT 006 IN LACR,Reach-1         , 6
Up Type= 0
Dn Type= 3
Dn Slope=0.005
Boundary for River Rch & Prof#=UNT 006 IN LACR,Reach-1         , 7
Up Type= 0
Dn Type= 3
Dn Slope=0.005
DSS Import GetInterval= 0
DSS Import GetPeak= 0
DSS Import FillOption= 0

--- UNT 006 IN LACR.g01 (geometry) ---

Geom Title=Existing Conditions
Program Version=4.10

River Reach=UNT 006 IN LACR ,Reach-1
Reach XY= 30
      2155587.72     13224246.85      2155687.72     13224146.86
      2155687.72     13223696.85      2155637.72     13223646.86
      2155587.72     13223296.85      2155537.72     13223246.85
      2155537.72     13223196.85      2155637.72     13223096.85
      2155637.72     13222946.85      2155537.72     13222846.86
      2155537.72     13222696.85      2155637.72     13222646.86
      2155787.72     13222646.86      2155887.72     13222446.85
      2155887.72     13222296.85      2156087.72     13222146.85
      2156237.72     13222096.85      2156237.72     13222046.85
      2156337.72     13221996.86      2156337.72     13221896.85
      2156387.72     13221896.85      2156387.72     13221846.86
      2156587.72     13221646.85      2156887.72     13221496.86
      2156937.72     13221396.85      2157037.72     13221296.85
      2157087.72     13221296.85       2157142.9      13220924.2
      2157491.91     13220659.53      2157393.41     13220541.16

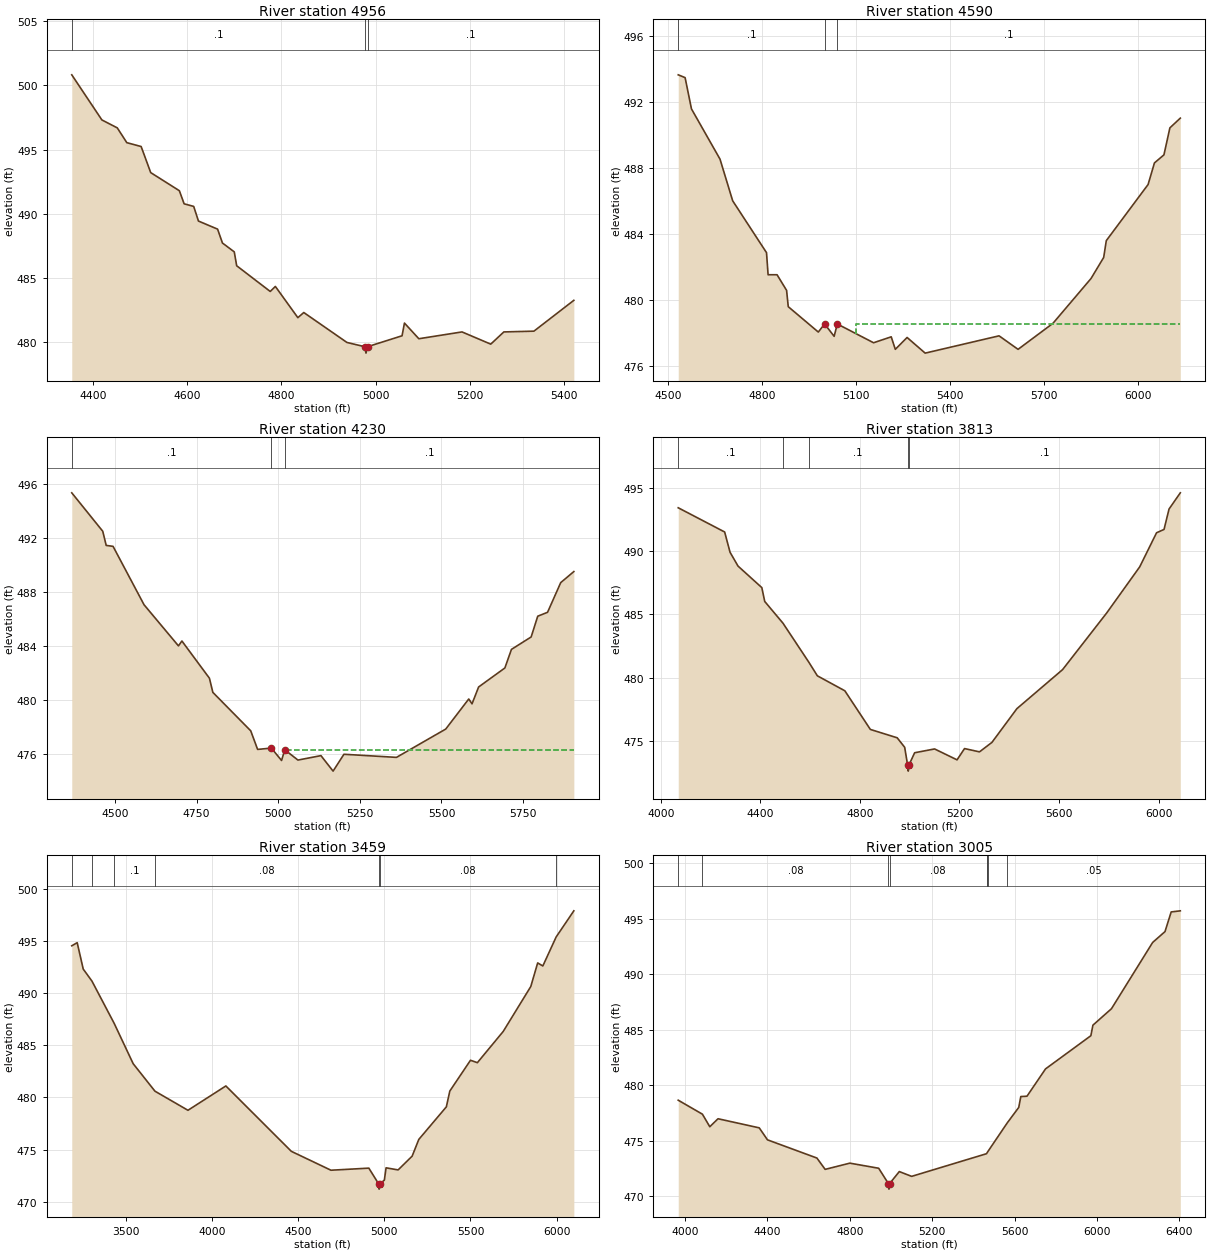
Type RM Length L Ch R = 1 ,4956    ,366,366,366
BEGIN DESCRIPTION:
UNT 006 IN LACR 6.0
END DESCRIPTION:
XS GIS Cut Line= 3
      2156323.04     13223971.12      2155982.74     13224026.68
      2155274.43     13224158.62
#Sta/Elev= 30
  4355.1  500.82    4419  497.31  4451.7  496.69  4471.9  495.54  4502.3  495.24
  4522.6  493.21  4583.4   491.8  4593.5  490.78  4613.8  490.58  4623.9  489.44
  4664.5  488.81  4674.8  487.73  4699.9  487.04    4705  485.96  4776.2  483.96
  4787.1  484.35  4834.8  481.92  4847.4  482.32    4939  479.99  4976.7  479.66
  4979.4  479.16  4982.7  479.66  5055.9  480.51    5061   481.5  5091.5  480.28
  5183.1  480.81  5244.1  479.86  5271.9  480.81  5335.7  480.87  5420.4  483.27
#Mann= 3 ,-1 , 0
  4355.1      .1       0  4976.7     .07       0  4982.7      .1       0
Bank Sta=4976.7,4982.7
XS Rating Curve= 0 ,0
Exp/Cntr=0.3,0.1

Type RM Length L Ch R = 1 ,4590    ,360,360,360
BEGIN DESCRIPTION:
Mapping XS 184a4fe2
END DESCRIPTION:
XS GIS Cut Line= 2
      2156149.42     13223783.62      2154566.12     13223547.52
#Sta/Elev= 30
  4533.2  493.67  4555.1   493.5  4575.4   491.6  4666.4  488.55  4706.8  486.02
  4814.7  482.87  4819.7  481.53  4848.3  481.53  4878.7  480.58    4884  479.59
  4979.8  478.05    5000  478.54  5030.3  477.79  5040.4  478.54    5156   477.4
  5212.3  477.76  5225.3     477  5262.9  477.72  5320.5  476.77  5556.1  477.82
  5616.7     477    5728  478.58  5849.3   481.3  5889.7  482.58    5898   483.6
  6031.3  487.01  6051.5  488.32  6081.8  488.81  6100.8  490.45    6134  491.04
#Mann= 3 , 0 , 0
  4533.2      .1       0    5000     .07       0  5040.4      .1       0
#XS Ineff= 2 , 0
                         5100.57          478.55
Permanent Ineff=
       F       F
Bank Sta=5000,5040.4
XS Rating Curve= 0 ,0
Exp/Cntr=0.3,0.1

Type RM Length L Ch R = 1 ,4230    ,417,417,417
BEGIN DESCRIPTION:
UNT 006 IN LACR 5.0
END DESCRIPTION:
XS GIS Cut Line= 3
      2156187.76     13223596.87      2155587.72     13223396.85
      2154687.76     13223296.86
#Sta/Elev= 30
  4367.5  495.34  4462.4  492.49    4473  491.44    4494  491.37  4588.9  487.04
  4694.3  483.99  4704.9  484.35  4789.2  481.59  4799.7  480.54  4915.7  477.69
  4936.8  476.31  4978.9  476.41  5010.1  475.49  5020.1  476.28  5060.4  475.52
  5130.8  475.85    5168   474.7  5201.2  475.95  5362.2  475.72  5513.1  477.82
  5583.6  480.05  5593.6  479.69  5613.8  480.94  5694.2  482.35  5714.4  483.73
  5774.7  484.65  5794.9  486.19    5825  486.48  5865.3  488.68  5905.5   489.5
#Mann= 3 , 0 , 0
  4367.5      .1       0  4978.9     .07       0  5020.1      .1       0
#XS Ineff= 2 , 0
                         5029.43          476.23
Permanent Ineff=
       F       F
Bank Sta=4978.9,5020.1
XS Rating Curve= 0 ,0
Exp/Cntr=0.3,0.1

Type RM Length L Ch R = 1 ,3813    ,354,354,354
BEGIN DESCRIPTION:
UNT 006 IN LACR 4.0
END DESCRIPTION:
XS GIS Cut Line= 3
      2156531.37     13223255.85      2156052.19     13223068.34
       2154552.5     13222971.14
#Sta/Elev= 30
  4070.1  493.41  4256.6   491.5  4278.3   489.9  4310.3  488.81    4406  487.11
  4417.6  486.02  4491.1   484.3  4594.7  481.23  4629.2  480.15  4739.5  478.97
  4842.1  475.92  4949.9  475.26    4980  474.51  4991.6  473.13  4994.3  472.63
  4997.6  473.13    5020  474.08  5100.2  474.38  5190.4  473.52  5220.5  474.41
  5280.6  474.15  5330.7   474.9  5430.9  477.56  5614.5  480.64  5791.7  485.11
  5924.4  488.75  5992.1  491.44  6022.1   491.7  6042.2  493.31  6087.5  494.59
#Mann= 5 ,-1 , 0
  4070.1      .1       0  4491.1     .05       0  4594.7      .1       0
  4991.6     .07       0  4997.6      .1       0
Bank Sta=4991.6,4997.6
XS Rating Curve= 0 ,0
Exp/Cntr=0.3,0.1

Type RM Length L Ch R = 1 ,3459    ,454,454,454
BEGIN DESCRIPTION:
UNT 006 IN LACR 3.0
END DESCRIPTION:
XS GIS Cut Line= 3
      2157211.23     13223077.27      2156801.51     13222709.22
      2154437.76     13222746.85
#Sta/Elev= 30
  3185.3  494.52  3216.8  494.82  3251.9  492.29  3302.5  491.14    3431  487.11
  3541.9  483.23  3668.2   480.6  3859.9  478.77  4079.9   481.1  4459.9  474.84
    4690  473.03    4910  473.23    4967  471.72  4969.7  471.22    4973  471.72
    5000  472.08    5010  473.26    5080  473.06  5161.4  474.38    5200  475.98
    5360   479.1    5380  480.61  5500.1  483.56  5540.1  483.33  5690.1  486.32
  5850.1  490.62  5890.1  492.88  5920.1  492.59  5997.5  495.37  6100.1  497.87
#Mann= 7 ,-1 , 0
  3185.3     .05       0  3302.5     .08       0    3431      .1       0
  3668.2     .08       0    4967     .07       0    4973     .08       0
  5997.5      .1       0
Bank Sta=4967,4973
XS Rating Curve= 0 ,0
Exp/Cntr=0.3,0.1

Type RM Length L Ch R = 1 ,3005    ,439,439,439
BEGIN DESCRIPTION:
UNT 006 IN LACR 2.0
END DESCRIPTION:
XS GIS Cut Line= 2
      2156870.95     13222528.67      2154433.41     13222500.89
#Sta/Elev= 30
  3966.7  478.64  4084.2  477.38  4119.9  476.25  4159.9  476.97    4360  476.15
    4400  475.07    4640  473.43    4680  472.41    4800  472.97    4940  472.51
    4987  471.13  4989.7  470.63    4993  471.13    5040  472.21    5100  471.78
  5463.4  473.82  5465.8  473.89  5470.3  474.02  5563.9  476.59    5620  477.99
    5630  478.97    5660     479    5750  481.46  5970.1  484.45  5980.1   485.4
  6070.1  486.88  6270.1  492.85  6330.1  493.83  6360.1   495.6  6404.4   495.7
#Mann= 8 ,-1 , 0
  3966.7      .1       0  4084.2     .08       0    4987     .07       0
    4993     .08       0  5463.4      .1       0  5465.8     .05       0
  5470.3     .08       0  5563.9     .05       0
Bank Sta=4987,4993
XS Rating Curve= 0 ,0
Exp/Cntr=0.3,0.1

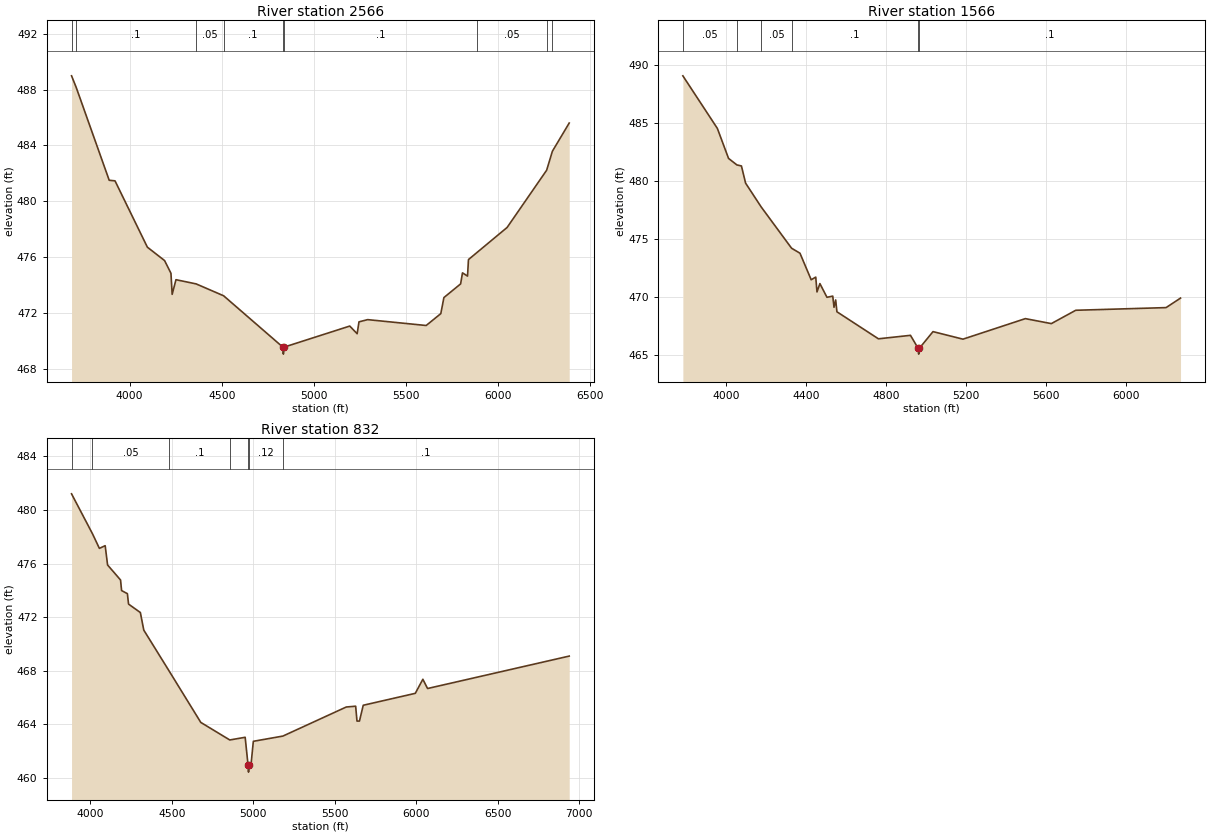
Type RM Length L Ch R = 1 ,2566    ,1000,1000,1000
BEGIN DESCRIPTION:
Mapping XS 5855d592
END DESCRIPTION:
XS GIS Cut Line= 4
      2157325.19     13222452.03      2156403.19     13222203.49
       2155433.1     13222171.42      2154663.45     13222275.64
#Sta/Elev= 30
  3684.7  488.98  3709.7  488.16  3889.2   481.5  3920.7  481.46  4096.4  476.71
  4189.8  475.75  4224.5  474.84    4231  473.33  4251.7  474.38    4361  474.08
  4510.3  473.23  4832.2  469.55  4834.9  469.05  4838.2  469.55  5195.4  471.06
  5235.4  470.51  5245.4  471.36  5292.4  471.52  5610.2   471.1  5689.7  471.95
  5706.5   473.1  5797.3  474.08  5807.4  474.87  5834.8  474.64  5839.9  475.82
  5888.1  476.35  6049.6  478.12  6264.4  482.22  6295.6  483.58  6386.9   485.6
#Mann= 9 ,-1 , 0
  3684.7     .05       0  3709.7      .1       0    4361     .05       0
  4510.3      .1       0  4832.2     .07       0  4838.2      .1       0
  5888.1     .05       0  6264.4      .1       0  6295.6     .05       0
Bank Sta=4832.2,4838.2
XS Rating Curve= 0 ,0
Exp/Cntr=0.3,0.1

Type RM Length L Ch R = 1 ,1566    ,734,734,734
BEGIN DESCRIPTION:
Mapping XS d6c65fc6
END DESCRIPTION:
XS GIS Cut Line= 4
      2157685.98     13222259.63      2156892.24      13221650.3
      2156395.17     13221538.05      2155491.01     13221914.12
#Sta/Elev= 30
  3783.6  489.04  3956.1  484.51  4012.2  481.92  4053.8  481.36  4076.6  481.27
  4097.4  479.79  4175.3  477.74  4327.4  474.18  4369.4  473.75  4425.5  471.46
  4448.3  471.69  4454.6  470.41  4469.1  471.13  4504.4  469.95  4533.4  470.05
  4539.7  469.09    4548  469.72  4554.3   468.7  4761.9  466.37  4922.2  466.67
  4960.5  465.55  4963.3  465.05  4966.5  465.55  5034.9  466.99  5184.7  466.34
  5496.9  468.11  5626.8  467.68  5748.9  468.83  6200.8  469.06  6273.1  469.88
#Mann= 6 ,-1 , 0
  3783.6     .05       0  4053.8      .1       0  4175.3     .05       0
  4327.4      .1       0  4960.5     .07       0  4966.5      .1       0
Bank Sta=4960.5,4966.5
XS Rating Curve= 0 ,0
Exp/Cntr=0.3,0.1

Type RM Length L Ch R = 1 ,832     ,0,0,0
BEGIN DESCRIPTION:
UNT 006 IN LACR 1.0
END DESCRIPTION:
XS GIS Cut Line= 4
      2157822.25     13221970.99      2157349.23     13221313.57
      2156980.43     13221040.98      2155345.67      13221762.2
#Sta/Elev= 30
  3883.9   481.2  4012.4  478.22  4054.8  477.13  4090.4  477.33  4105.1  475.89
  4184.7  474.77  4191.1  473.98  4226.7  473.75  4233.9  472.97  4306.4  472.34
  4327.3  471.03  4484.4  467.95  4677.4  464.14  4855.3  462.83  4949.8  463.03
  4967.7  460.93  4970.4  460.43  4973.7  460.93  4985.3  460.93  4999.9  462.73
  5181.3  463.12  5570.5  465.29  5628.1  465.35  5636.3  464.24  5651.4  464.24
  5674.7  465.42  5994.2  466.31  6040.7  467.36  6069.6  466.67  6939.2  469.09
#Mann= 7 ,-1 , 0
  3883.9     .08       0  4012.4     .05       0  4484.4      .1       0
  4855.3     .12       0  4967.7     .07       0  4973.7     .12       0
  5181.3      .1       0
Bank Sta=4967.7,4973.7
XS Rating Curve= 0 ,0
Exp/Cntr=0.3,0.1

Chan Stop Cuts=-1
Use User Specified Reach Order=0
Composite Channel Slope=5