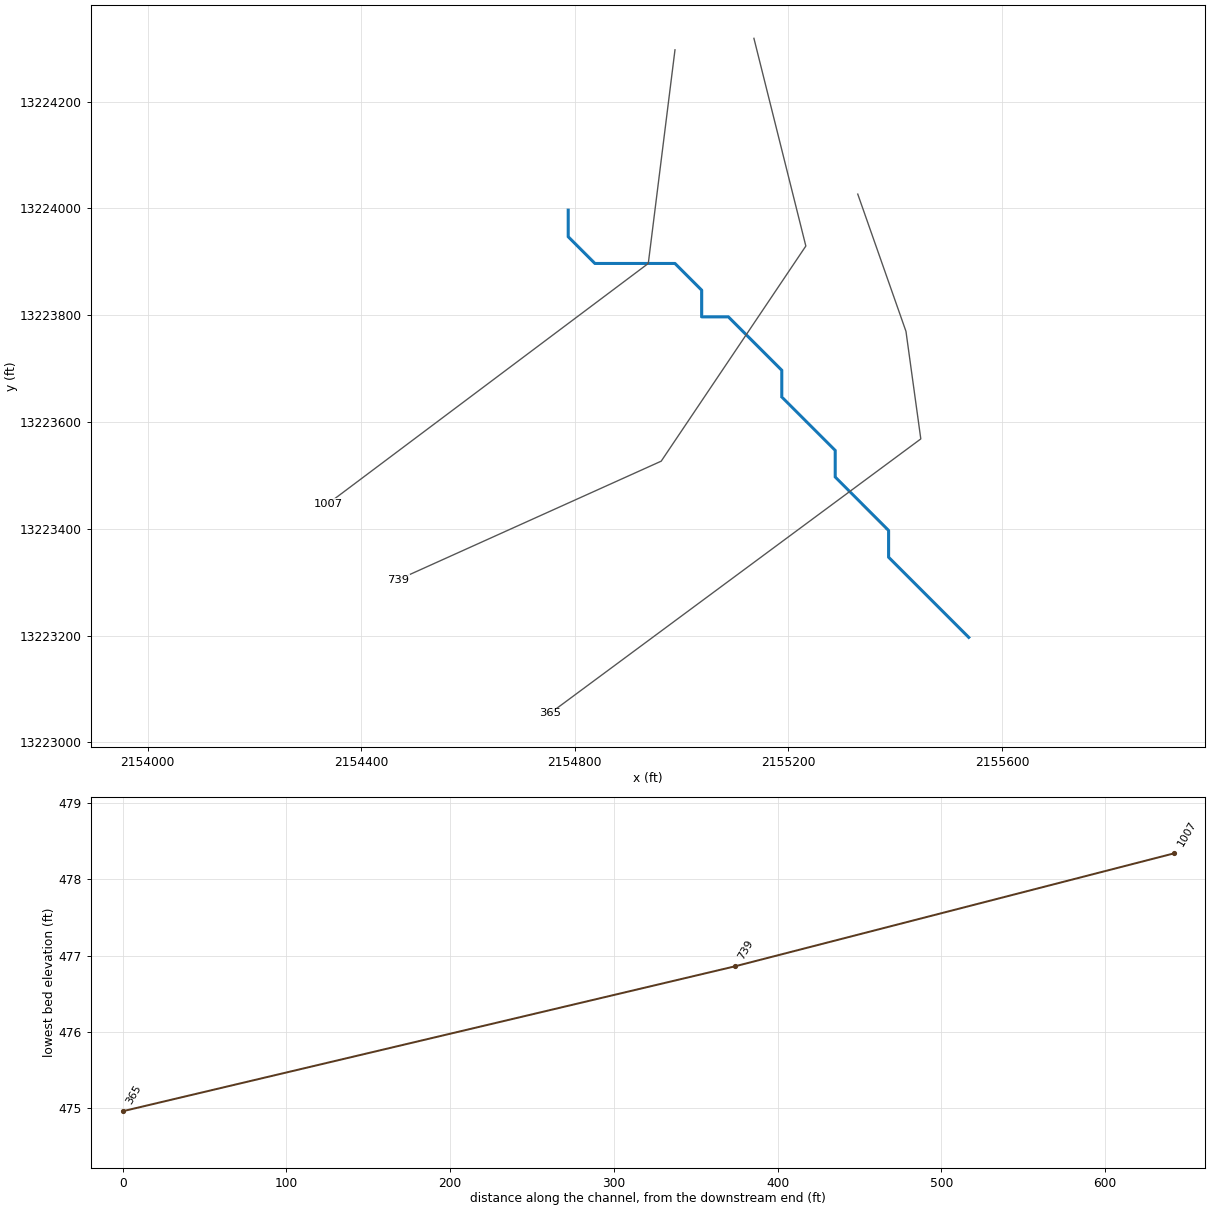
--- UNT 007 IN LACR.prj (project) ---

Proj Title=UNT 007 IN LACR Base Level Engineering
Current Plan=p01
Default Exp/Contr=0.3,0.1
English Units
Geom File=g01
Flow File=f01
Plan File=p01
BEGIN DESCRIPTION:
UNT 007 IN LACR
END DESCRIPTION:

--- UNT 007 IN LACR.p01 (plan) ---

Plan Title=Multiple Run
Short Identifier=Multiple
Geom File=g01
Flow File=f01
Subcritical Flow
K Sum by GR= 0
Std Step Tol= 0.01
Critical Tol= 0.01
Num of Std Step Trials= 20
Max Error Tol= 0.3
Flow Tol Ratio= 0.001
Split Flow NTrial= 30
Split Flow Tol= 0.02
Split Flow Ratio= 0.02
Log Output Level= 0
Friction Slope Method= 1
Unsteady Friction Slope Method= 2
Unsteady Bridges Friction Slope Method= 1
Parabolic Critical Depth
Global Vel Dist=  1 , 1 , 1
Global Log Level= 0
CheckData=True
Encroach Param= -1, 0, 0, 0
BEGIN DESCRIPTION:
Multiple Run
END DESCRIPTION:

--- UNT 007 IN LACR.f01 (steady flow) ---

Flow Title=Multiple
Number of Profiles=7
Profile Names=10-year,25-year,50-year,1pct_min,100-year,1pct_plu,500-year
River Rch & RM= UNT 007 IN LACR,Reach-1,1007
     110     147     178     158     213     289     313
Boundary for River Rch & Prof#=UNT 007 IN LACR,Reach-1,1
Up Type=0
Dn Type=3
Dn Slope=0.005
Boundary for River Rch & Prof#=UNT 007 IN LACR,Reach-1,2
Up Type=0
Dn Type=3
Dn Slope=0.005
Boundary for River Rch & Prof#=UNT 007 IN LACR,Reach-1,3
Up Type=0
Dn Type=3
Dn Slope=0.005
Boundary for River Rch & Prof#=UNT 007 IN LACR,Reach-1,4
Up Type=0
Dn Type=3
Dn Slope=0.005
Boundary for River Rch & Prof#=UNT 007 IN LACR,Reach-1,5
Up Type=0
Dn Type=3
Dn Slope=0.005
Boundary for River Rch & Prof#=UNT 007 IN LACR,Reach-1,6
Up Type=0
Dn Type=3
Dn Slope=0.005
Boundary for River Rch & Prof#=UNT 007 IN LACR,Reach-1,7
Up Type=0
Dn Type=3
Dn Slope=0.005

--- UNT 007 IN LACR.g01 (geometry) ---

Geom Title=Existing Conditions

River Reach=UNT 007 IN LACR,Reach-1
Reach XY= 21
      2154787.72     13223996.86      2154787.72     13223946.85
      2154837.72     13223896.85      2154887.72     13223896.85
      2154937.72     13223896.85      2154987.72     13223896.85
      2155037.72     13223846.85      2155037.72     13223796.86
      2155087.72     13223796.86      2155137.72     13223746.85
      2155187.72     13223696.85      2155187.72     13223646.86
      2155237.72     13223596.85      2155287.72     13223546.85
      2155287.72     13223496.86      2155337.72     13223446.85
      2155387.72     13223396.85      2155387.72     13223346.85
      2155437.72     13223296.85      2155487.72     13223246.85
      2155537.72     13223196.85

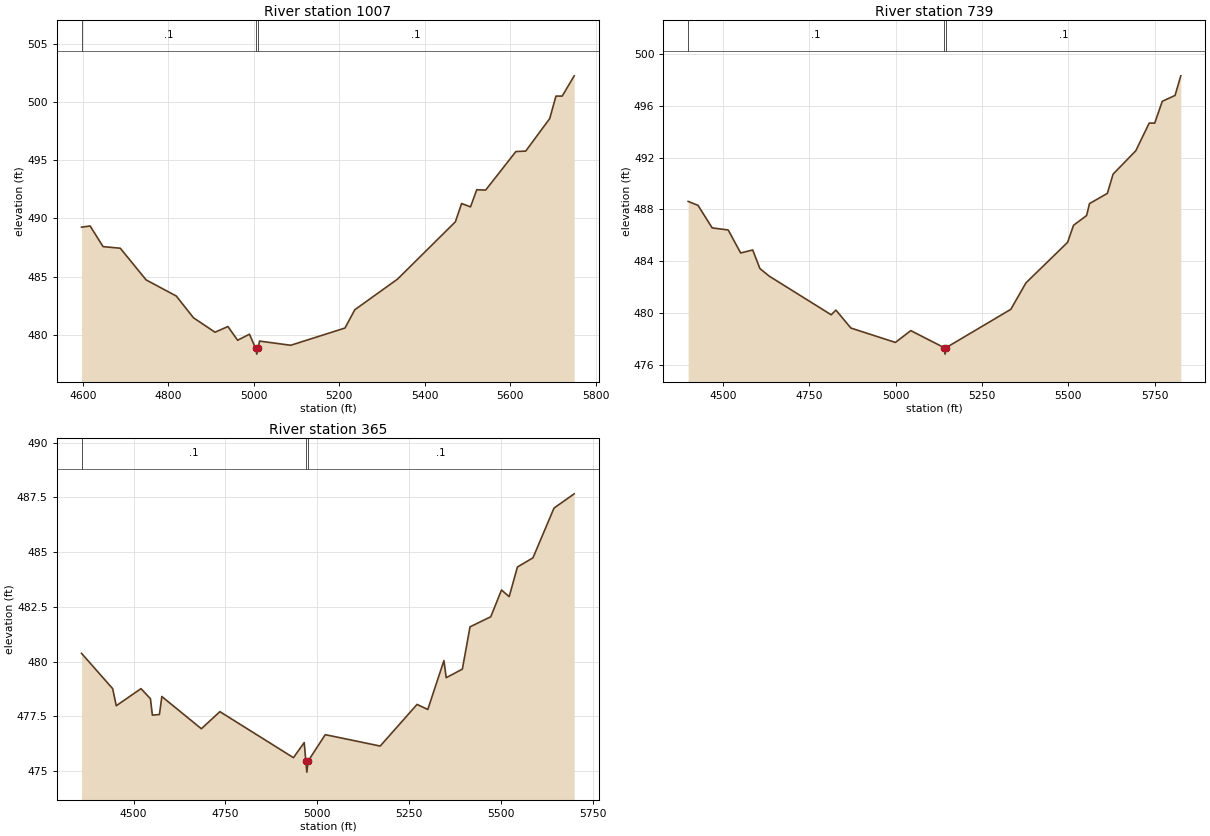
Type RM Length L Ch R = 1,1007,268,268,268
BEGIN DESCRIPTION:
UNT 007 IN LACR 1.0
END DESCRIPTION:
XS GIS Cut Line= 3
      2154987.72     13224296.84      2154937.72     13223896.85
      2154337.72     13223446.85
#Sta/Elev= 30
  4596.9  489.24  4617.0  489.34  4647.3  487.57  4687.6  487.43  4748.1  484.71
  4818.6  483.33  4858.9  481.46  4909.3  480.22  4939.5  480.71  4962.2  479.53
  4989.9  480.05  5004.3  478.84  5007.0  478.34  5010.3  478.84  5013.5  479.46
  5086.5  479.10  5213.5  480.58  5236.5  482.15  5336.5  484.78  5471.9  489.70
  5486.5  491.27  5507.3  490.98  5521.9  492.45  5542.7  492.42  5613.5  495.73
  5636.5  495.77  5692.7  498.56  5707.3  500.49  5721.9  500.49  5750.0  502.23
#Mann=3,-1,0
  4596.9     0.1       0  5004.3    0.07       0  5010.3     0.1       0
Bank Sta=5004.3,5010.3
Exp/Cntr=0.3,0.1

Type RM Length L Ch R = 1,739,374,374,374
BEGIN DESCRIPTION:
Mapping XS 78b7fc21
END DESCRIPTION:
XS GIS Cut Line= 4
      2155135.52     13224318.35      2155232.74     13223929.45
      2154961.91     13223526.68      2154468.90     13223304.47
#Sta/Elev= 30
  4399.1  488.62  4427.6  488.32  4468.8  486.58  4515.2  486.42  4551.3  484.65
  4586.2  484.88  4606.8  483.46  4633.7  482.87  4813.5  479.89  4827.2  480.25
  4870.5  478.87  4999.5  477.76  5044.1  478.67  5140.5  477.36  5143.3  476.86
  5146.5  477.36  5333.8  480.31  5377.7  482.35  5498.3  485.47  5515.4  486.78
  5553.2  487.53  5561.7  488.45  5613.5  489.24  5630.0  490.72  5695.8  492.52
  5734.6  494.65  5750.6  494.65  5772.5  496.33  5809.5  496.78  5826.1  498.29
#Mann=3,-1,0
  4399.1     0.1       0  5140.5    0.07       0  5146.5     0.1       0
Bank Sta=5140.5,5146.5
Exp/Cntr=0.3,0.1

Type RM Length L Ch R = 1,365,0,0,0
BEGIN DESCRIPTION:
UNT 007 IN LACR 2.0
END DESCRIPTION:
XS GIS Cut Line= 4
      2155329.95     13224026.72      2155420.24     13223769.73
      2155448.02     13223568.34      2154753.57     13223054.45
#Sta/Elev= 30
  4358.6  480.38  4443.2  478.77  4453.0  477.99  4520.3  478.77  4545.9  478.31
  4551.2  477.56  4570.4  477.59  4576.9  478.41  4684.4  476.94  4734.8  477.72
  4934.8  475.62  4964.1  476.31  4968.5  475.46  4971.2  474.96  4974.5  475.46
  5021.3  476.67  5170.7  476.15  5270.9  478.05  5300.1  477.82  5344.0  480.05
  5350.2  479.27  5394.1  479.66  5414.9  481.59  5471.3  482.05  5500.5  483.27
  5521.4  482.97  5543.8  484.32  5586.1  484.74  5643.3  487.01  5698.2  487.66
#Mann=3,-1,0
  4358.6     0.1       0  4968.5    0.07       0  4974.5     0.1       0
Bank Sta=4968.5,4974.5
Exp/Cntr=0.3,0.1

Chan Stop Cuts=-1