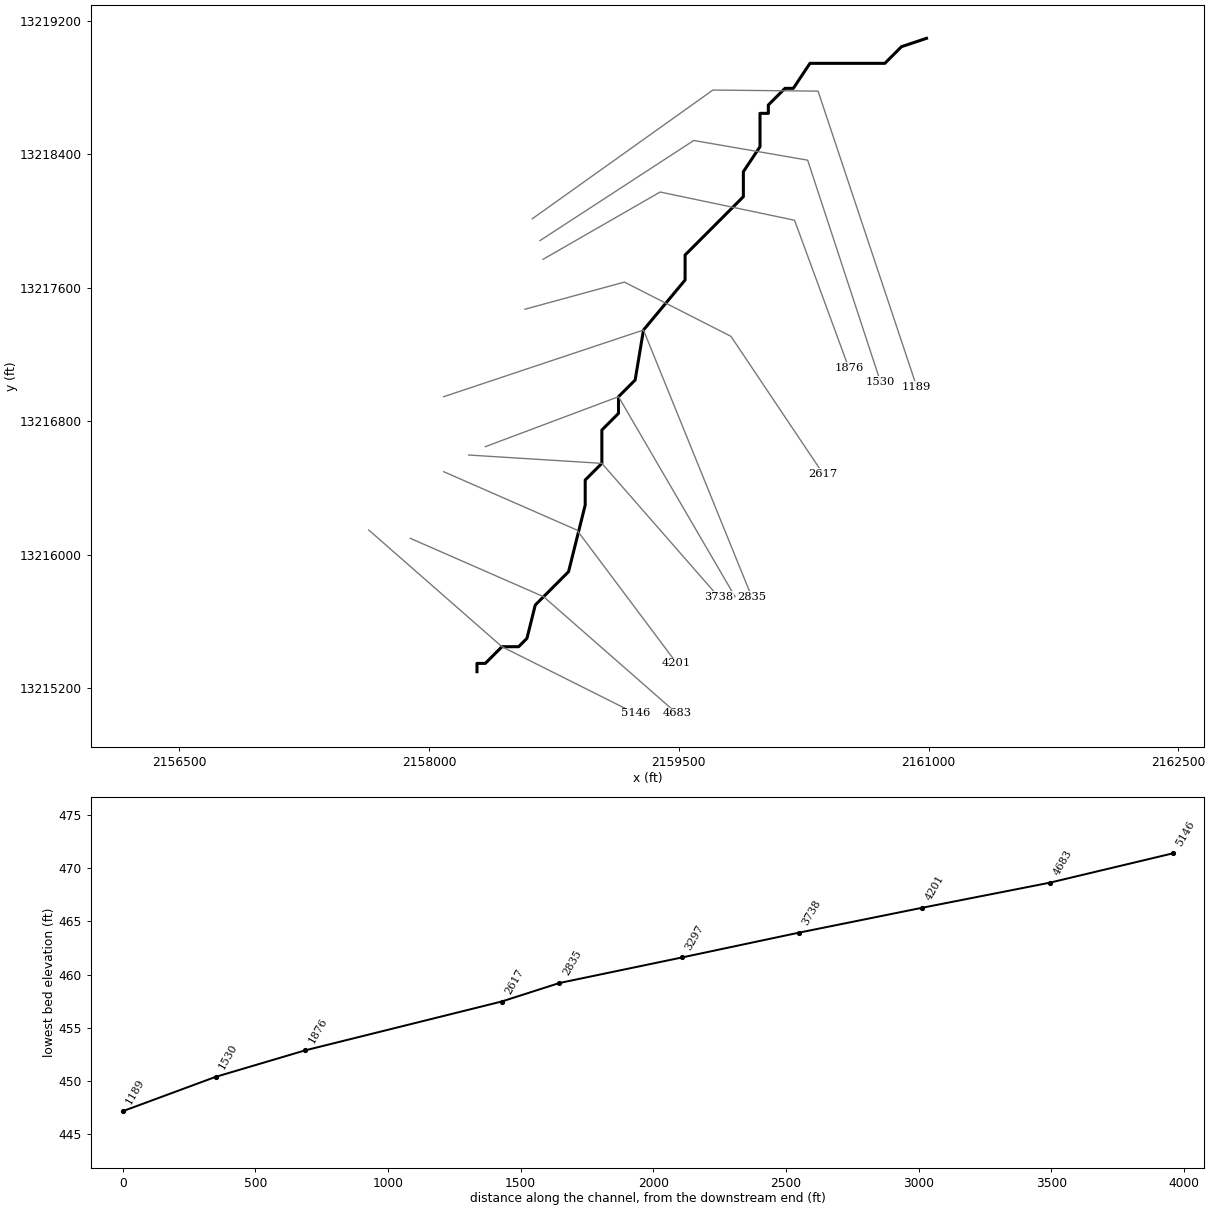
--- UNT 008 IN LACR.prj (project) ---

Proj Title=UNT 008 IN LACR Base Level Engineering
Current Plan=p01
Default Exp/Contr=0.3,0.1
English Units
Geom File=g01
Flow File=f01
Plan File=p01
Y Axis Title=Elevation
X Axis Title(PF)=Main Channel Distance
X Axis Title(XS)=Station
BEGIN DESCRIPTION:
UNT 008 IN LACR
END DESCRIPTION:
DSS Export Rating Curves= 0
DSS Export Rating Curve Sorted= 0
DSS Export Volume Flow Curves= 0
DXF OffsetX= 0
DXF OffsetY= 0
DXF ScaleX= 1
DXF ScaleY= 10

--- UNT 008 IN LACR.p01 (plan) ---

Plan Title=Multiple Run
Short Identifier=Multiple
Geom File=g01
Flow File=f01
Subcritical Flow
K Sum by GR= 0
Std Step Tol= 0.01
Critical Tol= 0.01
Num of Std Step Trials= 20
Max Error Tol= 0.3
Flow Tol Ratio= 0.001
Split Flow NTrial= 30
Split Flow Tol= 0.02
Split Flow Ratio= 0.02
Log Output Level= 0
Friction Slope Method= 1
Unsteady Friction Slope Method= 2
Unsteady Bridges Friction Slope Method= 1
Parabolic Critical Depth
Global Vel Dist=  1 , 1 , 1
Global Log Level= 0
CheckData=True
Encroach Param= -1, 0, 0, 0
BEGIN DESCRIPTION:
Multiple Run
END DESCRIPTION:

--- UNT 008 IN LACR.f01 (steady flow) ---

Flow Title=Multiple
Program Version=4.10
Number of Profiles= 7
Profile Names=10-year,25-year,50-year,1pct_min,100-year,1pct_plu,500-year
River Rch & RM=UNT 008 IN LACR,Reach-1         ,5146
     208     291     361     329     445     602     689
Boundary for River Rch & Prof#=UNT 008 IN LACR,Reach-1         , 1
Up Type= 0
Dn Type= 3
Dn Slope=0.007
Boundary for River Rch & Prof#=UNT 008 IN LACR,Reach-1         , 2
Up Type= 0
Dn Type= 3
Dn Slope=0.007
Boundary for River Rch & Prof#=UNT 008 IN LACR,Reach-1         , 3
Up Type= 0
Dn Type= 3
Dn Slope=0.007
Boundary for River Rch & Prof#=UNT 008 IN LACR,Reach-1         , 4
Up Type= 0
Dn Type= 3
Dn Slope=0.007
Boundary for River Rch & Prof#=UNT 008 IN LACR,Reach-1         , 5
Up Type= 0
Dn Type= 3
Dn Slope=0.007
Boundary for River Rch & Prof#=UNT 008 IN LACR,Reach-1         , 6
Up Type= 0
Dn Type= 3
Dn Slope=0.007
Boundary for River Rch & Prof#=UNT 008 IN LACR,Reach-1         , 7
Up Type= 0
Dn Type= 3
Dn Slope=0.007
DSS Import GetInterval= 0
DSS Import GetPeak= 0
DSS Import FillOption= 0

--- UNT 008 IN LACR.g01 (geometry) ---

Geom Title=Existing Conditions
Program Version=4.10

River Reach=UNT 008 IN LACR ,Reach-1
Reach XY= 30
      2158287.72     13215296.86      2158287.72     13215346.85
      2158337.72     13215346.85      2158437.72     13215446.86
      2158537.72     13215446.86      2158587.72     13215496.85
      2158637.72     13215696.85      2158837.72     13215896.85
      2158937.72     13216296.85      2158937.72     13216446.86
      2159037.72     13216546.85      2159037.72     13216746.86
      2159137.72     13216846.85      2159137.72     13216946.85
      2159237.72     13217046.85      2159287.72     13217346.85
      2159537.72     13217646.85      2159537.72     13217796.85
      2159887.72     13218146.85      2159887.72     13218296.85
      2159987.72     13218446.85      2159987.72     13218646.85
      2160037.72     13218646.85      2160037.72     13218696.85
      2160137.72     13218796.85      2160187.72     13218796.85
      2160287.72     13218946.85      2160737.72     13218946.85
      2160837.72     13219046.86      2160987.72     13219096.85

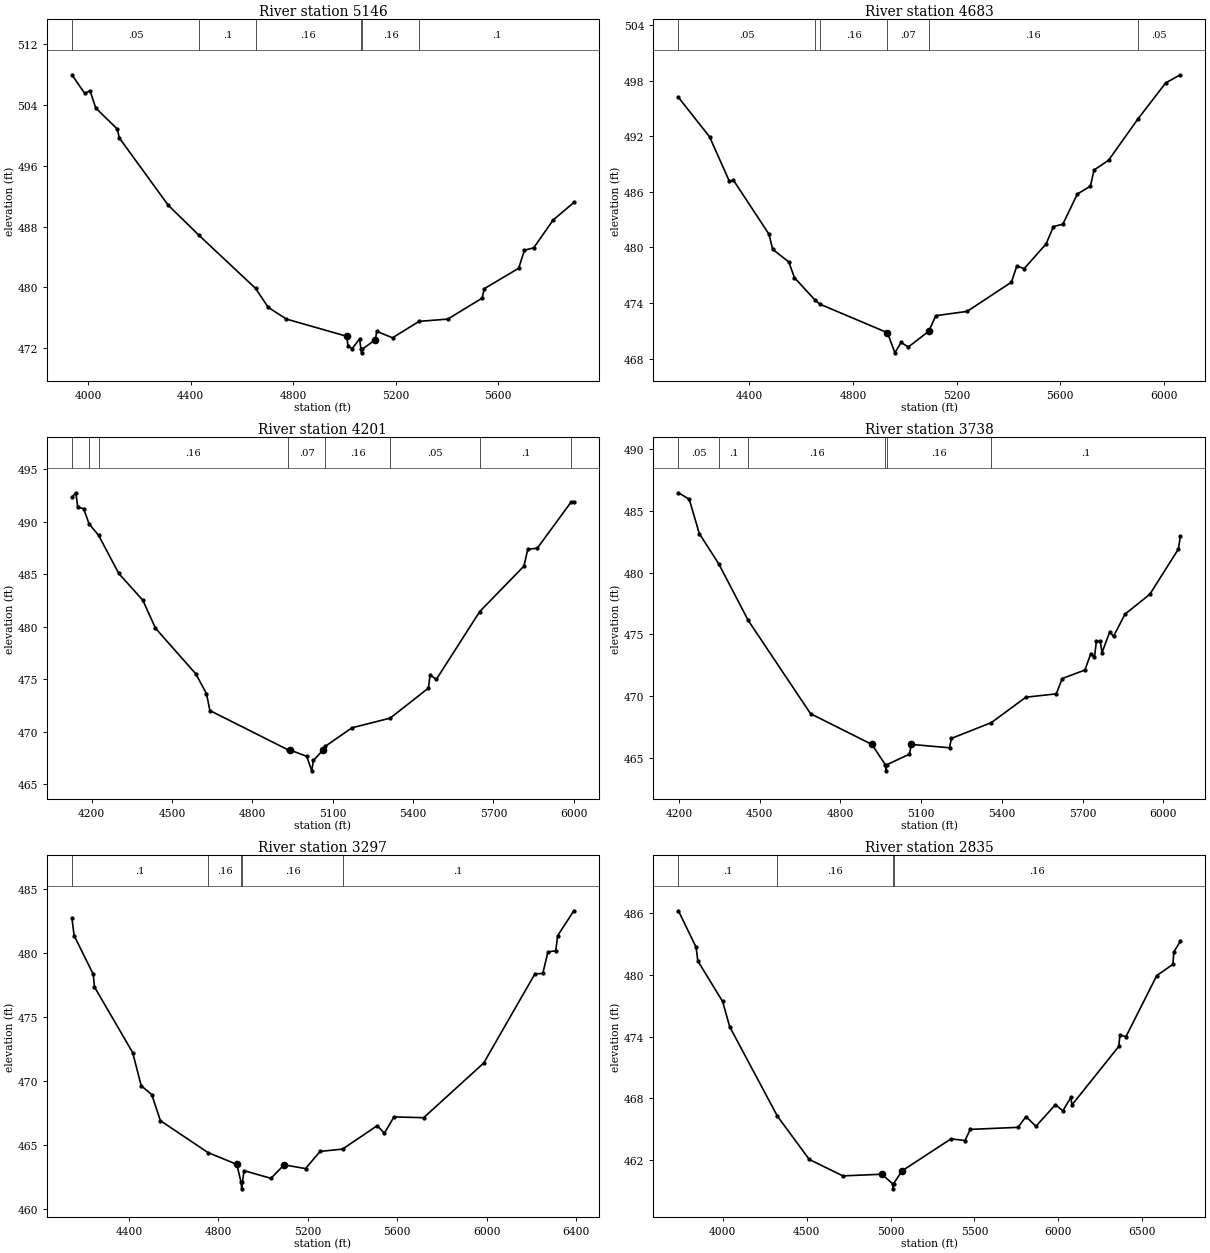
Type RM Length L Ch R = 1 ,5146    ,463,463,463
BEGIN DESCRIPTION:
UNT 008 IN LACR 7.0
END DESCRIPTION:
XS GIS Cut Line= 3
      2157637.73     13216146.85      2158437.72     13215446.86
       2159237.7     13215046.87
#Sta/Elev= 30
    3937  507.97  3986.8  505.51  4007.7  505.87  4029.5  503.61    4114  500.82
  4121.6  499.67  4312.4  490.81    4433  486.83  4653.1  479.86  4702.5  477.36
  4773.6  475.82  5008.4  473.56    5014  472.24  5030.7  471.95  5058.7  473.23
  5064.1  471.88  5066.8  471.38  5070.1  471.88  5120.2   473.1  5125.8  474.21
  5187.3  473.36  5290.7  475.52  5402.5  475.82  5536.7  478.58    5545  479.82
  5679.2  482.51  5701.6  484.88  5737.9   485.2  5813.4  488.85  5894.4  491.17
#Mann= 6 ,-1 , 0
    3937     .05       0    4433      .1       0  4653.1     .16       0
  5064.1     .07       0  5070.1     .16       0  5290.7      .1       0
Bank Sta=5008.4,5120.2
XS Rating Curve= 0 ,0
Exp/Cntr=0.3,0.1

Type RM Length L Ch R = 1 ,4683    ,482,482,482
BEGIN DESCRIPTION:
UNT 008 IN LACR 6.0
END DESCRIPTION:
XS GIS Cut Line= 3
      2157887.73     13216096.85      2158687.72     13215746.85
      2159487.71     13215046.86
#Sta/Elev= 30
  4126.8  496.19  4246.9  491.93  4323.3  487.14  4339.2  487.24  4476.1  481.43
  4490.5  479.79  4552.5  478.44  4574.3  476.74  4652.6  474.36  4672.5  473.88
  4933.3   470.8  4961.9  468.63  4985.6  469.75  5013.8  469.26  5092.5  470.96
  5120.1  472.64  5240.6   473.1  5411.4  476.25  5432.3  477.99  5460.8  477.72
  5545.3  480.38  5573.7  482.25  5609.8  482.51  5665.8  485.76  5716.1  486.61
  5730.3  488.35  5786.3   489.4  5898.5  493.82  6006.5  497.74    6063  498.62
#Mann= 6 ,-1 , 0
  4126.8     .05       0  4652.6      .1       0  4672.5     .16       0
  4933.3     .07       0  5092.5     .16       0  5898.5     .05       0
Bank Sta=4933.3,5092.5
XS Rating Curve= 0 ,0
Exp/Cntr=0.3,0.1

Type RM Length L Ch R = 1 ,4201    ,463,463,463
BEGIN DESCRIPTION:
UNT 008 IN LACR 5.0
END DESCRIPTION:
XS GIS Cut Line= 3
      2158087.73     13216496.85      2158887.72     13216146.85
      2159487.72     13215346.85
#Sta/Elev= 30
  4126.8  492.32  4141.2  492.75  4148.6  491.37  4170.4  491.24  4190.7  489.79
  4226.2   488.7  4301.4  485.07  4391.5  482.51  4438.3  479.86  4589.5  475.49
  4628.9  473.62  4641.7  472.01  4933.3  468.27  4938.8  468.27  5003.1  467.65
  5021.6  466.27  5028.1  467.26  5063.5  468.24  5071.9   468.6  5171.9  470.37
  5314.6  471.29  5457.3  474.15  5463.5  475.43  5486.5  474.97  5648.8  481.44
  5813.5  485.76  5828.1  487.37  5863.5  487.47  5990.7   491.9    6000   491.9
#Mann= 8 ,-1 , 0
  4126.8     .05       0  4190.7      .1       0  4226.2     .16       0
  4933.3     .07       0  5071.9     .16       0  5314.6     .05       0
  5648.8      .1       0  5990.7     .05       0
Bank Sta=4938.8,5063.5
XS Rating Curve= 0 ,0
Exp/Cntr=0.3,0.1

Type RM Length L Ch R = 1 ,3738    ,441,441,441
BEGIN DESCRIPTION:
UNT 008 IN LACR 4.0
END DESCRIPTION:
XS GIS Cut Line= 3
      2158237.68     13216596.86      2159037.72     13216546.85
      2159737.71     13215746.87
#Sta/Elev= 30
  4198.4  486.48  4238.5  485.96  4276.1  483.17  4348.4  480.71  4457.8  476.13
  4689.4  468.57  4917.3  466.08  4966.9  464.44  4969.7  463.94  4972.9  464.44
  5056.5  465.29  5064.1  466.08  5205.5  465.81  5212.6  466.57  5361.1  467.85
  5489.3  469.91  5602.2  470.18    5624  471.42  5708.5  472.11  5730.3  473.43
  5744.1  473.16  5751.2  474.44  5765.5  474.44  5772.1  473.52  5800.6   475.2
  5814.8  474.84  5857.5  476.64  5949.6  478.25  6055.9  481.92    6063  482.94
#Mann= 6 ,-1 , 0
  4198.4     .05       0  4348.4      .1       0  4457.8     .16       0
  4966.9     .07       0  4972.9     .16       0  5361.1      .1       0
Bank Sta=4917.3,5064.1
XS Rating Curve= 0 ,0
Exp/Cntr=0.3,0.1

Type RM Length L Ch R = 1 ,3297    ,462,462,462
BEGIN DESCRIPTION:
UNT 008 IN LACR 3.0
END DESCRIPTION:
XS GIS Cut Line= 3
      2158337.72     13216646.86      2159137.72     13216946.85
       2159837.7     13215746.89
#Sta/Elev= 30
  4145.6  482.71  4155.4  481.36  4240.8  478.35  4246.2  477.36    4417  472.24
  4455.3  469.65  4502.5  468.96  4540.8  466.93  4753.6  464.44  4882.5  463.52
  4901.8  462.11  4904.5  461.61  4907.8  462.11  4914.6  463.03  5035.1  462.43
  5093.9  463.48  5189.8  463.19  5254.7  464.53  5355.2  464.71  5510.6  466.54
  5542.1  465.94  5585.1  467.22  5717.8  467.16  5986.1  471.42  6215.2  478.38
  6250.3  478.41  6273.5  480.09  6308.2  480.18  6316.9  481.36  6389.2   483.3
#Mann= 5 ,-1 , 0
  4145.6      .1       0  4753.6     .16       0  4901.8     .07       0
  4907.8     .16       0  5355.2      .1       0
Bank Sta=4882.5,5093.9
XS Rating Curve= 0 ,0
Exp/Cntr=0.3,0.1

Type RM Length L Ch R = 1 ,2835    ,218,218,218
BEGIN DESCRIPTION:
UNT 008 IN LACR 2.0
END DESCRIPTION:
XS GIS Cut Line= 3
      2158087.73     13216946.86      2159287.72     13217346.85
      2159937.72     13215746.85
#Sta/Elev= 30
  3735.1  486.25  3840.5  482.71    3851  481.36  3998.6  477.43  4040.8  474.97
  4325.4  466.27  4515.1  462.07  4715.4  460.47  4947.3  460.63  5011.7  459.71
  5014.5  459.21  5017.7  459.71  5068.3  460.96  5360.1  464.07  5443.2  463.91
  5474.9  464.99  5759.1  465.19  5807.2  466.24  5866.2  465.29  5982.2  467.39
  6026.9   466.8    6075  468.11  6080.4  467.36    6360  473.06  6366.9  474.15
  6403.2  474.02  6586.7  479.95  6682.8  481.04  6688.2  482.25    6727  483.27
#Mann= 4 ,-1 , 0
  3735.1      .1       0  4325.4     .16       0  5011.7     .07       0
  5017.7     .16       0
Bank Sta=4947.3,5068.3
XS Rating Curve= 0 ,0
Exp/Cntr=0.3,0.1

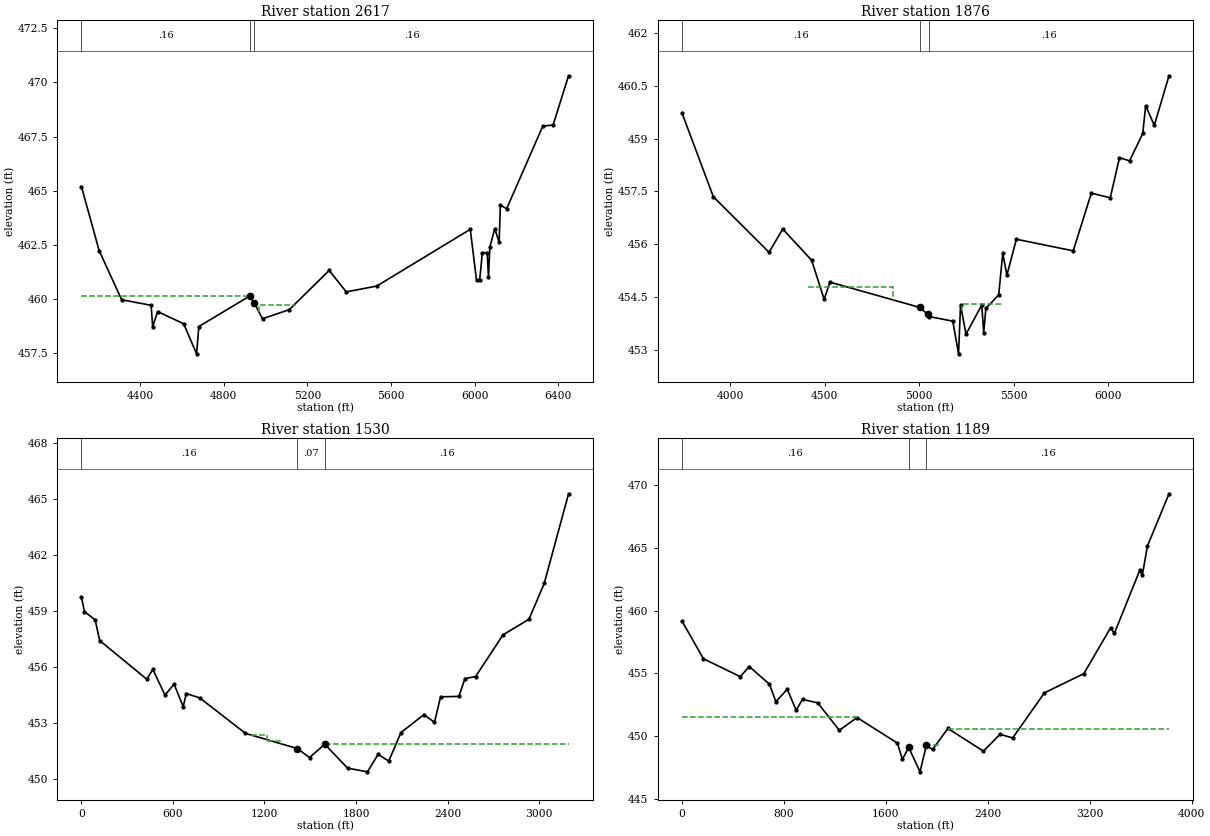
Type RM Length L Ch R = 1 ,2617    ,741,741,741
BEGIN DESCRIPTION:
Mapping XS f3c273e9
END DESCRIPTION:
XS GIS Cut Line= 4
      2158576.21     13217471.65      2159173.04     13217634.43
      2159813.23     13217308.91      2160366.59     13216484.29
#Sta/Elev= 30
  4119.4  465.19  4203.9  462.24  4311.5  459.97  4452.7  459.71    4460  458.73
  4483.8  459.42  4608.1  458.86  4670.1  457.47  4680.7  458.73  4924.3  460.14
  4946.5  459.81  4985.4  459.09  5113.3  459.51  5304.2  461.32  5385.9  460.33
    5532   460.6  5979.2  463.22  6009.1  460.86  6024.1  460.86  6036.8  462.14
  6060.2  462.14  6066.2  461.02  6072.9   462.4  6096.2  463.25  6117.2  462.63
  6123.2  464.34  6153.2  464.17  6325.8  467.98  6375.3  468.04  6449.3  470.31
#Mann= 3 , 0 , 0
  4119.4     .16       0  4924.3     .07       0  4946.5     .16       0
#XS Ineff= 2 ,-1
  4119.4  4923.3  460.15 4967.33 5143.47  459.74
Permanent Ineff=
       F       F
Bank Sta=4924.3,4946.5
XS Rating Curve= 0 ,0
Exp/Cntr=0.3,0.1

Type RM Length L Ch R = 1 ,1876    ,337,337,337
BEGIN DESCRIPTION:
Mapping XS 37d6897b
END DESCRIPTION:
XS GIS Cut Line= 4
      2158684.78     13217771.16      2159387.88     13218174.79
      2160195.18     13218005.52      2160520.38     13217120.97
#Sta/Elev= 30
  3743.5  459.74  3909.8  457.35  4204.6  455.77  4277.3  456.43  4430.4  455.54
  4496.4  454.43  4526.7  454.92  5002.8   454.2  5044.5     454  5052.7  453.94
  5177.3  453.81  5207.7  452.88  5218.2  454.27  5247.2  453.44  5330.6  454.27
  5340.8  453.48  5352.2  454.17  5420.3  454.56  5441.6  455.74  5463.6  455.12
  5513.8  456.14  5814.5  455.81  5910.4  457.45  6010.5  457.32  6059.5  458.46
  6112.8  458.37  6182.7  459.15    6198  459.94  6243.7  459.38  6321.5  460.79
#Mann= 3 ,-1 , 0
  3743.5     .16       0  5002.8     .07       0  5052.7     .16       0
#XS Ineff= 2 ,-1
 4411.93 4858.52  454.79 5223.76 5435.08  454.29
Permanent Ineff=
       F       F
Bank Sta=5002.8,5044.5
XS Rating Curve= 0 ,0
Exp/Cntr=0.3,0.1

Type RM Length L Ch R = 1 ,1530    ,350,350,350
XS GIS Cut Line= 4
     2158666.171    13217883.284     2159589.782    13218483.979
      2160273.81    13218365.923      2160711.31    13217036.062
#Sta/Elev= 30
       0459.725419.91355458.956789.61095 458.527119.4813457.4154428.1412455.3465
467.9683 455.869547.6225454.4995607.3631455.0853667.1038 453.874687.0173454.5816
776.6282454.34271075.331452.4502 1415.11451.64041495.081451.1598 1595.05451.8701
1745.004450.59051874.908450.3937 1944.83451.32432014.753450.96942094.664452.4948
2244.498453.4495 2314.42453.04732354.375454.40412474.242454.42912514.198455.3797
 2584.12455.49062763.921 457.7212933.732458.55173033.621460.46593193.444465.2636
#Mann= 3 , 0 , 0
       0     .16       0 1415.11     .07       0 1595.05     .16       0
#XS Ineff= 3 ,-1
 1113.52 1215.56  452.34 1218.28 1305.36  452.04 1595.163193.444  451.87
Permanent Ineff=
       F       F       F
Bank Sta=1415.11,1595.05
XS Rating Curve= 0 ,0
Exp/Cntr=0.3,0.1

Type RM Length L Ch R = 1 ,1189    ,0,0,0
BEGIN DESCRIPTION:
UNT 008 IN LACR 1.0
END DESCRIPTION:
XS GIS Cut Line= 4
      2158619.67     13218014.21     2159704.811    13218786.561
     2160336.321    13218780.051      2160928.68     13217007.27
#Sta/Elev= 30
       0459.1839 169.328456.1677458.1817454.7477 527.905455.5545687.2725 454.145
737.0748452.7559826.7191453.7413896.4424452.0732946.2448452.9389 1065.77452.6575
1235.098450.47621374.158451.49191690.416449.45911729.948448.16131779.363449.1165
1868.311447.16971917.726449.26881967.141448.9501 2086.79450.62342365.969448.8158
2495.587450.15772595.294449.86872844.561453.45963153.653454.98683363.037458.6286
3392.949458.19013592.363463.21093612.304462.81163652.187465.13753821.688469.3036
#Mann= 3 , 0 , 0
       0     .16       01779.363     .07       01917.726     .16       0
#XS Ineff= 4 ,-1
       0 1377.27  451.51  1660.2 1779.53   449.1 1918.36  2018.2  449.27
 2084.093821.688   450.6
Permanent Ineff=
       F       F       F       F
Bank Sta=1779.363,1917.726
XS Rating Curve= 0 ,0
Exp/Cntr=0.3,0.1

Chan Stop Cuts=-1
Use User Specified Reach Order=0
Composite Channel Slope=5