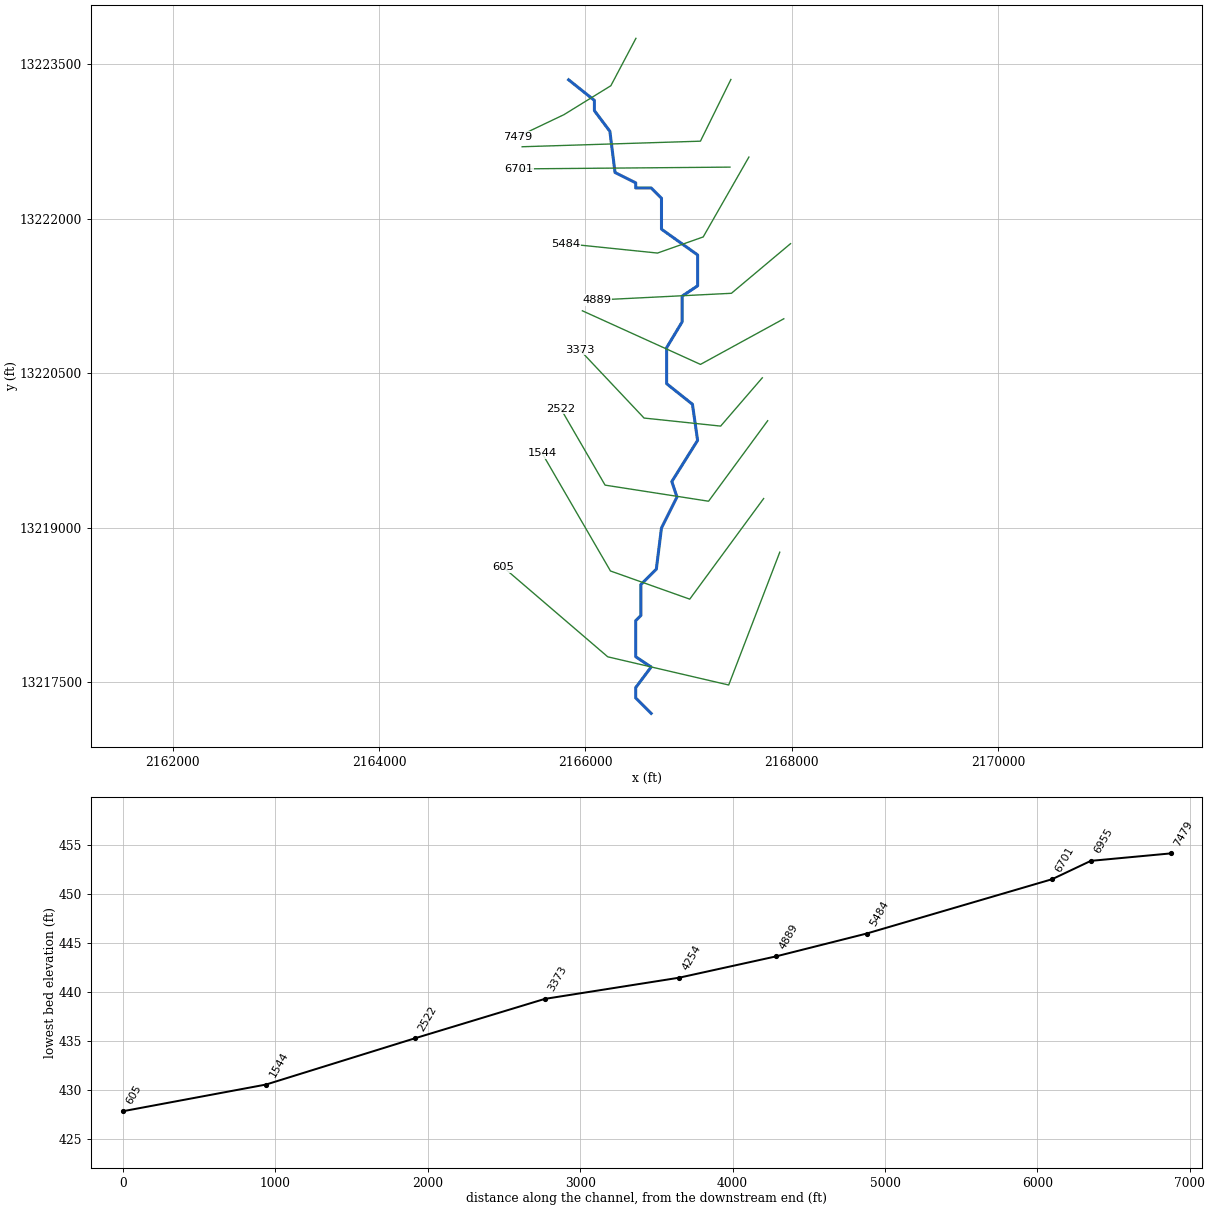
--- UNT 009 IN LACR.prj (project) ---

Proj Title=UNT 009 IN LACR Base Level Engineering
Current Plan=p01
Default Exp/Contr=0.3,0.1
English Units
Geom File=g01
Flow File=f01
Plan File=p01
Y Axis Title=Elevation
X Axis Title(PF)=Main Channel Distance
X Axis Title(XS)=Station
BEGIN DESCRIPTION:
UNT 009 IN LACR
END DESCRIPTION:
DSS Export Rating Curves= 0
DSS Export Rating Curve Sorted= 0
DSS Export Volume Flow Curves= 0
DXF OffsetX= 0
DXF OffsetY= 0
DXF ScaleX= 1
DXF ScaleY= 10

--- UNT 009 IN LACR.p01 (plan) ---

Plan Title=Multiple Run
Short Identifier=Multiple
Geom File=g01
Flow File=f01
Subcritical Flow
K Sum by GR= 0
Std Step Tol= 0.01
Critical Tol= 0.01
Num of Std Step Trials= 20
Max Error Tol= 0.3
Flow Tol Ratio= 0.001
Split Flow NTrial= 30
Split Flow Tol= 0.02
Split Flow Ratio= 0.02
Log Output Level= 0
Friction Slope Method= 1
Unsteady Friction Slope Method= 2
Unsteady Bridges Friction Slope Method= 1
Parabolic Critical Depth
Global Vel Dist=  1 , 1 , 1
Global Log Level= 0
CheckData=True
Encroach Param= -1, 0, 0, 0
BEGIN DESCRIPTION:
Multiple Run
END DESCRIPTION:

--- UNT 009 IN LACR.f01 (steady flow) ---

Flow Title=Multiple
Number of Profiles=7
Profile Names=10-year,25-year,50-year,1pct_min,100-year,1pct_plu,500-year
River Rch & RM= UNT 009 IN LACR,Reach-1,7479
     295     420     525     483     653     883    1026
River Rch & RM= UNT 009 IN LACR,Reach-1,605
     345     495     622     575     778    1052    1236
Boundary for River Rch & Prof#=UNT 009 IN LACR,Reach-1,1
Up Type=0
Dn Type=3
Dn Slope=0.005
Boundary for River Rch & Prof#=UNT 009 IN LACR,Reach-1,2
Up Type=0
Dn Type=3
Dn Slope=0.005
Boundary for River Rch & Prof#=UNT 009 IN LACR,Reach-1,3
Up Type=0
Dn Type=3
Dn Slope=0.005
Boundary for River Rch & Prof#=UNT 009 IN LACR,Reach-1,4
Up Type=0
Dn Type=3
Dn Slope=0.005
Boundary for River Rch & Prof#=UNT 009 IN LACR,Reach-1,5
Up Type=0
Dn Type=3
Dn Slope=0.005
Boundary for River Rch & Prof#=UNT 009 IN LACR,Reach-1,6
Up Type=0
Dn Type=3
Dn Slope=0.005
Boundary for River Rch & Prof#=UNT 009 IN LACR,Reach-1,7
Up Type=0
Dn Type=3
Dn Slope=0.005

--- UNT 009 IN LACR.g01 (geometry) ---

Geom Title=Existing Conditions
Program Version=4.10

River Reach=UNT 009 IN LACR ,Reach-1
Reach XY= 30
      2165837.72     13223346.85      2166087.72     13223146.86
      2166087.72     13223046.85      2166237.72     13222846.86
      2166287.72     13222446.85      2166487.72     13222346.86
      2166487.72     13222296.85      2166637.72     13222296.85
      2166737.72     13222196.85      2166737.72     13221896.85
      2167087.72     13221646.85      2167087.72     13221346.86
      2166937.72     13221246.85      2166937.72     13220996.85
      2166787.72     13220746.85      2166787.72     13220396.85
      2167037.72     13220196.86      2167087.72     13219846.85
      2166837.72     13219446.85      2166887.72     13219296.85
      2166737.72     13218996.85      2166687.72     13218596.85
      2166537.72     13218446.85      2166537.72     13218146.85
      2166487.72     13218096.85      2166487.72     13217746.86
      2166637.72     13217646.85      2166487.72     13217446.85
      2166487.72     13217346.85      2166637.72     13217196.85

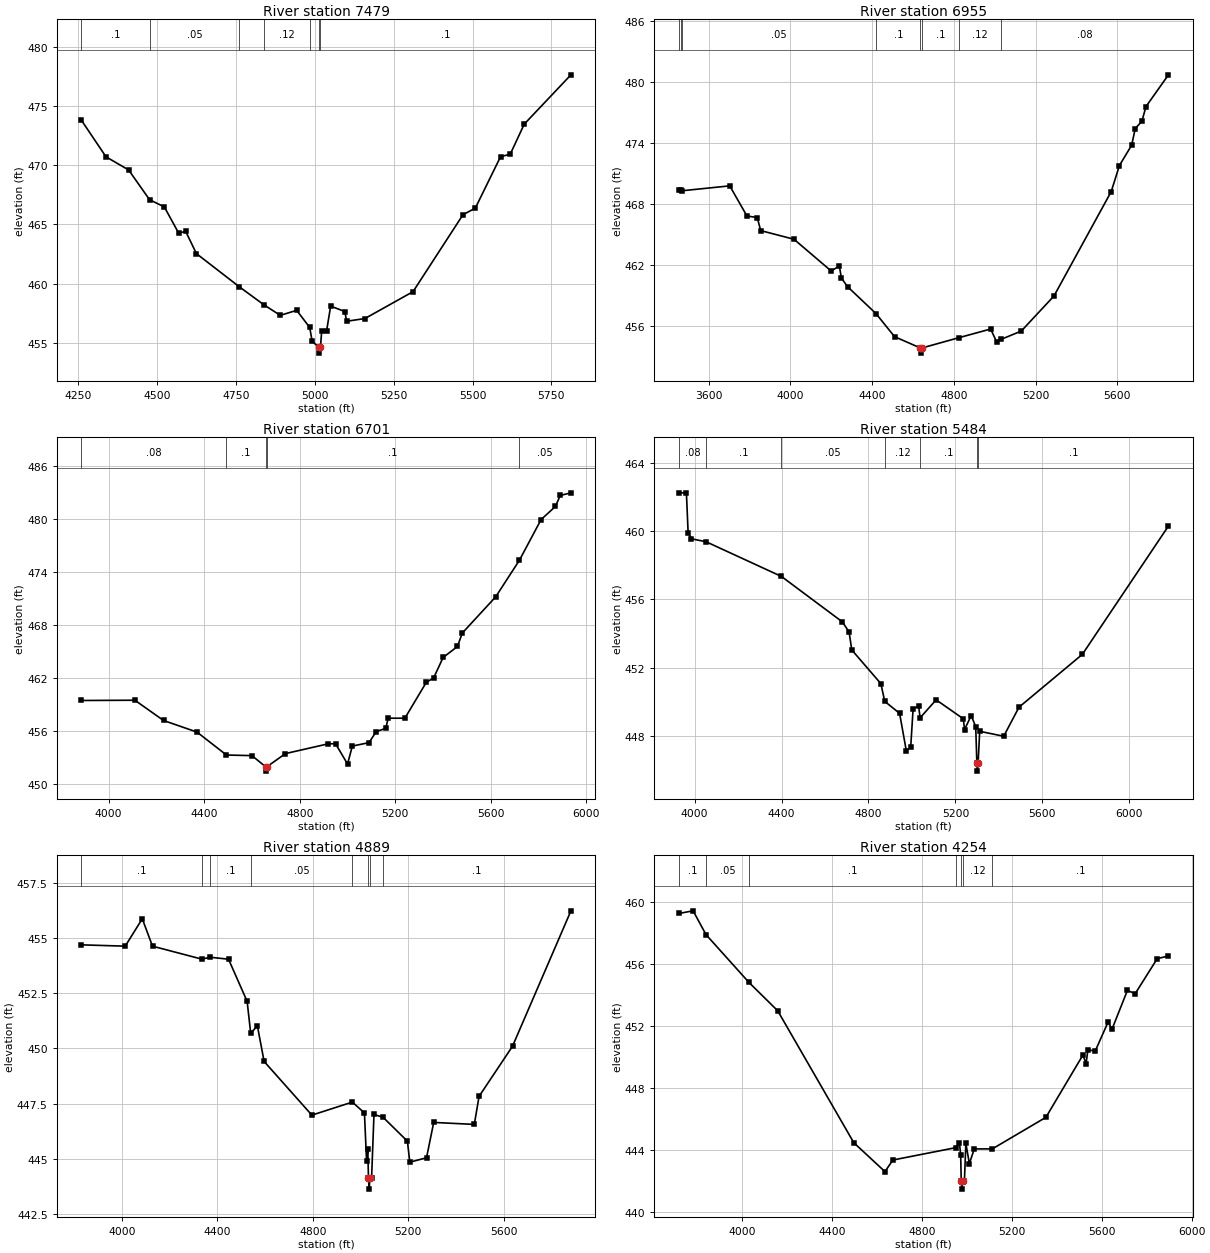
Type RM Length L Ch R = 1 ,7479    ,524,524,524
BEGIN DESCRIPTION:
UNT 009 IN LACR 5.0
END DESCRIPTION:
XS GIS Cut Line= 4
      2166490.04     13223749.18      2166246.97     13223289.09
      2165792.57     13223008.28      2165344.23     13222794.31
#Sta/Elev= 30
  4260.6  473.79  4338.6   470.7  4410.3  469.59  4476.6  467.08  4523.4  466.47
  4568.6  464.27  4591.2   464.4  4625.1  462.53  4760.5  459.74  4838.9  458.21
  4890.8  457.32  4942.8  457.74  4984.1   456.3  4991.7  455.15  5012.2  454.63
  5014.9  454.13  5018.2  454.63    5022  455.97  5037.4  455.97  5050.5   458.1
  5095.3  457.64  5101.2  456.82  5159.1  457.05  5311.6  459.32  5469.7  465.81
  5508.9  466.37  5588.7   470.7  5619.7  470.93    5664  473.46  5811.9  477.62
#Mann= 7 ,-1 , 0
  4260.6      .1       0  4476.6     .05       0  4760.5      .1       0
  4838.9     .12       0  4984.1      .1       0  5012.2     .07       0
  5018.2      .1       0
Bank Sta=5012.2,5018.2
XS Rating Curve= 0 ,0
Exp/Cntr=0.3,0.1

Type RM Length L Ch R = 1 ,6955    ,254,254,254
BEGIN DESCRIPTION:
UNT 009 IN LACR 4.0
END DESCRIPTION:
XS GIS Cut Line= 3
      2167410.18     13223349.89      2167115.02     13222750.89
      2165387.74     13222696.86
#Sta/Elev= 30
  3454.5  469.42  3463.4  469.42  3470.8  469.34  3703.2  469.82  3787.4  466.86
  3837.9   466.7  3854.8  465.42  4017.6  464.57  4199.6  461.45  4239.6  461.94
  4249.6  460.76  4279.6  459.91  4419.3  457.25  4509.8  454.99  4636.8  453.87
  4639.6  453.37  4642.8  453.87    4825  454.89    4980  455.74    5010  454.46
  5031.9  454.73  5130.1  455.54  5290.1  458.99  5570.3  469.26  5610.3  471.82
  5670.3  473.82  5687.9  475.46  5720.4  476.18  5740.4  477.62  5850.4  480.74
#Mann= 8 ,-1 , 0
  3454.5     .05       0  3463.4      .1       0  3470.8     .05       0
  4419.3      .1       0  4636.8     .07       0  4642.8      .1       0
    4825     .12       0  5031.9     .08       0
Bank Sta=4636.8,4642.8
XS Rating Curve= 0 ,0
Exp/Cntr=0.3,0.1

Type RM Length L Ch R = 1 ,6701    ,1217,1217,1217
BEGIN DESCRIPTION:
UNT 009 IN LACR 3.0
END DESCRIPTION:
XS GIS Cut Line= 2
      2167401.48     13222499.15      2165352.85     13222481.79
#Sta/Elev= 30
  3886.2  459.48    4110  459.51    4230  457.22    4370  455.91  4493.3  453.32
    4600  453.25    4657     452  4659.7   451.5    4663     452    4740  453.48
    4920  454.59    4950  454.59    5000   452.3    5020  454.33    5090  454.72
    5120  455.97    5160  456.33    5170  457.48    5240  457.48    5330  461.55
    5360  462.01    5400  464.34    5460  465.58    5480  467.09    5620  471.19
  5719.4  475.33    5810  479.92    5870   481.4    5890  482.64  5934.9  482.94
#Mann= 5 ,-1 , 0
  3886.2     .08       0  4493.3      .1       0    4657     .07       0
    4663      .1       0  5719.4     .05       0
Bank Sta=4657,4663
XS Rating Curve= 0 ,0
Exp/Cntr=0.3,0.1

Type RM Length L Ch R = 1 ,5484    ,595,595,595
BEGIN DESCRIPTION:
UNT 009 IN LACR 2.0
END DESCRIPTION:
XS GIS Cut Line= 4
      2167584.73     13222596.82      2167141.72     13221821.25
      2166699.01       13221665.      2165813.55     13221756.15
#Sta/Elev= 30
  3927.8  462.24  3962.3  462.24  3970.1  459.91  3985.3  459.55  4052.4  459.38
  4399.4  457.35    4680  454.69  4710.9   454.1  4723.2  453.05    4857  451.08
    4875  450.04  4943.3  449.34  4974.2  447.15  4994.5  447.38  5005.5  449.61
  5030.7  449.77  5037.8  449.08  5111.5  450.13  5236.7  449.02    5242  448.39
  5272.9  449.21  5293.6  448.56  5298.8  446.46  5301.6  445.96  5304.8  446.46
  5311.9  448.29  5422.4     448  5492.8   449.7  5784.3  452.79  6180.6   460.3
#Mann= 7 ,-1 , 0
  3927.8     .08       0  4052.4      .1       0  4399.4     .05       0
    4875     .12       0  5037.8      .1       0  5298.8     .07       0
  5304.8      .1       0
Bank Sta=5298.8,5304.8
XS Rating Curve= 0 ,0
Exp/Cntr=0.3,0.1

Type RM Length L Ch R = 1 ,4889    ,635,635,635
BEGIN DESCRIPTION:
Mapping XS 8c26a06c
END DESCRIPTION:
XS GIS Cut Line= 3
      2167988.04     13221756.11      2167415.15     13221274.37
      2166113.09     13221209.27
#Sta/Elev= 30
    3830  454.69  4013.7  454.63  4085.2  455.87  4128.1  454.63  4335.9  454.04
  4368.5  454.13  4446.8  454.04  4524.8  452.13  4539.7  450.69  4567.8  451.02
    4596  449.41  4796.2  446.98  4965.8  447.57  5016.5  447.08  5025.5  444.91
  5030.5  445.44  5033.5  444.13  5036.3  443.63  5039.5  444.13  5046.5  444.13
  5056.5  447.01    5095  446.88  5196.7   445.8  5206.7  444.85  5276.8  445.05
  5306.9  446.65  5477.1  446.56  5497.1  447.83  5637.3   450.1  5882.2  456.23
#Mann= 8 ,-1 , 0
    3830      .1       0  4335.9     .05       0  4368.5      .1       0
  4539.7     .05       0  4965.8     .12       0  5033.5     .07       0
  5039.5     .12       0    5095      .1       0
Bank Sta=5033.5,5039.5
XS Rating Curve= 0 ,0
Exp/Cntr=0.3,0.1

Type RM Length L Ch R = 1 ,4254    ,881,881,881
BEGIN DESCRIPTION:
Mapping XS 3ed6601a
END DESCRIPTION:
XS GIS Cut Line= 3
        2167923.       13221027.      2167115.68     13220584.27
       2165971.3     13221104.44
#Sta/Elev= 30
    3719  459.28  3782.1  459.45  3839.6  457.91  4030.7  454.82  4158.4  452.99
    4497  444.46  4635.7  442.59  4670.5  443.34  4950.3  444.14  4966.9  444.46
  4972.4  443.67    4975  441.96  4977.8  441.46    4981  441.96    4989  441.96
  4995.5  444.42    5011  443.11    5033  444.06  5113.1  444.06  5351.5   446.1
  5516.3  450.13  5530.4  449.57  5538.2  450.46  5571.1  450.39  5628.2  452.26
  5645.7   451.8    5714   454.3    5749   454.1  5846.8  456.36  5896.8  456.53
#Mann= 7 ,-1 , 0
    3719      .1       0  3839.6     .05       0  4030.7      .1       0
  4950.3     .12       0    4975     .07       0    4981     .12       0
  5113.1      .1       0
Bank Sta=4975,4981
XS Rating Curve= 0 ,0
Exp/Cntr=0.3,0.1

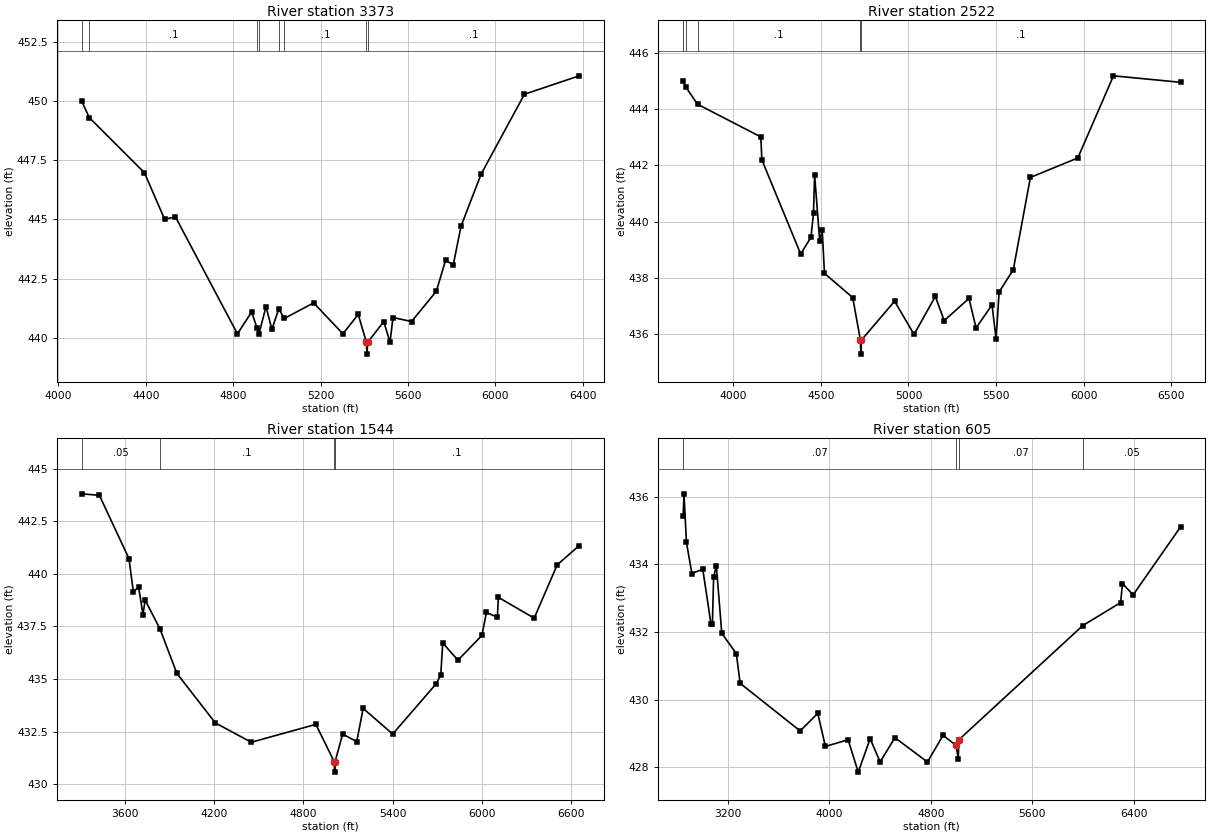
Type RM Length L Ch R = 1 ,3373    ,851,851,851
BEGIN DESCRIPTION:
Mapping XS 64ea95e1
END DESCRIPTION:
XS GIS Cut Line= 4
      2167714.65     13220454.08      2167310.99     13219985.31
       2166568.8     13220063.43      2165943.82     13220727.47
#Sta/Elev= 30
  4106.6     450  4141.1  449.31  4393.3  446.98  4485.6  445.01  4535.2  445.11
    4819  440.16  4883.8  441.08  4909.5  440.39  4917.2  440.14  4949.7  441.31
  4976.8  440.35  5008.1  441.21  5033.7  440.81  5167.9  441.47  5301.7  440.16
    5372  440.98  5409.3   439.8    5412   439.3  5415.3   439.8    5489  440.68
  5517.3   439.8  5531.1  440.85    5616  440.68  5729.3  441.96  5771.8  443.27
    5807  443.08  5842.6  444.72  5934.5  446.92  6132.7   450.3  6383.4  451.08
#Mann= 8 ,-1 , 0
  4106.6     .05       0  4141.1      .1       0  4909.5     .12       0
  4917.2      .1       0  5008.1     .12       0  5033.7      .1       0
  5409.3     .07       0  5415.3      .1       0
Bank Sta=5409.3,5415.3
XS Rating Curve= 0 ,0
Exp/Cntr=0.3,0.1

Type RM Length L Ch R = 1 ,2522    ,978,978,978
BEGIN DESCRIPTION:
Mapping XS e03af002
END DESCRIPTION:
XS GIS Cut Line= 4
      2167766.74     13220037.43       2167193.8     13219256.14
       2166191.2     13219412.39      2165761.48     13220154.62
#Sta/Elev= 30
    3713  445.01  3728.6  444.78  3795.3  444.17  4156.7  443.01  4162.9  442.19
  4384.4  438.85    4443  439.44  4457.7  440.29  4463.9  441.67  4493.2   439.3
  4507.4   439.7  4520.3  438.16  4681.8   437.3  4725.5  435.79  4728.2  435.29
  4731.5  435.79  4920.8  437.17  5032.1  435.99  5153.6  437.34  5204.2  436.48
  5345.8  437.27  5386.3  436.22  5477.4  437.04  5500.5  435.83  5517.9   437.5
  5598.9  438.29  5696.6  441.57  5967.3  442.26  6171.1  445.18  6554.2  444.95
#Mann= 5 ,-1 , 0
    3713      .1       0  3728.6     .08       0  3795.3      .1       0
  4725.5     .07       0  4731.5      .1       0
Bank Sta=4725.5,4731.5
XS Rating Curve= 0 ,0
Exp/Cntr=0.3,0.1

Type RM Length L Ch R = 1 ,1544    ,939,939,939
BEGIN DESCRIPTION:
Mapping XS 2d2ab2df
END DESCRIPTION:
XS GIS Cut Line= 4
      2167727.68     13219282.22      2167011.51     13218305.62
      2166243.28     13218579.06      2165580.09     13219723.39
#Sta/Elev= 30
  3307.5   443.8  3425.8  443.73  3625.3  440.72  3654.6  439.14  3690.1  439.37
  3719.4  438.06  3734.1  438.75  3834.4  437.37  3947.2  435.27  4206.5  432.91
  4448.8  431.99  4883.5  432.84  5006.9  431.07  5009.7  430.57  5012.9  431.07
  5063.9  432.38  5158.8  432.02  5201.9   433.6  5400.8  432.38  5694.8  434.78
  5724.4   435.2  5737.9  436.71    5840  435.89  6001.8  437.07  6031.9  438.16
  6105.8  437.93  6112.2  438.88  6353.3  437.89  6508.2  440.42  6656.6  441.34
#Mann= 4 ,-1 , 0
  3307.5     .05       0  3834.4      .1       0  5006.9     .07       0
  5012.9      .1       0
Bank Sta=5006.9,5012.9
XS Rating Curve= 0 ,0
Exp/Cntr=0.3,0.1

Type RM Length L Ch R = 1 ,605     ,0,0,0
BEGIN DESCRIPTION:
UNT 009 IN LACR 1.0
END DESCRIPTION:
XS GIS Cut Line= 4
      2167883.92     13218761.39      2167389.11     13217472.29
      2166217.24     13217745.73      2165202.17     13218617.65
#Sta/Elev= 30
  2846.6  435.43  2853.4  436.09  2872.7  434.65  2915.7  433.73  3001.4  433.86
  3065.7  432.25  3077.5  432.25  3087.1  433.63  3108.5  433.96  3151.4  431.96
  3266.2  431.36  3296.2  430.48  3769.1  429.07  3908.5  429.59  3968.5  428.61
  4147.5  428.81  4227.4  427.85  4321.3  428.84  4399.9  428.15  4516.4  428.87
  4773.1  428.15  4896.3  428.94    4999  428.64    5016  428.25  5021.2  428.81
  5998.3  432.19  6296.6  432.87  6310.9  433.43  6395.4   433.1  6768.9  435.11
#Mann= 4 ,-1 , 0
  2846.6     .07       0    4999    .035       0  5021.2     .07       0
  5998.3     .05       0
Bank Sta=4999,5021.2
XS Rating Curve= 0 ,0
Exp/Cntr=0.3,0.1

Chan Stop Cuts=-1
Use User Specified Reach Order=0
Composite Channel Slope=5