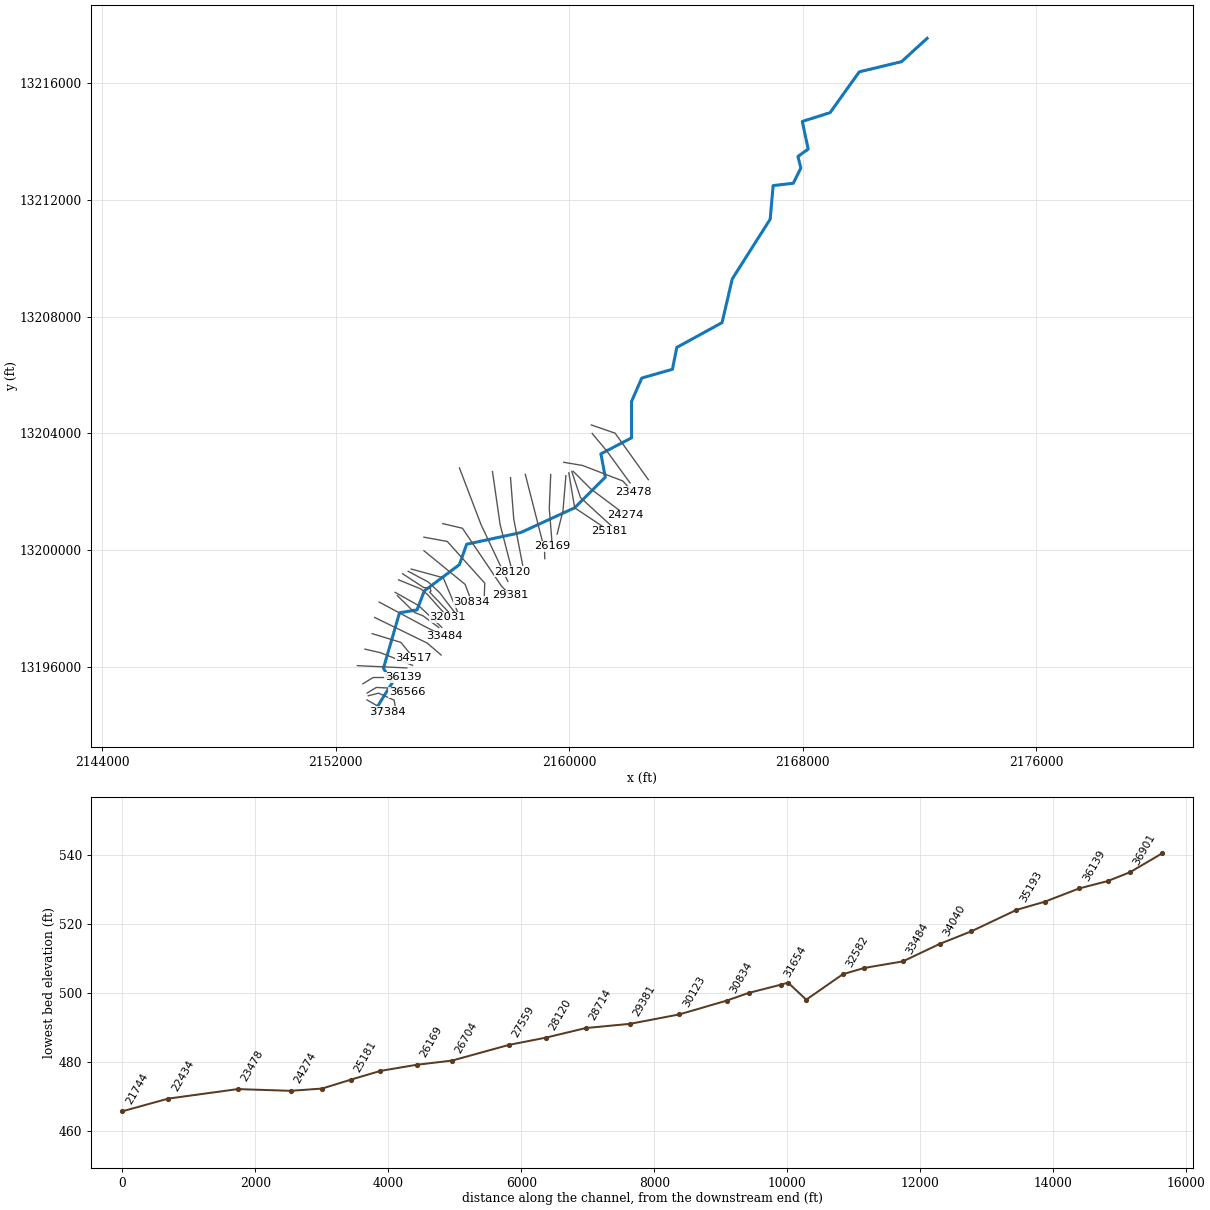
--- UNT 010 IN LACR.prj (project) ---

Proj Title=UNT 010 IN LACR Base Level Engineering
Current Plan=p01
Default Exp/Contr=0.3,0.1
English Units
Geom File=g01
Flow File=f01
Plan File=p01
Y Axis Title=Elevation
X Axis Title(PF)=Main Channel Distance
X Axis Title(XS)=Station
BEGIN DESCRIPTION:
UNT 010 IN LACR
END DESCRIPTION:
DSS Export Rating Curves= 0
DSS Export Rating Curve Sorted= 0
DSS Export Volume Flow Curves= 0
DXF OffsetX= 0
DXF OffsetY= 0
DXF ScaleX= 1
DXF ScaleY= 10

--- UNT 010 IN LACR.p01 (plan) ---

Plan Title=Multiple Run
Short Identifier=Multiple
Geom File=g01
Flow File=f01
Subcritical Flow
K Sum by GR= 0
Std Step Tol= 0.01
Critical Tol= 0.01
Num of Std Step Trials= 20
Max Error Tol= 0.3
Flow Tol Ratio= 0.001
Split Flow NTrial= 30
Split Flow Tol= 0.02
Split Flow Ratio= 0.02
Log Output Level= 0
Friction Slope Method= 1
Unsteady Friction Slope Method= 2
Unsteady Bridges Friction Slope Method= 1
Parabolic Critical Depth
Global Vel Dist=  1 , 1 , 1
Global Log Level= 0
CheckData=True
Encroach Param= -1, 0, 0, 0
BEGIN DESCRIPTION:
Multiple Run
END DESCRIPTION:

--- UNT 010 IN LACR.f01 (steady flow) ---

Flow Title=Multiple
Program Version=4.10
Number of Profiles= 7
Profile Names=10-year,25-year,50-year,1pct_min,100-year,1pct_plu,500-year
River Rch & RM=UNT 010 IN LACR,Reach-1         ,37384
     204     289     360     330     447     604     700
River Rch & RM=UNT 010 IN LACR,Reach-1         ,35193
     216     305     381     350     473     640     742
River Rch & RM=UNT 010 IN LACR,Reach-1         ,34040
     397     577     733     684     926    1252    1503
River Rch & RM=UNT 010 IN LACR,Reach-1         ,32582
     397     577     733     684     926    1252    1503
River Rch & RM=UNT 010 IN LACR,Reach-1         ,28714
     773    1153    1490    1412    1910    2582    3193
River Rch & RM=UNT 010 IN LACR,Reach-1         ,28120
     773    1153    1490    1412    1910    2582    3193
River Rch & RM=UNT 010 IN LACR,Reach-1         ,25181
     773    1153    1490    1412    1910    2582    3193
River Rch & RM=UNT 010 IN LACR,Reach-1         ,24748
     773    1153    1490    1412    1910    2582    3193
River Rch & RM=UNT 010 IN LACR,Reach-1         ,22434
     777    1158    1495    1416    1916    2591    3199
River Rch & RM=UNT 010 IN LACR,Reach-1         ,21180
     826    1233    1594    1511    2043    2763    3415
River Rch & RM=UNT 010 IN LACR,Reach-1         ,18997
     936    1399    1811    1717    2323    3141    3888
River Rch & RM=UNT 010 IN LACR,Reach-1         ,13197
     938    1400    1810    1714    2319    3136    3872
River Rch & RM=UNT 010 IN LACR,Reach-1         ,10656
    1039    1554    2012    1908    2581    3490    4318
River Rch & RM=UNT 010 IN LACR,Reach-1         ,9902
    1039    1554    2012    1908    2581    3490    4318
River Rch & RM=UNT 010 IN LACR,Reach-1         ,6030
    1080    1617    2094    1986    2686    3633    4498
River Rch & RM=UNT 010 IN LACR,Reach-1         ,3266
    1076    1608    2080    1970    2665    3604    4450
Boundary for River Rch & Prof#=UNT 010 IN LACR,Reach-1         , 1
Up Type= 0
Dn Type= 3
Dn Slope=0.002
Boundary for River Rch & Prof#=UNT 010 IN LACR,Reach-1         , 2
Up Type= 0
Dn Type= 3
Dn Slope=0.002
Boundary for River Rch & Prof#=UNT 010 IN LACR,Reach-1         , 3
Up Type= 0
Dn Type= 3
Dn Slope=0.002
Boundary for River Rch & Prof#=UNT 010 IN LACR,Reach-1         , 4
Up Type= 0
Dn Type= 3
Dn Slope=0.002
Boundary for River Rch & Prof#=UNT 010 IN LACR,Reach-1         , 5
Up Type= 0
Dn Type= 3
Dn Slope=0.002
Boundary for River Rch & Prof#=UNT 010 IN LACR,Reach-1         , 6
Up Type= 0
Dn Type= 3
Dn Slope=0.002
Boundary for River Rch & Prof#=UNT 010 IN LACR,Reach-1         , 7
Up Type= 0
Dn Type= 3
Dn Slope=0.002
DSS Import GetInterval= 0
DSS Import GetPeak= 0
DSS Import FillOption= 0

--- UNT 010 IN LACR.g01 (geometry) ---

Geom Title=Existing Conditions
Program Version=4.10

River Reach=UNT 010 IN LACR ,Reach-1
Reach XY= 30
      2153287.72     13194396.85      2153937.72     13195446.86
      2153637.72     13195946.85      2154187.72     13197846.85
      2154787.72     13197946.85      2155037.72     13198596.85
      2156237.72     13199496.85      2156487.72     13200196.86
      2158337.72     13200596.85      2160187.72     13201446.85
      2161237.72     13202496.86      2161087.72     13203296.86
      2162137.72     13203846.85      2162137.72     13205096.86
      2162487.72     13205896.85      2163537.72     13206196.85
      2163687.72     13206946.85      2165237.72     13207796.85
      2165587.72     13209296.85      2166887.72     13211346.86
      2166987.72     13212496.86      2167677.72     13212576.85
      2167937.72     13213096.85      2167837.72     13213496.86
      2168187.72     13213746.85      2167987.72     13214696.85
      2168937.72     13214996.85      2169937.72     13216396.85
      2171387.72     13216746.86      2172264.08     13217546.85

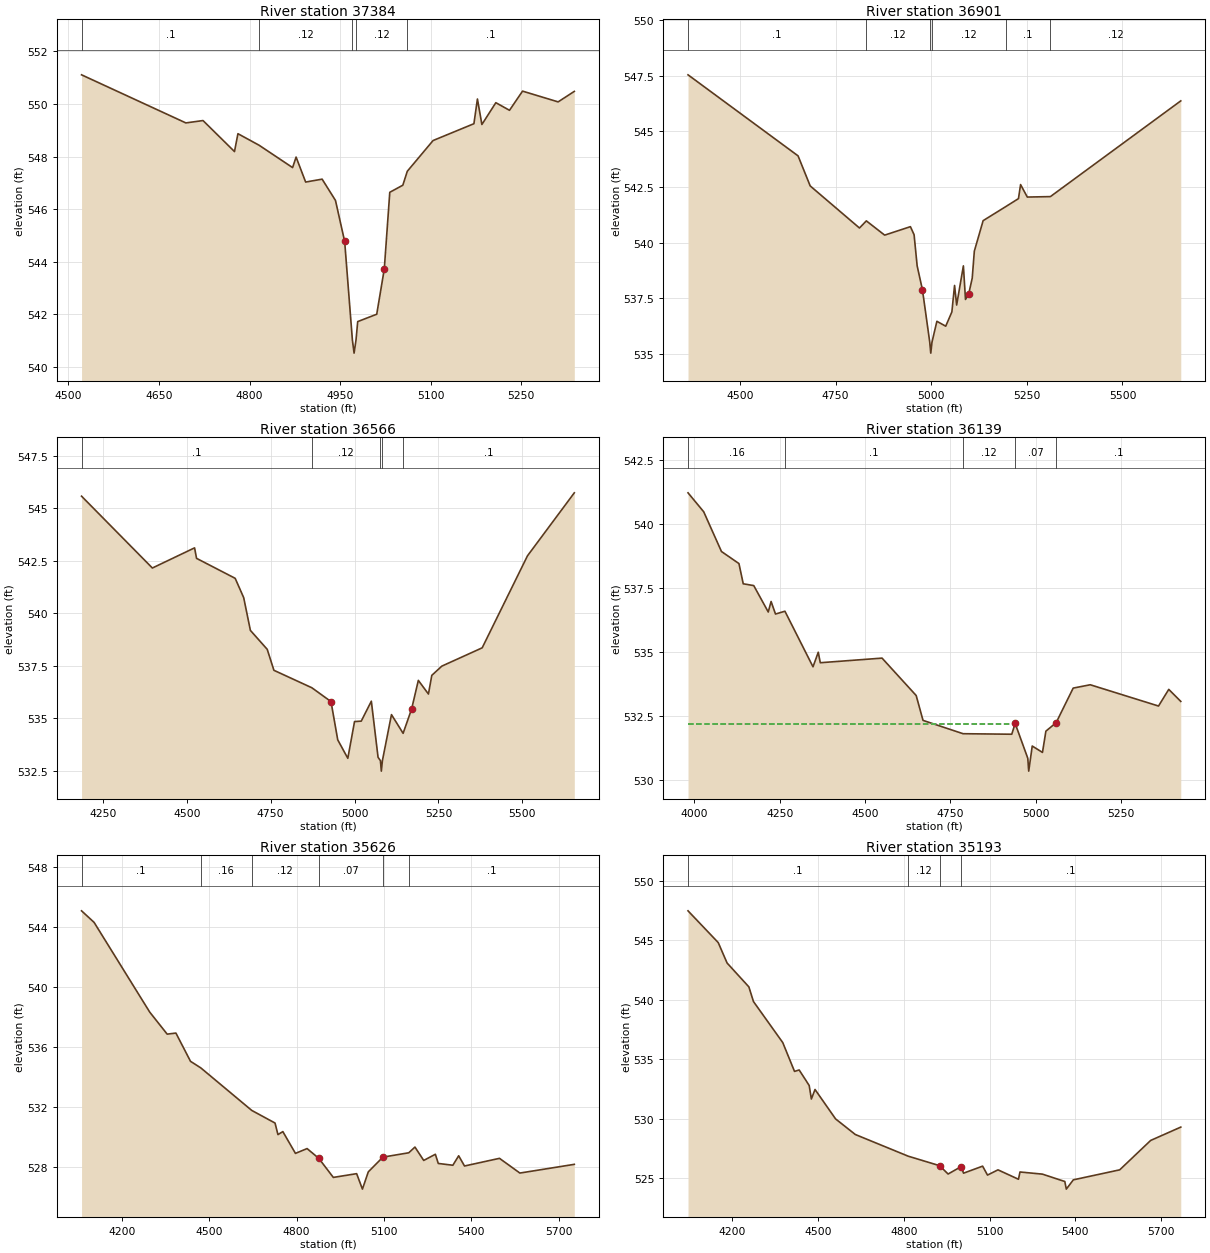
Type RM Length L Ch R = 1 ,37384   ,483,483,483
BEGIN DESCRIPTION:
UNT 010 IN LACR 57.0
END DESCRIPTION:
XS GIS Cut Line= 2
       2153073.5     13194858.35       2153780.3     13194450.96
#Sta/Elev= 30
  4521.9  551.11  4694.6  549.28    4723  549.37  4775.1  548.19  4780.8  548.87
  4815.9  548.43  4871.3  547.58  4877.1  547.98  4892.9  547.03  4920.2  547.14
  4942.3  546.33  4957.5  544.77  4970.3  541.02  4973.1  540.52  4976.3  541.02
  4979.1  541.72  5010.6     542  5023.1  543.72  5032.2  546.64  5053.8  546.91
  5061.2  547.44  5103.9  548.61  5171.5  549.25  5177.3  550.19  5184.7  549.22
  5207.8  550.05  5230.4  549.76    5252  550.49  5310.9  550.08  5337.7  550.48
#Mann= 5 ,-1 , 0
  4521.9      .1       0  4815.9     .12       0  4970.3     .07       0
  4976.3     .12       0  5061.2      .1       0
Bank Sta=4957.5,5023.1
XS Rating Curve= 0 ,0
Exp/Cntr=0.3,0.1

Type RM Length L Ch R = 1 ,36901   ,335,335,335
BEGIN DESCRIPTION:
Mapping XS e32fef49
END DESCRIPTION:
XS GIS Cut Line= 4
      2153117.84     13195001.01      2153471.99     13195089.54
      2154003.28      13194848.5      2154062.32     13194513.94
#Sta/Elev= 30
  4364.2  547.54  4651.9   543.9  4683.6  542.55  4812.4  540.66  4830.4  540.98
  4878.3  540.34  4945.6  540.72  4955.2  540.36  4963.2  538.96  4977.1  537.88
  4996.1  535.54  4998.8  535.04  5002.1  535.54  5014.8  536.47  5037.9  536.25
    5054  536.89    5061  538.08  5066.5   537.2  5084.1  538.96  5089.6  537.45
  5097.9  537.69  5107.2  538.41  5112.7  539.62  5135.7  540.99  5194.8  541.62
  5228.1  541.98  5233.6  542.61  5251.2  542.05  5311.5  542.07  5652.4  546.37
#Mann= 6 ,-1 , 0
  4364.2      .1       0  4830.4     .12       0  4996.1     .07       0
  5002.1     .12       0  5194.8      .1       0  5311.5     .12       0
Bank Sta=4977.1,5097.9
XS Rating Curve= 0 ,0
Exp/Cntr=0.3,0.1

Type RM Length L Ch R = 1 ,36566   ,427,427,427
BEGIN DESCRIPTION:
UNT 010 IN LACR 56.0
END DESCRIPTION:
XS GIS Cut Line= 4
      2153078.43     13195094.46      2153393.28     13195286.32
      2154273.84     13195242.04      2154450.92     13195114.16
#Sta/Elev= 30
  4186.3  545.57  4397.4  542.15  4523.2  543.11  4529.1  542.61  4644.2  541.66
  4669.6  540.74  4689.6  539.18  4739.7  538.28  4759.7  537.28  4872.7  536.45
  4929.9  535.79  4949.9  533.97    4980  533.09    5000  534.84    5020  534.86
  5050.1  535.81  5070.1  533.14  5077.1  532.98  5079.9  532.48  5083.1  532.98
  5110.1  535.17  5144.8  534.28  5170.2  535.44  5190.2   536.8  5220.3  536.15
  5230.3  537.04  5260.3  537.48  5380.5  538.35  5515.5  542.73  5655.1  545.73
#Mann= 5 ,-1 , 0
  4186.3      .1       0  4872.7     .12       0  5077.1     .07       0
  5083.1     .12       0  5144.8      .1       0
Bank Sta=4929.9,5170.2
XS Rating Curve= 0 ,0
Exp/Cntr=0.3,0.1

Type RM Length L Ch R = 1 ,36139   ,513,513,513
BEGIN DESCRIPTION:
UNT 010 IN LACR 55.0
END DESCRIPTION:
XS GIS Cut Line= 3
      2152930.86      13195409.3      2153280.14     13195625.75
      2154312.92     13195630.67
#Sta/Elev= 30
  3981.5  541.22  4027.5  540.48  4079.5  538.93  4130.7  538.46  4143.3  537.67
  4174.1   537.6  4216.6  536.57  4224.9  536.98  4237.8  536.49  4265.4   536.6
  4347.7  534.43  4363.1     535    4369  534.59    4550  534.77    4650  533.31
    4670  532.34  4787.4  531.82    4930   531.8    4940  532.22    4977  530.86
  4979.7  530.36    4990  531.34    5020  531.09    5030  531.92    5060  532.25
    5110   533.6    5160  533.73    5360   532.9    5390  533.55  5425.2  533.08
#Mann= 5 ,-1 , 0
  3981.5     .16       0  4265.4      .1       0  4787.4     .12       0
    4940     .07       0    5060      .1       0
#XS Ineff= 2 , 0
         4939.37  532.21
Permanent Ineff=
       F       F
Bank Sta=4940,5060
XS Rating Curve= 0 ,0
Exp/Cntr=0.3,0.1

Type RM Length L Ch R = 1 ,35626   ,433,433,433
BEGIN DESCRIPTION:
UNT 010 IN LACR 54.0
END DESCRIPTION:
XS GIS Cut Line= 2
      2152743.93     13196034.05      2154434.41     13195955.43
#Sta/Elev= 30
  4061.6  545.06  4104.7  544.29  4295.6  538.32  4355.7  536.85  4385.7  536.92
  4435.8  535.04  4471.3   534.6  4646.2  531.77  4726.1  530.93  4736.1  530.16
  4752.9  530.36  4796.2  528.91  4836.2  529.23  4876.3  528.58  4926.3  527.31
  5006.4  527.56  5026.2  526.53  5046.4  527.68  5096.5  528.66  5185.4  528.95
  5206.6  529.33  5236.7  528.44  5276.7  528.85  5286.7  528.24  5336.8  528.12
  5356.8  528.75  5376.8  528.07  5496.9  528.58    5567   527.6  5753.9  528.18
#Mann= 6 ,-1 , 0
  4061.6      .1       0  4471.3     .16       0  4646.2     .12       0
  4876.3     .07       0  5096.5     .12       0  5185.4      .1       0
Bank Sta=4876.3,5096.5
XS Rating Curve= 0 ,0
Exp/Cntr=0.3,0.1

Type RM Length L Ch R = 1 ,35193   ,676,676,676
BEGIN DESCRIPTION:
UNT 010 IN LACR 53.0
END DESCRIPTION:
XS GIS Cut Line= 3
      2153004.67     13196599.77      2153535.94     13196476.79
       2154632.8     13196043.95
#Sta/Elev= 30
  4044.8  547.48  4150.6  544.81  4181.4   543.1  4257.8  541.09  4273.8  539.86
  4376.4  536.41  4417.5  533.99  4433.8  534.11  4468.8  532.81  4476.5  531.67
  4489.3  532.47  4561.2     530  4630.2  528.69  4815.1  526.87  4925.2  526.07
    4955  525.37  5000.6  525.99  5009.1  525.44  5075.8  526.03  5092.9  525.28
  5129.6  525.72  5201.2  524.93  5206.6  525.54    5285  525.36  5363.5  524.74
  5368.7   524.1  5393.3  524.88  5555.6  525.72  5663.9  528.19  5769.3  529.31
#Mann= 4 ,-1 , 0
  4044.8      .1       0  4815.1     .12       0  4925.2     .07       0
  5000.6      .1       0
#XS Ineff= 2 , 0
                         5075.16          526.01
Permanent Ineff=
       F       F
Bank Sta=4925.2,5000.6
XS Rating Curve= 0 ,0
Exp/Cntr=0.3,0.1

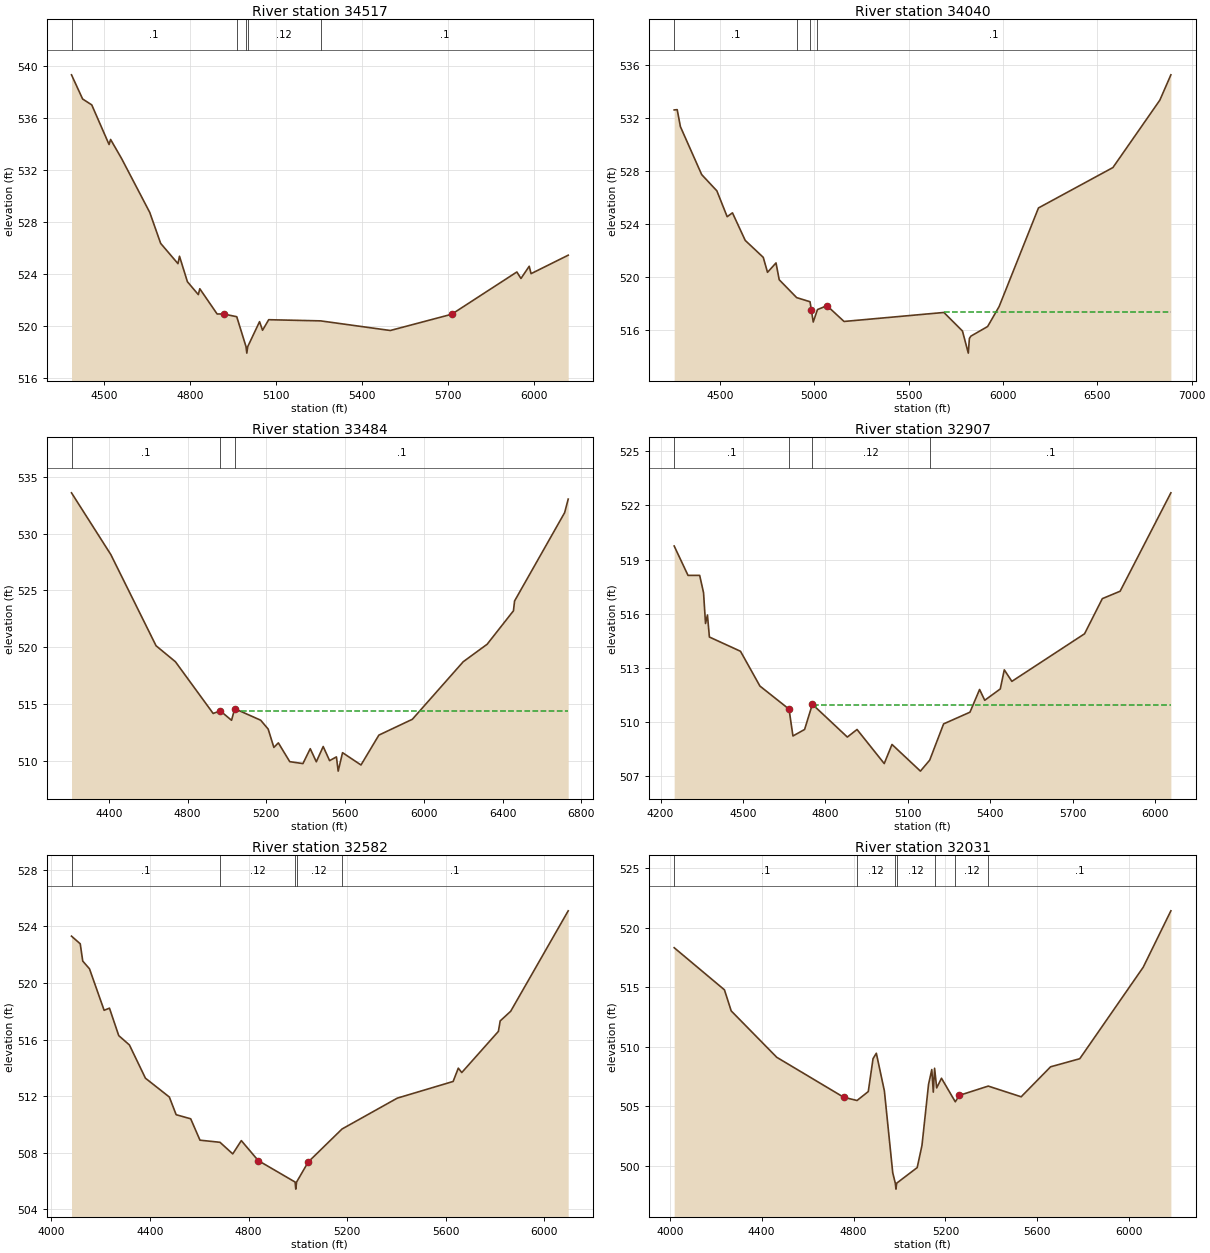
Type RM Length L Ch R = 1 ,34517   ,477,477,477
BEGIN DESCRIPTION:
UNT 010 IN LACR 52.0
END DESCRIPTION:
XS GIS Cut Line= 3
      2153250.62     13197131.06      2154234.49     13196830.99
      2154677.23     13196284.94
#Sta/Elev= 30
  4386.2  539.31    4425  537.45  4456.8     537  4517.2  533.95  4522.5  534.34
  4560.9  532.87    4659  528.73    4697  526.35  4757.4  524.79  4762.7  525.36
  4790.3   523.4  4828.3  522.41  4833.5  522.86  4893.9  520.92  4916.4  520.92
  4962.3  520.71  4994.6  518.41  4997.4  517.91  5000.6  518.41  5041.8  520.33
  5052.3  519.67  5073.7  520.48  5254.6  520.39  5497.6  519.65  5711.7   520.9
  5938.8  524.15  5953.1  523.65  5981.9  524.59  5988.3  524.02  6117.8  525.44
#Mann= 5 ,-1 , 0
  4386.2      .1       0  4962.3     .12       0  4994.6     .07       0
  5000.6     .12       0  5254.6      .1       0
Bank Sta=4916.4,5711.7
XS Rating Curve= 0 ,0
Exp/Cntr=0.3,0.1

Type RM Length L Ch R = 1 ,34040   ,556,556,556
BEGIN DESCRIPTION:
UNT 010 IN LACR 51.0
END DESCRIPTION:
XS GIS Cut Line= 3
      2153334.28     13197686.93      2155139.64     13196806.39
      2155611.87     13196398.11
#Sta/Elev= 30
    4257   532.6    4273  532.62    4290  531.34  4402.7  527.72  4483.3  526.49
  4537.9  524.54    4566  524.83  4633.6  522.75  4729.2  521.47  4751.8  520.34
  4796.8  521.05  4813.8  519.78  4906.3  518.43  4977.1  518.12    4984  517.52
  4994.1  516.59  5016.6  517.53  5067.2  517.82  5157.4  516.63  5686.7  517.31
  5785.1  515.91  5816.1  514.24  5821.9  515.35  5829.6  515.52  5918.6  516.25
  5979.6  517.76    6188   525.2  6582.7  528.25  6831.5  533.34  6889.9  535.25
#Mann= 4 ,-1 , 0
    4257      .1       0  4906.3     .12       0  4977.1     .07       0
  5016.6      .1       0
#XS Ineff= 2 , 0
       0                 5685.64       0  517.31
Permanent Ineff=
       F       T
Bank Sta=4984,5067.2
XS Rating Curve= 0 ,0
Exp/Cntr=0.3,0.1

Type RM Length L Ch R = 1 ,33484   ,577,577,577
BEGIN DESCRIPTION:
UNT 010 IN LACR 50.0
END DESCRIPTION:
XS GIS Cut Line= 3
      2153491.65     13198213.33      2155070.77     13197367.19
      2155723.86      13197038.2
#Sta/Elev= 30
  4210.3  533.57  4410.1  528.15  4639.8  520.15  4738.1  518.75  4929.8  514.21
    4966  514.44  5023.2  513.61  5039.4  514.63    5171  513.62  5209.2  512.84
  5238.2  511.23  5260.9  511.63  5318.9  509.98  5385.7  509.81  5422.9  511.12
  5453.8  509.97  5488.7  511.31  5521.2  510.07  5555.9   510.4  5564.8  509.15
    5587  510.77  5680.7  509.69  5771.5  512.31  5941.6   513.7    6200  518.75
  6321.2  520.28  6455.1  523.22  6460.7  524.08    6715  531.83  6733.1  533.02
#Mann= 3 , 0 , 0
  4210.3      .1       0    4966     .07       0  5039.4      .1       0
#XS Ineff= 2 , 0
       0                 5069.52       0  514.46
Permanent Ineff=
       F       T
Bank Sta=4966,5039.4
XS Rating Curve= 0 ,0
Exp/Cntr=0.3,0.1

Type RM Length L Ch R = 1 ,32907   ,325,325,325
BEGIN DESCRIPTION:
UNT 010 IN LACR 49.0
END DESCRIPTION:
XS GIS Cut Line= 4
      2154112.93     13198433.35      2154703.21     13197856.96
      2154998.35      13197738.9      2155532.92     13197343.18
#Sta/Elev= 30
  4249.5  519.75  4299.9  518.12  4342.3  518.12  4356.4  517.16  4363.6  515.45
  4370.6  515.92  4377.7   514.7  4490.9  513.91  4561.6  511.98  4667.6   510.7
  4681.8  509.21  4724.2  509.57  4752.5  510.97  4879.8  509.15  4915.1  509.57
  5014.1  507.68  5042.4  508.74  5145.8  507.26  5179.6  507.87  5230.2  509.88
  5326.2  510.53  5361.2  511.79    5380  511.19  5436.5  511.82  5451.1  512.88
  5478.7  512.24  5743.3  514.88    5808  516.83  5872.7  517.24  6057.5   522.7
#Mann= 4 ,-1 , 0
  4249.5      .1       0  4667.6     .07       0  4752.5     .12       0
  5179.6      .1       0
#XS Ineff= 2 , 0
       0                 4766.78       0  510.93
Permanent Ineff=
       F       T
Bank Sta=4667.6,4752.5
XS Rating Curve= 0 ,0
Exp/Cntr=0.3,0.1

Type RM Length L Ch R = 1 ,32582   ,551,551,551
BEGIN DESCRIPTION:
UNT 010 IN LACR 48.0
END DESCRIPTION:
XS GIS Cut Line= 3
       2154037.7     13198546.87      2154837.72     13198096.85
      2155637.73     13197346.85
#Sta/Elev= 30
  4082.1  523.31  4117.5  522.77  4127.7  521.55  4155.1     521  4214.4  518.07
  4236.1  518.22  4273.7  516.28    4317  515.62    4382  513.27  4478.9  511.94
  4506.6  510.69  4565.6   510.4  4603.2  508.89  4684.3  508.74  4736.1  507.92
  4770.8  508.86  4839.4  507.45    4989  505.93  4991.8  505.43    4995  505.93
  5042.3  507.35  5179.4  509.68  5403.2  511.86  5629.9  513.04  5650.9  513.98
    5665  513.67  5813.5  516.58  5820.8  517.32  5863.3     518  6096.6   525.1
#Mann= 5 ,-1 , 0
  4082.1      .1       0  4684.3     .12       0    4989     .07       0
    4995     .12       0  5179.4      .1       0
Bank Sta=4839.4,5042.3
XS Rating Curve= 0 ,0
Exp/Cntr=0.3,0.1

Type RM Length L Ch R = 1 ,32031   ,273,273,273
BEGIN DESCRIPTION:
UNT 010 IN LACR 47.0
END DESCRIPTION:
XS GIS Cut Line= 4
      2154154.08     13198976.15       2154924.1     13198662.11
      2155154.09     13198465.73      2155837.74     13197696.83
#Sta/Elev= 30
    4019  518.32  4237.9  514.78  4267.3  513.01  4465.7  509.11  4757.3  505.75
  4815.3  505.48  4864.2  506.23    4885     509  4899.3  509.45  4934.4  506.28
  4970.7  499.41  4981.9  498.53  4984.7  498.03  4987.9  498.53  5077.2  499.84
    5098   501.7  5126.6  506.83  5140.8  508.08  5147.4  506.18  5152.9  508.19
  5162.1  506.54    5183  507.35  5243.1  505.37  5260.8  505.91  5386.6  506.69
    5530  505.79    5658  508.31  5785.1  508.99  6061.4  516.68  6181.9  521.42
#Mann= 7 ,-1 , 0
    4019      .1       0  4815.3     .12       0  4981.9     .07       0
  4987.9     .12       0  5152.9     .05       0  5243.1     .12       0
  5386.6      .1       0
Bank Sta=4757.3,5260.8
XS Rating Curve= 0 ,0
Exp/Cntr=0.3,0.1

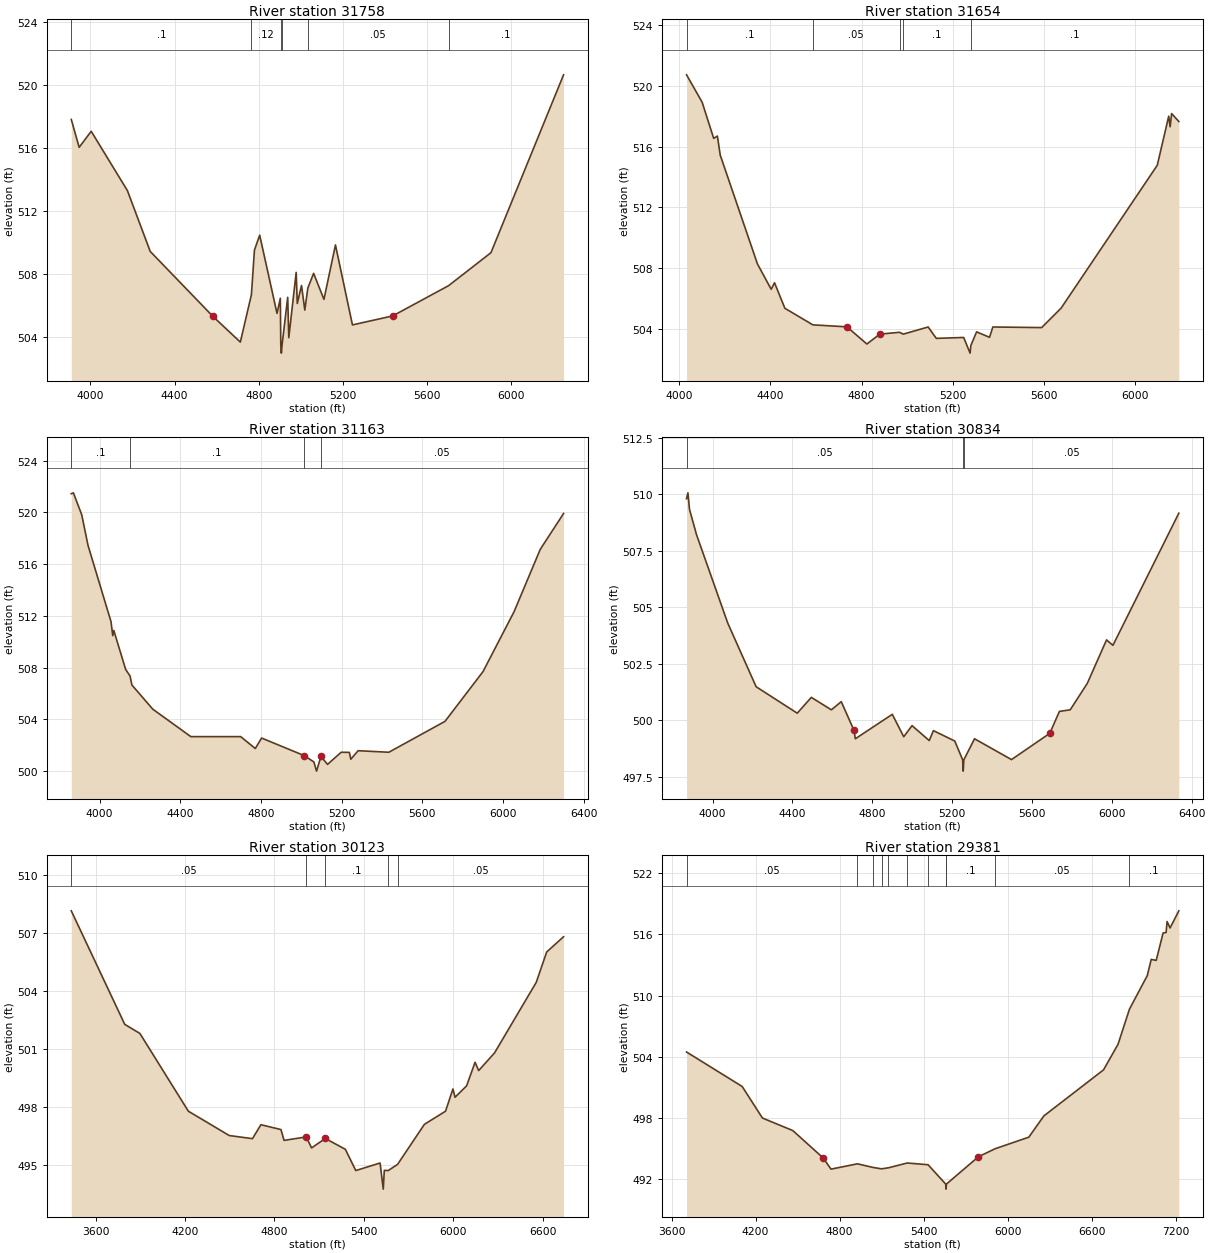
Type RM Length L Ch R = 1 ,31758   ,104,104,104
BEGIN DESCRIPTION:
UNT 010 IN LACR 46.0
END DESCRIPTION:
XS GIS Cut Line= 6
      2154294.68     13199184.51      2155018.67     13198710.53
      2155237.72     13198696.86      2155263.46     13198590.73
       2155221.8     13198554.28      2155966.57     13197767.83
#Sta/Elev= 30
  3908.7   517.8  3946.1  516.03  4003.4  517.05  4175.3  513.29  4283.8  509.43
  4581.7  505.31    4712  503.68  4764.6  506.69    4779  509.52  4803.9  510.46
  4886.2   505.5    4902  506.46  4904.1  503.48  4906.9  502.98  4910.1  503.48
    4937  506.52  4942.2  503.96  4977.3   508.1  4982.5  506.13  5002.6  507.27
  5018.3  505.71  5032.6   507.1  5060.1  508.04  5109.2  506.39  5163.9  509.84
  5244.6  504.77  5435.9  505.34  5701.6  507.26  5902.7  509.35  6247.7  520.63
#Mann= 6 ,-1 , 0
  3908.7      .1       0  4764.6     .12       0  4904.1     .07       0
  4910.1     .12       0  5032.6     .05       0  5701.6      .1       0
Bank Sta=4581.7,5435.9
XS Rating Curve= 0 ,0
Exp/Cntr=0.3,0.1

Type RM Length L Ch R = 1 ,31654   ,491,491,491
BEGIN DESCRIPTION:
Mapping XS 2f4e9191
END DESCRIPTION:
XS GIS Cut Line= 4
      2154487.45      13199267.8      2155169.71     13198903.23
      2155560.34     13198538.65      2156075.87     13197861.69
#Sta/Elev= 30
  4032.3  520.72  4100.6  518.92  4151.3  516.54  4167.6  516.69    4180  515.44
  4343.2  508.28  4403.4  506.61  4418.1  507.04  4463.5  505.36  4586.2  504.27
  4735.6  504.14  4823.1  503.01  4879.8  503.66  4966.4  503.78  4982.9  503.66
  5091.8  504.13  5127.5  503.38  5247.6  503.44  5275.7  502.41    5279  502.91
  5304.3  503.81    5361  503.45  5375.5  504.13  5589.6  504.09  5674.9  505.37
  6096.6  514.77  6146.8     518    6153   517.3  6159.5  518.17  6191.1  517.65
#Mann= 5 ,-1 , 0
  4032.3      .1       0  4586.2     .05       0  4966.4     .12       0
  4982.9      .1       0    5279      .1       0
Bank Sta=4735.6,4879.8
XS Rating Curve= 0 ,0
Exp/Cntr=0.3,0.1

Type RM Length L Ch R = 1 ,31163   ,329,329,329
BEGIN DESCRIPTION:
UNT 010 IN LACR 45.0
END DESCRIPTION:
XS GIS Cut Line= 3
       2154587.7     13199346.86      2155687.72     13199046.86
      2156187.72     13197846.85
#Sta/Elev= 30
  3859.8  521.45  3870.2  521.52  3911.7  519.82  3942.7  517.46  4056.8  511.55
  4065.4  510.47  4070.6  510.87  4129.3  507.86  4151.1  507.35  4160.4  506.65
  4264.1  504.78  4452.4  502.66  4699.4  502.66    4772  501.74  4803.1  502.55
  5014.6  501.19  5062.3   500.7  5075.6  499.99  5097.5  501.13    5130  500.51
  5197.7  501.45  5238.3  501.44  5245.4  500.91  5281.7  501.57  5433.9  501.45
  5712.3  503.84  5900.8  507.69  6054.6  512.32  6184.6  517.15    6300  519.92
#Mann= 4 ,-1 , 0
  3859.8      .1       0  4151.1      .1       0  5014.6     .03       0
  5097.5     .05       0
#XS Ineff= 2 , 0
         4803.12  502.54
Permanent Ineff=
       F       F
Bank Sta=5014.6,5097.5
XS Rating Curve= 0 ,0
Exp/Cntr=0.3,0.1

Type RM Length L Ch R = 1 ,30834   ,711,711,711
BEGIN DESCRIPTION:
UNT 010 IN LACR 44.0
END DESCRIPTION:
XS GIS Cut Line= 3
       2155024.7     13199974.06      2156434.43     13198821.27
      2156663.16     13198218.26
#Sta/Elev= 30
  3869.9   509.8  3876.8  510.06  3884.7  509.33  3919.9  508.21  4076.4   504.3
  4218.5  501.49  4424.5  500.32  4494.9  501.02  4595.4  500.47  4644.9  500.83
  4708.8  499.56  4715.3  499.19  4900.5  500.27  4957.9  499.28  4999.5  499.77
  5085.7  499.11  5106.5  499.55  5213.5  499.09    5253  498.26  5255.8  497.76
    5259  498.26  5312.5  499.19  5497.7  498.27  5689.4  499.43  5737.8   500.4
  5791.9  500.47  5877.5  501.64  5973.8  503.56  6005.8  503.32  6335.9  509.16
#Mann= 3 ,-1 , 0
  3869.9     .05       0    5253     .03       0    5259     .05       0
Bank Sta=4708.8,5689.4
XS Rating Curve= 0 ,0
Exp/Cntr=0.3,0.1

Type RM Length L Ch R = 1 ,30123   ,742,742,742
BEGIN DESCRIPTION:
UNT 010 IN LACR 43.0
END DESCRIPTION:
XS GIS Cut Line= 4
      2155024.68     13200439.34      2155823.32      13200293.5
      2157108.04     13198862.94      2157087.21     13198293.53
#Sta/Elev= 30
  3436.8  508.15  3795.7  502.28  3897.3  501.81  4222.6  497.79  4497.5  496.53
    4653  496.37  4709.8  497.09  4844.3  496.84  4865.2  496.28    5014  496.46
  5049.9  495.89  5141.8  496.38  5276.4  495.82  5346.6  494.72  5509.6  495.11
    5531  493.76    5538  494.73  5564.3  494.72  5627.1  495.04  5807.1  497.11
  5949.1  497.79  5998.5  498.94  6012.7  498.51  6090.4   499.1  6147.2  500.32
  6171.4  499.89  6277.6   500.8  6557.8  504.45  6627.8  506.02  6741.2  506.81
#Mann= 5 ,-1 , 0
  3436.8     .05       0    5014     .03       0  5141.8      .1       0
  5564.3      .1       0  5627.1     .05       0
Bank Sta=5014,5141.8
XS Rating Curve= 0 ,0
Exp/Cntr=0.3,0.1

Type RM Length L Ch R = 1 ,29381   ,667,667,667
BEGIN DESCRIPTION:
UNT 010 IN LACR 42.0
END DESCRIPTION:
XS GIS Cut Line= 4
      2155670.53     13200904.61      2156344.15     13200744.89
      2157677.49     13198765.72      2157982.87      13198453.4
#Sta/Elev= 30
  3707.2  504.46  4104.6  501.08    4249  497.99    4466  496.76  4681.9  494.09
  4738.9  492.98  4927.6   493.5    5041  493.14  5099.4  493.01  5148.6  493.11
  5283.3  493.58    5432  493.41  5557.5  491.52  5560.2  491.02  5563.5  491.52
  5791.4  494.19  5910.9  494.98  6151.2  496.11  6259.2   498.2    6685  502.71
  6788.6  505.22  6870.1  508.66  6997.4  511.95  7025.6  513.54  7061.1  513.44
  7110.5  516.13  7131.8  516.17  7138.8  517.25  7160.1  516.62  7222.7   518.3
#Mann= 11 ,-1 , 0
  3707.2     .05       0  4927.6      .1       0    5041     .05       0
  5099.4      .1       0  5148.6     .12       0  5283.3     .05       0
    5432      .1       0  5557.5     .07       0  5563.5      .1       0
  5910.9     .05       0  6870.1      .1       0
Bank Sta=4681.9,5791.4
XS Rating Curve= 0 ,0
Exp/Cntr=0.3,0.1

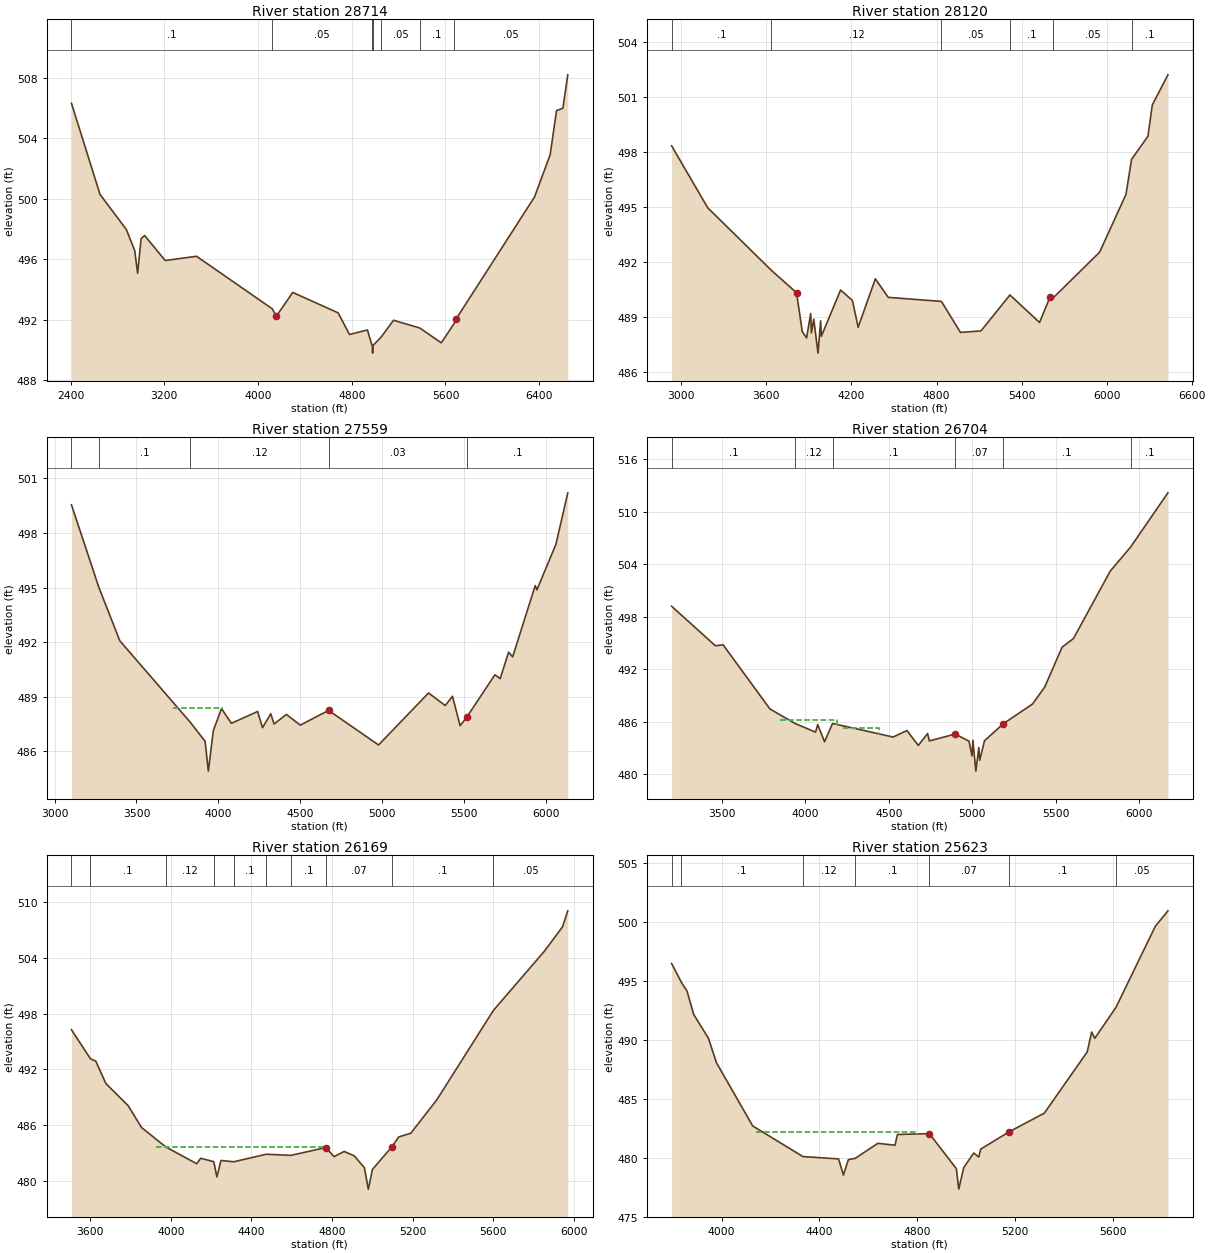
Type RM Length L Ch R = 1 ,28714   ,594,594,594
BEGIN DESCRIPTION:
Mapping XS cdf12c70
END DESCRIPTION:
XS GIS Cut Line= 3
      2156239.97     13202814.38      2156983.04     13200862.94
      2157898.94     13198920.13
#Sta/Elev= 30
  2407.9   506.3  2651.4  500.28  2876.1  497.96  2947.6  496.57  2972.3  495.07
  3002.4  497.36  3032.5  497.56  3207.8  495.91  3475.3  496.19  4121.4  492.72
  4156.3  492.23  4296.1   493.8    4684  492.45  4780.7  491.02  4933.9  491.32
  4971.4  490.34  4975.1  490.29  4977.9  489.79  4981.1  490.29  5051.7  490.86
  5156.2  491.96  5380.8  491.45  5564.1  490.47  5674.3  491.75  5691.2  492.05
  6360.1  500.11  6493.4   502.9    6548  505.82  6601.8  505.97  6643.9  508.18
#Mann= 8 ,-1 , 0
  2407.9      .1       0  4121.4     .05       0  4971.4      .1       0
  4975.1     .07       0  4981.1      .1       0  5051.7     .05       0
  5380.8      .1       0  5674.3     .05       0
#XS Ineff= 2 , 0
         4295.45  493.79
Permanent Ineff=
       F       F
Bank Sta=4156.3,5691.2
XS Rating Curve= 0 ,0
Exp/Cntr=0.3,0.1

Type RM Length L Ch R = 1 ,28120   ,561,561,561
BEGIN DESCRIPTION:
UNT 010 IN LACR 40.0
END DESCRIPTION:
XS GIS Cut Line= 3
      2157371.93     13202689.32      2157635.82     13200862.94
      2158052.07     13199260.36
#Sta/Elev= 30
  2931.4  498.33  3186.5  494.95  3635.7  491.54  3812.9  490.32  3853.3   488.2
  3883.7  487.86  3912.4  489.19  3917.5  488.13  3934.2  488.88  3964.2  487.03
  3982.7  488.79  3987.8  487.95  4123.4  490.47    4207   489.9  4247.4  488.44
  4368.6  491.08  4459.6  490.07  4834.7  489.85    4969  488.16  5113.6  488.24
  5318.2   490.2  5526.9   488.7  5602.1  490.11  5622.9  490.04  5950.5  492.53
  6136.5  495.68    6176  497.59  6291.5  498.85  6322.5  500.56  6432.5   502.2
#Mann= 6 ,-1 , 0
  2931.4      .1       0  3635.7     .12       0  4834.7     .05       0
  5318.2      .1       0  5622.9     .05       0    6176      .1       0
#XS Ineff= 2 , 0
         4368.18  491.05
Permanent Ineff=
       F       F
Bank Sta=3812.9,5602.1
XS Rating Curve= 0 ,0
Exp/Cntr=0.3,0.1

Type RM Length L Ch R = 1 ,27559   ,855,855,855
BEGIN DESCRIPTION:
UNT 010 IN LACR 39.0
END DESCRIPTION:
XS GIS Cut Line= 3
      2157989.99     13202480.98       2158101.1     13201064.33
      2158406.57     13199481.44
#Sta/Elev= 30
  3102.9  499.55  3269.4  495.03  3398.3  492.07  3828.9  487.59  3919.5  486.54
  3939.3   484.9  3969.7  487.13  4019.8  488.34    4080  487.53  4240.5  488.18
  4270.6  487.29  4320.8  488.06  4340.8  487.49  4416.4  488.02  4501.3  487.43
  4674.1  488.24  4979.6  486.34  5285.2   489.2    5387  488.51  5431.2  489.02
    5478   487.4  5519.4  487.88  5690.5   490.2  5723.1  489.99    5774  491.44
  5799.3  491.19    5937  495.11  5947.2  494.87  6063.6  497.38    6136  500.21
#Mann= 5 ,-1 , 0
  3102.9     .05       0  3269.4      .1       0  3828.9     .12       0
  4674.1     .03       0  5519.4      .1       0
#XS Ineff= 1 ,-1
 3721.88 4020.17  488.35
Permanent Ineff=
       T
Bank Sta=4674.1,5519.4
XS Rating Curve= 0 ,0
Exp/Cntr=0.3,0.1

Type RM Length L Ch R = 1 ,26704   ,535,535,535
BEGIN DESCRIPTION:
UNT 010 IN LACR 38.0
END DESCRIPTION:
XS GIS Cut Line= 3
      2158496.92     13202592.14      2159156.65     13200008.77
       2159163.6     13199703.23
#Sta/Elev= 30
  3198.7  499.21  3460.8  494.69  3506.8   494.8  3787.6  487.46  3937.8   485.8
  4060.8  484.81  4073.6  485.68  4114.4  483.71  4162.4   485.8  4525.2  484.25
  4607.8  484.99    4676  483.29  4731.7  484.65    4742   483.8  4896.8  484.59
  4979.4  483.78  4997.6   482.1  5002.8  483.88  5020.4  480.35  5038.5  483.06
  5043.6  481.59  5072.2  483.82  5185.8  485.78  5360.1  488.03  5433.5  489.99
  5536.7  494.52  5605.2  495.52  5825.7  503.24  5947.3  505.98  6170.6  512.18
#Mann= 6 ,-1 , 0
  3198.7      .1       0  3937.8     .12       0  4162.4      .1       0
  4896.8     .07       0  5185.8      .1       0  5947.3      .1       0
#XS Ineff= 2 ,-1
 3847.16 4191.19  486.25 4225.06 4441.98  485.25
Permanent Ineff=
       T       T
Bank Sta=4896.8,5185.8
XS Rating Curve= 0 ,0
Exp/Cntr=0.3,0.1

Type RM Length L Ch R = 1 ,26169   ,546,546,546
BEGIN DESCRIPTION:
UNT 010 IN LACR 36.0
END DESCRIPTION:
XS GIS Cut Line= 4
      2159367.28     13202587.39      2159318.67     13201420.76
        2159402.     13200386.04      2159408.91     13200130.45
#Sta/Elev= 30
  3507.4  496.25  3601.7  493.13    3628  492.88  3678.1  490.47  3788.2   488.1
  3855.1  485.74  3974.1  483.67  4128.5  481.85  4148.5  482.44  4213.1  482.07
  4228.6  480.43  4248.6   482.2  4312.1  482.06  4473.1  482.87  4595.2  482.75
  4769.3  483.59  4809.4  482.61  4859.5  483.17  4909.7   482.7  4959.9  481.43
  4979.7  479.12    5000  481.24  5097.3  483.69  5130.4  484.73  5190.6  485.13
    5321  488.78  5599.4  498.32  5852.4  504.69  5942.4  507.31  5968.8  509.04
#Mann= 10 ,-1 , 0
  3507.4     .05       0  3601.7      .1       0  3974.1     .12       0
  4213.1     .16       0  4312.1      .1       0  4473.1     .16       0
  4595.2      .1       0  4769.3     .07       0  5097.3      .1       0
  5599.4     .05       0
#XS Ineff= 1 ,-1
 3924.72 4768.47  483.69
Permanent Ineff=
       T
Bank Sta=4769.3,5097.3
XS Rating Curve= 0 ,0
Exp/Cntr=0.3,0.1

Type RM Length L Ch R = 1 ,25623   ,442,442,442
BEGIN DESCRIPTION:
UNT 010 IN LACR 35.0
END DESCRIPTION:
XS GIS Cut Line= 3
      2159887.72      13202546.9      2159787.72     13201346.86
      2159587.73     13200546.88
#Sta/Elev= 30
  3795.8  496.46  3836.2  494.85  3858.6  494.13  3886.2  492.14  3946.4  490.12
    3979  488.06    4127   482.7  4332.3   480.1  4478.2   479.9  4498.3  478.53
  4518.3  479.84  4546.5  479.95  4638.8  481.22    4709  481.06    4719  481.97
  4849.5  482.04  4959.9  479.07  4969.6  477.34    4990  479.17  5030.9   480.4
  5051.5  480.06  5059.3  480.73  5175.2  482.19  5319.5  483.78  5494.8  488.97
  5512.8  490.65  5525.7  490.12  5612.5  492.75  5773.1  499.61  5824.6  500.92
#Mann= 7 ,-1 , 0
  3795.8     .05       0  3836.2      .1       0  4332.3     .12       0
  4546.5      .1       0  4849.5     .07       0  5175.2      .1       0
  5612.5     .05       0
#XS Ineff= 1 ,-1
  4139.2 4798.79  482.19
Permanent Ineff=
       T
Bank Sta=4849.5,5175.2
XS Rating Curve= 0 ,0
Exp/Cntr=0.3,0.1

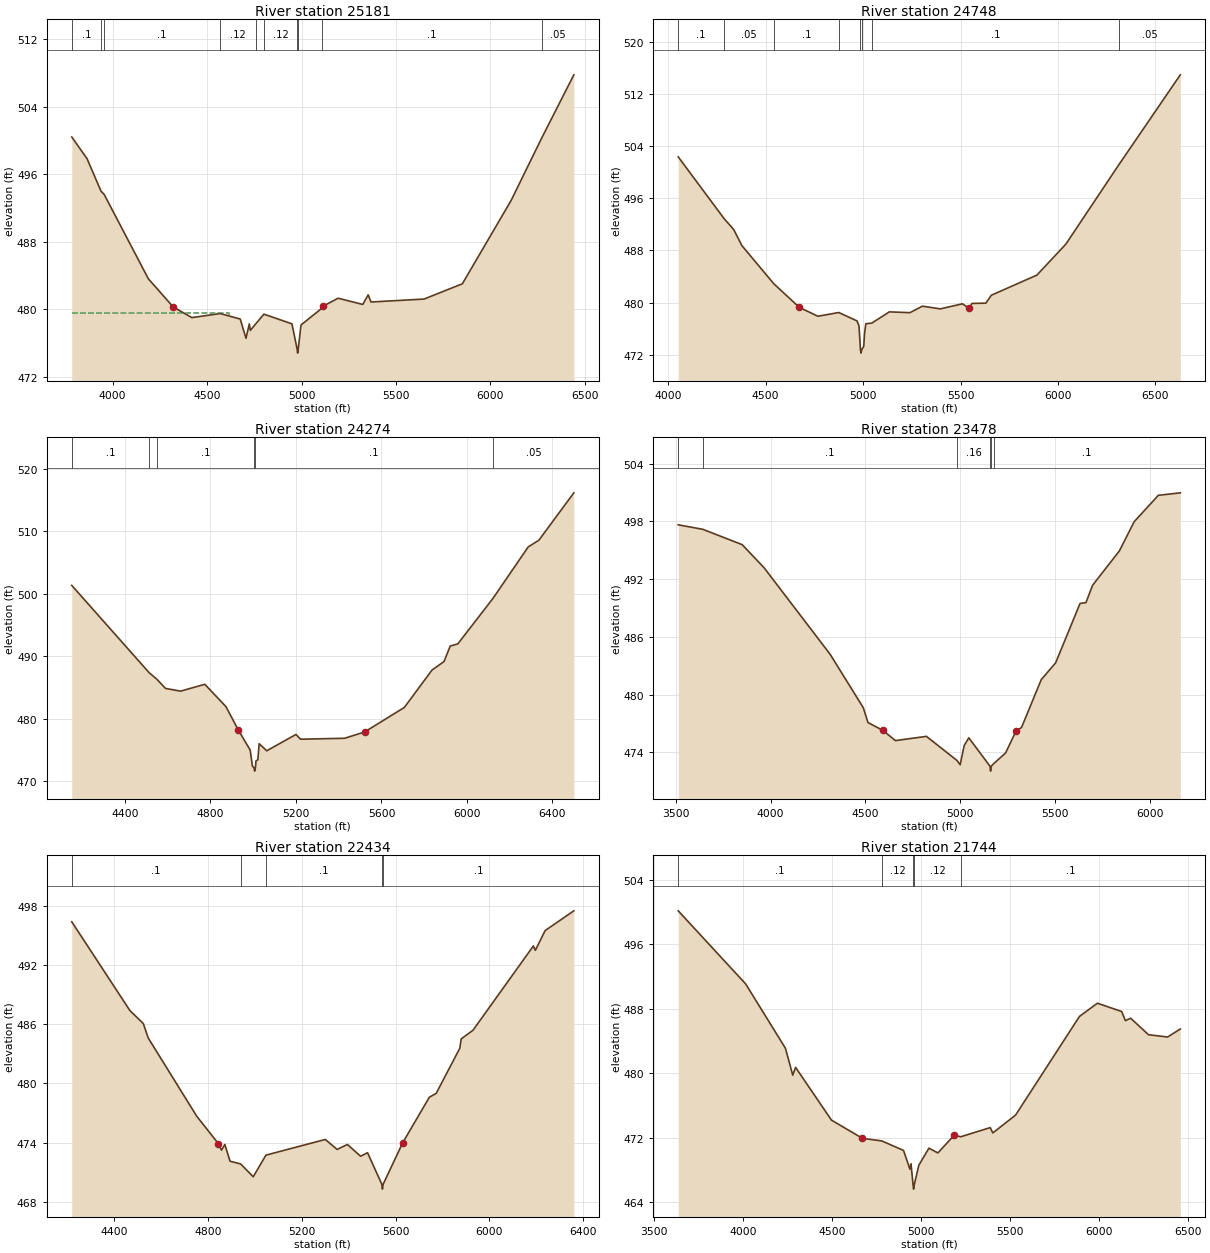
Type RM Length L Ch R = 1 ,25181   ,433,433,433
BEGIN DESCRIPTION:
UNT 010 IN LACR 34.0
END DESCRIPTION:
XS GIS Cut Line= 3
      2159987.71      13202646.9      2160187.72     13201446.85
       2161387.7     13200646.87
#Sta/Elev= 30
  3783.4  500.43  3864.6  497.85  3938.5     494  3954.6  493.64    4189  483.62
  4320.8  480.28  4419.6  479.02  4569.4   479.5  4675.6  478.85    4706  476.57
  4723.7  478.28  4728.8   477.5  4761.4  478.38  4800.9  479.43  4949.3  478.28
  4976.7  475.31  4979.5  474.81  4982.7  475.31  4997.5  478.15  5109.6  480.16
  5115.7  480.39  5193.8  481.32  5324.5  480.58    5353  481.72  5368.1  480.87
    5649  481.22  5851.8  483.03  6110.2  492.91  6271.2  500.27  6442.2   507.8
#Mann= 10 ,-1 , 0
  3783.4      .1       0  3938.5     .05       0  3954.6      .1       0
  4569.4     .12       0  4761.4      .1       0  4800.9     .12       0
  4976.7     .07       0  4982.7     .12       0  5109.6      .1       0
  6271.2     .05       0
#XS Ineff= 2 , 0
          4614.6  479.52
Permanent Ineff=
       F       F
Bank Sta=4320.8,5115.7
XS Rating Curve= 0 ,0
Exp/Cntr=0.3,0.1

Type RM Length L Ch R = 1 ,24748   ,474,474,474
BEGIN DESCRIPTION:
UNT 010 IN LACR 33.0
END DESCRIPTION:
XS GIS Cut Line= 3
      2160087.72     13202696.87      2160387.72     13201796.85
      2161587.73     13200696.84
#Sta/Elev= 30
  4051.3  502.38  4287.2  492.87  4335.9  491.22  4378.1  488.74  4541.8  482.88
  4673.2  479.24  4768.1  477.89  4875.2  478.46  4968.4  477.18  4978.9  476.42
  4986.5  472.72  4989.2  472.22  4992.5  472.72  5003.4  473.27  5007.1  475.14
  5013.9  476.73  5044.9  476.84  5134.7  478.56  5240.8  478.44  5304.3  479.44
  5396.2  479.02  5509.6   479.8  5544.8  479.11    5559  479.86  5629.9   479.9
  5658.2  481.12  5891.9  484.21  6040.5  488.97    6312  501.15  6627.9  514.99
#Mann= 8 ,-1 , 0
  4051.3      .1       0  4287.2     .05       0  4541.8      .1       0
  4875.2     .12       0  4986.5     .07       0  4992.5     .12       0
  5044.9      .1       0    6312     .05       0
Bank Sta=4673.2,5544.8
XS Rating Curve= 0 ,0
Exp/Cntr=0.3,0.1

Type RM Length L Ch R = 1 ,24274   ,796,796,796
BEGIN DESCRIPTION:
UNT 010 IN LACR 32.0
END DESCRIPTION:
XS GIS Cut Line= 3
      2160137.74     13202696.84      2160737.72     13202096.85
      2161937.72     13201196.85
#Sta/Elev= 30
  4151.5  501.35  4513.7  487.34  4550.4  486.27  4589.9  484.83  4660.6  484.39
  4773.7  485.49  4872.7  481.91  4929.3  478.23  4985.9  474.95  4996.5  472.39
  5004.3  472.06    5007  471.56  5010.3  472.06  5013.5  473.23  5021.9  473.37
  5028.1  475.96  5063.5  474.82    5200  477.44  5221.9  476.68  5428.1  476.83
  5521.9  477.85  5707.3  481.78  5836.5  487.77  5892.7  489.14  5921.9  491.63
  5957.3  491.97  6121.4  499.25  6286.5  507.52  6336.5   508.6    6500   516.2
#Mann= 6 ,-1 , 0
  4151.5      .1       0  4513.7     .05       0  4550.4      .1       0
  5004.3     .07       0  5010.3      .1       0  6121.4     .05       0
Bank Sta=4929.3,5521.9
XS Rating Curve= 0 ,0
Exp/Cntr=0.3,0.1

Type RM Length L Ch R = 1 ,23478   ,1044,1044,1044
BEGIN DESCRIPTION:
UNT 010 IN LACR 30.0
END DESCRIPTION:
XS GIS Cut Line= 4
        2159816.     13203007.48      2160456.19     13202898.97
      2161834.23     13202367.29      2162192.28     13201987.54
#Sta/Elev= 30
    3513  497.64  3642.9  497.17  3850.2  495.58  3965.8  493.18    4314   484.2
  4489.3  478.64  4513.9   477.1  4592.7  476.29  4658.4  475.23  4822.1  475.67
  4983.8  473.16    5000  472.72  5021.4  474.72  5045.8  475.52  5157.8  472.56
  5160.5  472.06  5163.8  472.56  5177.1  472.84  5239.5  473.94    5294  476.19
    5324   476.6  5427.8  481.56  5503.8  483.31  5632.4  489.47  5663.5  489.56
  5698.6  491.36  5840.3  494.94  5917.9  497.96  6045.4   500.7  6161.3  500.96
#Mann= 6 ,-1 , 0
    3513     .05       0  3642.9      .1       0  4983.8     .16       0
  5157.8     .07       0  5163.8     .16       0  5177.1      .1       0
Bank Sta=4592.7,5294
XS Rating Curve= 0 ,0
Exp/Cntr=0.3,0.1

Type RM Length L Ch R = 1 ,22434   ,690,690,690
BEGIN DESCRIPTION:
UNT 010 IN LACR 29.0
END DESCRIPTION:
XS GIS Cut Line= 3
      2160787.74     13203996.84      2161287.72     13203396.85
      2162087.69     13202296.89
#Sta/Elev= 30
    4219  496.37    4467  487.38  4524.2  486.06  4545.1   484.6    4752  476.68
  4843.8  473.92  4857.5  473.25  4871.8  473.82  4893.9  472.13  4939.2  471.85
  4992.8  470.55    5047  472.74  5300.2  474.33  5350.5  473.32  5394.5  473.82
  5450.9  472.63  5480.3  472.99  5541.1   469.8  5543.8   469.3  5547.1   469.8
  5630.6  474.01  5743.8   478.6  5773.2     479  5873.7  483.56  5879.8  484.51
  5930.1  485.39  6187.4  493.92  6195.9  493.48  6237.7  495.48  6360.1  497.48
#Mann= 5 ,-1 , 0
    4219      .1       0  4939.2     .12       0    5047      .1       0
  5541.1     .07       0  5547.1      .1       0
Bank Sta=4843.8,5630.6
XS Rating Curve= 0 ,0
Exp/Cntr=0.3,0.1

Type RM Length L Ch R = 1 ,21744   ,564,564,564
BEGIN DESCRIPTION:
UNT 010 IN LACR 28.0
END DESCRIPTION:
XS GIS Cut Line= 3
      2160760.02     13204287.86      2161573.82     13204005.75
      2162712.51     13202411.57
#Sta/Elev= 30
  3636.2  500.15  4014.8  491.09  4238.5   483.1  4279.4  479.77  4295.5  480.73
  4496.9  474.19    4671  471.93  4779.7  471.61  4901.7  470.43  4937.7  468.11
  4943.8  468.77  4955.6  466.13  4958.3  465.63  4961.6  466.13  4987.7  468.59
  5044.6  470.71    5095  470.12  5187.1  472.34  5222.7  472.12  5388.7  473.26
  5403.4   472.6  5531.2  474.81  5890.1  487.05  5990.8  488.69  6127.3  487.66
  6148.1  486.53  6177.6  486.83  6278.1  484.78  6385.3   484.5  6456.6  485.49
#Mann= 5 ,-1 , 0
  3636.2      .1       0  4779.7     .12       0  4955.6     .07       0
  4961.6     .12       0  5222.7      .1       0
Bank Sta=4671,5187.1
XS Rating Curve= 0 ,0
Exp/Cntr=0.3,0.1