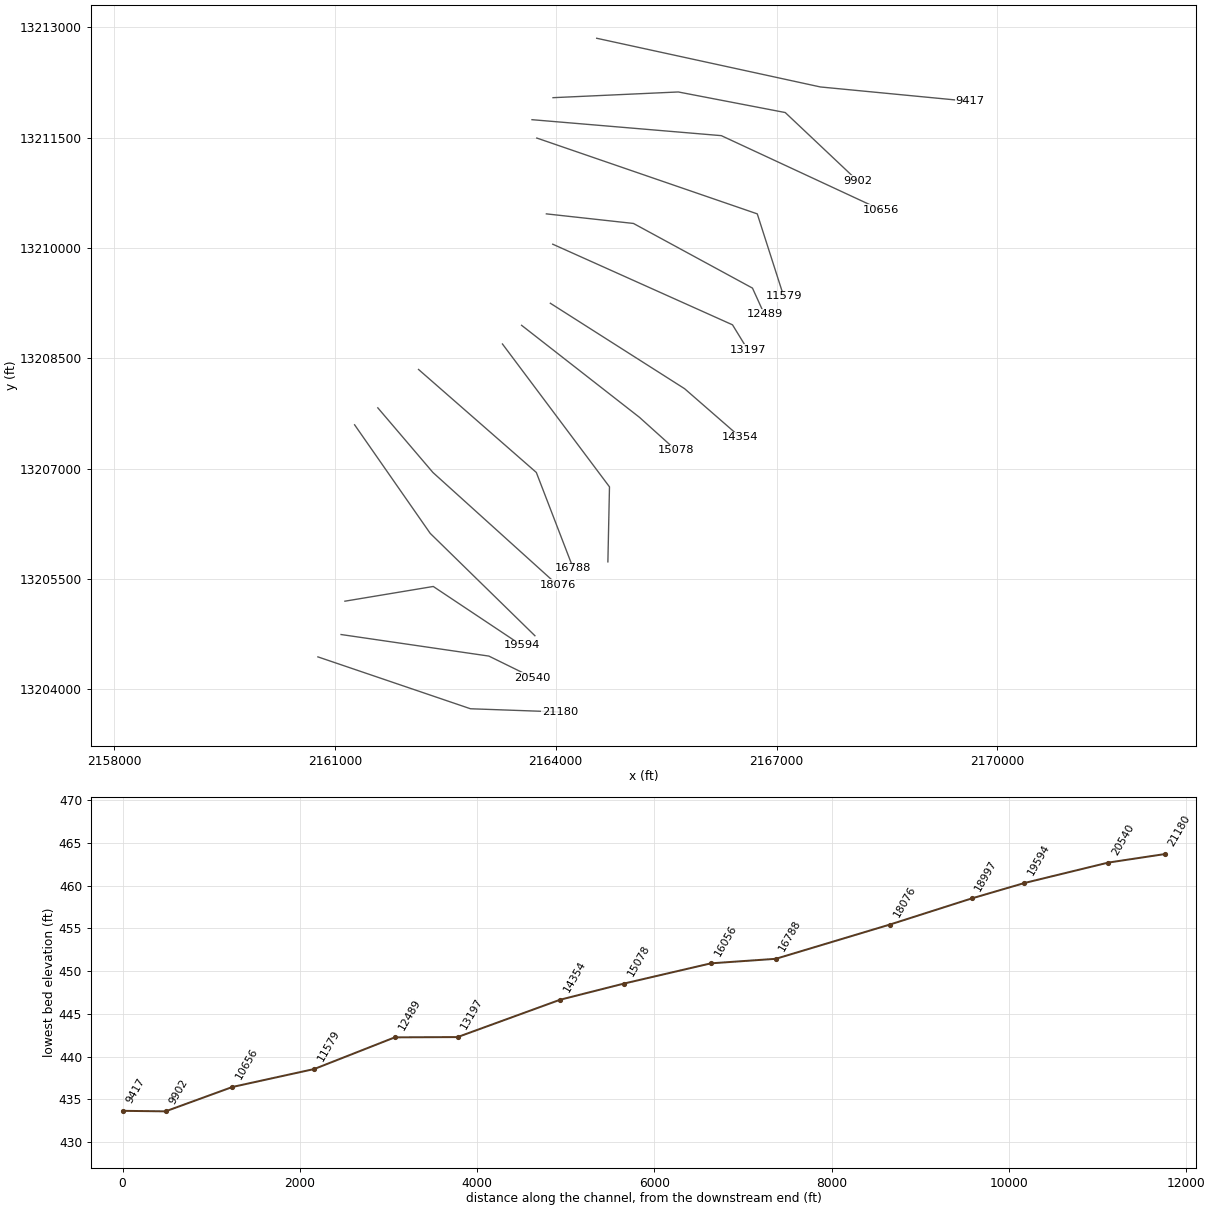
HEC-RAS study UNT 010 IN LACR.prj: UNT 010 IN LACR Base Level Engineering

--- UNT 010 IN LACR.g01 (geometry) --- (continued)

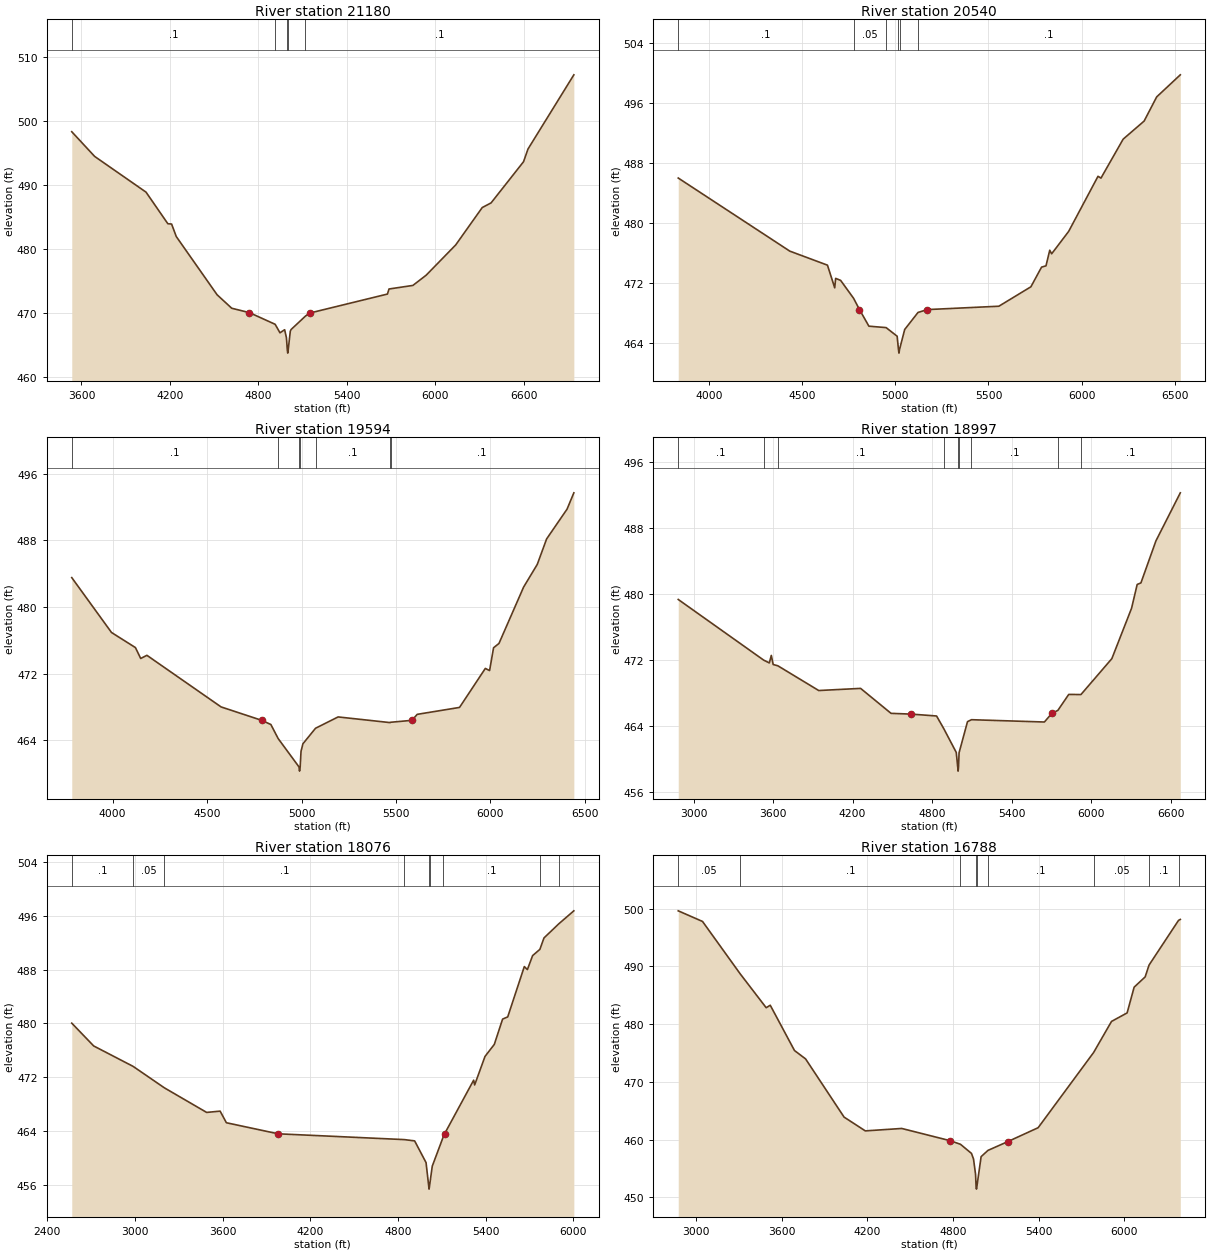
Type RM Length L Ch R = 1 ,21180   ,640,640,640
BEGIN DESCRIPTION:
UNT 010 IN LACR 26.0
END DESCRIPTION:
XS GIS Cut Line= 3
      2160770.88     13204439.77      2162843.35     13203734.48
      2164058.58     13203691.08
#Sta/Elev= 30
  3534.3  498.33  3689.4  494.47    4038  488.88  4185.9  483.94  4211.5  483.89
  4242.9  481.94  4519.9  472.83  4619.2  470.72  4739.4  470.03  4913.6  468.21
  4946.4  466.88  4978.1  467.36  4990.3   466.1  4996.2   464.2    4999   463.7
  5002.2   464.2  5016.4  467.12  5021.7  467.39  5118.6  469.48  5147.1  469.96
  5675.3  472.94  5685.9  473.73  5847.9  474.29    5938  475.89  6138.1  480.62
  6318.2  486.47  6378.3   487.2  6598.4  493.64  6628.4  495.62  6939.5  507.23
#Mann= 5 ,-1 , 0
  3534.3      .1       0  4913.6     .12       0  4996.2     .07       0
  5002.2     .12       0  5118.6      .1       0
Bank Sta=4739.4,5147.1
XS Rating Curve= 0 ,0
Exp/Cntr=0.3,0.1

Type RM Length L Ch R = 1 ,20540   ,946,946,946
BEGIN DESCRIPTION:
UNT 010 IN LACR 24.0
END DESCRIPTION:
XS GIS Cut Line= 3
      2161085.53     13204743.59      2163092.91     13204450.62
      2163689.73     13204157.64
#Sta/Elev= 30
  3835.6  486.03  4434.1  476.29  4636.2  474.42  4675.1   471.4  4680.1  472.66
  4706.9  472.39  4776.2  470.01    4808   468.5  4858.5  466.29  4950.7   466.1
  5010.1  464.95    5017   463.2  5019.7   462.7    5023   463.2  5050.5  465.85
    5122  468.12  5171.8   468.5  5555.8  468.95  5727.6  471.54  5784.8  474.16
  5808.5  474.33  5828.7  476.41  5838.8  475.93  5930.2  478.92  6087.6  486.26
  6103.5  486.02  6222.5  491.21    6335  493.62  6402.4  496.84  6529.1  499.78
#Mann= 6 ,-1 , 0
  3835.6      .1       0  4776.2     .05       0  4950.7     .12       0
    5017     .07       0    5023     .12       0    5122      .1       0
Bank Sta=4808,5171.8
XS Rating Curve= 0 ,0
Exp/Cntr=0.3,0.1

Type RM Length L Ch R = 1 ,19594   ,597,597,597
BEGIN DESCRIPTION:
UNT 010 IN LACR 23.0
END DESCRIPTION:
XS GIS Cut Line= 3
      2161137.67     13205196.85      2162337.72     13205396.85
       2163537.7     13204596.87
#Sta/Elev= 30
  3783.4  483.52  3993.8  476.94  4120.5  475.13  4148.4  473.82  4181.4   474.2
  4574.2  468.01  4789.6   466.4  4837.8   465.9  4876.3  464.22  4986.9  460.81
  4989.6  460.31  4992.9  460.81  4997.5  462.69  5007.5  463.59  5074.2  465.45
  5193.8  466.81  5469.3  466.13  5471.4  466.17  5584.4   466.4  5612.9  467.12
  5836.8  467.95  5973.5  472.63    5996  472.37  6017.1  475.11  6045.6  475.62
  6176.3  482.39  6248.4   485.1    6298  488.16  6406.2  491.73  6442.2  493.69
#Mann= 7 ,-1 , 0
  3783.4      .1       0  4876.3     .12       0  4986.9     .07       0
  4992.9     .12       0  5074.2      .1       0  5469.3     .05       0
  5471.4      .1       0
Bank Sta=4789.6,5584.4
XS Rating Curve= 0 ,0
Exp/Cntr=0.3,0.1

Type RM Length L Ch R = 1 ,18997   ,921,921,921
BEGIN DESCRIPTION:
UNT 010 IN LACR 22.0
END DESCRIPTION:
XS GIS Cut Line= 3
      2161269.29     13207594.64      2162296.08     13206119.11
      2163718.33     13204727.28
#Sta/Elev= 30
  2884.6  479.33  3529.2  471.97  3571.8  471.63  3586.7  472.54  3600.7  471.44
  3636.3  471.28  3944.5  468.28  4260.4  468.54  4490.1  465.51  4641.8  465.42
  4833.5  465.19  4887.6  463.66    4982  460.77  4993.1     459  4995.8   458.5
  4999.1     459  5003.2  460.73  5066.8   464.5  5096.8  464.74  5646.7  464.46
  5703.3  465.51  5748.5  465.87  5830.6  467.81  5922.5  467.79  6155.8  472.15
  6304.4  478.26  6346.8  481.15  6375.1  481.34  6488.3  486.44  6672.2  492.27
#Mann= 9 ,-1 , 0
  2884.6      .1       0  3529.2     .05       0  3636.3      .1       0
  4887.6     .12       0  4993.1     .07       0  4999.1     .12       0
  5096.8      .1       0  5748.5     .05       0  5922.5      .1       0
Bank Sta=4641.8,5703.3
XS Rating Curve= 0 ,0
Exp/Cntr=0.3,0.1

Type RM Length L Ch R = 1 ,18076   ,1288,1288,1288
BEGIN DESCRIPTION:
UNT 010 IN LACR 21.0
END DESCRIPTION:
XS GIS Cut Line= 3
      2161584.64     13207825.22      2162333.36     13206946.28
      2164026.09     13205416.32
#Sta/Elev= 30
  2568.3  480.05  2718.4  476.67  2987.7  473.65  3201.7  470.47  3491.4  466.82
  3583.7  467.01  3626.5  465.29  3980.6  463.65  4844.7  462.79    4915   462.6
  4993.1  459.38  5011.1  455.95  5013.8  455.45  5017.1  455.95  5035.7  458.86
  5110.3  463.17  5120.2  463.66  5318.9   471.6  5325.7  470.89  5396.6  475.12
  5460.2   476.9    5517  480.65  5552.1  480.98  5665.7  488.44  5686.6  487.99
  5722.4  490.06  5772.2  490.99  5800.2  492.68  5901.9  494.78  6004.6   496.7
#Mann= 9 ,-1 , 0
  2568.3      .1       0  2987.7     .05       0  3201.7      .1       0
  4844.7     .12       0  5011.1     .07       0  5017.1     .12       0
  5110.3      .1       0  5772.2     .05       0  5901.9      .1       0
Bank Sta=3980.6,5120.2
XS Rating Curve= 0 ,0
Exp/Cntr=0.3,0.1

Type RM Length L Ch R = 1 ,16788   ,732,732,732
BEGIN DESCRIPTION:
UNT 010 IN LACR 19.0
END DESCRIPTION:
XS GIS Cut Line= 3
      2162137.74     13208346.84      2163737.72     13206946.85
      2164237.71     13205646.89
#Sta/Elev= 30
    2874  499.61  3044.3  497.77    3308  488.71  3490.4  482.84  3518.9  483.27
  3688.8  475.43  3766.6  473.98  4036.2  463.91  4185.2  461.52  4440.5  461.94
  4780.3  459.82  4852.1   459.2  4929.3  457.62  4943.5  456.66  4957.8     454
  4961.4  451.94  4964.2  451.44  4967.4  451.94  4996.7  457.06  5045.2  458.15
  5184.3  459.67  5396.4  462.07  5785.2  475.09  5910.7  480.47    6020  481.94
  6069.3   486.4  6146.4  488.17  6173.7  490.22  6380.4  497.96  6392.8  498.12
#Mann= 9 ,-1 , 0
    2874     .05       0    3308      .1       0  4852.1     .12       0
  4961.4     .07       0  4967.4     .12       0  5045.2      .1       0
  5785.2     .05       0  6173.7      .1       0  6380.4     .05       0
Bank Sta=4780.3,5184.3
XS Rating Curve= 0 ,0
Exp/Cntr=0.3,0.1

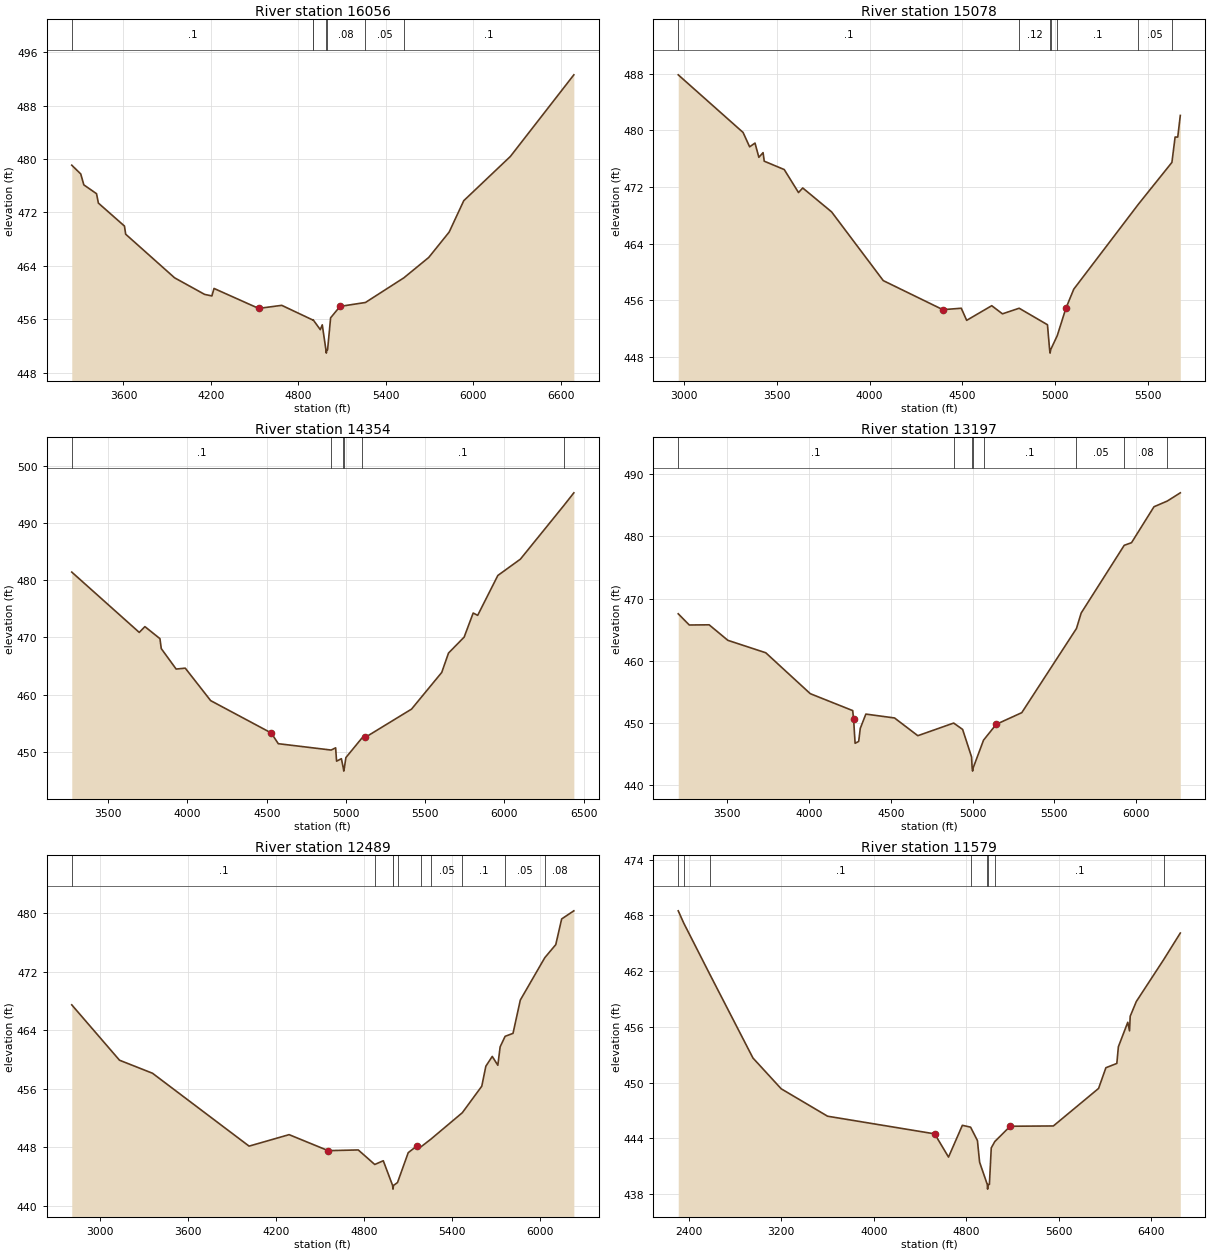
Type RM Length L Ch R = 1 ,16056   ,978,978,978
BEGIN DESCRIPTION:
UNT 010 IN LACR 18.0
END DESCRIPTION:
XS GIS Cut Line= 3
       2163277.4     13208693.22      2164731.37     13206750.97
      2164709.67     13205731.38
#Sta/Elev= 30
    3245  479.07  3306.6  477.76  3327.9  476.12  3414.9   474.8  3427.8  473.39
  3606.6  469.95    3615  468.73  3950.5   462.2  4156.8  459.71  4206.8  459.48
  4221.4   460.6  4527.7  457.61  4686.1  458.07  4899.6  455.87  4901.2  455.92
  4950.7  454.43  4964.3  455.15  4989.4  451.41  4992.2  450.91  4995.4  451.41
  5000.8  451.41  5021.6   456.2  5086.2  457.91  5260.9   458.5  5524.2  462.19
  5695.3  465.25  5835.3  469.05  5935.4  473.75  6255.4  480.38    6691  492.61
#Mann= 7 ,-1 , 0
    3245      .1       0  4899.6     .12       0  4901.2     .08       0
  4989.4     .07       0  4995.4     .08       0  5260.9     .05       0
  5524.2      .1       0
Bank Sta=4527.7,5086.2
XS Rating Curve= 0 ,0
Exp/Cntr=0.3,0.1

Type RM Length L Ch R = 1 ,15078   ,724,724,724
BEGIN DESCRIPTION:
UNT 010 IN LACR 16.0
END DESCRIPTION:
XS GIS Cut Line= 3
      2163537.72     13208946.86      2165137.72     13207696.85
      2165637.73     13207246.84
#Sta/Elev= 30
  2969.6  487.86  3318.7  479.72    3354  477.69  3382.9  478.22  3403.7  476.21
  3426.3  476.87  3432.7  475.66  3540.3  474.48  3617.2  471.23  3639.8  471.88
  3795.3   468.5  4073.6  458.79  4394.1  454.69  4493.5  454.89  4522.5  453.18
  4657.4  455.25  4715.1   454.1  4805.1  454.89  4957.5  452.56    4969  449.05
  4971.7  448.55    4975  449.05  5010.3  451.03  5056.4  454.86    5099  457.58
  5446.6  469.57  5627.5  475.49  5644.7  479.07  5658.9  479.07  5672.7  482.12
#Mann= 7 ,-1 , 0
  2969.6      .1       0  4805.1     .12       0    4969     .07       0
    4975     .12       0  5010.3      .1       0  5446.6     .05       0
  5627.5     .08       0
Bank Sta=4394.1,5056.4
XS Rating Curve= 0 ,0
Exp/Cntr=0.3,0.1

Type RM Length L Ch R = 1 ,14354   ,1157,1157,1157
BEGIN DESCRIPTION:
UNT 010 IN LACR 15.0
END DESCRIPTION:
XS GIS Cut Line= 3
      2163928.38     13209246.66      2165751.33     13208085.61
       2166510.9      13207423.7
#Sta/Elev= 30
  3269.8   481.4  3695.8  470.87  3731.4  471.88  3826.3  469.78  3834.7  468.04
  3928.6  464.47  3986.2  464.63  4146.4  458.96  4528.8  453.31  4573.2  451.44
  4906.9  450.33  4935.1  450.72  4941.1  448.39  4971.5  448.82  4983.8  447.15
  4986.5  446.65  4989.8  447.15    5000  449.02  5100.7  452.41  5123.1  452.56
  5414.3  457.48  5604.8  463.88  5647.5  467.26  5746.3  470.05  5803.2  474.25
  5831.7  473.85  5958.9  480.81  6101.3  483.66  6375.1  493.01  6438.6  495.24
#Mann= 6 ,-1 , 0
  3269.8      .1       0  4906.9     .12       0  4983.8     .07       0
  4989.8     .12       0  5100.7      .1       0  6375.1     .08       0
Bank Sta=4528.8,5123.1
XS Rating Curve= 0 ,0
Exp/Cntr=0.3,0.1

Type RM Length L Ch R = 1 ,13197   ,708,708,708
BEGIN DESCRIPTION:
UNT 010 IN LACR 13.0
END DESCRIPTION:
XS GIS Cut Line= 3
      2163960.92      13210049.6      2166402.38     13208953.66
      2166608.55     13208617.27
#Sta/Elev= 30
  3199.8  467.55  3267.5  465.75  3388.9  465.78  3503.2  463.29  3735.2  461.29
  4007.4  454.72  4266.9     452  4272.4  450.62  4281.5  446.75  4303.4  447.05
  4313.2  449.15  4347.3  451.44  4522.6  450.82  4665.1  447.97  4884.3     450
  4939.1  448.98  4993.9  444.55  4997.4  442.78  5000.1  442.28  5003.4  442.78
  5067.1  447.26  5144.9   449.8  5300.9  451.67  5635.4  465.19  5664.3  467.68
  5927.5  478.55  5972.1  478.97  6109.4  484.74  6191.5  485.67  6270.5  486.98
#Mann= 8 ,-1 , 0
  3199.8      .1       0  4884.3     .12       0  4997.4     .07       0
  5003.4     .12       0  5067.1      .1       0  5635.4     .05       0
  5927.5     .08       0  6191.5     .05       0
Bank Sta=4272.4,5144.9
XS Rating Curve= 0 ,0
Exp/Cntr=0.3,0.1

Type RM Length L Ch R = 1 ,12489   ,910,910,910
BEGIN DESCRIPTION:
UNT 010 IN LACR 11.0
END DESCRIPTION:
XS GIS Cut Line= 4
      2163874.21      13210461.9      2165056.89      13210331.7
      2166673.64     13209452.79      2166836.42     13209094.69
#Sta/Elev= 30
  2807.6  467.45  3133.1  459.88  3357.9   458.1  4016.7  448.13  4289.4   449.7
  4556.1  447.51    4761  447.61  4873.5  445.62  4931.7  446.13  4995.2  442.75
    4998  442.25  5001.2  442.75  5028.6  443.15  5101.8  447.24  5159.4  448.13
  5188.3  448.03  5256.6  449.09  5470.6   452.7  5603.3  456.33    5631  459.06
  5674.7   460.4  5712.7  459.19  5728.5  461.71  5762.5  463.15  5816.2  463.55
  5866.1  468.11  6032.9   473.9  6107.8  475.69  6147.9   479.2    6231  480.31
#Mann= 10 ,-1 , 0
  2807.6      .1       0  4873.5     .16       0  4995.2     .07       0
  5001.2     .16       0  5028.6     .05       0  5188.3      .1       0
  5256.6     .05       0  5470.6      .1       0  5762.5     .05       0
  6032.9     .08       0
Bank Sta=4556.1,5159.4
XS Rating Curve= 0 ,0
Exp/Cntr=0.3,0.1

Type RM Length L Ch R = 1 ,11579   ,923,923,923
BEGIN DESCRIPTION:
UNT 010 IN LACR 9.0
END DESCRIPTION:
XS GIS Cut Line= 3
      2163743.99     13211492.71      2166738.75     13210461.91
      2167096.83     13209344.27
#Sta/Elev= 30
  2309.8   468.5  2358.2  467.16  2584.3  461.63  2955.6  452.66  3200.2  449.34
  3600.8  446.39    4527  444.49  4646.6  441.99  4766.3  445.41  4837.5  445.21
  4896.5  443.77  4915.4  441.44  4981.8  439.04  4984.6  438.54  4987.8  439.04
    5000  439.04  5016.1  442.98  5047.3  443.67  5179.8  445.31  5553.1  445.34
    5944  449.38  6007.3  451.61  6101.8  452.07  6115.2  453.87  6196.4   456.5
  6211.6  455.58  6217.4  457.15  6269.9  458.73    6508  463.27  6650.6  466.11
#Mann= 8 ,-1 , 0
  2309.8      .1       0  2358.2     .05       0  2584.3      .1       0
  4837.5     .16       0  4981.8     .07       0  4987.8     .16       0
  5047.3      .1       0    6508     .05       0
Bank Sta=4527,5179.8
XS Rating Curve= 0 ,0
Exp/Cntr=0.3,0.1

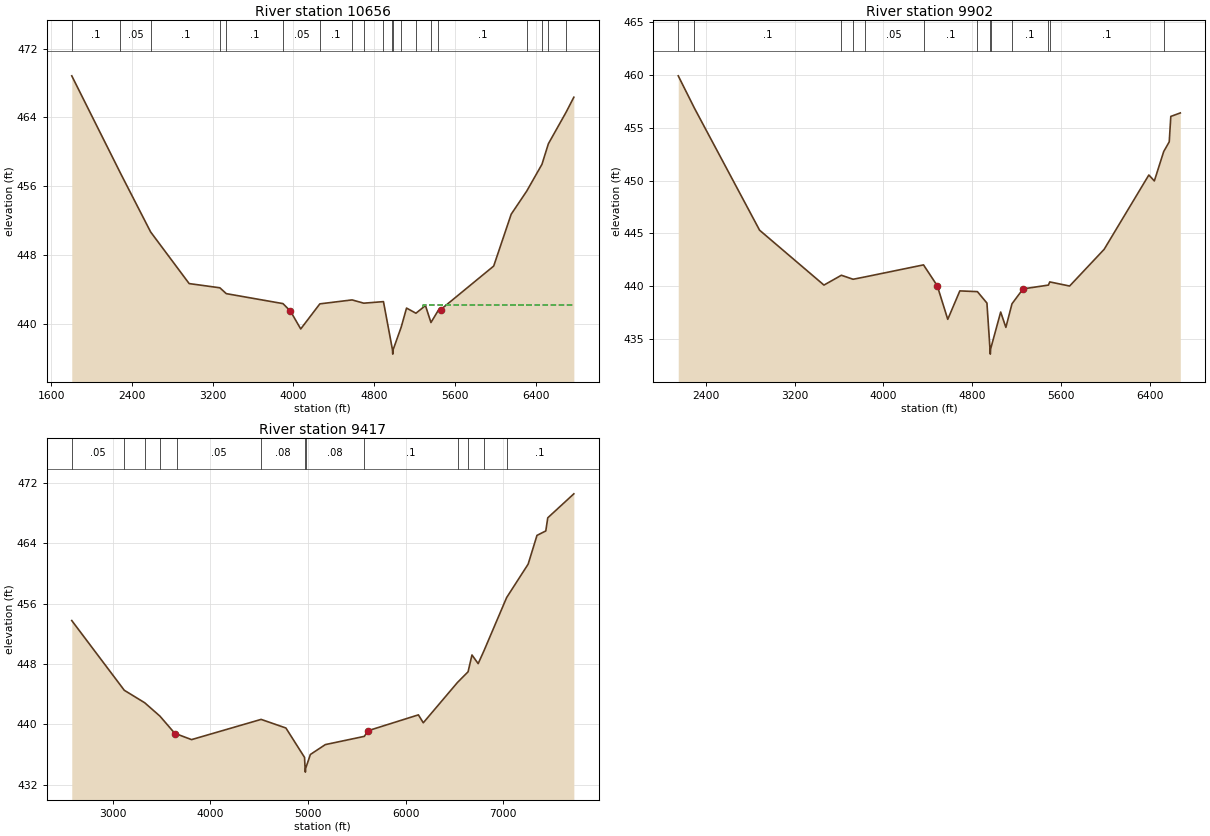
Type RM Length L Ch R = 1 ,10656   ,754,754,754
BEGIN DESCRIPTION:
UNT 010 IN LACR 8.0
END DESCRIPTION:
XS GIS Cut Line= 3
      2163678.83     13211742.29      2166250.47     13211525.28
      2168420.64     13210516.14
#Sta/Elev= 30
  1805.2  468.83  2287.7   457.5  2586.5  450.66  2968.2  444.65  3272.6  444.16
  3335.8  443.48  3897.4  442.32  3971.8  441.44  4073.5  439.37  4262.8  442.29
  4582.3  442.75  4697.9  442.37  4893.2  442.55  4982.5  436.94  4985.2  436.44
  4988.5  436.94  5069.1  439.59  5121.8   441.8  5214.9   441.2  5309.3  442.09
  5363.7  440.12  5434.5   441.5  5459.8  441.62  5985.3  446.69  6158.5  452.72
  6312.8  455.42  6463.3  458.53  6526.9  460.92  6701.8  464.58  6779.3  466.34
#Mann= 20 ,-1 , 0
  1805.2      .1       0  2287.7     .05       0  2586.5      .1       0
  3272.6     .05       0  3335.8      .1       0  3897.4     .05       0
  4262.8      .1       0  4582.3     .08       0  4697.9      .1       0
  4893.2     .12       0  4982.5     .07       0  4988.5     .12       0
  5069.1      .1       0  5214.9     .12       0  5363.7     .12       0
  5434.5      .1       0  6312.8     .05       0  6463.3      .1       0
  6526.9     .05       0  6701.8      .1       0
#XS Ineff= 2 , 0
                         5287.44           442.2
Permanent Ineff=
       F       F
Bank Sta=3971.8,5459.8
XS Rating Curve= 0 ,0
Exp/Cntr=0.3,0.1

Type RM Length L Ch R = 1 ,9902    ,485,485,485
BEGIN DESCRIPTION:
UNT 010 IN LACR 7.0
END DESCRIPTION:
XS GIS Cut Line= 4
      2163964.66     13212041.44      2165665.84     13212119.12
      2167118.43     13211839.48       2168097.2     13210915.09
#Sta/Elev= 30
  2149.2  459.91  2294.9  456.86    2883  445.31  3463.6  440.12  3620.8  441.05
  3726.4  440.67  3832.6  440.89  4361.5  442.03  4485.4  440.06  4580.2  436.88
  4689.1  439.57  4847.7   439.5  4933.5  438.42  4961.1  434.09  4963.8  433.59
  4967.1  434.09  5057.6  437.57  5104.4  436.12  5159.4  438.35  5259.4  439.76
  5488.3  440.12  5500.1  440.42  5679.3  440.03  5990.7   443.5  6393.8  450.53
  6443.5  449.97    6528  452.75  6577.9  453.67    6592  456.07  6677.7   456.4
#Mann= 13 ,-1 , 0
  2149.2     .05       0  2294.9      .1       0  3620.8     .05       0
  3726.4      .1       0  3832.6     .05       0  4361.5      .1       0
  4847.7     .16       0  4961.1     .07       0  4967.1     .16       0
  5159.4      .1       0  5488.3     .16       0  5500.1      .1       0
    6528     .05       0
Bank Sta=4485.4,5259.4
XS Rating Curve= 0 ,0
Exp/Cntr=0.3,0.1

Type RM Length L Ch R = 1 ,9417    ,1396,1396,1396
BEGIN DESCRIPTION:
UNT 010 IN LACR 6.0
END DESCRIPTION:
XS GIS Cut Line= 3
      2164557.76     13212849.06      2167595.95     13212187.17
      2169623.92     13211991.96
#Sta/Elev= 30
  2577.9  453.74  3116.3   444.5  3325.1  442.85  3481.9  441.07  3641.2  438.68
  3659.5  438.67    3806  437.96  4518.9  440.64    4773   439.5  4964.1   435.6
  4969.7  434.15  4972.5  433.65  4975.7  434.15  5023.9  435.99  5177.4   437.3
  5576.9  438.39  5615.4  439.14  6131.2  441.24  6181.4  440.19  6532.1  445.54
  6640.5  446.95  6680.4  449.18    6744  448.03  6803.5  449.74  7035.8  456.79
  7256.3  461.22  7346.8  465.03  7437.2  465.62  7457.3  467.36  7724.7  470.54
#Mann= 13 ,-1 , 0
  2577.9     .05       0  3116.3      .1       0  3325.1     .05       0
  3481.9      .1       0  3659.5     .05       0  4518.9     .08       0
  4969.7     .07       0  4975.7     .08       0  5576.9      .1       0
  6532.1     .08       0  6640.5      .1       0  6803.5     .05       0
  7035.8      .1       0
Bank Sta=3641.2,5615.4
XS Rating Curve= 0 ,0
Exp/Cntr=0.3,0.1