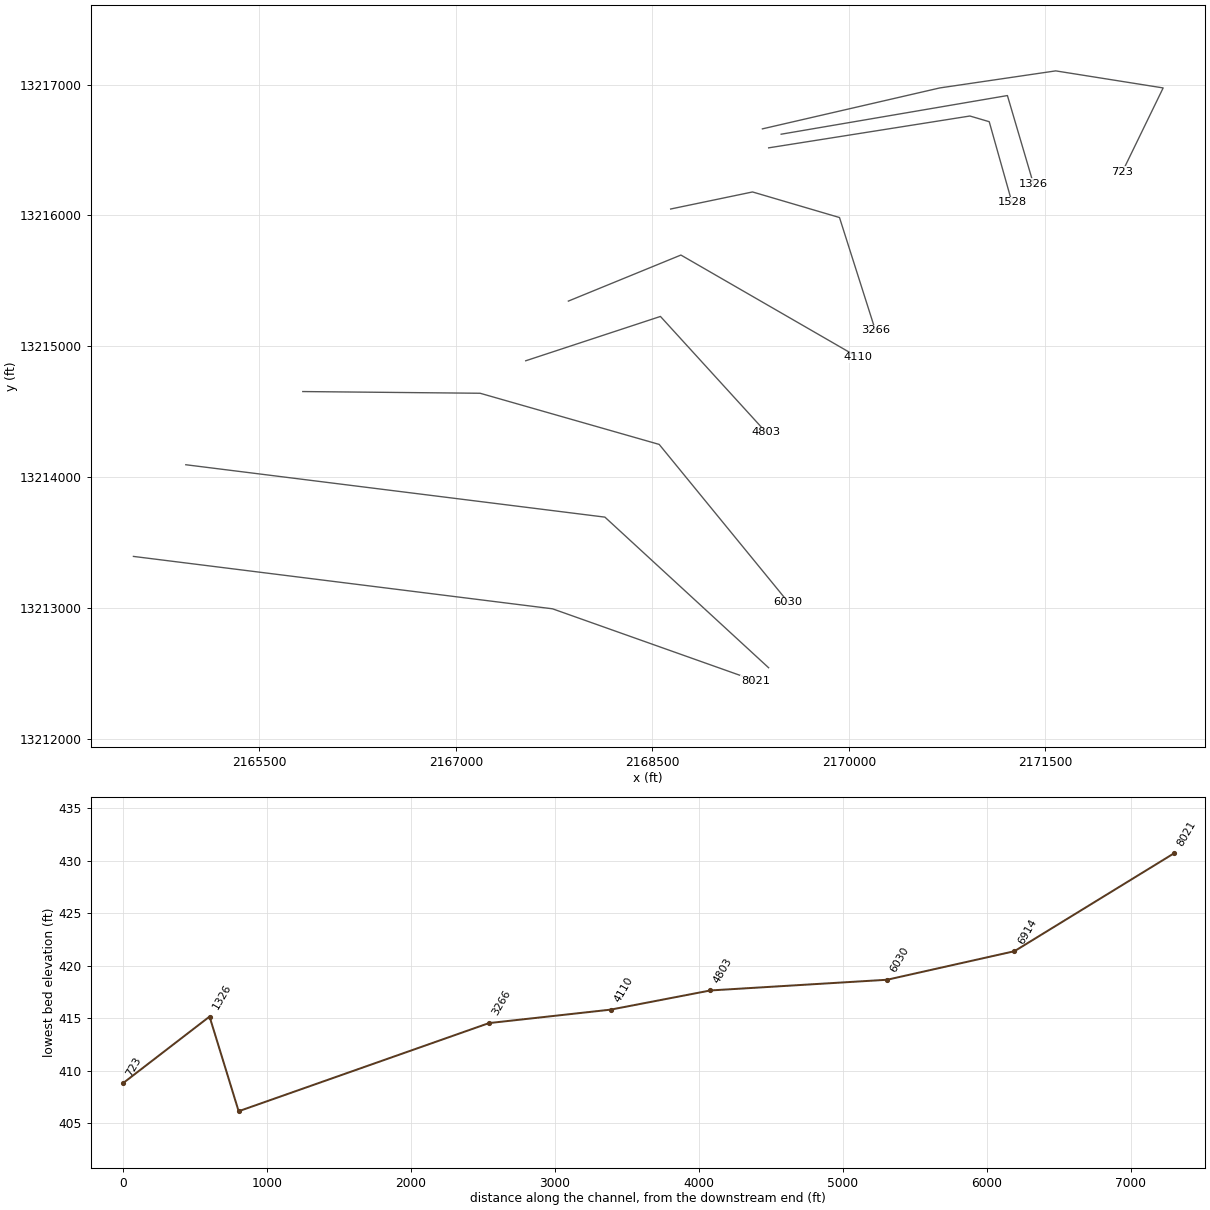
HEC-RAS study UNT 010 IN LACR.prj: UNT 010 IN LACR Base Level Engineering

--- UNT 010 IN LACR.g01 (geometry) --- (continued)

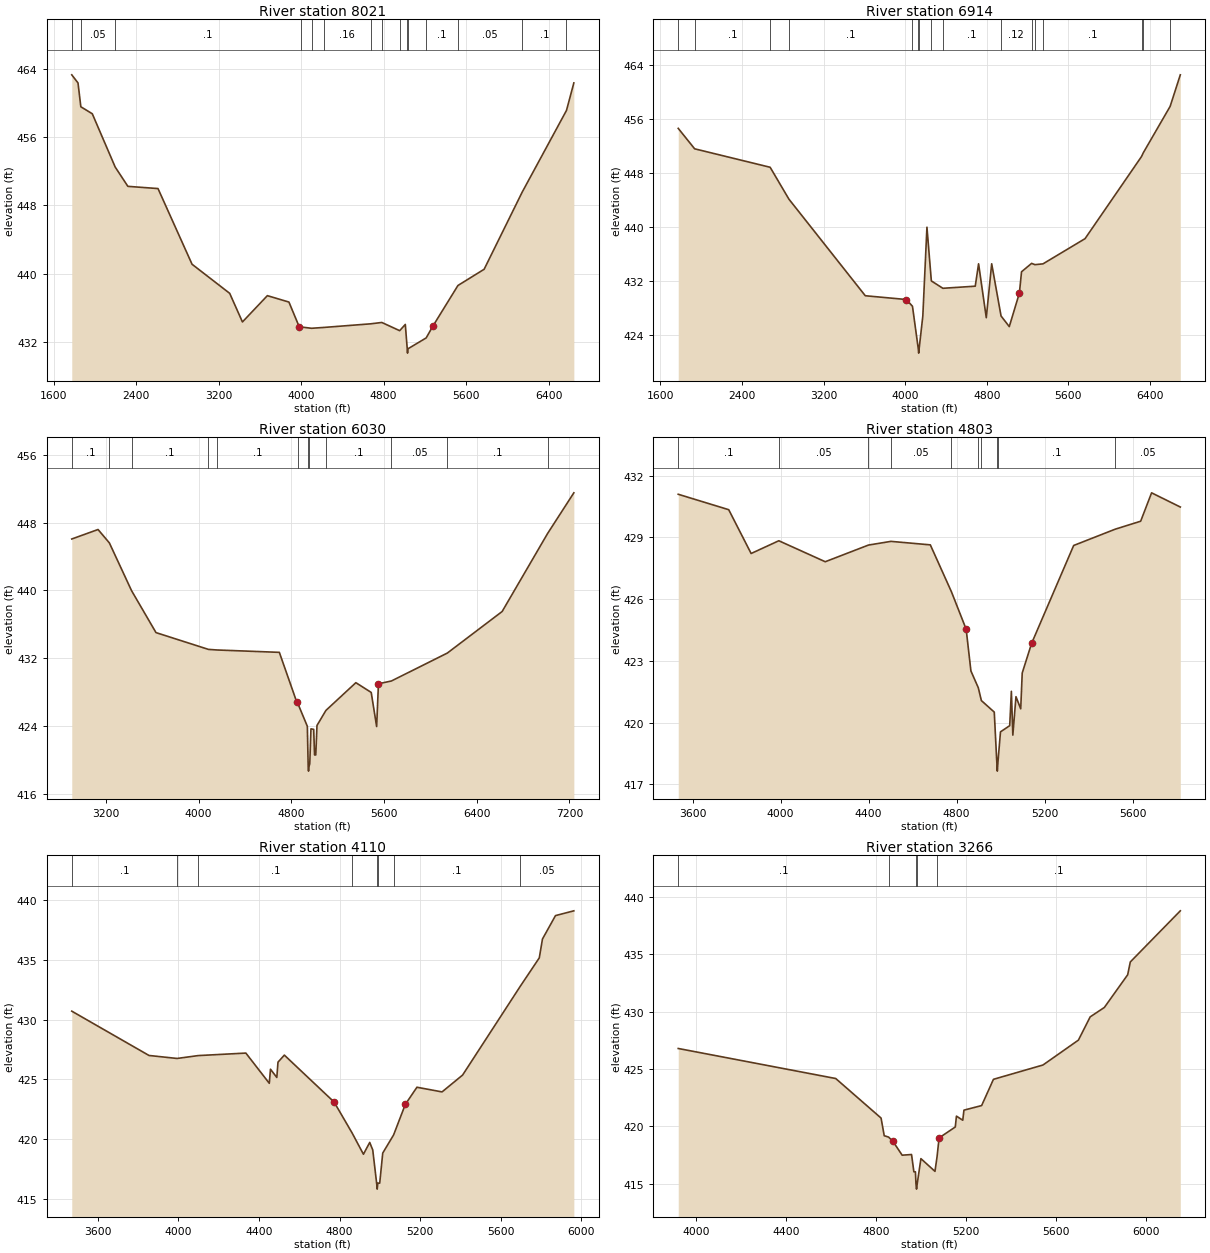
Type RM Length L Ch R = 1 ,8021    ,1107,1107,1107
BEGIN DESCRIPTION:
UNT 010 IN LACR 5.0
END DESCRIPTION:
XS GIS Cut Line= 3
      2164537.72     13213396.85      2167737.72     13212996.86
      2169287.73     13212446.85
#Sta/Elev= 30
  1775.1  463.29  1835.6  462.34    1863  459.55  1974.1  458.73  2196.3  452.49
  2319.3  450.23  2611.6  449.97  2941.6  441.11  3306.9   437.7  3430.4  434.35
  3672.2  437.43  3881.4  436.68  3982.1  433.76  3997.6  433.76    4101  433.61
  4222.8  433.71  4673.2  434.13  4782.3  434.29  4955.5  433.33  5010.1  434.06
  5028.8   431.2  5031.6   430.7  5034.8   431.2  5212.5  432.48  5275.9  433.83
  5520.6  438.62  5774.6  440.52    6144  449.56  6573.3  459.12  6644.7  462.34
#Mann= 15 ,-1 , 0
  1775.1      .1       0    1863     .05       0  2196.3      .1       0
  3997.6     .08       0    4101      .1       0  4222.8     .16       0
  4673.2     .12       0  4782.3     .16       0  4955.5     .12       0
  5028.8     .07       0  5034.8     .12       0  5212.5      .1       0
  5520.6     .05       0    6144      .1       0  6573.3     .05       0
Bank Sta=3982.1,5275.9
XS Rating Curve= 0 ,0
Exp/Cntr=0.3,0.1

Type RM Length L Ch R = 1 ,6914    ,884,884,884
BEGIN DESCRIPTION:
UNT 010 IN LACR 3.0
END DESCRIPTION:
XS GIS Cut Line= 3
      2164937.72     13214096.85      2168137.72     13213696.85
       2169387.7     13212546.87
#Sta/Elev= 30
  1775.1  454.59  1935.9  451.57  2676.4  448.84  2860.1  444.14  3609.3  429.86
  4012.4   429.3  4072.1   428.3  4130.3  421.88  4133.1  421.38  4136.3  421.88
  4173.6  426.87  4213.9  439.99  4257.1  432.05    4370  430.96  4687.6  431.27
  4720.3  434.58  4795.9  426.61  4848.8  434.58  4940.6  426.87  5021.3   425.3
  5120.5  430.25  5141.5   433.4  5240.2  434.64  5273.2  434.45  5351.9  434.57
  5764.2  438.29  6318.3  450.43  6335.5  450.98  6598.8  457.84  6698.5   462.5
#Mann= 16 ,-1 , 0
  1775.1     .05       0  1935.9      .1       0  2676.4     .05       0
  2860.1      .1       0  4072.1     .12       0  4130.3     .07       0
  4136.3     .12       0  4257.1     .08       0    4370      .1       0
  4940.6     .12       0  5240.2      .1       0  5273.2     .12       0
  5351.9      .1       0  6318.3     .05       0  6335.5      .1       0
  6598.8     .05       0
Bank Sta=4012.4,5120.5
XS Rating Curve= 0 ,0
Exp/Cntr=0.3,0.1

Type RM Length L Ch R = 1 ,6030    ,1227,1227,1227
BEGIN DESCRIPTION:
UNT 010 IN LACR 2.0
END DESCRIPTION:
XS GIS Cut Line= 4
      2165830.88     13214655.69      2167185.07     13214642.67
      2168552.26     13214252.04      2169537.69     13213046.89
#Sta/Elev= 30
  2905.2  446.06    3132  447.18  3229.7   445.6  3421.3  439.96  3632.1  435.01
  4084.6  433.03  4158.2  432.96  4696.5  432.68  4847.3   426.8  4860.5   426.5
  4938.2  423.95  4945.6  419.16  4948.4  418.66  4951.6  419.16  4959.1  419.52
  4969.4  423.65  4992.9  423.59  5000.6  420.57    5011  420.57  5021.4  424.05
  5098.8  425.83  5356.9   429.1  5489.4  427.95  5536.3  423.92  5551.8  428.97
  5663.9   429.3  6146.7   432.6  6619.3   437.5  7011.2   446.7  7238.1  451.51
#Mann= 12 ,-1 , 0
  2905.2      .1       0  3229.7     .05       0  3421.3      .1       0
  4084.6     .08       0  4158.2      .1       0  4860.5     .16       0
  4945.6     .07       0  4951.6     .16       0  5098.8      .1       0
  5663.9     .05       0  6146.7      .1       0  7011.2     .05       0
Bank Sta=4847.3,5551.8
XS Rating Curve= 0 ,0
Exp/Cntr=0.3,0.1

Type RM Length L Ch R = 1 ,4803    ,693,693,693
BEGIN DESCRIPTION:
Mapping XS b588c01e
END DESCRIPTION:
XS GIS Cut Line= 3
      2167533.17     13214890.68      2168561.86     13215229.23
      2169369.17     13214343.79
#Sta/Elev= 30
  3534.9   431.1  3764.3  430.35  3866.1  428.22  3991.9  428.84  4202.9  427.82
  4399.1  428.63  4501.4  428.81  4680.3  428.64  4776.2  426.36  4843.1  424.54
  4864.7  422.51  4898.4  421.69  4912.2  421.07  4970.8  420.51    4982  418.14
  4984.7  417.64    4988  418.14  4999.1  419.55    5041  419.85  5048.5  421.52
  5055.2  419.39  5069.4  421.26    5091  420.67  5097.8  422.41  5140.4  423.85
  5331.6  428.61  5519.7   429.4    5636  429.79  5685.6  431.17  5816.1  430.48
#Mann= 10 ,-1 , 0
  3534.9      .1       0  3991.9     .05       0  4399.1     .08       0
  4501.4     .05       0  4776.2      .1       0  4898.4     .12       0
  4912.2      .1       0    4982     .07       0    4988      .1       0
  5519.7     .05       0
Bank Sta=4843.1,5140.4
XS Rating Curve= 0 ,0
Exp/Cntr=0.3,0.1

Type RM Length L Ch R = 1 ,4110    ,844,844,844
BEGIN DESCRIPTION:
Mapping XS feba4b10
END DESCRIPTION:
XS GIS Cut Line= 3
      2167858.71     13215346.41      2168718.11     13215697.98
      2170072.28     13214916.73
#Sta/Elev= 30
  3470.6  430.71  3853.9     427  3993.3  426.75  4098.1  426.99  4334.7   427.2
    4451  424.67  4456.8  425.85  4488.3  425.16  4494.1  426.44  4525.7  427.03
  4772.7   423.1  4863.1  420.48  4918.2  418.73  4949.4  419.72  4964.4  419.09
  4983.7  416.31  4986.5  415.81  4989.7  416.31    4999  416.31    5014  418.83
    5068  420.35    5126   422.9  5183.7  424.34  5308.4  423.95  5410.4  425.36
  5697.3  432.81    5791  435.17  5806.8  436.75  5871.4  438.71  5962.5  439.11
#Mann= 8 ,-1 , 0
  3470.6      .1       0  3993.3     .08       0  4098.1      .1       0
  4863.1     .12       0  4983.7     .07       0  4989.7     .12       0
    5068      .1       0  5697.3     .05       0
Bank Sta=4772.7,5126
XS Rating Curve= 0 ,0
Exp/Cntr=0.3,0.1

Type RM Length L Ch R = 1 ,3266    ,1738,1738,1738
BEGIN DESCRIPTION:
Mapping XS a632fc78
END DESCRIPTION:
XS GIS Cut Line= 4
      2168639.95     13216049.54      2169264.98     13216179.75
      2169929.04     13215984.44      2170202.49     13215125.04
#Sta/Elev= 30
  3920.9   426.8  4621.2  424.18  4822.8  420.73  4836.9  419.19  4856.2  419.07
  4875.5   418.7  4916.6  417.49  4958.3  417.55  4968.7  416.04  4975.6  416.04
  4977.8  415.03  4980.5  414.53  4983.8  415.03    5000  417.19  5062.5  416.08
  5071.8  417.36  5080.8     419  5152.8  419.95    5158   420.9  5186.1  420.54
  5191.3  421.42    5270  421.82  5322.5  424.11  5542.8  425.36  5700.3  427.53
  5752.7  429.56  5815.7  430.38  5919.3  433.23  5931.1  434.35  6153.4  438.81
#Mann= 5 ,-1 , 0
  3920.9      .1       0  4856.2     .12       0  4977.8     .07       0
  4983.8     .12       0  5071.8      .1       0
Bank Sta=4875.5,5080.8
XS Rating Curve= 0 ,0
Exp/Cntr=0.3,0.1

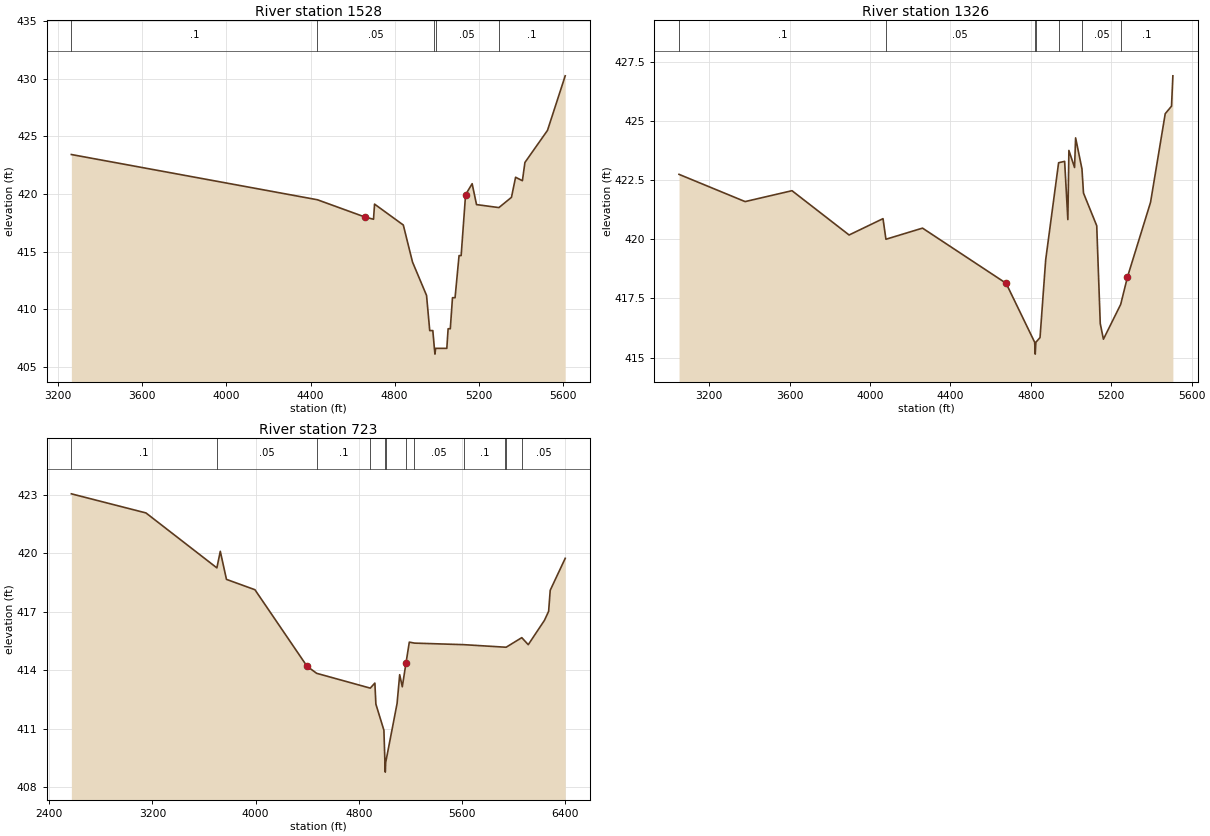
Type RM Length L Ch R = 1 ,1528    ,202,202,202
BEGIN DESCRIPTION:
Mapping XS bc8623fe
END DESCRIPTION:
XS GIS Cut Line= 4
      2169388.24     13216516.56       2170924.7     13216759.61
      2171072.27     13216716.21      2171245.61     13216100.85
#Sta/Elev= 30
  3262.4  423.43  4432.4  419.51    4659  418.01  4699.4  417.82  4704.4  419.13
  4841.1  417.32  4884.9  414.11  4951.6  411.22  4966.8  408.17  4981.5  408.17
  4988.9  406.63  4991.6  406.13  4994.9  406.63  5048.1  406.63  5054.2  408.33
  5064.6  408.33    5075  411.02  5087.3  411.02  5106.2  414.67  5116.2  414.67
  5137.3  419.95  5168.5   420.9  5189.3  419.09  5295.8  418.83  5355.5  419.72
  5375.1  421.46  5407.5  421.16  5419.5  422.74  5526.8  425.52  5611.1  430.25
#Mann= 5 ,-1 , 0
  3262.4      .1       0  4432.4     .05       0  4988.9    .035       0
  4994.9     .05       0  5295.8      .1       0
Bank Sta=4659,5137.3
XS Rating Curve= 0 ,0
Exp/Cntr=0.3,0.1

Type RM Length L Ch R = 1 ,1326    ,603,603,603
BEGIN DESCRIPTION:
Mapping XS 7c846719
END DESCRIPTION:
XS GIS Cut Line= 3
      2169483.71     13216620.72      2171211.16     13216915.86
      2171410.37      13216240.3
#Sta/Elev= 30
  3049.8  422.74  3378.5  421.59  3611.8  422.05  3895.9  420.18  4064.6  420.87
  4079.1     420  4261.1  420.47    4677  418.14  4819.1  415.65  4821.8  415.15
  4825.1  415.65  4845.7  415.85  4873.8  419.13  4938.1  423.23  4968.1  423.29
  4984.1  420.83  4989.3  423.75  5017.5  423.03  5022.7  424.28  5054.3  422.97
  5061.9  421.95  5127.8  420.57  5145.3  416.44  5161.1  415.78    5247  417.25
  5280.8  418.41  5395.5  421.56  5468.5   425.3  5499.8  425.62  5506.6   426.9
#Mann= 7 ,-1 , 0
  3049.8      .1       0  4079.1     .05       0  4819.1     .07       0
  4825.1     .05       0  4938.1     .12       0  5054.3     .05       0
    5247      .1       0
Bank Sta=4677,5280.8
XS Rating Curve= 0 ,0
Exp/Cntr=0.3,0.1

Type RM Length L Ch R = 1 ,723     ,0,0,0
BEGIN DESCRIPTION:
UNT 010 IN LACR 1.0
END DESCRIPTION:
XS GIS Cut Line= 5
      2169340.49     13216661.52      2170694.67     13216974.02
      2171580.09     13217104.23       2172400.4     13216974.02
      2172088.38     13216332.24
#Sta/Elev= 30
  2571.1  423.06  3149.4  422.08  3699.4  419.26  3725.8  420.11  3773.7  418.67
  3994.3  418.14  4398.6  414.21    4473  413.85  4888.5  413.09  4924.3  413.35
  4932.1  412.27  4994.3  410.93  5002.3  409.28    5005  408.78  5008.3  409.28
  5096.4   412.3  5116.7  413.78  5136.9  413.16  5165.6  414.38  5191.3  415.45
  5231.1   415.4  5614.6  415.32  5936.6  415.19  5942.3  415.19  6063.2  415.68
  6113.5  415.32  6239.2  416.57  6271.4  417.03  6283.7  418.11    6400  419.75
#Mann= 12 ,-1 , 0
  2571.1      .1       0  3699.4     .05       0    4473      .1       0
  4888.5     .12       0  5002.3     .07       0  5008.3     .12       0
  5165.6      .1       0  5231.1     .05       0  5614.6      .1       0
  5936.6     .05       0  5942.3      .1       0  6063.2     .05       0
Bank Sta=4398.6,5165.6
XS Rating Curve= 0 ,0
Exp/Cntr=0.3,0.1

Chan Stop Cuts=-1
Use User Specified Reach Order=0
Composite Channel Slope=5