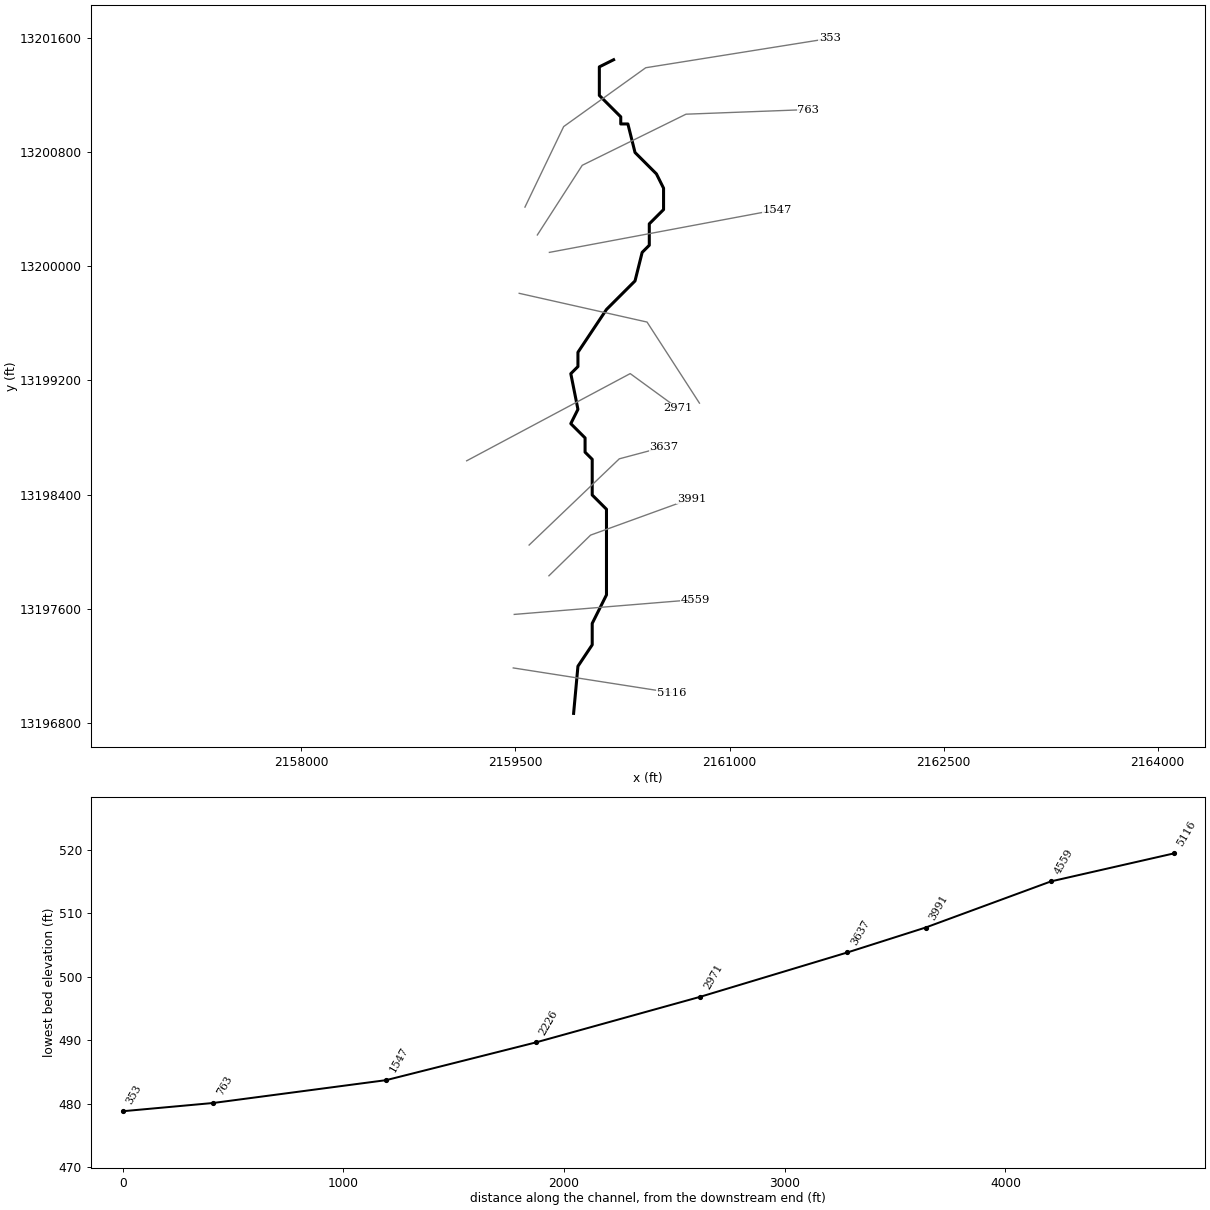
--- UNT 012 IN LACR.prj (project) ---

Proj Title=UNT 012 IN LACR Base Level Engineering
Current Plan=p01
Default Exp/Contr=0.3,0.1
English Units
Geom File=g01
Flow File=f01
Plan File=p01
Y Axis Title=Elevation
X Axis Title(PF)=Main Channel Distance
X Axis Title(XS)=Station
BEGIN DESCRIPTION:
UNT 012 IN LACR
END DESCRIPTION:
DSS Export Rating Curves= 0
DSS Export Rating Curve Sorted= 0
DSS Export Volume Flow Curves= 0
DXF OffsetX= 0
DXF OffsetY= 0
DXF ScaleX= 1
DXF ScaleY= 10

--- UNT 012 IN LACR.p01 (plan) ---

Plan Title=Multiple Run
Short Identifier=Multiple
Geom File=g01
Flow File=f01
Subcritical Flow
K Sum by GR= 0
Std Step Tol= 0.01
Critical Tol= 0.01
Num of Std Step Trials= 20
Max Error Tol= 0.3
Flow Tol Ratio= 0.001
Split Flow NTrial= 30
Split Flow Tol= 0.02
Split Flow Ratio= 0.02
Log Output Level= 0
Friction Slope Method= 1
Unsteady Friction Slope Method= 2
Unsteady Bridges Friction Slope Method= 1
Parabolic Critical Depth
Global Vel Dist=  1 , 1 , 1
Global Log Level= 0
CheckData=True
Encroach Param= -1, 0, 0, 0
BEGIN DESCRIPTION:
Multiple Run
END DESCRIPTION:

--- UNT 012 IN LACR.f01 (steady flow) ---

Flow Title=Multiple
Number of Profiles=7
Profile Names=10-year,25-year,50-year,1pct_min,100-year,1pct_plu,500-year
River Rch & RM= UNT 012 IN LACR,Reach-1,5116
     237     333     414     379     513     694     799
Boundary for River Rch & Prof#=UNT 012 IN LACR,Reach-1,1
Up Type=0
Dn Type=3
Dn Slope=0.005
Boundary for River Rch & Prof#=UNT 012 IN LACR,Reach-1,2
Up Type=0
Dn Type=3
Dn Slope=0.005
Boundary for River Rch & Prof#=UNT 012 IN LACR,Reach-1,3
Up Type=0
Dn Type=3
Dn Slope=0.005
Boundary for River Rch & Prof#=UNT 012 IN LACR,Reach-1,4
Up Type=0
Dn Type=3
Dn Slope=0.005
Boundary for River Rch & Prof#=UNT 012 IN LACR,Reach-1,5
Up Type=0
Dn Type=3
Dn Slope=0.005
Boundary for River Rch & Prof#=UNT 012 IN LACR,Reach-1,6
Up Type=0
Dn Type=3
Dn Slope=0.005
Boundary for River Rch & Prof#=UNT 012 IN LACR,Reach-1,7
Up Type=0
Dn Type=3
Dn Slope=0.005

--- UNT 012 IN LACR.g01 (geometry) ---

Geom Title=Existing Conditions
Program Version=4.10

River Reach=UNT 012 IN LACR ,Reach-1
Reach XY= 30
      2159907.39     13196866.52      2159937.72     13197196.85
      2160037.72     13197346.85      2160037.72     13197496.85
      2160137.72     13197696.85      2160137.72     13198296.85
      2160037.72     13198396.85      2160037.72     13198646.85
      2159987.72     13198696.85      2159987.72     13198796.85
      2159887.72     13198896.85      2159937.72     13198996.85
      2159887.72     13199246.85      2159937.72     13199296.85
      2159937.72     13199396.85      2160137.72     13199696.85
      2160337.72     13199896.85      2160387.72     13200096.85
      2160437.72     13200146.85      2160437.72     13200296.85
      2160537.72     13200396.85      2160537.72     13200546.85
      2160487.72     13200646.85      2160337.72     13200796.85
      2160287.72     13200996.86      2160237.72     13200996.86
      2160237.72     13201046.85      2160087.72     13201196.85
      2160087.72     13201396.85      2160187.72     13201446.85

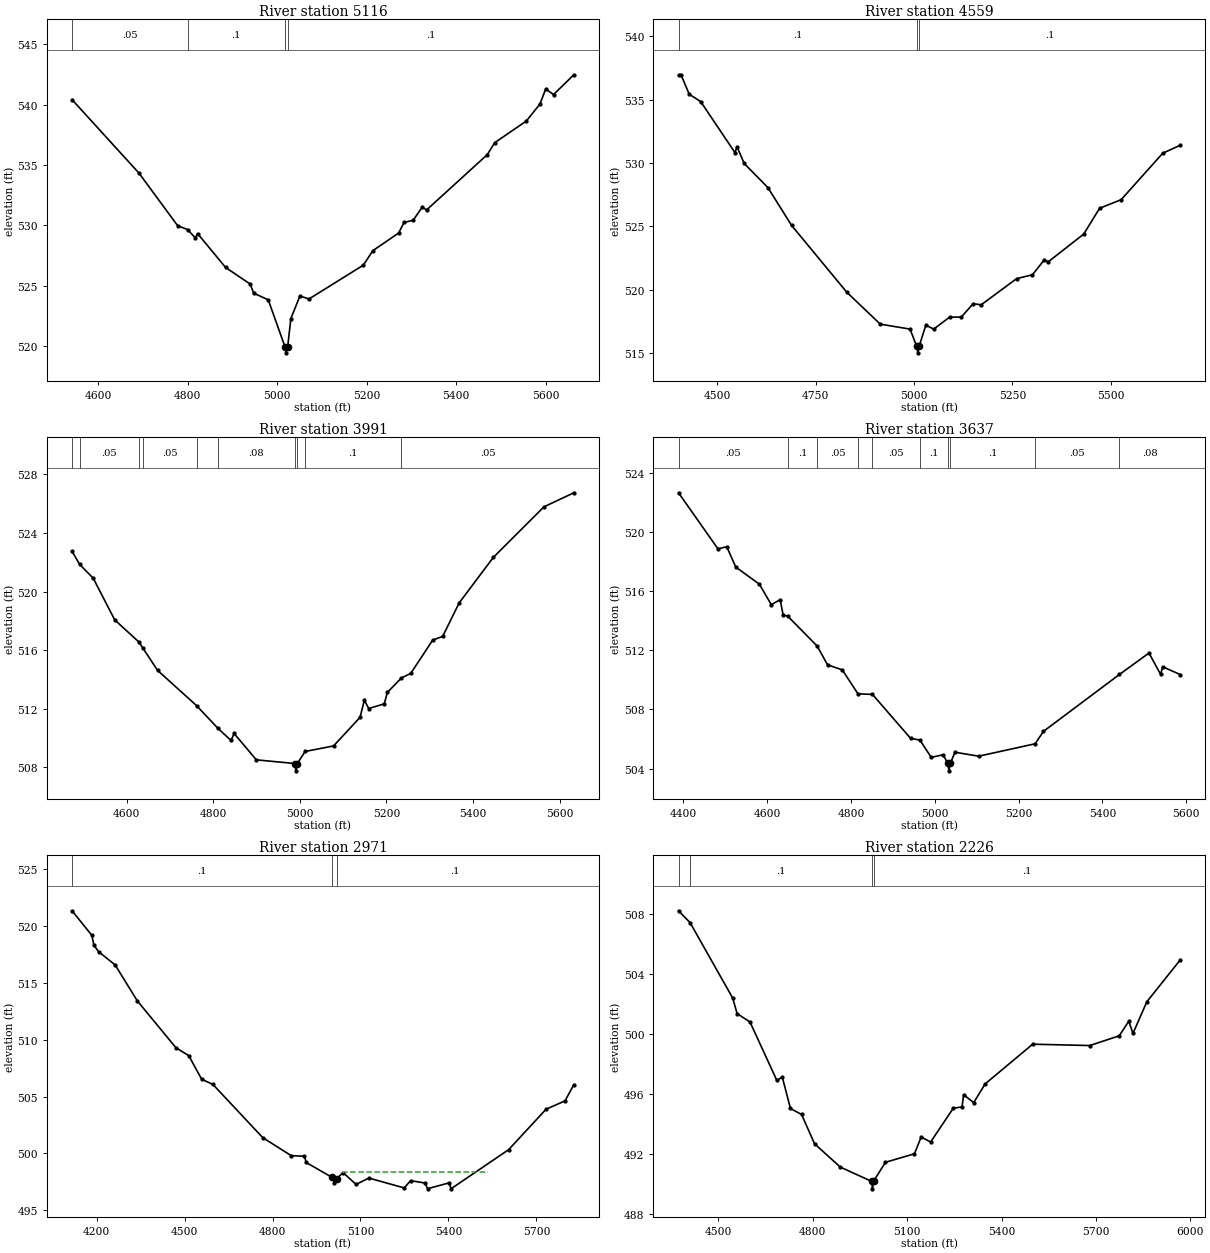
Type RM Length L Ch R = 1 ,5116    ,557,557,557
BEGIN DESCRIPTION:
UNT 012 IN LACR 6.0
END DESCRIPTION:
XS GIS Cut Line= 2
      2159484.52     13197184.98      2160592.67     13197011.83
#Sta/Elev= 30
  4541.3  540.42  4691.2  534.32  4777.3  529.98  4799.6  529.66  4816.7  528.97
  4821.8  529.33  4884.5  526.52  4939.3  525.15  4947.3  524.39  4979.8  523.84
  5017.2  519.95    5020  519.45  5023.2  519.95  5030.4  522.29  5050.6  524.16
  5070.8  523.91  5192.3  526.71  5213.5  527.91  5271.2  529.37  5283.4  530.25
  5303.6  530.43  5323.9  531.51  5333.9  531.29  5469.5  535.87  5485.8  536.85
  5556.7  538.65    5587  540.05  5600.1  541.31  5617.4  540.84  5662.9  542.48
#Mann= 4 ,-1 , 0
  4541.3     .05       0  4799.6      .1       0  5017.2     .07       0
  5023.2      .1       0
Bank Sta=5017.2,5023.2
XS Rating Curve= 0 ,0
Exp/Cntr=0.3,0.1

Type RM Length L Ch R = 1 ,4559    ,568,568,568
BEGIN DESCRIPTION:
UNT 012 IN LACR 6.1
END DESCRIPTION:
XS GIS Cut Line= 2
      2159491.42     13197559.99      2160762.26     13197664.16
#Sta/Elev= 30
  4401.7  536.92    4408  536.95  4428.8  535.42  4458.2  534.83  4545.2  530.81
  4550.2  531.29  4568.6  529.96  4628.8  528.06    4689  525.08  4829.4  519.81
  4914.4   517.3    4990  516.91    5007  515.54  5009.8  515.04    5013  515.54
  5030.1  517.22  5050.2  516.91  5090.3  517.85  5120.4  517.86  5150.5  518.92
  5170.6  518.82  5260.9  520.89    5301  521.19  5331.1  522.37  5341.1  522.21
  5431.4   524.4  5471.6  526.43  5526.5  527.11  5632.1  530.77  5676.8   531.4
#Mann= 3 ,-1 , 0
  4401.7      .1       0    5007     .07       0    5013      .1       0
Bank Sta=5007,5013
XS Rating Curve= 0 ,0
Exp/Cntr=0.3,0.1

Type RM Length L Ch R = 1 ,3991    ,354,354,354
BEGIN DESCRIPTION:
UNT 012 IN LACR 5.0
END DESCRIPTION:
XS GIS Cut Line= 3
      2159734.47     13197830.81      2160026.15     13198115.54
      2160732.69     13198371.84
#Sta/Elev= 30
  4473.7  522.74  4491.3  521.85  4522.6  520.91  4572.2  518.07    4628  516.56
  4637.4  516.14  4671.3  514.62  4761.3  512.22  4810.3  510.68    4841  509.84
    4848  510.32  4899.4  508.52  4988.2  508.27    4991  507.77  4994.2  508.27
  5011.9  509.09  5077.8  509.47    5139  511.42  5148.9  512.59    5159  512.02
  5194.9  512.34  5202.1  513.12  5234.7  514.11  5256.2  514.42  5306.8  516.69
  5329.8  516.94    5368  519.23  5446.8  522.33  5563.8  525.78  5632.9  526.74
#Mann= 10 ,-1 , 0
  4473.7      .1       0  4491.3     .05       0    4628      .1       0
  4637.4     .05       0  4761.3      .1       0  4810.3     .08       0
  4988.2     .07       0  4994.2     .08       0  5011.9      .1       0
  5234.7     .05       0
Bank Sta=4988.2,4994.2
XS Rating Curve= 0 ,0
Exp/Cntr=0.3,0.1

Type RM Length L Ch R = 1 ,3637    ,666,666,666
BEGIN DESCRIPTION:
UNT 012 IN LACR 4.0
END DESCRIPTION:
XS GIS Cut Line= 3
      2159595.57     13198046.08      2160227.54     13198650.27
      2160540.01     13198733.59
#Sta/Elev= 30
  4388.3  522.66  4482.3  518.87  4503.4  519.01  4524.8  517.64  4581.4  516.47
  4609.7  515.09  4630.8  515.43    4638  514.39  4648.6  514.32  4719.2  512.29
    4744  511.02  4779.2  510.68  4816.6  509.06  4851.2  509.02  4942.1  506.05
  4964.4  505.93  4991.5  504.76  5019.8  504.94    5031  504.35  5033.7  503.85
    5037  504.35  5048.1  505.11  5104.7  504.84  5239.4  505.68  5259.3  506.52
  5440.7  510.37  5511.2  511.82  5538.8  510.38  5543.9  510.89    5586  510.36
#Mann= 10 ,-1 , 0
  4388.3     .05       0  4648.6      .1       0  4719.2     .05       0
  4816.6      .1       0  4851.2     .05       0  4964.4      .1       0
    5031     .07       0    5037      .1       0  5239.4     .05       0
  5440.7     .08       0
Bank Sta=5031,5037
XS Rating Curve= 0 ,0
Exp/Cntr=0.3,0.1

Type RM Length L Ch R = 1 ,2971    ,745,745,745
BEGIN DESCRIPTION:
UNT 012 IN LACR 3.1
END DESCRIPTION:
XS GIS Cut Line= 3
      2159158.07     13198636.37      2160303.93     13199247.49
      2160637.28     13199004.42
#Sta/Elev= 30
  4116.4  521.36    4184  519.19  4190.7  518.34  4206.7  517.76  4263.3  516.59
  4338.8  513.43  4470.5   509.3  4514.4   508.6  4558.4  506.52  4596.6  506.07
  4766.6  501.38    4864  499.79    4909  499.74  4914.7  499.19  5002.5  497.89
  5011.3  497.38  5018.8  497.77  5040.7   498.3  5084.7  497.26  5128.6  497.82
    5249  496.95  5270.9  497.59  5320.5  497.38  5328.7  496.88  5402.7   497.4
  5408.4  496.87  5605.2  500.32  5732.7  503.88  5797.6  504.62  5827.6  506.05
#Mann= 3 ,-1 , 0
  4116.4      .1       0  5002.5     .07       0  5018.8      .1       0
#XS Ineff= 1 ,-1
 5040.45 5535.08  498.31
Permanent Ineff=
       F
Bank Sta=5002.5,5018.8
XS Rating Curve= 0 ,0
Exp/Cntr=0.3,0.1

Type RM Length L Ch R = 1 ,2226    ,679,679,679
BEGIN DESCRIPTION:
UNT 012 IN LACR 3.0
END DESCRIPTION:
XS GIS Cut Line= 3
      2159526.18     13199809.98      2160421.99      13199608.6
      2160789.18      13199040.5
#Sta/Elev= 30
  4373.2  508.23  4409.8  507.44  4545.5   502.4  4559.3  501.37  4600.3  500.81
  4685.6  496.91  4702.8  497.14  4728.9  495.04  4764.3  494.64  4805.3  492.69
  4887.3  491.13  4986.8  490.18  4989.5  489.68  4992.8  490.18  5030.7  491.45
    5123  492.02  5144.2  493.14  5174.2   492.8    5246  495.05  5274.1  495.15
  5279.2  495.96  5311.2  495.43  5347.5  496.68  5498.6  499.33    5680  499.24
  5773.7  499.89    5804  500.86  5817.3  500.05  5861.4  502.16  5967.8  504.96
#Mann= 4 ,-1 , 0
  4373.2     .05       0  4409.8      .1       0  4986.8     .07       0
  4992.8      .1       0
Bank Sta=4986.8,4992.8
XS Rating Curve= 0 ,0
Exp/Cntr=0.3,0.1

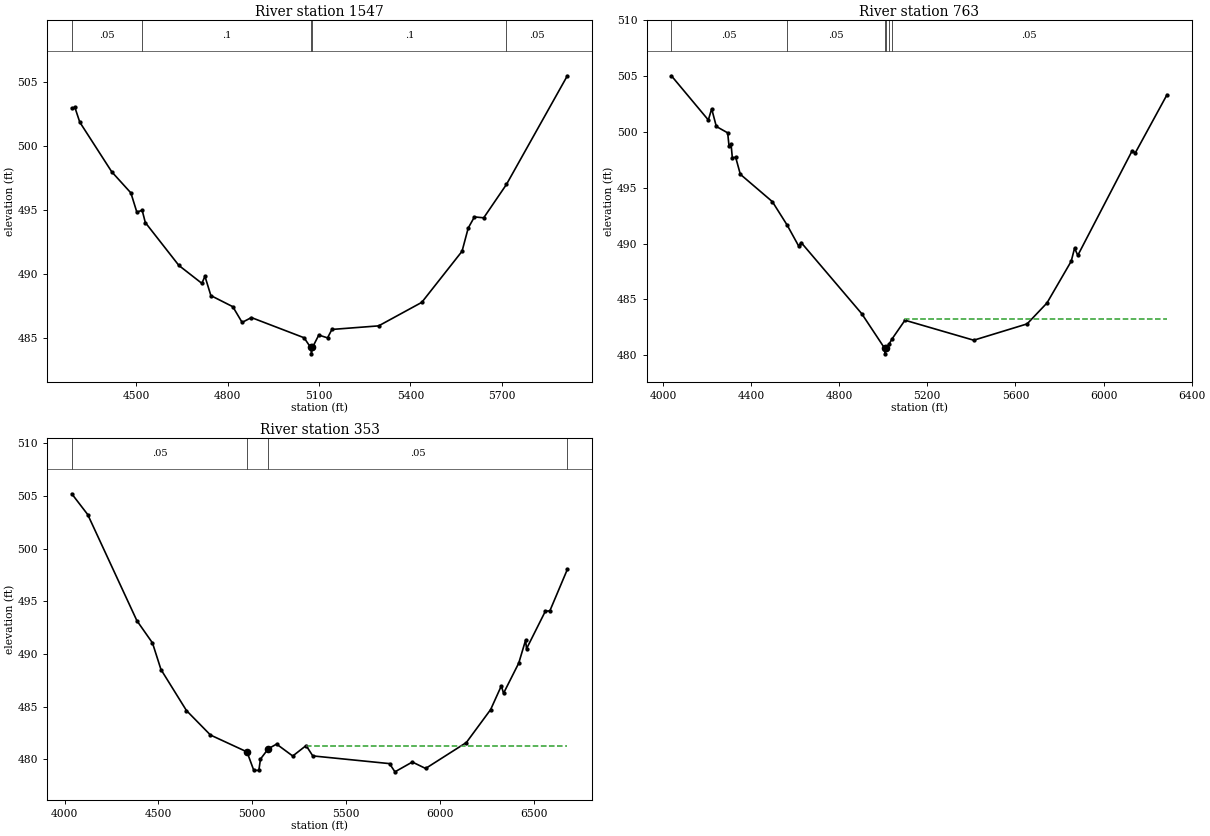
Type RM Length L Ch R = 1 ,1547    ,784,784,784
BEGIN DESCRIPTION:
UNT 012 IN LACR 2.0
END DESCRIPTION:
XS GIS Cut Line= 3
      2159737.72     13200096.85      2160537.72     13200246.85
      2161337.74     13200396.86
#Sta/Elev= 30
  4287.8  502.96    4298  503.03  4314.1  501.87  4419.2  497.98    4482  496.33
  4501.5  494.83  4519.1  494.97  4529.4  494.01  4639.7  490.65  4715.1  489.25
  4725.3   489.8  4744.8  488.29  4816.9  487.42  4847.4  486.19  4877.9  486.57
  5050.9  484.99  5072.5  484.23  5075.2  483.73  5078.5  484.23  5099.2   485.2
    5128  484.98  5142.4  485.64  5295.9  485.92  5437.5  487.76  5569.8  491.76
  5590.1  493.58  5610.5  494.45    5641  494.38  5715.6  496.99  5915.7   505.5
#Mann= 5 ,-1 , 0
  4287.8     .05       0  4519.1      .1       0  5072.5     .07       0
  5078.5      .1       0  5715.6     .05       0
Bank Sta=5072.5,5078.5
XS Rating Curve= 0 ,0
Exp/Cntr=0.3,0.1

Type RM Length L Ch R = 1 ,763     ,410,410,410
BEGIN DESCRIPTION:
UNT 012 IN LACR 2.1
END DESCRIPTION:
XS GIS Cut Line= 4
      2159653.26     13200218.89      2159967.91     13200707.13
      2160694.91     13201065.21      2161552.14     13201097.76
#Sta/Elev= 30
  4038.6  505.03  4206.2  501.07  4221.4  502.07  4242.5  500.49    4294  499.92
    4300  498.77  4309.2  498.93  4315.1   497.7  4330.3  497.73  4351.4  496.21
  4496.7  493.76  4564.2  491.65  4616.3  489.78  4627.5   490.1  4902.6  483.72
  5006.3  480.63  5009.1  480.13  5012.3  480.63    5028  481.05  5038.4  481.42
  5098.6  483.14  5410.7  481.35  5652.8  482.81  5742.9  484.68    5853  488.42
  5868.3  489.59    5883  488.95  6130.1  498.33  6143.2   498.1  6287.7  503.33
#Mann= 6 ,-1 , 0
  4038.6     .05       0  4564.2     .05       0  5006.3     .07       0
  5012.3      .1       0    5028     .12       0  5038.4     .05       0
#XS Ineff= 2 , 0
       0                 5098.01       0  483.23
Permanent Ineff=
       F       T
Bank Sta=5006.3,5012.3
XS Rating Curve= 0 ,0
Exp/Cntr=0.3,0.1

Type RM Length L Ch R = 1 ,353     ,0,0,0
BEGIN DESCRIPTION:
UNT 012 IN LACR 1.0
END DESCRIPTION:
XS GIS Cut Line= 4
      2159566.43     13200414.15       2159837.7      13200978.4
      2160412.79     13201390.73      2161703.34     13201596.78
#Sta/Elev= 30
  4038.2  505.19  4123.2  503.22  4385.2  493.16  4468.3  491.05  4513.5  488.53
  4649.3  484.64  4777.2  482.32  4971.9  480.72  5008.1  478.97  5035.1  478.97
  5043.7  480.04  5085.4  481.02  5129.6  481.46  5215.6  480.33  5286.9  481.32
  5322.5  480.34  5731.3  479.61  5760.2  478.83  5852.8  479.76  5923.7  479.15
  6140.8  481.61    6270  484.73  6327.1  486.98  6338.9  486.28  6419.9  489.14
  6456.3  491.31  6461.4   490.5  6561.7  494.06  6585.6  494.09  6678.8  498.02
#Mann= 4 ,-1 , 0
  4038.2     .05       0  4971.9    .035       0  5085.4     .05       0
  6678.8      .1       0
#XS Ineff= 2 , 0
       0                 5286.91       0  481.32
Permanent Ineff=
       F       T
Bank Sta=4971.9,5085.4
XS Rating Curve= 0 ,0
Exp/Cntr=0.3,0.1

Chan Stop Cuts=-1
Use User Specified Reach Order=0
Composite Channel Slope=5