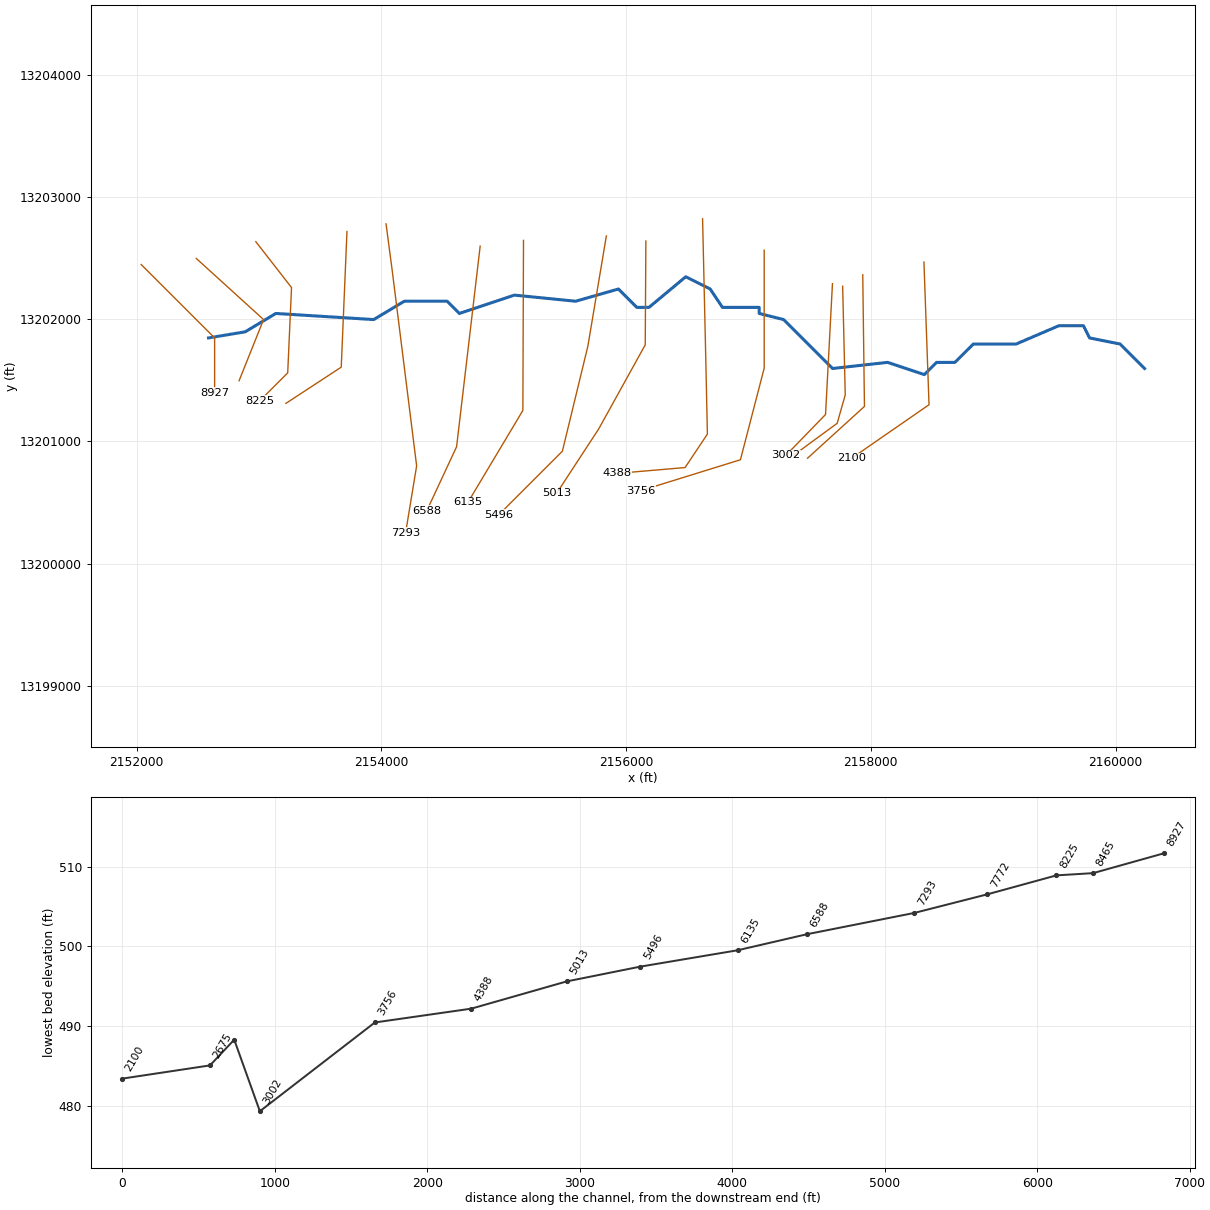
--- UNT 013 IN LACR.prj (project) ---

Proj Title=UNT 013 IN LACR Base Level Engineering
Current Plan=p01
Default Exp/Contr=0.3,0.1
English Units
Geom File=g01
Flow File=f01
Plan File=p01
Y Axis Title=Elevation
X Axis Title(PF)=Main Channel Distance
X Axis Title(XS)=Station
BEGIN DESCRIPTION:
UNT 013 IN LACR
END DESCRIPTION:
DSS Export Rating Curves= 0
DSS Export Rating Curve Sorted= 0
DSS Export Volume Flow Curves= 0
DXF OffsetX= 0
DXF OffsetY= 0
DXF ScaleX= 1
DXF ScaleY= 10

--- UNT 013 IN LACR.p01 (plan) ---

Plan Title=Multiple Run
Short Identifier=Multiple
Geom File=g01
Flow File=f01
Subcritical Flow
K Sum by GR= 0
Std Step Tol= 0.01
Critical Tol= 0.01
Num of Std Step Trials= 20
Max Error Tol= 0.3
Flow Tol Ratio= 0.001
Split Flow NTrial= 30
Split Flow Tol= 0.02
Split Flow Ratio= 0.02
Log Output Level= 0
Friction Slope Method= 1
Unsteady Friction Slope Method= 2
Unsteady Bridges Friction Slope Method= 1
Parabolic Critical Depth
Global Vel Dist=  1 , 1 , 1
Global Log Level= 0
CheckData=True
Encroach Param= -1, 0, 0, 0
BEGIN DESCRIPTION:
Multiple Run
END DESCRIPTION:

--- UNT 013 IN LACR.f01 (steady flow) ---

Flow Title=Multiple
Program Version=4.10
Number of Profiles= 7
Profile Names=10-year,25-year,50-year,1pct_min,100-year,1pct_plu,500-year
River Rch & RM=UNT 013 IN LACR,Reach-1         ,8927
     182     253     313     285     385     521     594
River Rch & RM=UNT 013 IN LACR,Reach-1         ,7772
     242     342     425     390     527     713     823
River Rch & RM=UNT 013 IN LACR,Reach-1         ,7293
     401     582     738     688     930    1258    1503
River Rch & RM=UNT 013 IN LACR,Reach-1         ,3002
     401     582     738     688     930    1258    1503
Boundary for River Rch & Prof#=UNT 013 IN LACR,Reach-1         , 1
Up Type= 0
Dn Type= 3
Dn Slope=0.005
Boundary for River Rch & Prof#=UNT 013 IN LACR,Reach-1         , 2
Up Type= 0
Dn Type= 3
Dn Slope=0.005
Boundary for River Rch & Prof#=UNT 013 IN LACR,Reach-1         , 3
Up Type= 0
Dn Type= 3
Dn Slope=0.005
Boundary for River Rch & Prof#=UNT 013 IN LACR,Reach-1         , 4
Up Type= 0
Dn Type= 3
Dn Slope=0.005
Boundary for River Rch & Prof#=UNT 013 IN LACR,Reach-1         , 5
Up Type= 0
Dn Type= 3
Dn Slope=0.005
Boundary for River Rch & Prof#=UNT 013 IN LACR,Reach-1         , 6
Up Type= 0
Dn Type= 3
Dn Slope=0.005
Boundary for River Rch & Prof#=UNT 013 IN LACR,Reach-1         , 7
Up Type= 0
Dn Type= 3
Dn Slope=0.005
DSS Import GetInterval= 0
DSS Import GetPeak= 0
DSS Import FillOption= 0

--- UNT 013 IN LACR.g01 (geometry) ---

Geom Title=Existing Conditions
Program Version=4.10

River Reach=UNT 013 IN LACR ,Reach-1
Reach XY= 30
      2152587.72     13201846.86      2152887.72     13201896.85
      2153137.72     13202046.85      2153937.72     13201996.86
      2154187.72     13202146.86      2154537.72     13202146.86
      2154637.72     13202046.85      2155087.72     13202196.85
      2155587.72     13202146.86      2155937.72     13202246.85
      2156087.72     13202096.85      2156187.72     13202096.85
      2156487.72     13202346.85      2156687.72     13202246.85
      2156787.72     13202096.85      2157087.72     13202096.85
      2157087.72     13202046.85      2157287.72     13201996.86
      2157687.72     13201596.85      2158137.72     13201646.86
      2158437.72     13201546.85      2158537.72     13201646.86
      2158687.72     13201646.86      2158837.72     13201796.85
      2159187.72     13201796.85      2159537.72     13201946.85
      2159737.72     13201946.85      2159787.72     13201846.86
      2160037.72     13201796.85      2160237.72     13201596.85

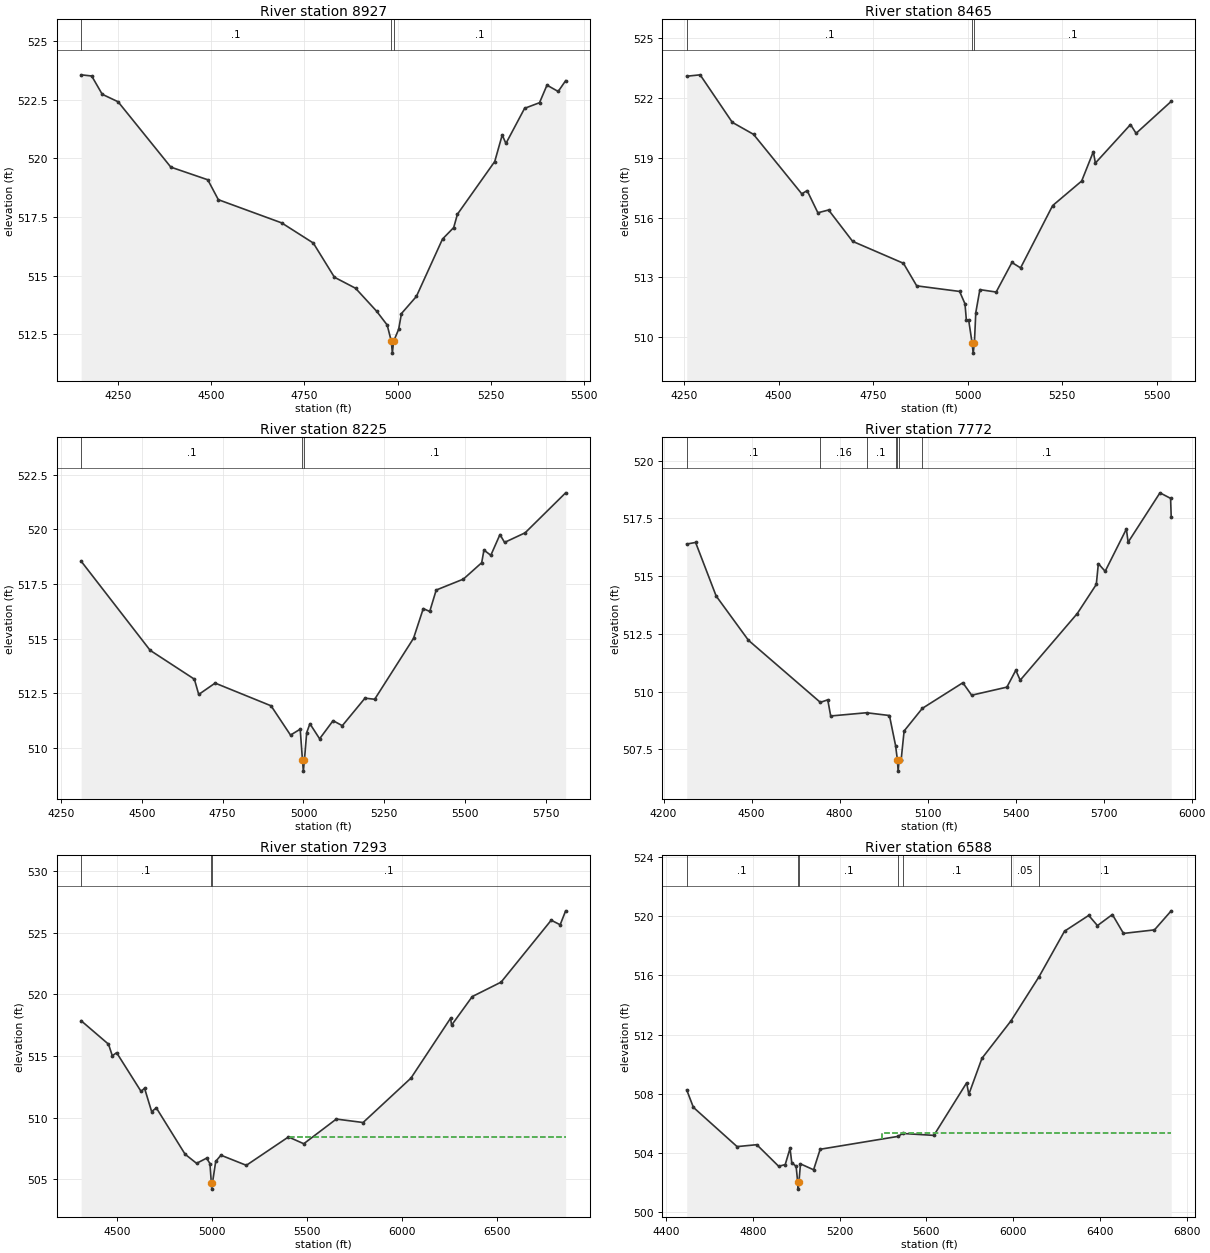
Type RM Length L Ch R = 1 ,8927    ,462,462,462
BEGIN DESCRIPTION:
UNT 013 IN LACR 8.0
END DESCRIPTION:
XS GIS Cut Line= 3
      2152037.74     13202446.84      2152637.72     13201846.86
      2152637.72     13201396.86
#Sta/Elev= 30
  4151.5  523.57  4179.8  523.52    4208  522.74  4250.5  522.42  4391.9  519.63
  4490.9  519.09  4519.2  518.24  4688.9  517.25  4773.7  516.39  4830.3  514.93
  4886.9  514.46  4943.4  513.48  4971.7  512.89  4982.9  512.19  4985.6  511.69
  4988.9  512.19  5002.5  512.71    5010  513.38    5050  514.11    5120  516.56
    5150  517.05    5160  517.62    5260  519.87    5280     521    5290  520.64
    5340  522.14    5380  522.38    5400  523.13    5430  522.86    5450  523.32
#Mann= 3 ,-1 , 0
  4151.5      .1       0  4982.9     .07       0  4988.9      .1       0
Bank Sta=4982.9,4988.9
XS Rating Curve= 0 ,0
Exp/Cntr=0.3,0.1

Type RM Length L Ch R = 1 ,8465    ,240,240,240
BEGIN DESCRIPTION:
UNT 013 IN LACR 7.0
END DESCRIPTION:
XS GIS Cut Line= 3
      2152487.72     13202496.85      2153037.72     13201996.86
      2152837.73     13201496.87
#Sta/Elev= 30
  4256.7  523.08  4292.2  523.15  4377.3  520.77  4433.4  520.17  4561.1  517.19
  4575.3  517.35  4603.7  516.24  4632.1  516.38  4695.6  514.81  4830.1  513.71
  4865.2  512.58  4978.7   512.3  4992.9  511.68  4996.6  510.86  5002.7  510.86
  5011.8  509.71  5014.6  509.21  5017.8  509.71  5021.5  511.24  5032.3  512.39
  5075.4  512.27  5117.1  513.75    5140  513.48  5224.8   516.6  5301.6  517.83
  5332.5   519.3  5337.9  518.73  5430.8  520.66  5445.6  520.22  5538.5  521.82
#Mann= 3 ,-1 , 0
  4256.7      .1       0  5011.8     .07       0  5017.8      .1       0
Bank Sta=5011.8,5017.8
XS Rating Curve= 0 ,0
Exp/Cntr=0.3,0.1

Type RM Length L Ch R = 1 ,8225    ,453,453,453
BEGIN DESCRIPTION:
UNT 013 IN LACR 6.0
END DESCRIPTION:
XS GIS Cut Line= 4
       2152974.5     13202633.77      2153266.15      13202258.8
       2153234.9     13201560.88      2153005.77     13201331.75
#Sta/Elev= 30
  4312.8  518.54  4526.1  514.46  4662.8  513.14  4676.3  512.44    4727  512.96
  4899.9  511.92    4960  510.58    4990  510.85    4997  509.43  4999.7  508.93
    5003  509.43    5010  510.69    5020   511.1    5050  510.41  5091.6  511.24
  5120.1  511.01  5190.2  512.27  5220.2  512.22  5340.3  515.01  5370.4  516.37
  5390.4  516.24  5410.4  517.22  5494.4  517.72    5551  518.47    5558  519.05
  5579.2  518.81  5607.5  519.76  5621.7   519.4  5685.3  519.84  5810.5  521.67
#Mann= 3 ,-1 , 0
  4312.8      .1       0    4997     .07       0    5003      .1       0
Bank Sta=4997,5003
XS Rating Curve= 0 ,0
Exp/Cntr=0.3,0.1

Type RM Length L Ch R = 1 ,7772    ,479,479,479
BEGIN DESCRIPTION:
UNT 013 IN LACR 5.0
END DESCRIPTION:
XS GIS Cut Line= 3
      2153719.27     13202717.11       2153672.4     13201607.75
        2153220.     13201311.35
#Sta/Elev= 30
  4279.1  516.39  4309.4  516.46  4379.4  514.14  4489.5  512.22  4734.5  509.53
  4759.8  509.64  4769.8  508.94  4891.9  509.08    4970  508.96  4990.9  507.66
    4997  507.05  4999.7  506.55    5003  507.05    5010  507.05    5020  508.29
  5082.1  509.27  5220.2  510.38  5250.2  509.84  5370.3  510.19  5400.6  510.92
  5415.7  510.49  5610.2  513.38    5675  514.64    5682  515.54  5705.2  515.21
  5777.5  517.04  5783.5  516.47    5892  518.61  5928.2  518.37  5930.3  517.57
#Mann= 7 ,-1 , 0
  4279.1      .1       0  4734.5     .16       0  4891.9      .1       0
  4990.9     .12       0    4997     .07       0    5003     .12       0
  5082.1      .1       0
Bank Sta=4997,5003
XS Rating Curve= 0 ,0
Exp/Cntr=0.3,0.1

Type RM Length L Ch R = 1 ,7293    ,705,705,705
BEGIN DESCRIPTION:
UNT 013 IN LACR 4.0
END DESCRIPTION:
XS GIS Cut Line= 4
       2154038.6     13202779.61      2154087.21     13202411.55
       2154288.6     13200800.44      2154198.32     13200251.82
#Sta/Elev= 30
  4311.6  517.86  4455.6  515.96  4475.8  515.02  4498.4  515.27  4627.1  512.13
  4645.4  512.39  4682.7   510.5  4707.7  510.79  4858.9  507.04  4919.4   506.3
    4972  506.72  4989.9  506.28    4997  504.71  4999.8  504.21    5003  504.71
  5020.2  506.46  5047.6  506.96  5181.4  506.14  5403.1  508.44  5483.7  507.89
  5655.1  509.89  5796.1  509.61  6048.1  513.21  6256.9  518.07  6261.9   517.5
  6370.9  519.82  6522.7  520.99  6786.5  526.01  6833.7  525.64  6862.5  526.77
#Mann= 3 ,-1 , 0
  4311.6      .1       0    4997     .07       0    5003      .1       0
#XS Ineff= 2 , 0
                         5413.07          508.45
Permanent Ineff=
       F       F
Bank Sta=4997,5003
XS Rating Curve= 0 ,0
Exp/Cntr=0.3,0.1

Type RM Length L Ch R = 1 ,6588    ,453,453,453
BEGIN DESCRIPTION:
UNT 013 IN LACR 3.0
END DESCRIPTION:
XS GIS Cut Line= 4
      2154807.81     13202597.32      2154708.86     13201753.59
      2154615.11     13200956.71      2154370.61     13200431.31
#Sta/Elev= 30
  4496.1  508.25  4526.8  507.07  4728.1  504.41  4818.8  504.54  4919.5  503.08
  4949.7  503.19  4971.9  504.29  4979.9  503.33    5000  503.07  5007.1  502.03
  5009.8  501.53  5013.1  502.03  5020.1  503.24  5080.5  502.84  5110.8  504.23
  5468.5   505.1  5491.3   505.3  5634.3  505.17  5785.4  508.73  5795.4  507.95
  5855.8  510.39  5989.2  512.92  6118.9  515.92  6236.1     519  6347.6  520.07
  6387.8  519.38  6456.5  520.13  6507.7  518.85  6650.5  519.09  6727.5  520.38
#Mann= 7 ,-1 , 0
  4496.1      .1       0  5007.1     .07       0  5013.1      .1       0
  5468.5     .12       0  5491.3      .1       0  5989.2     .05       0
  6118.9      .1       0
#XS Ineff= 2 , 0
       0                 5396.02       0  505.32
Permanent Ineff=
       F       T
Bank Sta=5007.1,5013.1
XS Rating Curve= 0 ,0
Exp/Cntr=0.3,0.1

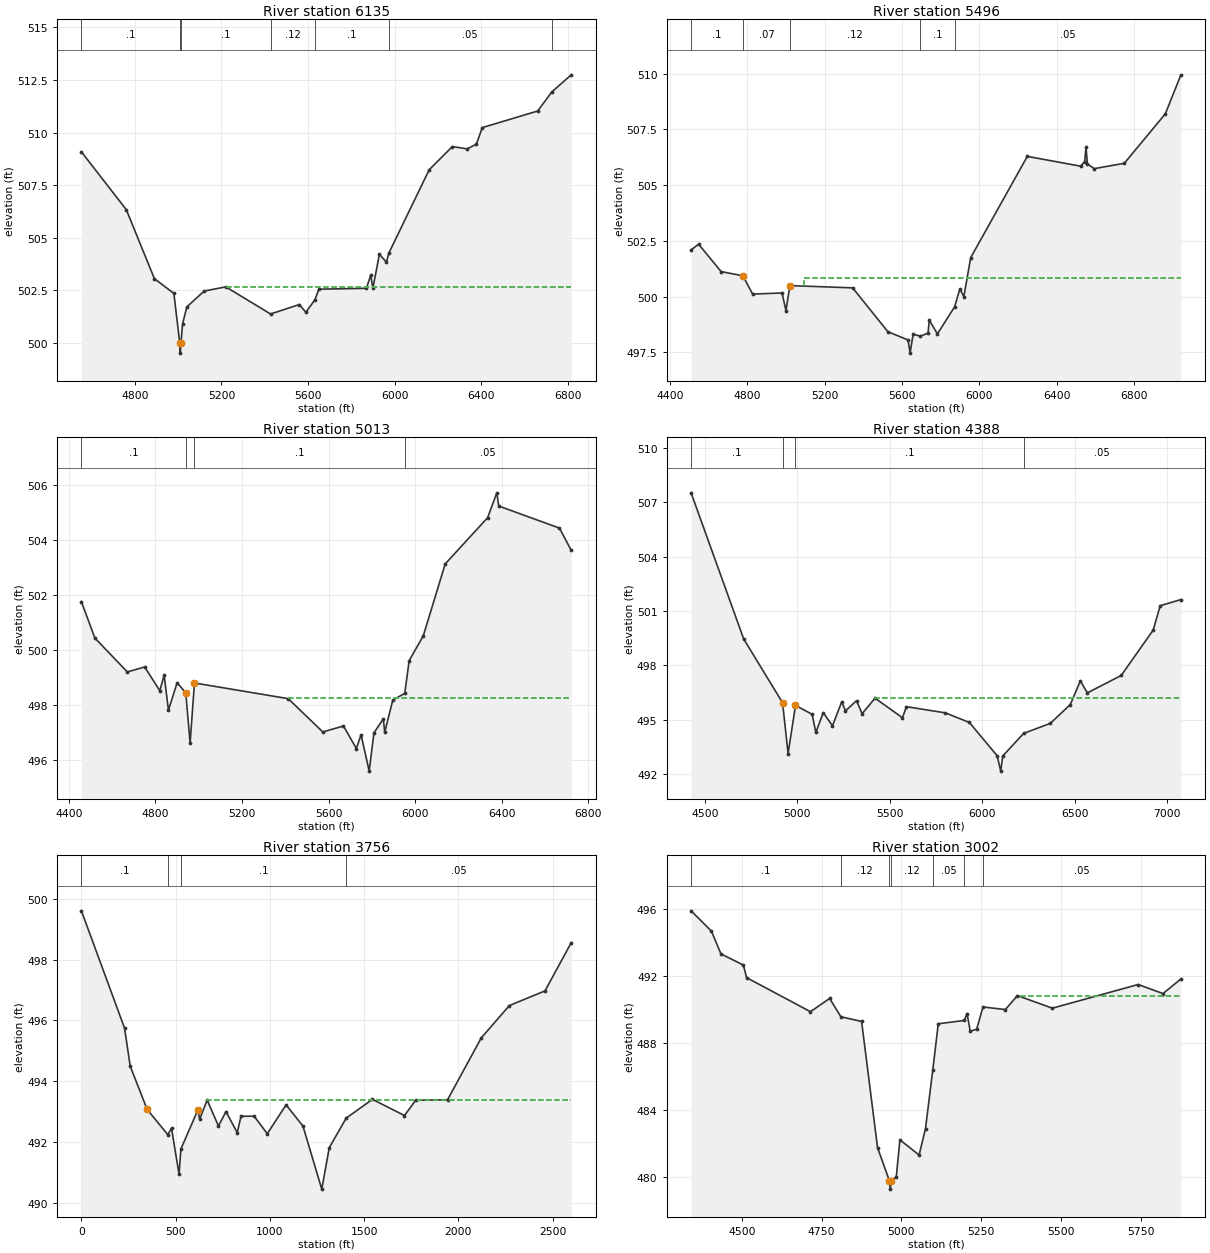
Type RM Length L Ch R = 1 ,6135    ,639,639,639
BEGIN DESCRIPTION:
UNT 013 IN LACR 2.0
END DESCRIPTION:
XS GIS Cut Line= 3
      2155161.98     13202644.25      2155156.77     13201253.59
      2154708.88     13200503.63
#Sta/Elev= 30
  4552.6  509.09    4760  506.34    4890  503.06    4980  502.36    5007  500.02
  5009.8  499.52    5013  500.02    5020   500.9    5040  501.72    5120  502.47
    5220  502.67    5427  501.38    5560  501.83    5590  501.46  5632.2  502.06
    5650  502.56    5870   502.6    5890  503.23    5900  502.61    5930  504.22
  5962.8  503.84  5972.9  504.26  6160.3  508.24  6267.3  509.34  6335.5  509.23
  6378.2  509.45  6405.5  510.24  6661.6  511.03  6727.3  511.94  6816.8  512.75
#Mann= 7 ,-1 , 0
  4552.6      .1       0    5007     .07       0    5013      .1       0
    5427     .12       0  5632.2      .1       0  5972.9     .05       0
  6727.3      .1       0
#XS Ineff= 2 , 0
       0                 5220.17       0  502.67
Permanent Ineff=
       F       T
Bank Sta=5007,5013
XS Rating Curve= 0 ,0
Exp/Cntr=0.3,0.1

Type RM Length L Ch R = 1 ,5496    ,483,483,483
BEGIN DESCRIPTION:
Mapping XS 53a85026
END DESCRIPTION:
XS GIS Cut Line= 4
      2155839.07      13202680.7      2155688.02     13201779.63
      2155479.69     13200920.25      2154960.05     13200400.61
#Sta/Elev= 30
  4509.4  502.09  4548.3  502.35  4664.6  501.12  4776.9  500.93  4827.6  500.11
  4979.7  500.16    5000  499.37  5020.3  500.49  5344.7  500.39    5527  498.42
  5631.7  498.05  5641.7  497.46  5657.6  498.31  5695.3  498.22  5734.6  498.36
  5741.2  498.94    5783  498.32    5872  499.54  5899.2  500.34  5919.8     500
  5955.4  501.75    6248  506.29  6523.2  505.85  6544.5  506.06  6551.5  506.71
  6558.6  505.95    6594  505.74  6749.5  505.98  6961.6   508.2  7042.2  509.95
#Mann= 5 ,-1 , 0
  4509.4      .1       0  4776.9     .07       0  5020.3     .12       0
  5695.3      .1       0    5872     .05       0
#XS Ineff= 2 , 0
       0                 5093.18       0  500.85
Permanent Ineff=
       F       T
Bank Sta=4776.9,5020.3
XS Rating Curve= 0 ,0
Exp/Cntr=0.3,0.1

Type RM Length L Ch R = 1 ,5013    ,625,625,625
BEGIN DESCRIPTION:
Mapping XS 2761618c
END DESCRIPTION:
XS GIS Cut Line= 4
      2156161.98     13202639.04      2156156.77     13201790.05
      2155776.56     13201102.55      2155432.84     13200576.54
#Sta/Elev= 30
  4457.8  501.75    4520  500.43    4670   499.2    4750  499.38    4820  498.52
    4840  499.08    4860  497.81    4900  498.81    4940  498.44    4960  496.62
    4980   498.8    5413  498.23  5573.3  497.02  5668.4  497.24    5728  496.42
  5749.8  496.92  5787.3   495.6  5809.3  496.99  5852.8   497.5    5859  497.01
  5896.4  498.18  5951.6  498.42    5972  499.61  6037.2  500.51  6138.5  503.12
  6334.7   504.8  6376.8   505.7  6385.9  505.22  6666.4  504.42  6720.8  503.61
#Mann= 4 ,-1 , 0
  4457.8      .1       0    4940     .07       0    4980      .1       0
  5951.6     .05       0
#XS Ineff= 2 , 0
       0                 5414.77       0  498.27
Permanent Ineff=
       F       T
Bank Sta=4940,4980
XS Rating Curve= 0 ,0
Exp/Cntr=0.3,0.1

Type RM Length L Ch R = 1 ,4388    ,632,632,632
BEGIN DESCRIPTION:
Mapping XS bc198a1a1
END DESCRIPTION:
XS GIS Cut Line= 5
      2156625.52     13202821.31      2156651.56     13201675.46
      2156664.73     13201060.01      2156482.29     13200786.57
      2155925.98     13200738.81
#Sta/Elev= 30
  4425.4  507.51  4709.9  499.46    4920  495.95    4950  493.15    4990   495.8
    5080  495.31    5100  494.31    5140   495.4    5190  494.68  5240.1     496
  5260.1   495.5  5320.1  496.06  5350.1  495.34  5420.1   496.2  5568.3  495.12
  5590.2  495.73  5800.2  495.39  5930.2  494.86  6080.3  493.03    6100  492.18
  6110.3  493.01  6223.9  494.26  6368.1  494.81  6476.2  495.85  6530.5  497.15
  6568.3  496.49  6751.3  497.45  6924.3  499.95  6962.1  501.29  7074.2  501.63
#Mann= 4 ,-1 , 0
  4425.4      .1       0    4920     .05       0    4990      .1       0
  6223.9     .05       0
#XS Ineff= 2 , 0
       0                  5417.9       0  496.19
Permanent Ineff=
       F       T
Bank Sta=4920,4990
XS Rating Curve= 0 ,0
Exp/Cntr=0.3,0.1

Type RM Length L Ch R = 1 ,3756    ,754,754,754
BEGIN DESCRIPTION:
Mapping XS bc198a1a
END DESCRIPTION:
XS GIS Cut Line= 4
      2157128.87     13202564.35      2157128.87     13201599.05
      2156934.78     13200850.41     2156116.385    13200596.203
#Sta/Elev= 30
       0499.6059229.0862495.7401 258.967494.4903348.6094493.0705458.1724492.2372
478.0929 492.448 517.934490.9374527.8942491.7671617.5367 493.045627.4969492.7533
 667.338493.3765727.0996492.5215766.9407492.9984826.7023492.3039846.6229492.8426
916.3447492.8466986.0828 492.2681085.767493.21911175.482492.51991275.166 490.445
 1315.04491.80991404.755492.78241544.313493.40051713.775492.86781773.508493.3693
1942.534493.38742121.503495.42412270.643496.48842459.554496.97122598.752498.5585
#Mann= 4 ,-1 , 0
       0      .1       0458.1724     .07       0527.8942      .1       0
1404.755     .05       0
#XS Ineff= 2 , 0
                          664.77          493.38
Permanent Ineff=
       F       F
Bank Sta=348.6094,617.5367
XS Rating Curve= 0 ,0
Exp/Cntr=0.3,0.1

Type RM Length L Ch R = 1 ,3002    ,168,168,168
BEGIN DESCRIPTION:
Mapping XS 8cc7a7b7
END DESCRIPTION:
XS GIS Cut Line= 3
      2157686.85     13202290.49       2157630.3      13201220.6
      2157307.58     13200887.46
#Sta/Elev= 30
  4341.1  495.87  4404.8  494.66  4434.9   493.3    4505  492.64    4515  491.89
  4715.3  489.86  4775.3  490.65  4810.6  489.56  4875.5  489.28  4925.5  481.76
  4962.6  479.79  4965.4  479.29  4968.6  479.79  4984.2  480.02  4995.6  482.23
  5055.7  481.32  5075.8   482.9  5098.5  486.37  5115.8  489.14  5197.6  489.34
  5205.9  489.75    5216   488.7    5236  488.81    5256  490.14  5326.1  489.99
  5363.9  490.82  5473.4  490.07  5742.2  491.48  5820.1  490.94  5876.3  491.81
#Mann= 7 ,-1 , 0
  4341.1      .1       0  4810.6     .12       0  4962.6     .07       0
  4968.6     .12       0  5098.5     .05       0  5197.6      .1       0
    5256     .05       0
#XS Ineff= 2 , 0
                         5376.14          490.82
Permanent Ineff=
       F       F
Bank Sta=4962.6,4968.6
XS Rating Curve= 0 ,0
Exp/Cntr=0.3,0.1

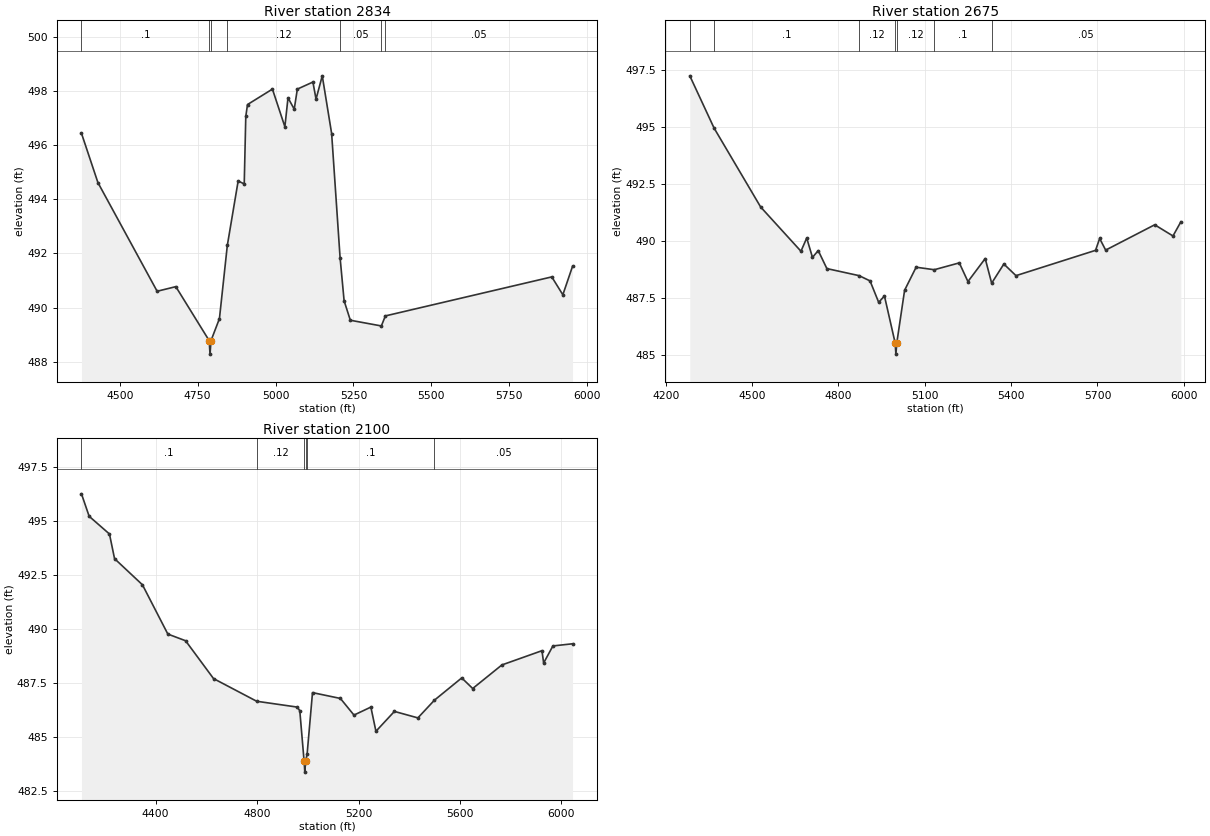
Type RM Length L Ch R = 1 ,2834    ,159,159,159
BEGIN DESCRIPTION:
Mapping XS bbbff698
END DESCRIPTION:
XS GIS Cut Line= 4
      2157770.19     13202269.68      2157791.32     13201381.19
      2157725.35     13201148.55      2157365.98     13200884.67
#Sta/Elev= 30
    4377  496.43  4429.8  494.61  4619.9   490.6  4679.9  490.77  4786.9  488.78
  4789.7  488.28  4792.9  488.78  4819.9  489.59  4845.2  492.29    4880  494.67
  4899.5  494.56  4904.5  497.05    4910  497.49    4990  498.06    5030  496.67
    5040  497.74    5060  497.32    5070  498.06    5120  498.32    5130  497.69
    5150  498.55  5180.1  496.42  5207.2  491.84  5220.1  490.25  5240.1  489.53
  5339.7  489.32  5352.6  489.69  5886.8  491.13  5922.3  490.47  5953.4  491.52
#Mann= 7 ,-1 , 0
    4377      .1       0  4786.9     .07       0  4792.9      .1       0
  4845.2     .12       0  5207.2     .05       0  5339.7      .1       0
  5352.6     .05       0
Bank Sta=4786.9,4792.9
XS Rating Curve= 0 ,0
Exp/Cntr=0.3,0.1

Type RM Length L Ch R = 1 ,2675    ,575,575,575
BEGIN DESCRIPTION:
Mapping XS 86212655
END DESCRIPTION:
XS GIS Cut Line= 3
      2157934.43      13202362.9      2157948.32     13201286.55
      2157483.01     13200862.92
#Sta/Elev= 30
  4283.9  497.25  4368.2  494.96    4530   491.5    4670  489.56    4690  490.14
    4710  489.29    4730  489.59    4760   488.8  4872.1  488.49    4910  488.26
    4940  487.32    4960   487.6    4997  485.55  4999.8  485.05    5003  485.55
    5030  487.85    5070  488.86  5133.1  488.75    5220  489.05    5250  488.23
    5310  489.24  5332.4  488.16  5374.7     489  5416.9  488.49  5693.3   489.6
  5707.5  490.12  5728.4  489.61  5898.7  490.72  5962.2  490.23  5989.6  490.85
#Mann= 7 ,-1 , 0
  4283.9     .05       0  4368.2      .1       0  4872.1     .12       0
    4997     .07       0    5003     .12       0  5133.1      .1       0
  5332.4     .05       0
Bank Sta=4997,5003
XS Rating Curve= 0 ,0
Exp/Cntr=0.3,0.1

Type RM Length L Ch R = 1 ,2100    ,0,0,0
BEGIN DESCRIPTION:
UNT 013 IN LACR 1.0
END DESCRIPTION:
XS GIS Cut Line= 3
      2158434.43     13202467.14       2158476.1     13201300.44
      2157844.11     13200862.91
#Sta/Elev= 30
  4107.7  496.27    4138  495.23  4218.1  494.41  4238.1  493.27  4348.1  492.06
  4448.2  489.78  4518.2  489.47  4628.3  487.72  4798.5  486.67  4958.5   486.4
  4968.5  486.23  4985.5  483.89  4988.3  483.39  4991.5  483.89  4997.4  484.23
  5018.6  487.07  5128.6   486.8  5182.1  486.03  5248.7   486.4  5268.7  485.28
  5341.5   486.2  5434.1   485.9  5499.3  486.72    5607  487.75  5650.2  487.26
  5765.2  488.35  5923.3  489.01  5929.9  488.44  5966.4  489.23  6043.8  489.33
#Mann= 6 ,-1 , 0
  4107.7      .1       0  4798.5     .12       0  4985.5     .07       0
  4991.5     .12       0  4997.4      .1       0  5499.3     .05       0
Bank Sta=4985.5,4991.5
XS Rating Curve= 0 ,0
Exp/Cntr=0.3,0.1

Chan Stop Cuts=-1
Use User Specified Reach Order=0
Composite Channel Slope=5