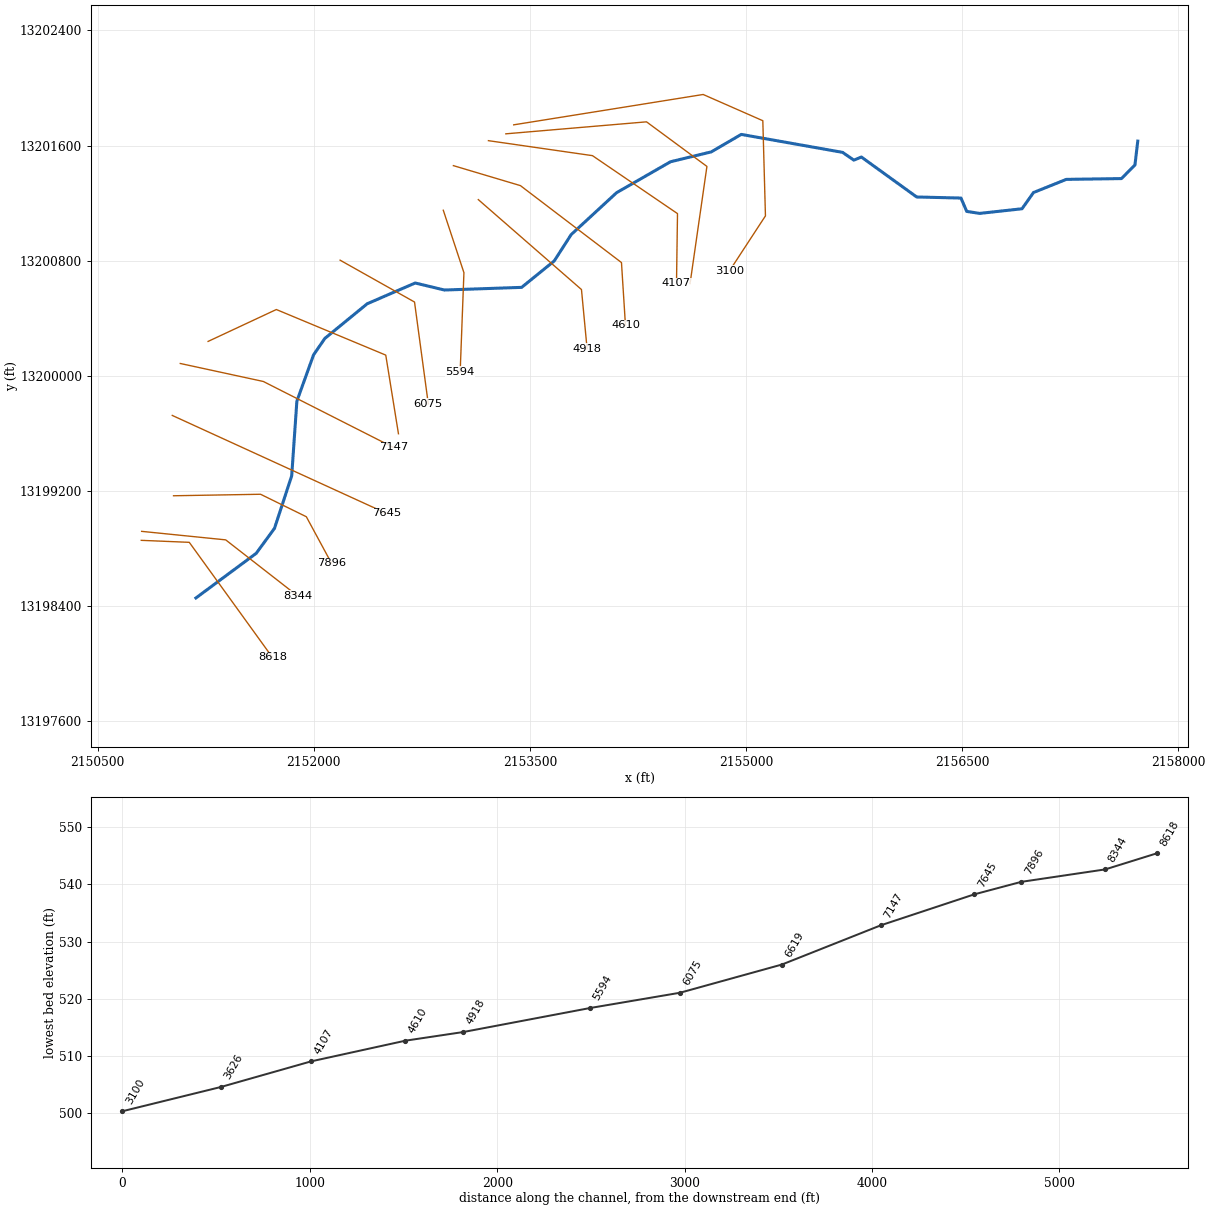
--- UNT 014 IN LACR.prj (project) ---

Proj Title=UNT 014 IN LACR Base Level Engineering
Current Plan=p01
Default Exp/Contr=0.3,0.1
English Units
Geom File=g01
Geom File=g02
Flow File=f01
Plan File=p01
Y Axis Title=Elevation
X Axis Title(PF)=Main Channel Distance
X Axis Title(XS)=Station
BEGIN DESCRIPTION:
UNT 014 IN LACR
END DESCRIPTION:
DSS Export Rating Curves= 0
DSS Export Rating Curve Sorted= 0
DSS Export Volume Flow Curves= 0
DXF OffsetX= 0
DXF OffsetY= 0
DXF ScaleX= 1
DXF ScaleY= 10

--- UNT 014 IN LACR.p01 (plan) ---

Plan Title=Multiple Run
Short Identifier=Multiple
Geom File=g01
Flow File=f01
Subcritical Flow
K Sum by GR= 0
Std Step Tol= 0.01
Critical Tol= 0.01
Num of Std Step Trials= 20
Max Error Tol= 0.3
Flow Tol Ratio= 0.001
Split Flow NTrial= 30
Split Flow Tol= 0.02
Split Flow Ratio= 0.02
Log Output Level= 0
Friction Slope Method= 1
Unsteady Friction Slope Method= 2
Unsteady Bridges Friction Slope Method= 1
Parabolic Critical Depth
Global Vel Dist=  1 , 1 , 1
Global Log Level= 0
CheckData=True
Encroach Param= -1, 0, 0, 0
BEGIN DESCRIPTION:
Multiple Run
END DESCRIPTION:

--- UNT 014 IN LACR.f01 (steady flow) ---

Flow Title=Multiple
Number of Profiles=7
Profile Names=10-year,25-year,50-year,1pct_min,100-year,1pct_plu,500-year
River Rch & RM= UNT 014 IN LACR,Reach-1,8618
     196     275     341     312     422     571     656
River Rch & RM= UNT 014 IN LACR,Reach-1,7147
     207     290     359     328     444     600     688
Boundary for River Rch & Prof#=UNT 014 IN LACR,Reach-1,1
Up Type=0
Dn Type=3
Dn Slope=0.005
Boundary for River Rch & Prof#=UNT 014 IN LACR,Reach-1,2
Up Type=0
Dn Type=3
Dn Slope=0.005
Boundary for River Rch & Prof#=UNT 014 IN LACR,Reach-1,3
Up Type=0
Dn Type=3
Dn Slope=0.005
Boundary for River Rch & Prof#=UNT 014 IN LACR,Reach-1,4
Up Type=0
Dn Type=3
Dn Slope=0.005
Boundary for River Rch & Prof#=UNT 014 IN LACR,Reach-1,5
Up Type=0
Dn Type=3
Dn Slope=0.005
Boundary for River Rch & Prof#=UNT 014 IN LACR,Reach-1,6
Up Type=0
Dn Type=3
Dn Slope=0.005
Boundary for River Rch & Prof#=UNT 014 IN LACR,Reach-1,7
Up Type=0
Dn Type=3
Dn Slope=0.005

--- UNT 014 IN LACR.g01 (geometry) ---

Geom Title=Existing Conditions
Program Version=4.10

River Reach=UNT 014 IN LACR ,Reach-1
Reach XY= 30
      2151182.13     13198455.66      2151600.63     13198765.96
      2151727.36     13198939.57      2151846.75     13199304.48
      2151882.55     13199823.14      2151998.66     13200145.41
      2152076.78     13200259.34      2152370.84     13200500.22
      2152703.95     13200644.54      2152906.86     13200595.71
      2153442.88     13200614.16      2153669.03     13200797.73
      2153786.74     13200981.05      2154101.84     13201272.11
      2154476.33     13201487.18      2154758.93     13201555.69
      2154967.27     13201677.22      2155670.87     13201552.39
      2155748.58     13201498.56      2155801.24     13201519.91
      2156185.06     13201242.37      2156492.32     13201234.85
      2156532.37     13201142.05      2156622.67     13201128.26
      2156916.37     13201160.52      2156995.86     13201273.28
      2157223.61     13201364.69      2157606.63     13201370.23
      2157700.16     13201465.15      2157719.61     13201630.75

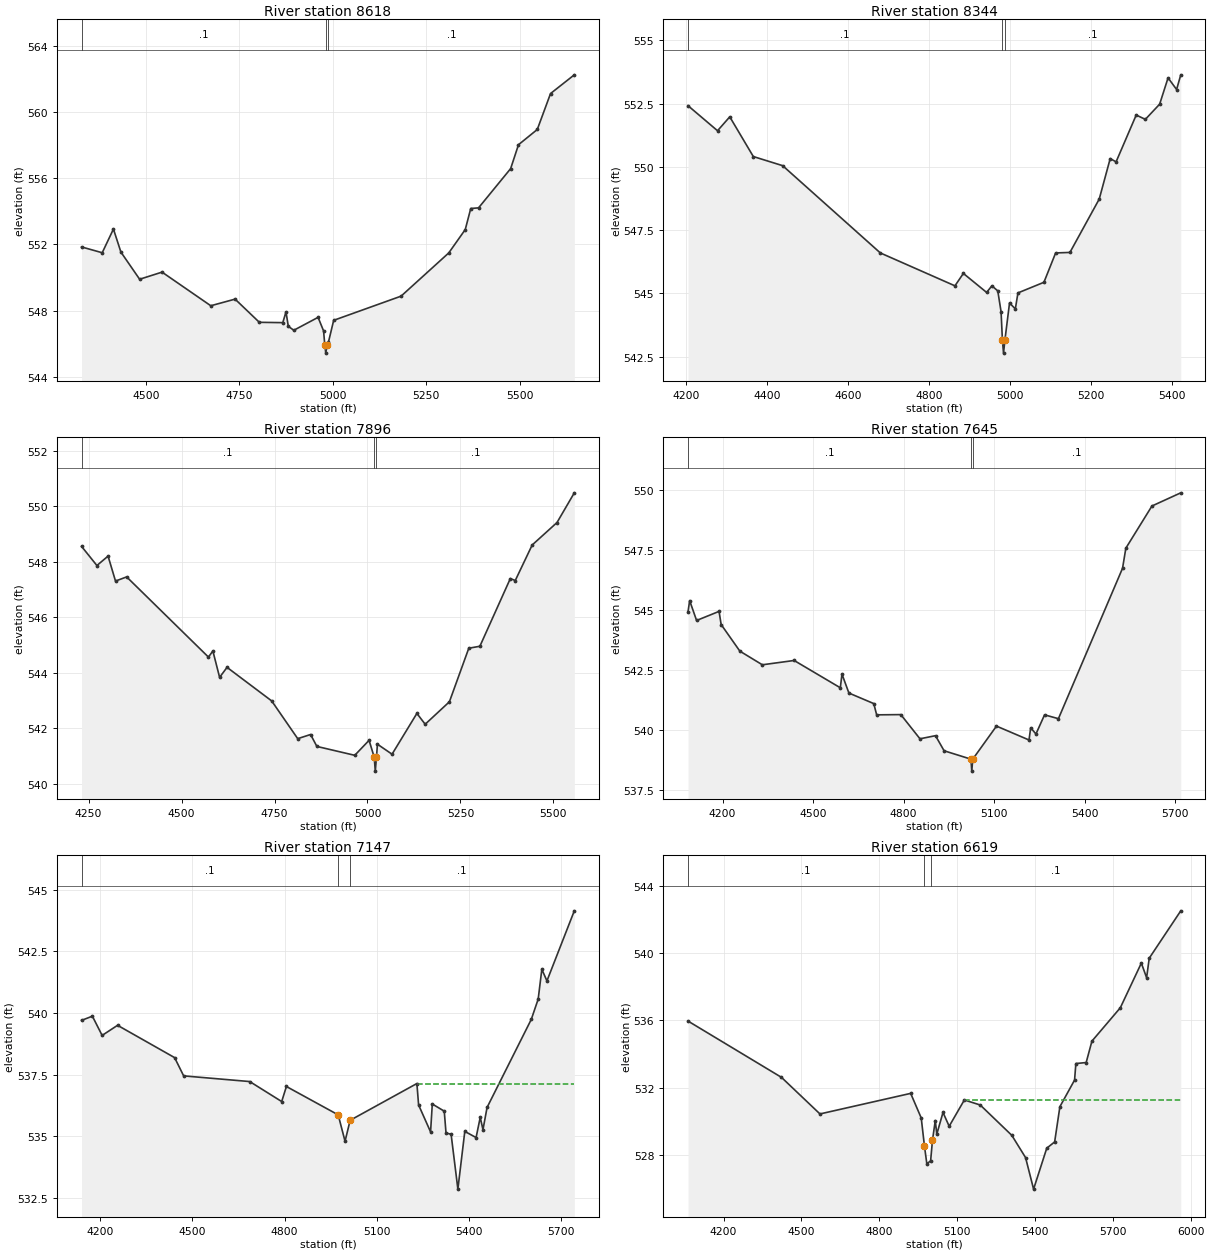
Type RM Length L Ch R = 1 ,8618    ,274,274,274
BEGIN DESCRIPTION:
UNT 014 IN LACR 8.0
END DESCRIPTION:
XS GIS Cut Line= 4
2150802.3104661513198856.0083152      2150802.51       13198856.
      2151135.82     13198842.112151712.1031251713198043.6419357
#Sta/Elev= 30
  4328.1  551.85  4383.4   551.5  4413.4  552.93  4433.4  551.54  4483.5   549.9
  4543.5  550.33  4673.9   548.3  4738.9   548.7  4803.8   547.3  4866.6  547.28
  4875.1  547.93  4881.3  547.06    4896  546.82    4961   547.6  4975.7  546.78
  4978.9  545.94  4981.6  545.44  4984.9  545.94  4988.8  546.11  5002.7  547.42
  5183.1  548.88  5310.7  551.49  5354.8   552.9  5369.5  554.17  5390.4  554.21
  5476.3  556.58  5497.2  558.02  5547.5  558.94    5583  561.11  5646.6  562.24
#Mann= 3 ,-1 , 0
  4328.1      .1       0  4981.6     .07       0  4988.8      .1       0
Bank Sta=4978.9,4984.9
XS Rating Curve= 0 ,0
Exp/Cntr=0.3,0.1

Type RM Length L Ch R = 1 ,8344    ,448,448,448
BEGIN DESCRIPTION:
UNT 014 IN LACR 7.0
END DESCRIPTION:
XS GIS Cut Line= 3
      2150805.16     13198918.42      2151388.46     13198859.31
      2151885.84     13198471.31
#Sta/Elev= 30
  4205.5  552.42  4278.4  551.43  4308.6  551.98  4366.8  550.41  4439.2  550.05
  4680.5   546.6  4864.8   545.3  4885.6  545.79    4943  545.04  4956.1   545.3
  4970.6   545.1  4978.7  544.28  4982.1  543.14  4984.8  542.64  4988.1  543.14
  4999.6  544.62    5014  544.39  5020.4  545.02  5084.6  545.44  5113.5   546.6
  5148.8  546.62  5221.2  548.73  5248.3  550.33  5262.8   550.2  5312.5  552.05
  5335.1  551.88  5370.4  552.48  5391.2  553.52  5412.3  553.06  5422.6  553.64
#Mann= 3 ,-1 , 0
  4205.5      .1       0  4982.1     .07       0  4988.1      .1       0
Bank Sta=4982.1,4988.1
XS Rating Curve= 0 ,0
Exp/Cntr=0.3,0.1

Type RM Length L Ch R = 1 ,7896    ,251,251,251
BEGIN DESCRIPTION:
UNT 014 IN LACR 6.0
END DESCRIPTION:
XS GIS Cut Line= 4
      2151026.45     13199165.82      2151630.65     13199176.24
      2151948.36     13199019.99       2152122.8     13198697.15
#Sta/Elev= 30
    4231  548.56  4272.3  547.87  4302.3  548.21  4322.3  547.31  4352.3  547.46
  4572.3  544.57  4584.2  544.79  4602.3  543.84  4622.3   544.2  4742.4  542.99
  4812.4  541.63    4847  541.78  4863.9  541.35  4965.8  541.03  5004.3  541.57
  5018.2  540.96    5021  540.46  5024.2  540.96  5026.8  541.43  5066.1  541.07
  5132.9  542.54  5155.2  542.15  5220.4  542.96  5272.5  544.89  5302.3  544.96
  5384.2   547.4  5397.5  547.33    5443  548.61  5509.8  549.42  5556.3  550.49
#Mann= 3 ,-1 , 0
    4231      .1       0  5018.2     .07       0  5024.2      .1       0
Bank Sta=5018.2,5024.2
XS Rating Curve= 0 ,0
Exp/Cntr=0.3,0.1

Type RM Length L Ch R = 1 ,7645    ,498,498,498
BEGIN DESCRIPTION:
UNT 014 IN LACR 5.0
END DESCRIPTION:
XS GIS Cut Line= 2
      2151017.78     13199724.05      2152503.32     13199043.75
#Sta/Elev= 30
  4085.3  544.92  4090.7  545.39  4113.7  544.56  4188.2  544.94  4195.2  544.39
  4257.2  543.28  4331.7  542.71  4437.2  542.89  4590.3  541.75  4595.8  542.32
  4618.8  541.53  4701.2  541.09  4710.8  540.62  4790.9  540.63  4854.4  539.62
  4905.9  539.75  4934.4  539.12  5023.4  538.77  5026.2  538.27  5029.4  538.77
  5108.1  540.15    5216  539.57  5221.5  540.08    5239  539.82  5267.5  540.62
  5313.5  540.46  5526.1  546.74  5537.1  547.58  5623.6  549.34  5719.2  549.89
#Mann= 3 ,-1 , 0
  4085.3      .1       0  5023.4     .07       0  5029.4      .1       0
Bank Sta=5023.4,5029.4
XS Rating Curve= 0 ,0
Exp/Cntr=0.3,0.1

Type RM Length L Ch R = 1 ,7147    ,528,528,528
BEGIN DESCRIPTION:
UNT 014 IN LACR 4.0
END DESCRIPTION:
XS GIS Cut Line= 3
      2151073.29     13200085.17      2151649.71     13199960.16
       2152552.5     13199501.82
#Sta/Elev= 30
  4139.7   539.7  4174.9  539.87  4206.6  539.09  4256.8   539.5  4442.3  538.19
  4471.7  537.45  4686.6  537.22  4790.5  536.41  4805.8  537.02  4974.2  535.87
  4996.5   534.8  5013.1  535.65  5230.1  537.14  5235.7  536.27  5274.6  535.18
  5280.2  536.31  5319.1  536.02  5324.8  535.14  5341.4  535.08  5363.4  532.86
  5385.9   535.2  5422.6  534.95  5436.1  535.77    5445  535.27  5458.3  536.17
  5602.1  539.74  5624.5  540.56  5636.4  541.77    5653   541.3    5742  544.14
#Mann= 3 , 0 , 0
  4139.7      .1       0  4974.2     .07       0  5013.1      .1       0
#XS Ineff= 2 , 0
                         5230.34          537.13
Permanent Ineff=
       F       F
Bank Sta=4974.2,5013.1
XS Rating Curve= 0 ,0
Exp/Cntr=0.3,0.1

Type RM Length L Ch R = 1 ,6619    ,544,544,544
BEGIN DESCRIPTION:
UNT 014 IN LACR 3.0
END DESCRIPTION:
XS GIS Cut Line= 5
2151266.4466742613200238.5657926      2151266.99     13200238.82
      2151740.11     13200460.18      2152499.65     13200143.34
      2152587.73     13199596.82
#Sta/Elev= 30
  4062.8  535.96  4423.1  532.62  4571.4  530.45  4921.1  531.67  4961.8  530.21
  4974.2  528.55  4983.4  527.49    4998  527.67  5005.1  528.88  5015.9  530.06
  5021.8  529.25  5045.7  530.54  5069.5  529.72    5128  531.28  5189.3  530.98
    5311  529.18    5364  527.86  5394.9  525.99  5445.7  528.42  5476.1  528.79
  5496.3  530.88  5552.9  532.46  5557.9  533.44  5597.6   533.5  5619.8  534.77
  5729.3  536.75  5810.3   539.4  5830.6  538.53  5840.7  539.69  5962.3   542.5
#Mann= 3 ,-1 , 0
  4062.8      .1       0  4974.2     .07       0    4998      .1       0
#XS Ineff= 2 , 0
                         5128.41          531.28
Permanent Ineff=
       F       F
Bank Sta=4974.2,5005.1
XS Rating Curve= 0 ,0
Exp/Cntr=0.3,0.1

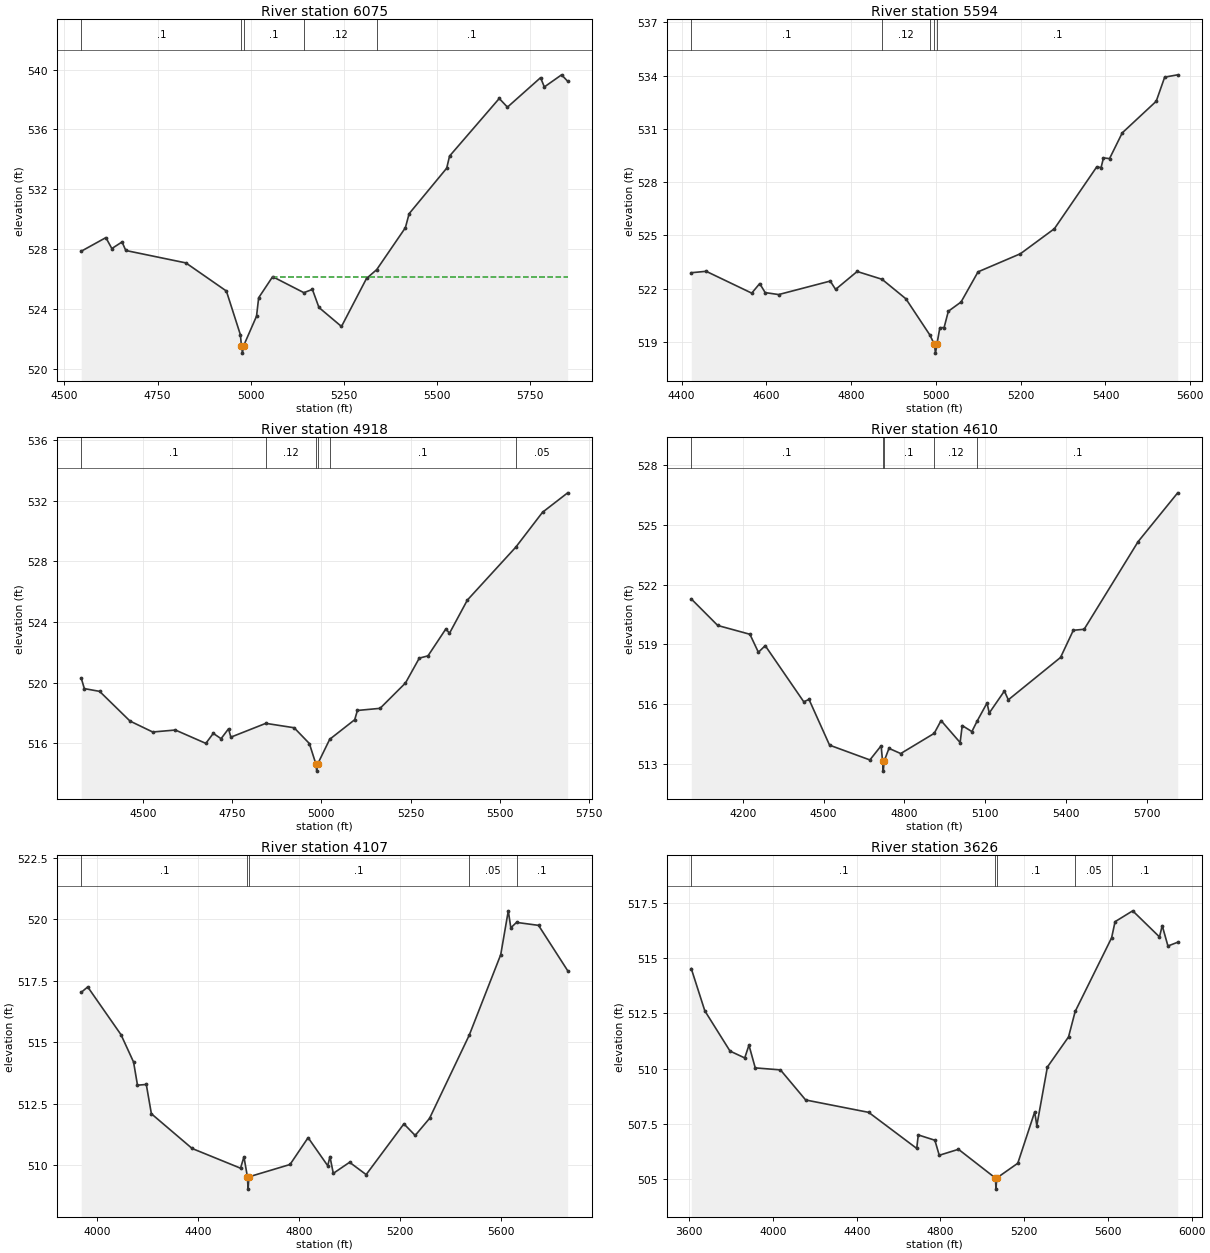
Type RM Length L Ch R = 1 ,6075    ,481,481,481
BEGIN DESCRIPTION:
UNT 014 IN LACR 2.0
END DESCRIPTION:
XS GIS Cut Line= 3
      2152182.78     13200803.09      2152699.31     13200512.27
       2152794.8     13199804.75
#Sta/Elev= 30
  4545.1  527.86  4611.3  528.77  4627.3  528.04  4654.7  528.48  4664.8  527.91
  4826.2  527.08    4935   525.2  4972.6  522.28  4975.4  521.55  4978.1  521.05
  4981.4  521.55    5016  523.52  5021.7  524.75  5059.3  526.16  5143.2  525.09
    5166  525.31  5183.7   524.1  5244.2  522.83  5311.4  526.04  5338.8  526.63
  5415.8  529.43  5425.9  530.37  5526.8  533.41  5534.5  534.22    5668  538.07
    5690  537.49    5779  539.46  5789.1  538.84  5835.4  539.65  5851.8  539.22
#Mann= 5 ,-1 , 0
  4545.1      .1       0  4975.4     .07       0  4981.4      .1       0
  5143.2     .12       0  5338.8      .1       0
#XS Ineff= 2 , 0
                         5058.18          526.16
Permanent Ineff=
       F       F
Bank Sta=4975.4,4981.4
XS Rating Curve= 0 ,0
Exp/Cntr=0.3,0.1

Type RM Length L Ch R = 1 ,5594    ,676,676,676
BEGIN DESCRIPTION:
Mapping XS b79fd7cf
END DESCRIPTION:
XS GIS Cut Line= 3
      2152898.97     13201150.25      2153042.19     13200716.26
      2153016.15     13200026.16
#Sta/Elev= 30
  4422.8   522.9    4458  522.98  4565.5  521.75  4584.3  522.29  4597.2  521.78
    4629  521.67  4750.7  522.43  4763.3  521.96  4814.2  522.97  4872.9  522.53
  4929.2  521.43  4985.5   519.4  4996.3  518.87    4999  518.37  5002.3  518.87
  5009.3   519.8  5019.3  519.81  5029.3  520.73  5059.3  521.25  5099.4  522.95
  5199.4  523.97  5279.5  525.38  5379.6  528.87  5389.6  528.82  5395.3  529.37
  5409.6  529.33  5439.6  530.78  5519.7  532.56  5539.7  533.92  5570.4  534.05
#Mann= 5 ,-1 , 0
  4422.8      .1       0  4872.9     .12       0  4985.5      .1       0
  4996.3     .07       0  5002.3      .1       0
Bank Sta=4996.3,5002.3
XS Rating Curve= 0 ,0
Exp/Cntr=0.3,0.1

Type RM Length L Ch R = 1 ,4918    ,308,308,308
BEGIN DESCRIPTION:
Mapping XS c0ff8e35
END DESCRIPTION:
XS GIS Cut Line= 3
      2153142.04     13201224.05      2153858.16     13200599.07
      2153897.23     13200186.71
#Sta/Elev= 30
  4326.2   520.3    4335  519.61  4377.7  519.43  4463.1  517.47  4526.7  516.75
  4590.3  516.88  4675.8     516  4696.6  516.66  4718.5  516.31  4739.4  516.96
    4746  516.41    4844  517.32  4923.5  517.03  4966.2  515.99  4984.1  514.67
  4986.9  514.17  4990.1  514.67  5023.3  516.27  5093.4  517.56    5101  518.17
  5164.6  518.31  5235.8  519.98  5274.6  521.62    5299  521.77  5349.2  523.55
  5359.3  523.26  5409.5  525.45  5545.4  528.94  5620.4  531.24  5690.9  532.52
#Mann= 6 ,-1 , 0
  4326.2      .1       0    4844     .12       0  4984.1     .07       0
  4990.1     .12       0  5023.3      .1       0  5545.4     .05       0
Bank Sta=4984.1,4990.1
XS Rating Curve= 0 ,0
Exp/Cntr=0.3,0.1

Type RM Length L Ch R = 1 ,4610    ,503,503,503
BEGIN DESCRIPTION:
Mapping XS c987e671
END DESCRIPTION:
XS GIS Cut Line= 4
      2152969.17     13201460.16      2153434.43     13201321.27
      2154135.82     13200786.55      2154163.51     13200350.45
#Sta/Elev= 30
    4009  521.28  4107.3  519.95  4226.6  519.51    4258  518.61  4283.4  518.94
  4426.4  516.13  4445.8  516.25  4522.1  513.96  4671.7  513.22  4713.4  513.93
  4718.6  513.16  4721.4  512.66  4724.6  513.16  4742.4   513.8    4786  513.54
  4910.2  514.55  4935.7  515.19  5006.4  514.09  5014.2  514.94    5050  514.64
  5070.1  515.18  5106.2  516.07  5114.5  515.57  5170.6  516.67  5185.2  516.23
  5378.9  518.35  5426.3  519.71  5466.4  519.76  5666.8  524.15  5813.5  526.59
#Mann= 5 ,-1 , 0
    4009      .1       0  4718.6     .07       0  4724.6      .1       0
  4910.2     .12       0  5070.1      .1       0
Bank Sta=4718.6,4724.6
XS Rating Curve= 0 ,0
Exp/Cntr=0.3,0.1

Type RM Length L Ch R = 1 ,4107    ,481,481,481
BEGIN DESCRIPTION:
Mapping XS 3f5ab19c
END DESCRIPTION:
XS GIS Cut Line= 4
      2153212.24     13201633.77      2153934.43     13201529.61
      2154524.71     13201126.83      2154517.77     13200641.25
#Sta/Elev= 30
  3936.3  517.03    3962  517.25  4094.1  515.31  4143.9   514.2  4159.5  513.26
  4194.4  513.29  4214.6   512.1  4376.3  510.69  4568.3  509.89  4581.8  510.35
  4595.6  509.54  4598.3  509.04  4601.6  509.54  4764.6  510.04  4836.4  511.13
  4914.2  509.99  4923.1  510.36  4936.3  509.68    5001  510.13  5066.7  509.63
  5216.4  511.69  5261.2  511.22    5318  511.91  5475.6  515.29  5600.6  518.56
  5630.6  520.34  5640.6  519.65  5663.2  519.87  5750.6  519.75  5866.2  517.91
#Mann= 5 ,-1 , 0
  3936.3      .1       0  4595.6     .07       0  4601.6      .1       0
  5475.6     .05       0  5663.2      .1       0
Bank Sta=4595.6,4601.6
XS Rating Curve= 0 ,0
Exp/Cntr=0.3,0.1

Type RM Length L Ch R = 1 ,3626    ,526,526,526
BEGIN DESCRIPTION:
Mapping XS 46eb8fb0
END DESCRIPTION:
XS GIS Cut Line= 4
      2153333.17     13201681.28      2154309.68     13201764.61
      2154728.96     13201454.71      2154611.93     13200640.71
#Sta/Elev= 30
  3609.6  514.53  3674.4  512.62  3794.8   510.8  3865.1  510.49  3885.2  511.07
  3915.3  510.04  4035.7  509.95  4156.1  508.59  4457.2  508.03  4686.7   506.4
  4694.1  507.01  4773.4  506.77  4794.3  506.09  4886.1  506.36  5062.7  505.06
  5065.4  504.56  5068.7  505.06  5169.5  505.73  5250.3  508.05  5260.4  507.43
  5310.9  510.08  5411.9  511.44  5443.6  512.59  5617.7  515.92  5634.2  516.65
  5718.5  517.14  5846.4  515.96  5859.5  516.47  5886.8  515.55  5933.4  515.72
#Mann= 5 ,-1 , 0
  3609.6      .1       0  5062.7     .07       0  5068.7      .1       0
  5443.6     .05       0  5617.7      .1       0
Bank Sta=5062.7,5068.7
XS Rating Curve= 0 ,0
Exp/Cntr=0.3,0.1

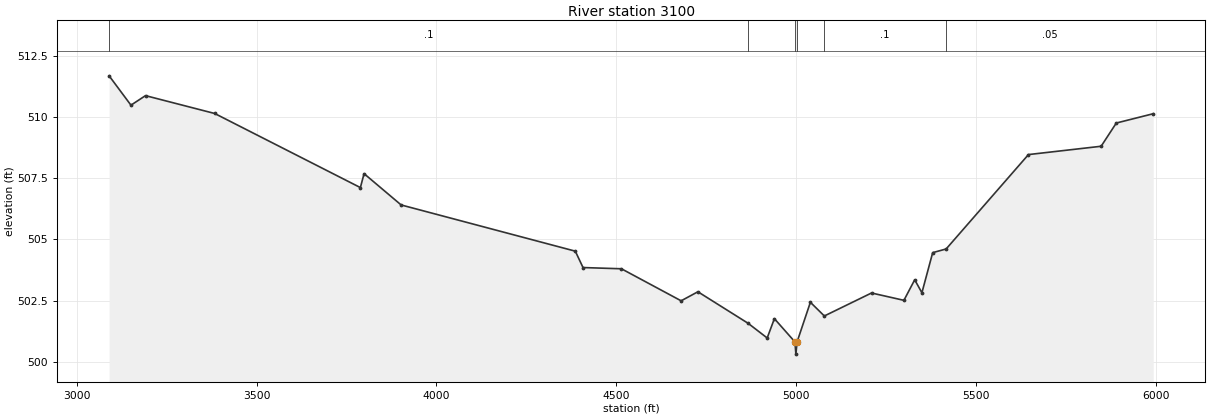
Type RM Length L Ch R = 1 ,3100    ,0,0,0
BEGIN DESCRIPTION:
UNT 014 IN LACR 1.0
END DESCRIPTION:
XS GIS Cut Line= 5
       2153387.8     13201743.77      2154702.91     13201954.71
      2155116.98     13201772.42      2155135.21     13201110.96
      2154885.19     13200728.12
#Sta/Elev= 30
    3090  511.69  3150.7  510.49  3191.2  510.88  3383.6  510.15  3788.7  507.12
  3798.9  507.69    3902  506.41  4386.3  504.52  4407.8  503.85  4514.6   503.8
  4680.6  502.49  4727.2  502.86  4866.9  501.57  4919.9  500.97  4939.9  501.76
    4997  500.81  4999.7  500.31    5003  500.81    5040  502.43  5078.8  501.87
    5210  502.81  5300.1  502.51  5330.1  503.35  5350.1  502.82  5380.1  504.46
  5417.5  504.61  5646.4  508.47  5848.5  508.81  5890.7  509.76  5993.3  510.14
#Mann= 6 ,-1 , 0
    3090      .1       0  4866.9     .12       0    4997     .07       0
    5003     .12       0  5078.8      .1       0  5417.5     .05       0
Bank Sta=4997,5003
XS Rating Curve= 0 ,0
Exp/Cntr=0.3,0.1

Chan Stop Cuts=-1
Use User Specified Reach Order=0
Composite Channel Slope=5

--- UNT 014 IN LACR.g02 (geometry) ---

Geom Title=Dummy
Program Version=4.10

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
River Reach=UNT 014 IN LACR ,Reach-1
Reach XY= 30
      2151187.72     13198446.85      2151737.72     13198946.85
      2151837.72     13199196.86      2151837.72     13199446.85
      2151887.72     13199496.85      2151887.72     13199846.86
      2151987.72     13199996.85      2151987.72     13200096.85
      2152037.72     13200196.86      2152437.72     13200546.85
      2152587.72     13200546.85      2152687.72     13200646.85
      2152787.72     13200596.85      2153387.72     13200596.85
      2153587.72     13200696.86      2154187.72     13201346.86
      2154737.72     13201546.85      2154987.72     13201696.85
      2155487.72     13201546.85      2155887.72     13201496.86
      2155987.72     13201346.86      2156087.72     13201346.86
      2156137.72     13201246.85      2156437.72     13201246.85
      2156537.72     13201146.85      2156887.72     13201146.85
      2157037.72     13201296.85      2157187.72     13201346.86
      2157687.72     13201396.85      2157737.72     13201646.86

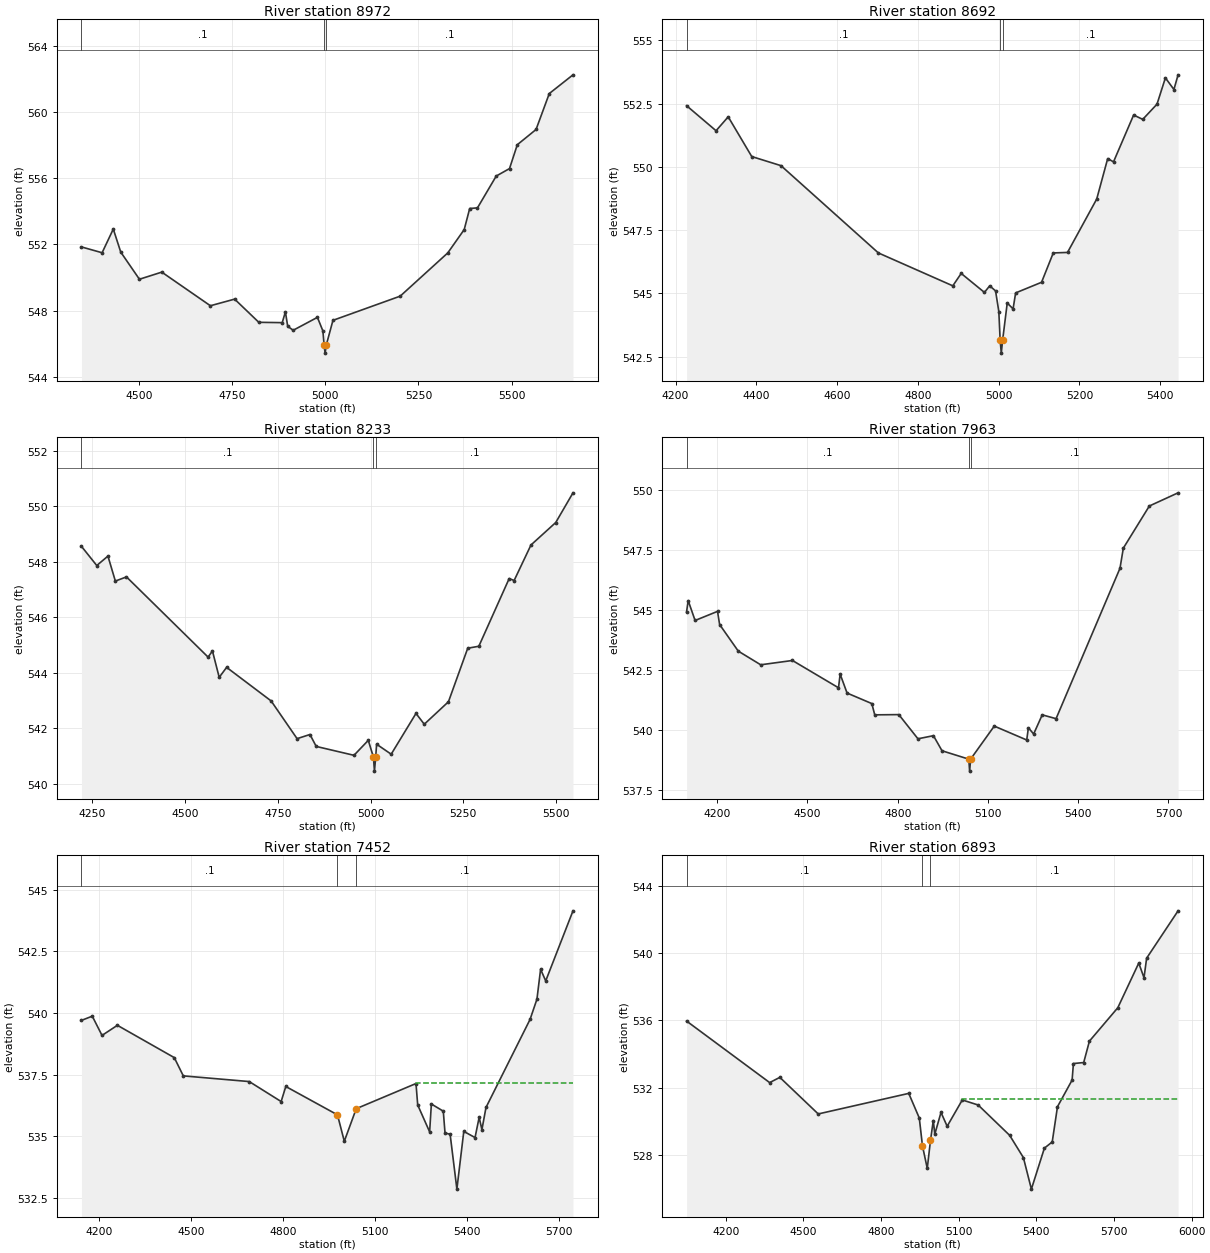
Type RM Length L Ch R = 1 ,8972    ,280,280,280
BEGIN DESCRIPTION:
UNT 014 IN LACR 8.0
END DESCRIPTION:
XS GIS Cut Line= 3
       2150802.5       13198856.      2151135.82     13198842.11
      2151712.21      13198043.5
#Sta/Elev= 30
  4346.1  551.85  4401.4   551.5  4431.4  552.93  4451.4  551.54  4501.5   549.9
  4561.5  550.33  4691.9   548.3  4756.9   548.7  4821.8   547.3  4884.6  547.28
  4893.1  547.93  4899.3  547.06    4914  546.82    4979   547.6  4993.7  546.78
  4996.9  545.94  4999.6  545.44  5002.9  545.94  5020.7  547.42  5201.1  548.88
  5328.7  551.49  5372.8   552.9  5387.5  554.17  5408.4  554.21  5458.7  556.13
  5494.3  556.58  5515.2  558.02  5565.5  558.94    5601  561.11  5664.6  562.24
#Mann= 3 ,-1 , 0
  4346.1      .1       0  4996.9     .07       0  5002.9      .1       0
Bank Sta=4996.9,5002.9
XS Rating Curve= 0 ,0
Exp/Cntr=0.3,0.1

Type RM Length L Ch R = 1 ,8692    ,459,459,459
BEGIN DESCRIPTION:
UNT 014 IN LACR 7.0
END DESCRIPTION:
XS GIS Cut Line= 3
      2150805.12     13198918.43      2151388.46     13198859.31
      2151885.88     13198471.28
#Sta/Elev= 30
  4227.2  552.42  4300.2  551.43  4330.3  551.98  4388.6  550.41    4461  550.05
  4702.2   546.6  4886.5   545.3  4907.3  545.79  4964.8  545.04  4977.9   545.3
  4992.4   545.1  5000.5  544.28  5003.8  543.14  5006.6  542.64  5009.8  543.14
  5021.3  544.62  5035.8  544.39  5042.1  545.02  5106.3  545.44  5135.3   546.6
  5170.6  546.62  5242.9  548.73  5270.1  550.33  5284.5   550.2  5334.3  552.05
  5356.9  551.88  5392.2  552.48    5413  553.52  5434.1  553.06  5444.4  553.64
#Mann= 3 ,-1 , 0
  4227.2      .1       0  5003.8     .07       0  5009.8      .1       0
Bank Sta=5003.8,5009.8
XS Rating Curve= 0 ,0
Exp/Cntr=0.3,0.1

Type RM Length L Ch R = 1 ,8233    ,270,270,270
BEGIN DESCRIPTION:
UNT 014 IN LACR 6.0
END DESCRIPTION:
XS GIS Cut Line= 4
      2151026.48     13199165.82      2151630.65     13199176.24
      2151948.36     13199019.99      2152122.76     13198697.21
#Sta/Elev= 30
  4220.7  548.56  4261.9  547.87    4292  548.21    4312  547.31    4342  547.46
    4562  544.57  4573.8  544.79    4592  543.84    4612   544.2    4732  542.99
    4802  541.63  4836.7  541.78  4853.6  541.35  4955.4  541.03    4994  541.57
  5007.9  540.96  5010.6  540.46  5013.9  540.96  5016.4  541.43  5055.7  541.07
  5122.6  542.54  5144.9  542.15  5210.1  542.96  5262.1  544.89    5292  544.96
  5373.8   547.4  5387.2  547.33  5432.6  548.61  5499.4  549.42  5545.9  550.49
#Mann= 3 ,-1 , 0
  4220.7      .1       0  5007.9     .07       0  5013.9      .1       0
Bank Sta=5007.9,5013.9
XS Rating Curve= 0 ,0
Exp/Cntr=0.3,0.1

Type RM Length L Ch R = 1 ,7963    ,511,511,511
BEGIN DESCRIPTION:
UNT 014 IN LACR 5.0
END DESCRIPTION:
XS GIS Cut Line= 2
       2151017.8     13199724.03      2152503.25     13199043.78
#Sta/Elev= 30
  4098.2  544.92  4103.5  545.39  4126.5  544.56    4201  544.94  4208.1  544.39
  4270.1  543.28  4344.6  542.71  4450.1  542.89  4603.2  541.75  4608.7  542.32
  4631.7  541.53    4714  541.09  4723.7  540.62  4803.7  540.63  4867.3  539.62
  4918.8  539.75  4947.3  539.12  5036.3  538.77  5039.1  538.27  5042.3  538.77
    5121  540.15  5228.9  539.57  5234.4  540.08  5251.9  539.82  5280.4  540.62
  5326.4  540.46  5538.9  546.74    5550  547.58  5636.5  549.34    5732  549.89
#Mann= 3 ,-1 , 0
  4098.2      .1       0  5036.3     .07       0  5042.3      .1       0
Bank Sta=5036.3,5042.3
XS Rating Curve= 0 ,0
Exp/Cntr=0.3,0.1

Type RM Length L Ch R = 1 ,7452    ,559,559,559
BEGIN DESCRIPTION:
UNT 014 IN LACR 4.0
END DESCRIPTION:
XS GIS Cut Line= 3
      2151073.34     13200085.16      2151649.71     13199960.16
      2152552.46     13199501.84
#Sta/Elev= 30
  4143.3   539.7  4178.5  539.87  4210.2  539.09  4260.3   539.5  4445.8  538.19
  4475.2  537.45  4690.1  537.22  4794.1  536.41  4809.3  537.02  4977.8  535.87
    5000   534.8  5038.9  536.12  5233.7  537.14  5239.3  536.27  5278.2  535.18
  5283.8  536.31  5322.7  536.02  5328.3  535.14    5345  535.08    5367  532.86
  5389.5   535.2  5426.2  534.95  5439.6  535.77  5448.6  535.27  5461.9  536.17
  5605.6  539.74    5628  540.56  5639.9  541.77  5656.6   541.3  5745.5  544.14
#Mann= 3 , 0 , 0
  4143.3      .1       0  4977.8     .07       0  5038.9      .1       0
#XS Ineff= 2 , 0
                         5232.39          537.15
Permanent Ineff=
       F       F
Bank Sta=4977.8,5038.9
XS Rating Curve= 0 ,0
Exp/Cntr=0.3,0.1

Type RM Length L Ch R = 1 ,6893    ,582,582,582
BEGIN DESCRIPTION:
UNT 014 IN LACR 3.0
END DESCRIPTION:
XS GIS Cut Line= 4
      2151267.02     13200238.83      2151740.11     13200460.18
      2152499.65     13200143.34      2152587.71     13199596.89
#Sta/Elev= 30
  4048.8  535.96  4369.8  532.31  4409.1  532.62  4557.4  530.45  4907.1  531.67
  4947.8  530.21  4960.2  528.55  4978.6  527.22  4991.1  528.88  5001.9  530.06
  5007.8  529.25  5031.7  530.54  5055.5  529.72    5114  531.28  5175.3  530.98
    5297  529.18    5350  527.86  5380.9  525.99  5431.1  528.42  5461.4  528.79
  5481.7  530.88  5538.2  532.46  5543.3  533.44    5583   533.5  5605.1  534.77
  5714.7  536.75  5795.7   539.4    5816  538.53  5826.1  539.69  5947.6   542.5
#Mann= 3 , 0 , 0
  4048.8      .1       0  4960.2     .07       0  4991.1      .1       0
#XS Ineff= 2 , 0
                         5113.64          531.31
Permanent Ineff=
       F       F
Bank Sta=4960.2,4991.1
XS Rating Curve= 0 ,0
Exp/Cntr=0.3,0.1

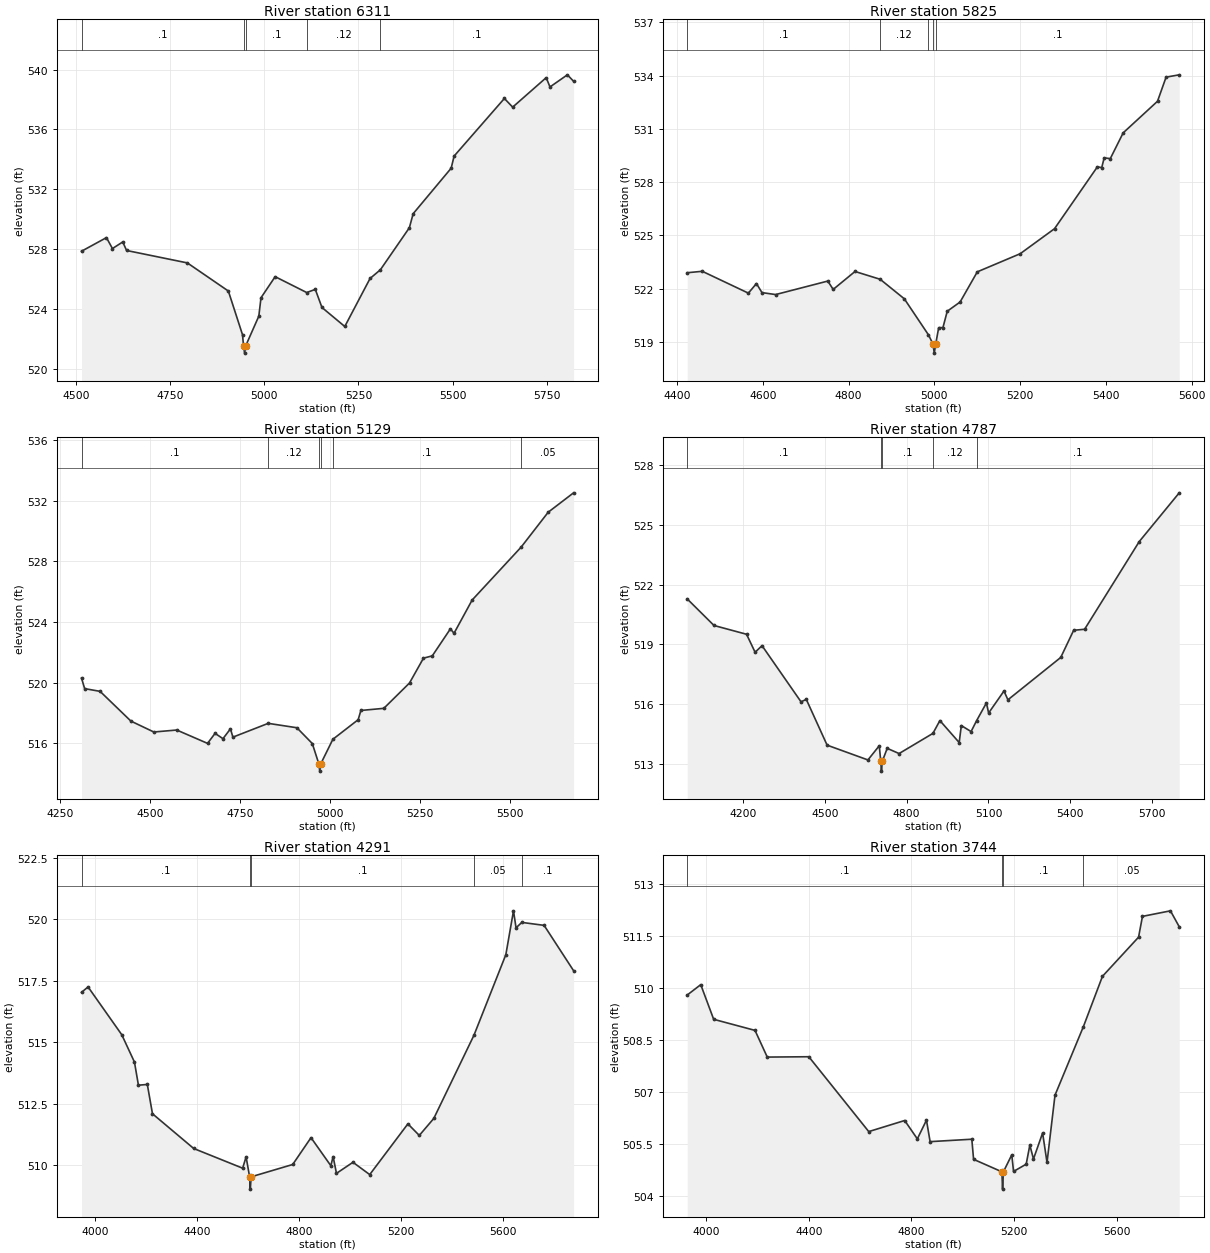
Type RM Length L Ch R = 1 ,6311    ,486,486,486
BEGIN DESCRIPTION:
UNT 014 IN LACR 2.0
END DESCRIPTION:
XS GIS Cut Line= 3
      2152182.82     13200803.06      2152699.31     13200512.27
      2152794.79     13199804.81
#Sta/Elev= 30
  4514.6  527.86  4580.8  528.77  4596.7  528.04  4624.1  528.48  4634.3  527.91
  4795.6  527.08  4904.5   525.2  4942.1  522.28  4944.8  521.55  4947.6  521.05
  4950.8  521.55  4985.4  523.52  4991.2  524.75  5028.8  526.16  5112.6   525.1
  5135.4  525.31  5153.1   524.1  5213.7  522.83  5280.8  526.04  5308.2  526.62
  5385.2  529.43  5395.3  530.37  5496.2  533.41    5504  534.22  5637.5  538.07
  5659.5  537.49  5748.5  539.46  5758.6  538.84  5804.8  539.65  5821.2  539.22
#Mann= 5 ,-1 , 0
  4514.6      .1       0  4944.8     .07       0  4950.8      .1       0
  5112.6     .12       0  5308.2      .1       0
Bank Sta=4944.8,4950.8
XS Rating Curve= 0 ,0
Exp/Cntr=0.3,0.1

Type RM Length L Ch R = 1 ,5825    ,696,696,696
BEGIN DESCRIPTION:
Mapping XS b79fd7cf
END DESCRIPTION:
XS GIS Cut Line= 3
      2152898.97     13201150.25      2153042.19     13200716.26
      2153016.15     13200026.16
#Sta/Elev= 30
  4423.5   522.9  4458.7  522.98  4566.2  521.75    4585  522.29  4597.9  521.78
  4629.7  521.67  4751.4  522.43    4764  521.96  4814.9  522.97  4873.6  522.53
  4929.9  521.43  4986.2   519.4    4997  518.87  4999.7  518.37    5003  518.87
    5010   519.8    5020  519.81    5030  520.73    5060  521.25  5100.1  522.95
  5200.1  523.97  5280.2  525.38  5380.3  528.87  5390.3  528.82    5396  529.37
  5410.3  529.33  5440.3  530.78  5520.4  532.56  5540.4  533.92  5571.1  534.05
#Mann= 5 ,-1 , 0
  4423.5      .1       0  4873.6     .12       0  4986.2      .1       0
    4997     .07       0    5003      .1       0
Bank Sta=4997,5003
XS Rating Curve= 0 ,0
Exp/Cntr=0.3,0.1

Type RM Length L Ch R = 1 ,5129    ,342,342,342
BEGIN DESCRIPTION:
Mapping XS c0ff8e35
END DESCRIPTION:
XS GIS Cut Line= 3
      2153142.05     13201224.04      2153858.16     13200599.07
      2153897.22     13200186.79
#Sta/Elev= 30
  4310.5   520.3  4319.2  519.61    4362  519.43  4447.4  517.47    4511  516.75
  4574.6  516.88    4660     516  4680.9  516.66  4702.8  516.31  4723.6  516.96
  4730.3  516.41  4828.3  517.32  4907.8  517.03  4950.5  515.99  4968.4  514.67
  4971.2  514.17  4974.4  514.67  5007.6  516.27  5077.7  517.56  5085.3  518.17
  5148.9  518.31  5220.1  519.98  5258.9  521.62  5283.3  521.77  5333.5  523.55
  5343.6  523.26  5393.8  525.45  5529.7  528.94  5604.7  531.24  5675.1  532.52
#Mann= 6 ,-1 , 0
  4310.5      .1       0  4828.3     .12       0  4968.4     .07       0
  4974.4     .12       0  5007.6      .1       0  5529.7     .05       0
Bank Sta=4968.4,4974.4
XS Rating Curve= 0 ,0
Exp/Cntr=0.3,0.1

Type RM Length L Ch R = 1 ,4787    ,496,496,496
BEGIN DESCRIPTION:
Mapping XS c987e671
END DESCRIPTION:
XS GIS Cut Line= 4
      2152969.14     13201460.17      2153434.43     13201321.27
      2154135.82     13200786.55      2154163.51     13200350.48
#Sta/Elev= 30
  3995.2  521.28  4093.5  519.95  4212.9  519.51  4244.2  518.61  4269.6  518.94
  4412.6  516.13    4432  516.25  4508.3  513.96    4658  513.22  4699.6  513.93
  4704.9  513.16  4707.6  512.66  4710.9  513.16  4728.7   513.8  4772.3  513.54
  4896.4  514.55  4921.9  515.19  4992.7  514.09  5000.5  514.94  5036.3  514.64
  5056.3  515.18  5092.4  516.07  5100.7  515.57  5156.9  516.67  5171.4  516.23
  5365.1  518.35  5412.5  519.71  5452.6  519.76    5653  524.15  5799.7  526.59
#Mann= 5 ,-1 , 0
  3995.2      .1       0  4704.9     .07       0  4710.9      .1       0
  4896.4     .12       0  5056.3      .1       0
Bank Sta=4704.9,4710.9
XS Rating Curve= 0 ,0
Exp/Cntr=0.3,0.1

Type RM Length L Ch R = 1 ,4291    ,547,547,547
BEGIN DESCRIPTION:
Mapping XS 3f5ab19c
END DESCRIPTION:
XS GIS Cut Line= 4
      2153212.24     13201633.77      2153934.43     13201529.61
      2154524.71     13201126.83      2154517.77     13200641.24
#Sta/Elev= 30
  3946.1  517.03  3971.8  517.25  4103.9  515.31  4153.7   514.2  4169.3  513.26
  4204.2  513.29  4224.4   512.1  4386.1  510.69  4578.1  509.89  4591.6  510.35
  4605.4  509.54  4608.1  509.04  4611.4  509.54  4774.4  510.04  4846.2  511.13
    4924  509.99  4932.9  510.36  4946.1  509.68  5010.8  510.13  5076.5  509.63
  5226.2  511.69  5270.9  511.22  5327.8  511.91  5485.4  515.29  5610.4  518.56
  5640.4  520.34  5650.4  519.65    5673  519.87  5760.4  519.75    5876  517.91
#Mann= 5 ,-1 , 0
  3946.1      .1       0  4605.4     .07       0  4611.4      .1       0
  5485.4     .05       0    5673      .1       0
Bank Sta=4605.4,4611.4
XS Rating Curve= 0 ,0
Exp/Cntr=0.3,0.1

Type RM Length L Ch R = 1 ,3744    ,0,0,0
BEGIN DESCRIPTION:
UNT 014 IN LACR 1.0
END DESCRIPTION:
XS GIS Cut Line= 4
      2153705.28     13201703.22      2154434.43      13201793.5
      2154892.76     13201307.39      2154795.67     13200801.14
#Sta/Elev= 30
  3926.3  509.81  3979.1  510.11  4029.5  509.11  4190.7  508.79  4238.4  508.02
  4400.4  508.03  4634.1  505.87  4774.2  506.19  4823.5  505.66  4859.1   506.2
  4873.3  505.58  5035.9  505.65  5042.8  505.07  5153.1  504.71  5155.8  504.21
  5159.1  504.71  5191.7   505.2  5198.6  504.72  5247.9  504.93  5262.1  505.48
  5276.3  505.08  5311.9  505.83  5329.1  504.98  5360.2  506.92    5471   508.9
  5545.2  510.35    5686  511.48  5701.2  512.08  5810.3  512.24  5844.6  511.78
#Mann= 4 ,-1 , 0
  3926.3      .1       0  5153.1     .07       0  5159.1      .1       0
    5471     .05       0
Bank Sta=5153.1,5159.1
XS Rating Curve= 0 ,0
Exp/Cntr=0.3,0.1