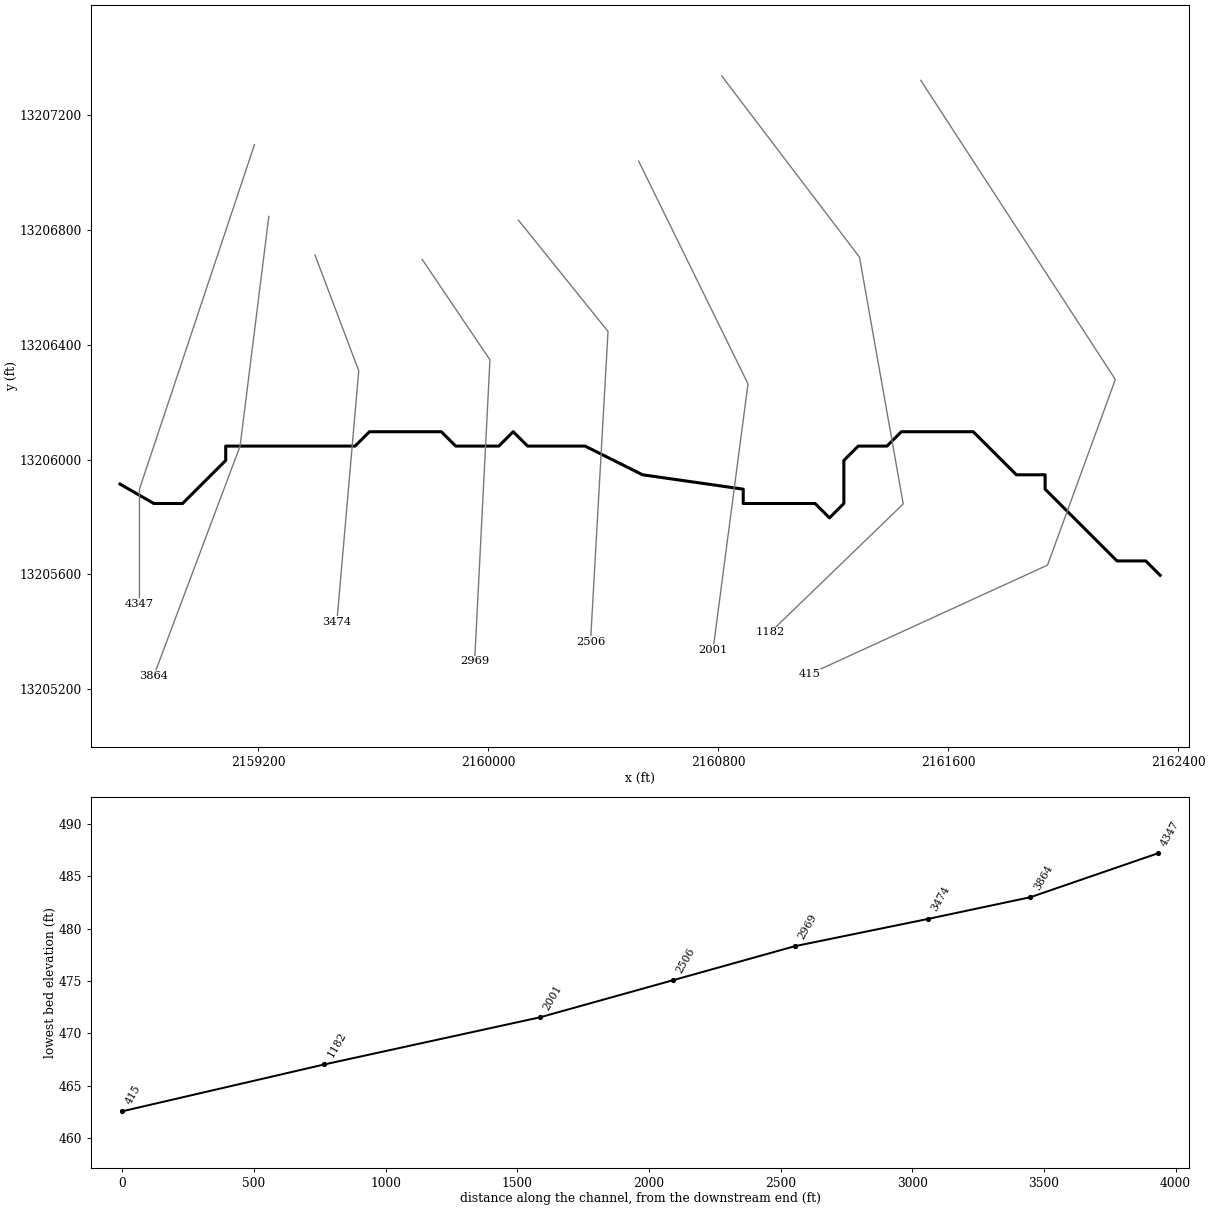
--- UNT 015 IN LACR.prj (project) ---

Proj Title=UNT 015 IN LACR Base Level Engineering
Current Plan=p01
Default Exp/Contr=0.3,0.1
English Units
Geom File=g01
Flow File=f01
Plan File=p01
Y Axis Title=Elevation
X Axis Title(PF)=Main Channel Distance
X Axis Title(XS)=Station
BEGIN DESCRIPTION:
UNT 015 IN LACR
END DESCRIPTION:
DSS Export Rating Curves= 0
DSS Export Rating Curve Sorted= 0
DSS Export Volume Flow Curves= 0
DXF OffsetX= 0
DXF OffsetY= 0
DXF ScaleX= 1
DXF ScaleY= 10

--- UNT 015 IN LACR.p01 (plan) ---

Plan Title=Multiple Run
Short Identifier=Multiple
Geom File=g01
Flow File=f01
Subcritical Flow
K Sum by GR= 0
Std Step Tol= 0.01
Critical Tol= 0.01
Num of Std Step Trials= 20
Max Error Tol= 0.3
Flow Tol Ratio= 0.001
Split Flow NTrial= 30
Split Flow Tol= 0.02
Split Flow Ratio= 0.02
Log Output Level= 0
Friction Slope Method= 1
Unsteady Friction Slope Method= 2
Unsteady Bridges Friction Slope Method= 1
Parabolic Critical Depth
Global Vel Dist=  1 , 1 , 1
Global Log Level= 0
CheckData=True
Encroach Param= -1, 0, 0, 0
BEGIN DESCRIPTION:
Multiple Run
END DESCRIPTION:

--- UNT 015 IN LACR.f01 (steady flow) ---

Flow Title=Multiple
Number of Profiles=7
Profile Names=10-year,25-year,50-year,1pct_min,100-year,1pct_plu,500-year
River Rch & RM= UNT 015 IN LACR,Reach-1,4347
     196     272     336     305     412     558     632
Boundary for River Rch & Prof#=UNT 015 IN LACR,Reach-1,1
Up Type=0
Dn Type=3
Dn Slope=0.005
Boundary for River Rch & Prof#=UNT 015 IN LACR,Reach-1,2
Up Type=0
Dn Type=3
Dn Slope=0.005
Boundary for River Rch & Prof#=UNT 015 IN LACR,Reach-1,3
Up Type=0
Dn Type=3
Dn Slope=0.005
Boundary for River Rch & Prof#=UNT 015 IN LACR,Reach-1,4
Up Type=0
Dn Type=3
Dn Slope=0.005
Boundary for River Rch & Prof#=UNT 015 IN LACR,Reach-1,5
Up Type=0
Dn Type=3
Dn Slope=0.005
Boundary for River Rch & Prof#=UNT 015 IN LACR,Reach-1,6
Up Type=0
Dn Type=3
Dn Slope=0.005
Boundary for River Rch & Prof#=UNT 015 IN LACR,Reach-1,7
Up Type=0
Dn Type=3
Dn Slope=0.005

--- UNT 015 IN LACR.g01 (geometry) ---

Geom Title=Existing Conditions
Program Version=4.10

River Reach=UNT 015 IN LACR ,Reach-1
Reach XY= 30
      2158720.05     13205914.53      2158837.72     13205846.85
      2158937.72     13205846.85      2159087.72     13205996.85
      2159087.72     13206046.85      2159537.72     13206046.85
      2159587.72     13206096.86      2159837.72     13206096.86
      2159887.72     13206046.85      2160037.72     13206046.85
      2160087.72     13206096.86      2160137.72     13206046.85
      2160337.72     13206046.85      2160537.72     13205946.86
      2160887.72     13205896.85      2160887.72     13205846.85
      2161137.72     13205846.85      2161187.72     13205796.85
      2161237.72     13205846.85      2161237.72     13205996.85
      2161287.72     13206046.85      2161387.72     13206046.85
      2161437.72     13206096.86      2161687.72     13206096.86
      2161837.72     13205946.86      2161937.72     13205946.86
      2161937.72     13205896.85      2162187.72     13205646.85
      2162287.72     13205646.85      2162337.72     13205596.86

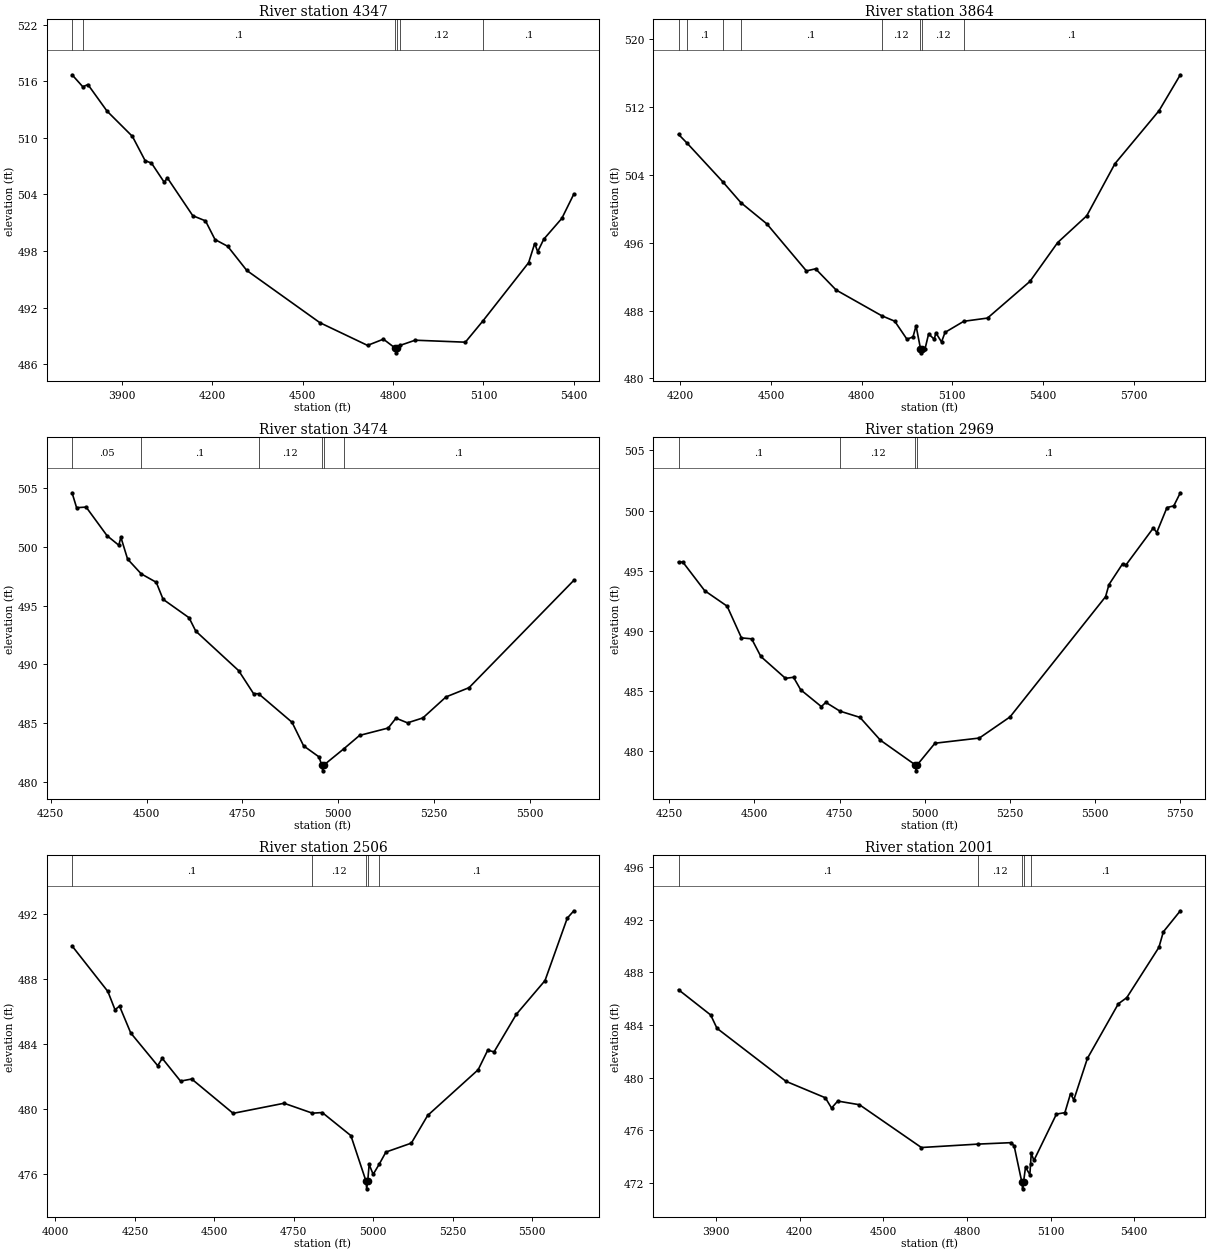
Type RM Length L Ch R = 1 ,4347    ,483,483,483
BEGIN DESCRIPTION:
UNT 015 IN LACR 7.0
END DESCRIPTION:
XS GIS Cut Line= 3
      2159187.72     13207096.84      2158787.72     13205896.85
      2158787.72     13205496.85
#Sta/Elev= 30
  3735.1  516.69  3770.7  515.42  3787.8  515.65    3851  512.84  3935.4  510.15
  3977.5  507.58  3998.6  507.32  4040.8  505.29  4051.3  505.75  4135.6  501.74
  4177.8  501.19  4209.4  499.21  4251.6  498.49  4314.8  495.93  4557.3  490.39
  4715.4  487.98  4768.1  488.64  4807.3  487.69    4810  487.19  4813.3  487.69
  4822.5  487.97  4873.5  488.53    5040  488.32  5098.6  490.59    5250  496.76
    5270  498.79    5280  497.92    5300  499.24    5360  501.45    5400  504.04
#Mann= 6 ,-1 , 0
  3735.1     .05       0  3770.7      .1       0  4807.3     .07       0
  4813.3      .1       0  4822.5     .12       0  5098.6      .1       0
Bank Sta=4807.3,4813.3
XS Rating Curve= 0 ,0
Exp/Cntr=0.3,0.1

Type RM Length L Ch R = 1 ,3864    ,390,390,390
BEGIN DESCRIPTION:
UNT 015 IN LACR 6.0
END DESCRIPTION:
XS GIS Cut Line= 3
      2159237.72     13206846.83      2159137.72     13206046.85
      2158837.72     13205246.86
#Sta/Elev= 30
  4193.8  508.77  4222.6  507.72  4339.5  503.21  4400.2  500.72    4486  498.22
    4617  492.67  4647.3  492.92  4715.3  490.42    4866  487.39  4909.3  486.74
  4949.6  484.62  4969.8  484.89  4979.8   486.2  4994.5  483.51  4997.2  483.01
  5000.5  483.51  5009.8  483.52  5021.4  485.24  5040.1  484.61  5045.4  485.37
  5064.1  484.29  5075.7  485.42  5137.8  486.73  5216.3  487.11  5356.9  491.44
  5448.6  496.02  5544.7  499.17  5638.1  505.32  5784.1  511.57  5854.4   515.8
#Mann= 8 ,-1 , 0
  4193.8     .05       0  4222.6      .1       0  4339.5     .05       0
  4400.2      .1       0    4866     .12       0  4994.5     .07       0
  5000.5     .12       0  5137.8      .1       0
Bank Sta=4994.5,5000.5
XS Rating Curve= 0 ,0
Exp/Cntr=0.3,0.1

Type RM Length L Ch R = 1 ,3474    ,505,505,505
BEGIN DESCRIPTION:
UNT 015 IN LACR 5.0
END DESCRIPTION:
XS GIS Cut Line= 3
      2159398.31     13206712.32      2159550.41     13206309.25
      2159474.35     13205434.57
#Sta/Elev= 30
  4305.8  504.63  4317.6  503.36  4342.5  503.41  4397.1  500.97  4427.7  500.16
  4433.1  500.84  4450.6  498.98  4486.1  497.72  4525.4     497  4543.2  495.55
  4610.9  493.98  4628.4  492.84  4740.3  489.47  4779.2  487.51  4792.3   487.5
  4879.5  485.07  4909.7  483.06  4949.8  482.12  4956.8  481.43  4959.6  480.93
  4962.8  481.43  5015.4  482.83  5055.7  483.95  5130.5  484.58  5150.6  485.42
  5180.7  485.02  5220.8  485.44  5281.1  487.23  5341.3  488.02  5614.6  497.17
#Mann= 6 ,-1 , 0
  4305.8     .05       0  4486.1      .1       0  4792.3     .12       0
  4956.8     .07       0  4962.8     .12       0  5015.4      .1       0
Bank Sta=4956.8,4962.8
XS Rating Curve= 0 ,0
Exp/Cntr=0.3,0.1

Type RM Length L Ch R = 1 ,2969    ,463,463,463
BEGIN DESCRIPTION:
UNT 015 IN LACR 4.0
END DESCRIPTION:
XS GIS Cut Line= 3
      2159770.98     13206697.14      2160006.76     13206347.28
      2159953.52     13205297.72
#Sta/Elev= 30
  4277.3  495.71  4289.7  495.72    4354  493.33  4419.9  492.04    4462   489.4
  4491.9  489.32  4518.9  487.85  4591.2  486.03  4614.8  486.12  4635.8  485.08
  4696.4  483.68  4709.6  484.03  4751.1   483.3  4809.8  482.78  4869.8  480.88
    4972  478.83  4974.7  478.33    4978  478.83    5030  480.63  5160.2  481.06
  5250.3  482.82  5530.7  492.83  5540.7  493.84  5580.7  495.57  5590.8  495.48
  5670.9  498.55  5680.9  498.17  5710.9  500.25  5730.9  500.39  5750.1  501.48
#Mann= 4 ,-1 , 0
  4277.3      .1       0  4751.1     .12       0    4972     .07       0
    4978      .1       0
Bank Sta=4972,4978
XS Rating Curve= 0 ,0
Exp/Cntr=0.3,0.1

Type RM Length L Ch R = 1 ,2506    ,505,505,505
BEGIN DESCRIPTION:
UNT 015 IN LACR 3.0
END DESCRIPTION:
XS GIS Cut Line= 3
      2160105.64     13206834.04      2160417.46     13206446.16
      2160356.62     13205366.16
#Sta/Elev= 30
  4052.3  490.01    4165  487.21  4187.4  486.09  4201.7  486.31    4237  484.66
  4321.8  482.65  4336.2   483.1  4393.7   481.7  4428.9  481.83  4559.3  479.72
  4719.6  480.34  4808.8  479.73  4839.7  479.77  4929.9  478.35    4977  475.58
  4979.7  475.08    4983  475.58  4987.4  476.58    5000  475.97  5018.6  476.58
  5040.1  477.34  5120.2  477.89  5171.5  479.59  5330.5   482.4  5360.6   483.6
  5380.6   483.5  5450.7  485.81  5540.9  487.88    5611  491.72  5631.7  492.17
#Mann= 5 ,-1 , 0
  4052.3      .1       0  4808.8     .12       0    4977     .07       0
    4983     .12       0  5018.6      .1       0
Bank Sta=4977,4983
XS Rating Curve= 0 ,0
Exp/Cntr=0.3,0.1

Type RM Length L Ch R = 1 ,2001    ,819,819,819
BEGIN DESCRIPTION:
UNT 015 IN LACR 2.0
END DESCRIPTION:
XS GIS Cut Line= 3
      2160523.94     13207039.42      2160904.23     13206263.62
      2160782.64     13205336.45
#Sta/Elev= 30
  3766.1  486.67  3881.4  484.75  3903.9  483.74  4151.4  479.71  4292.4  478.46
  4314.7  477.68  4336.9  478.21  4414.9  477.93  4636.8  474.68    4840  474.94
  4959.7  475.05  4969.7  474.77    4997  472.04  4999.7  471.54    5003  472.04
  5010.1  473.18  5025.7  472.62  5028.3  473.45  5030.8  474.24  5040.3   473.7
    5121  477.22  5151.3  477.33  5171.5  478.77  5183.3   478.3    5232  481.45
  5342.9   485.6  5373.2  486.07  5488.4  489.89  5504.3  491.07  5565.2  492.67
#Mann= 5 ,-1 , 0
  3766.1      .1       0    4840     .12       0    4997     .07       0
    5003     .12       0  5028.3      .1       0
Bank Sta=4997,5003
XS Rating Curve= 0 ,0
Exp/Cntr=0.3,0.1

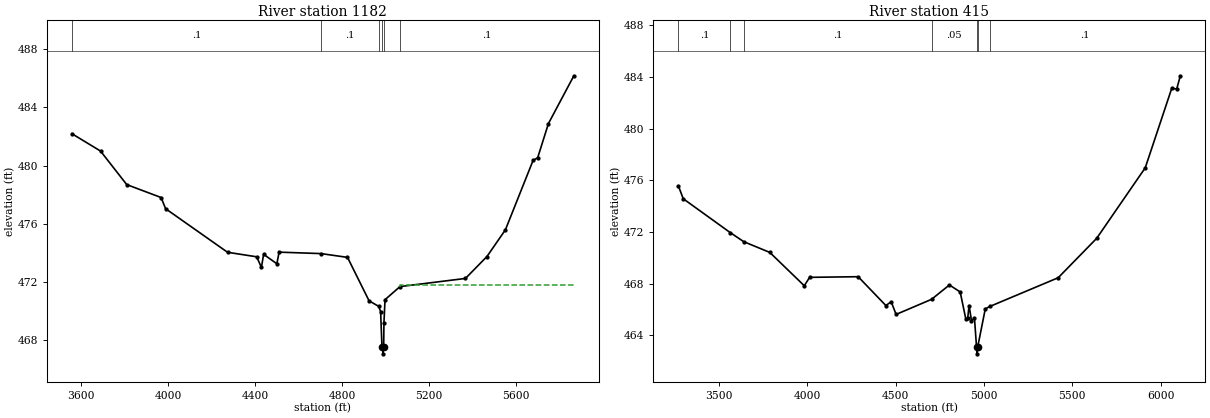
Type RM Length L Ch R = 1 ,1182    ,767,767,767
BEGIN DESCRIPTION:
Mapping XS 3c18798f
END DESCRIPTION:
XS GIS Cut Line= 4
      2160812.94     13207336.05      2161292.12     13206704.75
      2161444.24      13205845.3      2160981.53     13205397.77
#Sta/Elev= 30
  3557.3  482.19  3688.7     481  3809.3  478.69  3967.4   477.8  3988.2  477.03
  4273.2  474.03  4407.1  473.72    4429  472.99  4439.1  473.89  4500.1  473.24
  4510.2  474.04  4703.5  473.94    4825  473.68  4924.3  470.69  4968.3  470.31
  4977.4  469.95  4983.4   467.6  4985.5  467.54  4988.3  467.04  4991.5  467.54
  4992.6  469.16  4997.7  470.77  5066.7  471.67  5367.7  472.23  5466.7  473.74
  5551.6  475.58  5678.7  480.35    5700  480.54  5749.4  482.89  5866.4  486.18
#Mann= 6 ,-1 , 0
  3557.3      .1       0  4703.5      .1       0  4968.3     .12       0
  4985.5     .07       0  4991.5     .12       0  5066.7      .1       0
#XS Ineff= 2 , 0
                         5068.55          471.76
Permanent Ineff=
       F       F
Bank Sta=4985.5,4991.5
XS Rating Curve= 0 ,0
Exp/Cntr=0.3,0.1

Type RM Length L Ch R = 1 ,415     ,0,0,0
BEGIN DESCRIPTION:
UNT 015 IN LACR 1.0
END DESCRIPTION:
XS GIS Cut Line= 4
      2161505.08     13207320.81      2162181.99     13206278.83
      2161946.21     13205632.34      2161117.16     13205252.05
#Sta/Elev= 30
    3269  475.56  3296.5  474.57  3562.9  471.95  3639.1  471.25  3786.5  470.42
  3981.9  467.84  4012.2  468.49    4287  468.54  4443.9  466.31  4474.2   466.6
    4502  465.62  4702.9  466.79  4803.8   467.9  4864.9  467.36  4896.8  465.27
  4907.5  465.33  4915.4  466.31  4928.8  465.15    4946  465.31  4957.7  463.07
  4960.5  462.57  4963.7  463.07  5007.1  466.05  5035.1  466.25  5420.1  468.46
  5638.1  471.51  5913.2  476.97    6063  483.11  6091.5  483.07  6111.8  484.09
#Mann= 7 ,-1 , 0
    3269      .1       0  3562.9     .05       0  3639.1      .1       0
  4702.9     .05       0  4957.7    .035       0  4963.7     .05       0
  5035.1      .1       0
Bank Sta=4957.7,4963.7
XS Rating Curve= 0 ,0
Exp/Cntr=0.3,0.1

Chan Stop Cuts=-1
Use User Specified Reach Order=0
Composite Channel Slope=5