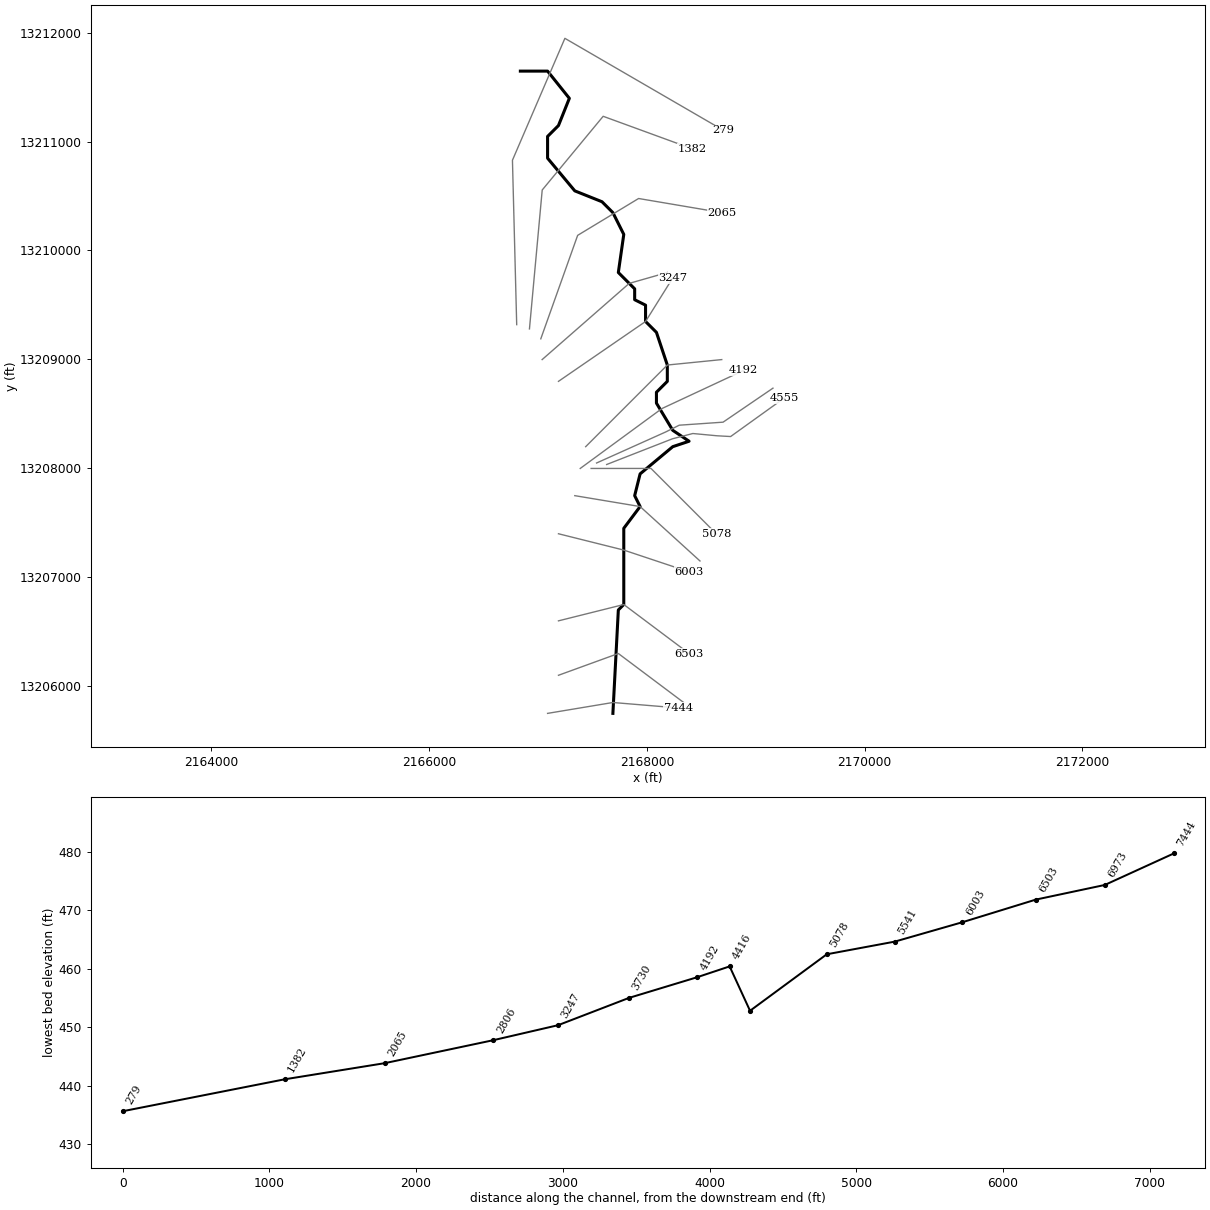
--- UNT 016 IN LACR.prj (project) ---

Proj Title=UNT 016 IN LACR Base Level Engineering
Current Plan=p01
Default Exp/Contr=0.3,0.1
English Units
Geom File=g01
Flow File=f01
Plan File=p01
Y Axis Title=Elevation
X Axis Title(PF)=Main Channel Distance
X Axis Title(XS)=Station
BEGIN DESCRIPTION:
UNT 016 IN LACR
END DESCRIPTION:
DSS Export Rating Curves= 0
DSS Export Rating Curve Sorted= 0
DSS Export Volume Flow Curves= 0
DXF OffsetX= 0
DXF OffsetY= 0
DXF ScaleX= 1
DXF ScaleY= 10

--- UNT 016 IN LACR.p01 (plan) ---

Plan Title=Multiple Run
Short Identifier=Multiple
Geom File=g01
Flow File=f01
Subcritical Flow
K Sum by GR= 0
Std Step Tol= 0.01
Critical Tol= 0.01
Num of Std Step Trials= 20
Max Error Tol= 0.3
Flow Tol Ratio= 0.001
Split Flow NTrial= 30
Split Flow Tol= 0.02
Split Flow Ratio= 0.02
Log Output Level= 0
Friction Slope Method= 1
Unsteady Friction Slope Method= 2
Unsteady Bridges Friction Slope Method= 1
Parabolic Critical Depth
Global Vel Dist=  1 , 1 , 1
Global Log Level= 0
CheckData=True
Encroach Param= -1, 0, 0, 0
BEGIN DESCRIPTION:
Multiple Run
END DESCRIPTION:

--- UNT 016 IN LACR.f01 (steady flow) ---

Flow Title=Multiple
Number of Profiles=7
Profile Names=10-year,25-year,50-year,1pct_min,100-year,1pct_plu,500-year
River Rch & RM= UNT 016 IN LACR,Reach-1,7444
     138     189     230     206     279     378     419
River Rch & RM= UNT 016 IN LACR,Reach-1,4555
     232     325     404     369     499     674     774
Boundary for River Rch & Prof#=UNT 016 IN LACR,Reach-1,1
Up Type=0
Dn Type=3
Dn Slope=0.005
Boundary for River Rch & Prof#=UNT 016 IN LACR,Reach-1,2
Up Type=0
Dn Type=3
Dn Slope=0.005
Boundary for River Rch & Prof#=UNT 016 IN LACR,Reach-1,3
Up Type=0
Dn Type=3
Dn Slope=0.005
Boundary for River Rch & Prof#=UNT 016 IN LACR,Reach-1,4
Up Type=0
Dn Type=3
Dn Slope=0.005
Boundary for River Rch & Prof#=UNT 016 IN LACR,Reach-1,5
Up Type=0
Dn Type=3
Dn Slope=0.005
Boundary for River Rch & Prof#=UNT 016 IN LACR,Reach-1,6
Up Type=0
Dn Type=3
Dn Slope=0.005
Boundary for River Rch & Prof#=UNT 016 IN LACR,Reach-1,7
Up Type=0
Dn Type=3
Dn Slope=0.005

--- UNT 016 IN LACR.g01 (geometry) ---

Geom Title=Existing Conditions
Program Version=4.10

River Reach=UNT 016 IN LACR ,Reach-1
Reach XY= 30
      2167687.72     13205746.86      2167737.72     13206696.85
      2167787.72     13206746.86      2167787.72     13207446.85
      2167937.72     13207646.85      2167887.72     13207746.86
      2167937.72     13207946.85      2168237.72     13208196.85
      2168387.72     13208246.86      2168237.72     13208346.85
      2168087.72     13208596.85      2168087.72     13208696.85
      2168187.72     13208796.85      2168187.72     13208946.85
      2168087.72     13209246.85      2167987.72     13209346.85
      2167987.72     13209496.85      2167887.72     13209546.86
      2167887.72     13209646.85      2167737.72     13209796.85
      2167787.72     13210146.85      2167687.72     13210346.86
      2167587.72     13210446.85      2167337.72     13210546.85
      2167087.72     13210846.86      2167087.72     13211046.85
      2167187.72     13211146.85      2167287.72     13211396.85
      2167087.72     13211646.85      2166837.72     13211646.85

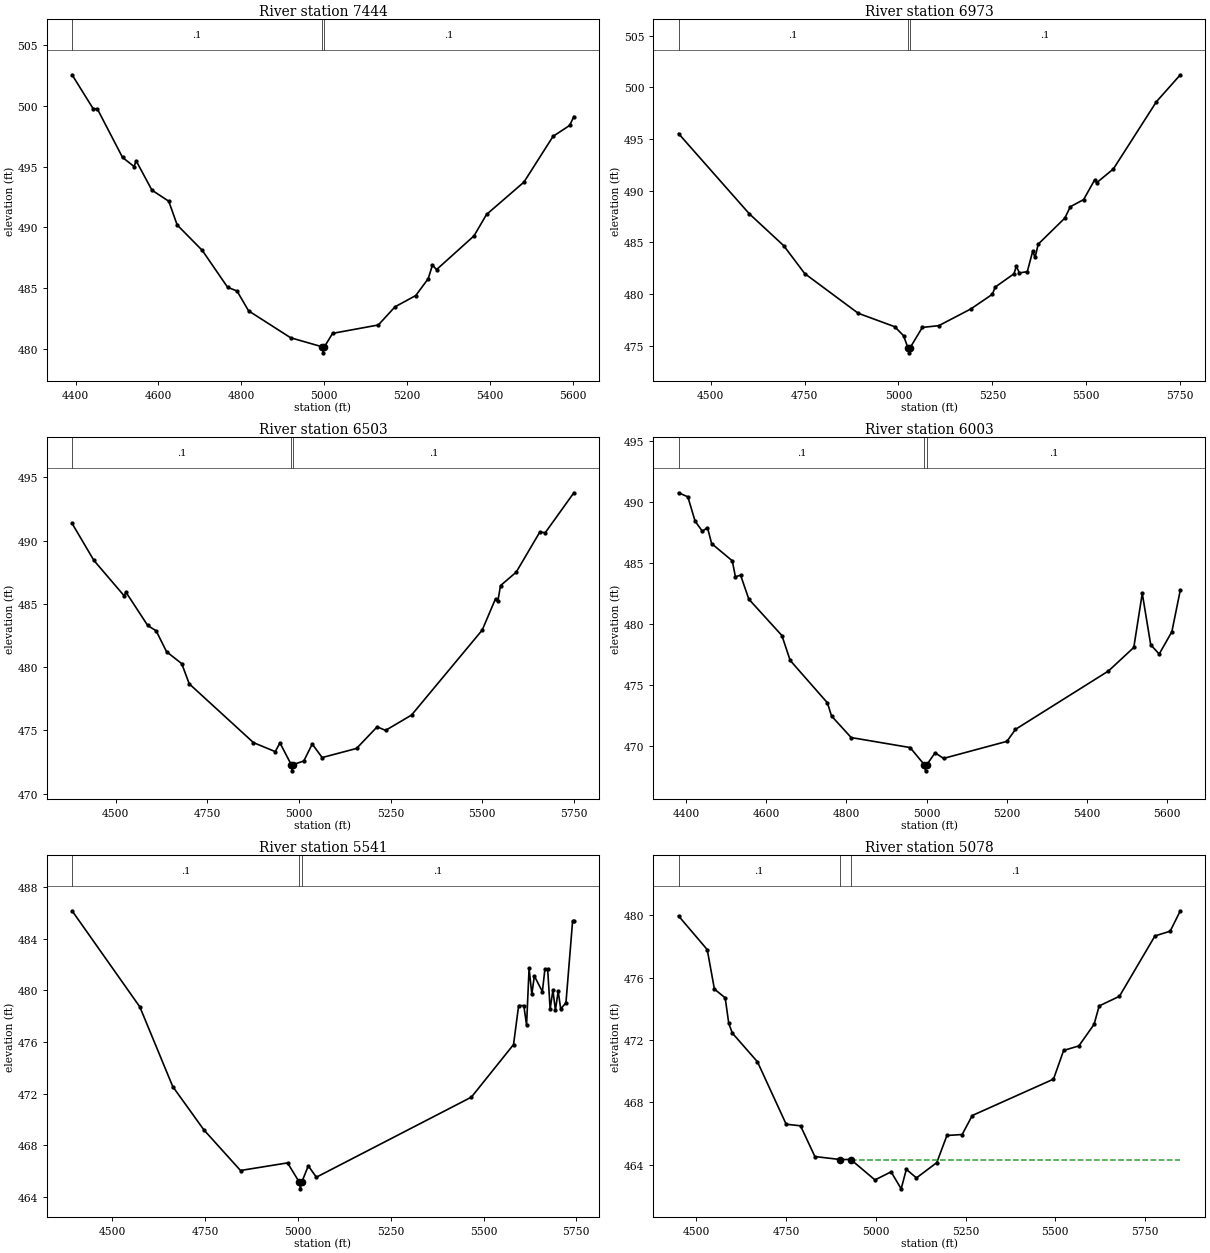
Type RM Length L Ch R = 1 ,7444    ,471,471,471
BEGIN DESCRIPTION:
UNT 016 IN LACR 12.0
END DESCRIPTION:
XS GIS Cut Line= 3
       2167087.7     13205746.85      2167687.72     13205846.85
      2168287.74     13205796.85
#Sta/Elev= 30
  4391.7  502.54  4442.4  499.76  4452.6  499.74  4513.4  495.75  4541.3     495
  4546.3  495.47  4584.3  493.06  4624.9  492.15  4645.2   490.2    4706   488.1
  4766.8  485.08  4789.6  484.77  4817.5  483.14  4918.9  480.93  4994.5  480.19
  4997.2  479.69  5000.5  480.19  5020.1  481.29  5130.5  481.98  5170.6  483.47
  5220.8   484.4  5250.9  485.79  5260.9   486.9  5270.9  486.53  5361.2   489.3
  5391.4  491.06  5481.7  493.72  5551.9  497.48    5592  498.38  5602.1  499.11
#Mann= 3 ,-1 , 0
  4391.7      .1       0  4994.5     .07       0  5000.5      .1       0
Bank Sta=4994.5,5000.5
XS Rating Curve= 0 ,0
Exp/Cntr=0.3,0.1

Type RM Length L Ch R = 1 ,6973    ,470,470,470
BEGIN DESCRIPTION:
UNT 016 IN LACR 11.0
END DESCRIPTION:
XS GIS Cut Line= 3
      2167187.75     13206096.87      2167737.72     13206296.85
      2168337.72     13205846.85
#Sta/Elev= 30
  4414.8  495.52    4603  487.76  4694.7  484.67  4750.6  481.97  4892.9  478.13
    4990  476.83  5013.5  475.96  5025.1   474.8  5027.9   474.3  5031.1   474.8
  5063.5  476.76  5107.3  476.93  5192.7  478.55    5250  479.97  5257.3  480.66
  5307.3  481.95  5313.5  482.66  5321.9  482.04  5342.7  482.15  5357.3  484.14
  5363.5  483.53  5371.9  484.82  5442.7  487.34  5457.3  488.44  5492.7  489.13
  5521.9  491.03  5528.1  490.78  5571.9   492.1  5686.5  498.61    5750  501.21
#Mann= 3 ,-1 , 0
  4414.8      .1       0  5025.1     .07       0  5031.1      .1       0
Bank Sta=5025.1,5031.1
XS Rating Curve= 0 ,0
Exp/Cntr=0.3,0.1

Type RM Length L Ch R = 1 ,6503    ,500,500,500
BEGIN DESCRIPTION:
UNT 016 IN LACR 10.0
END DESCRIPTION:
XS GIS Cut Line= 3
      2167187.69     13206596.85      2167787.72     13206746.86
      2168387.72     13206296.85
#Sta/Elev= 30
  4381.5  491.37  4440.8  488.45  4523.3  485.65  4528.4  485.93  4587.7   483.3
  4610.9  482.87  4639.2  481.22  4680.5  480.28  4701.1  478.68  4876.3  474.03
  4935.6  473.32  4948.5  474.01    4979   472.3  4981.7   471.8    4985   472.3
  5013.5  472.58  5036.5  473.92  5063.5  472.85  5157.3  473.57  5213.5  475.28
  5236.5     475  5307.3  476.21    5500  482.93  5536.5  485.42  5542.7  485.22
    5550  486.45  5592.7  487.51  5657.3  490.69  5671.9  490.63    5750  493.79
#Mann= 3 ,-1 , 0
  4381.5      .1       0    4979     .07       0    4985      .1       0
Bank Sta=4979,4985
XS Rating Curve= 0 ,0
Exp/Cntr=0.3,0.1

Type RM Length L Ch R = 1 ,6003    ,462,462,462
BEGIN DESCRIPTION:
UNT 016 IN LACR 9.0
END DESCRIPTION:
XS GIS Cut Line= 3
      2167187.69     13207396.86      2167787.72     13207246.86
      2168387.76     13207046.84
#Sta/Elev= 30
  4381.5  490.75  4404.7  490.42  4422.8  488.42  4440.8   487.6  4453.7  487.89
    4464  486.58  4515.5  485.17  4523.3  483.86  4536.2  483.99  4556.8  482.02
  4639.2  479.04  4659.8     477  4752.6  473.52  4762.9  472.44  4811.9  470.67
  4958.8  469.85  4994.4  468.44  4997.2  467.94  5000.4  468.44  5021.1  469.42
  5042.2  468.96  5200.3  470.36  5221.4  471.34  5453.3  476.13  5516.5  478.06
  5537.6   482.5  5558.7  478.28  5579.8  477.52  5611.4  479.35  5632.5  482.78
#Mann= 3 ,-1 , 0
  4381.5      .1       0  4994.4     .07       0  5000.4      .1       0
Bank Sta=4994.4,5000.4
XS Rating Curve= 0 ,0
Exp/Cntr=0.3,0.1

Type RM Length L Ch R = 1 ,5541    ,463,463,463
BEGIN DESCRIPTION:
UNT 016 IN LACR 8.0
END DESCRIPTION:
XS GIS Cut Line= 3
       2167337.7     13207746.86      2167937.72     13207646.85
      2168487.72     13207146.86
#Sta/Elev= 30
  4391.7  486.15  4574.2  478.71  4662.9  472.54  4746.6  469.19  4845.4  466.04
  4972.1  466.63  5004.1  465.12  5006.8  464.62  5010.1  465.12    5028   466.4
  5049.7  465.52  5467.3  471.72  5580.8  475.79  5594.6  478.81  5608.5  478.81
  5615.9   477.3  5622.7  481.69  5630.1  479.69  5636.9   481.1  5658.5  479.89
  5665.3  481.63  5672.7  481.63  5679.4  478.55  5686.9     480  5693.6  478.45
  5701.1  479.93  5707.8  478.55    5722  479.02  5739.9  485.35  5743.3  485.35
#Mann= 3 ,-1 , 0
  4391.7      .1       0  5004.1     .07       0  5010.1      .1       0
Bank Sta=5004.1,5010.1
XS Rating Curve= 0 ,0
Exp/Cntr=0.3,0.1

Type RM Length L Ch R = 1 ,5078    ,523,523,523
BEGIN DESCRIPTION:
UNT 016 IN LACR 7.0
END DESCRIPTION:
XS GIS Cut Line= 3
      2167487.72     13207996.85      2168037.72     13207996.85
       2168637.7     13207396.87
#Sta/Elev= 30
    4450  479.95    4530  477.79    4550  475.26    4580   474.7    4590  473.06
    4600  472.44    4670   470.6    4750   466.6    4790   466.5    4830  464.53
    4900  464.34    4930  464.34  4997.5  463.03  5042.4  463.55  5070.5  462.46
  5084.9  463.71  5113.1  463.16  5169.7  464.14    5198  465.88  5240.4  465.94
  5268.7  467.16    5495  469.49  5523.3  471.33  5565.7  471.62  5608.1     473
  5622.3  474.18  5678.8   474.8  5777.8  478.67  5820.2  478.97  5848.5  480.28
#Mann= 3 , 0 , 0
    4450      .1       0    4900     .07       0    4930      .1       0
#XS Ineff= 2 , 0
                         4940.26          464.33
Permanent Ineff=
       F       F
Bank Sta=4900,4930
XS Rating Curve= 0 ,0
Exp/Cntr=0.3,0.1

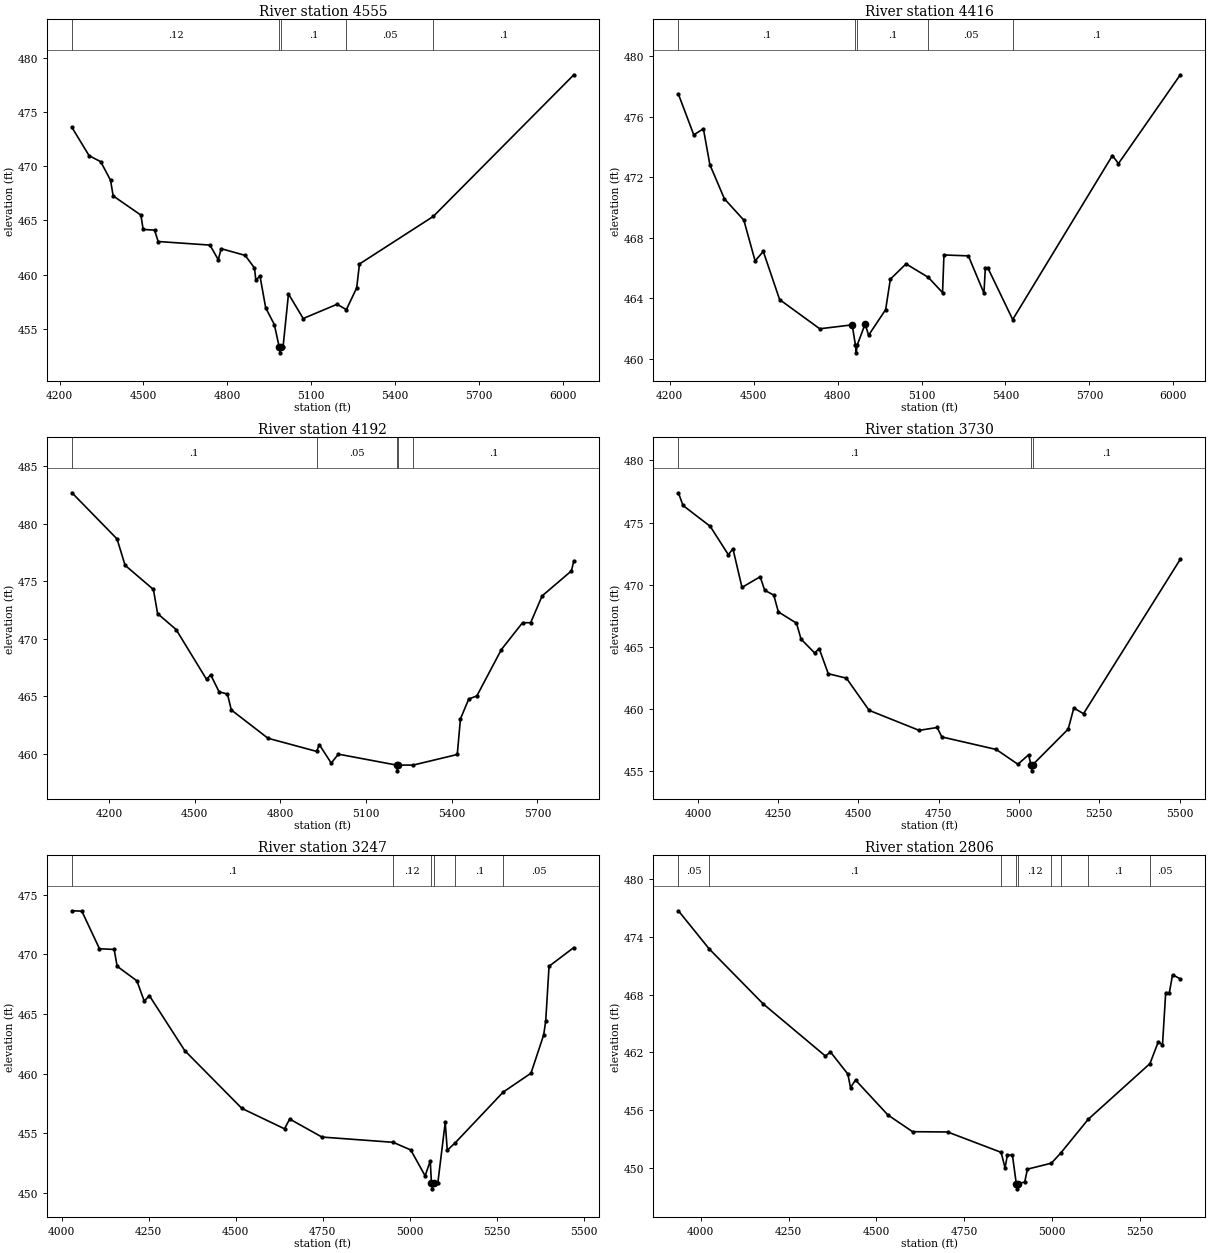
Type RM Length L Ch R = 1 ,4555    ,139,139,139
BEGIN DESCRIPTION:
Mapping XS 60abf721
END DESCRIPTION:
XS GIS Cut Line= 6
      2167630.41     13208033.05       2168234.6     13208269.16
       2168422.1     13208317.77      2168644.32     13208296.94
      2168769.32       13208290.       2169260.8     13208643.03
#Sta/Elev= 30
    4244  473.56  4305.5  470.96  4346.9  470.41  4382.1   468.7  4391.4  467.26
  4490.7  465.49  4498.8  464.17  4539.6  464.11  4552.5  463.06  4737.8  462.73
  4767.6  461.38  4777.9   462.4  4863.8  461.78  4896.9  460.63  4902.2  459.48
  4916.6  459.91  4937.2  456.96  4968.2  455.41  4985.9  453.31  4988.6  452.81
  4991.9  453.31  4999.2  453.31  5018.8  458.23  5071.5  455.97  5192.5  457.28
  5225.9  456.79  5262.8  458.79  5272.8  460.99  5536.9  465.37  6039.9  478.41
#Mann= 5 ,-1 , 0
    4244     .12       0  4985.9     .07       0  4991.9      .1       0
  5225.9     .05       0  5536.9      .1       0
Bank Sta=4985.9,4991.9
XS Rating Curve= 0 ,0
Exp/Cntr=0.3,0.1

Type RM Length L Ch R = 1 ,4416    ,224,224,224
BEGIN DESCRIPTION:
UNT 016 IN LACR 6.0
END DESCRIPTION:
XS GIS Cut Line= 5
      2167537.76     13208046.87       2168172.1     13208331.66
       2168297.1     13208394.16      2168699.88     13208421.94
      2169158.25     13208734.47
#Sta/Elev= 30
  4231.3  477.49  4286.1   474.8  4320.6   475.2  4343.7  472.83  4395.7  470.57
  4465.1  469.16  4505.3  466.47  4534.6  467.09    4593  463.91  4736.4  461.98
  4852.2  462.24    4864  460.89  4866.8  460.39    4870  460.89  4898.6   462.3
  4910.9  461.55  4971.9  463.25  4988.7  465.26  5044.7  466.27  5124.3  465.38
  5175.2  464.37  5180.2  466.86  5267.5   466.8  5323.1  464.34  5328.1  465.98
  5337.7  465.98  5425.9  462.59  5782.2  473.43  5803.8   472.9  6024.9  478.77
#Mann= 5 ,-1 , 0
  4231.3      .1       0    4864     .07       0    4870      .1       0
  5124.3     .05       0  5425.9      .1       0
Bank Sta=4852.2,4898.6
XS Rating Curve= 0 ,0
Exp/Cntr=0.3,0.1

Type RM Length L Ch R = 1 ,4192    ,462,462,462
BEGIN DESCRIPTION:
UNT 016 IN LACR 5.0
END DESCRIPTION:
XS GIS Cut Line= 3
      2167387.68     13207996.83      2168137.72     13208546.86
      2168887.68     13208896.84
#Sta/Elev= 30
  4069.9  482.68  4227.8  478.67    4256  476.38  4355.2  474.28  4369.8  472.18
  4434.6   470.8  4541.2  466.47  4555.8  466.86  4585.1  465.39  4614.5  465.19
    4628  463.81  4756.5  461.35  4926.6  460.21  4936.3  460.79    4978  459.19
  5002.8  459.97  5206.7  459.02  5209.4  458.52  5212.7  459.02  5264.8  459.02
  5419.3  459.94  5430.4  463.03  5459.5  464.76  5487.9  465.03  5573.8  469.06
  5647.9  471.39  5676.3  471.39  5716.5  473.72    5819  475.89  5827.6  476.77
#Mann= 5 ,-1 , 0
  4069.9      .1       0  4926.6     .05       0  5206.7     .03       0
  5212.7     .05       0  5264.8      .1       0
Bank Sta=5206.7,5212.7
XS Rating Curve= 0 ,0
Exp/Cntr=0.3,0.1

Type RM Length L Ch R = 1 ,3730    ,483,483,483
BEGIN DESCRIPTION:
UNT 016 IN LACR 4.0
END DESCRIPTION:
XS GIS Cut Line= 3
      2167437.69     13208196.83      2168187.72     13208946.85
      2168687.73     13208996.86
#Sta/Elev= 30
  3939.3   477.4  3953.5  476.38  4038.3   474.7  4094.9  472.41    4109   472.9
  4137.3  469.78  4193.9  470.64    4208  469.55  4236.3  469.16  4250.5  467.81
    4307   466.9  4321.2  465.62  4363.6   464.5  4377.7  464.86    4406  462.83
  4462.6  462.47  4533.3  459.88  4688.9  458.27  4745.4   458.5  4759.6  457.74
  4929.3  456.73  4996.5  455.54  5030.1   456.3  5037.2  455.51  5039.9  455.01
  5043.2  455.51  5153.3  458.37  5170.8  460.07    5201  459.61  5502.5  472.05
#Mann= 3 ,-1 , 0
  3939.3      .1       0  5037.2     .07       0  5043.2      .1       0
Bank Sta=5037.2,5043.2
XS Rating Curve= 0 ,0
Exp/Cntr=0.3,0.1

Type RM Length L Ch R = 1 ,3247    ,441,441,441
BEGIN DESCRIPTION:
UNT 016 IN LACR 3.0
END DESCRIPTION:
XS GIS Cut Line= 3
      2167187.74     13208796.87      2167987.72     13209346.85
      2168237.72     13209746.86
#Sta/Elev= 30
  4029.2  473.65  4057.6  473.62  4108.3  470.47  4150.5  470.41  4159.1     469
  4215.9  467.78  4236.9  466.08  4251.7  466.54  4353.2  461.94  4517.6  457.09
  4640.1  455.38    4655   456.2  4747.6  454.69  4952.1  454.25  5002.9  453.61
  5044.2  451.44    5059  452.69  5062.4  450.85  5065.2  450.35  5068.4  450.85
  5080.8  450.85    5102  455.91  5107.9  453.58  5131.5  454.23  5268.7  458.46
  5348.5  460.04    5385  463.25  5390.9  464.44  5400.4     469  5471.7  470.57
#Mann= 6 ,-1 , 0
  4029.2      .1       0  4952.1     .12       0  5062.4     .07       0
  5068.4     .12       0  5131.5      .1       0  5268.7     .05       0
Bank Sta=5062.4,5068.4
XS Rating Curve= 0 ,0
Exp/Cntr=0.3,0.1

Type RM Length L Ch R = 1 ,2806    ,741,741,741
BEGIN DESCRIPTION:
UNT 016 IN LACR 2.0
END DESCRIPTION:
XS GIS Cut Line= 3
      2167037.73     13208996.86      2167837.72     13209696.86
      2168187.72     13209796.85
#Sta/Elev= 30
    3937  476.74  4024.5  472.77  4177.6  467.06  4355.1  461.61  4369.3  462.04
  4418.7  459.74  4426.3  458.33  4440.5  459.12  4532.6  455.48  4602.8  453.74
  4702.5  453.71  4854.4  451.59  4865.7  449.97  4872.3  451.31  4886.6  451.31
  4897.8  448.29  4900.6  447.79  4903.8  448.29  4921.7  448.52  4929.3  449.84
  4997.4  450.46  5024.3  451.53  5102.4  455.04  5277.7  460.83  5301.6  463.12
  5313.3  462.76  5322.4  468.21  5332.8  468.21  5341.9  470.08    5364  469.65
#Mann= 9 ,-1 , 0
    3937     .05       0  4024.5      .1       0  4854.4     .12       0
  4897.8     .07       0  4903.8     .12       0  4997.4      .1       0
  5024.3     .12       0  5102.4      .1       0  5277.7     .05       0
Bank Sta=4897.8,4903.8
XS Rating Curve= 0 ,0
Exp/Cntr=0.3,0.1

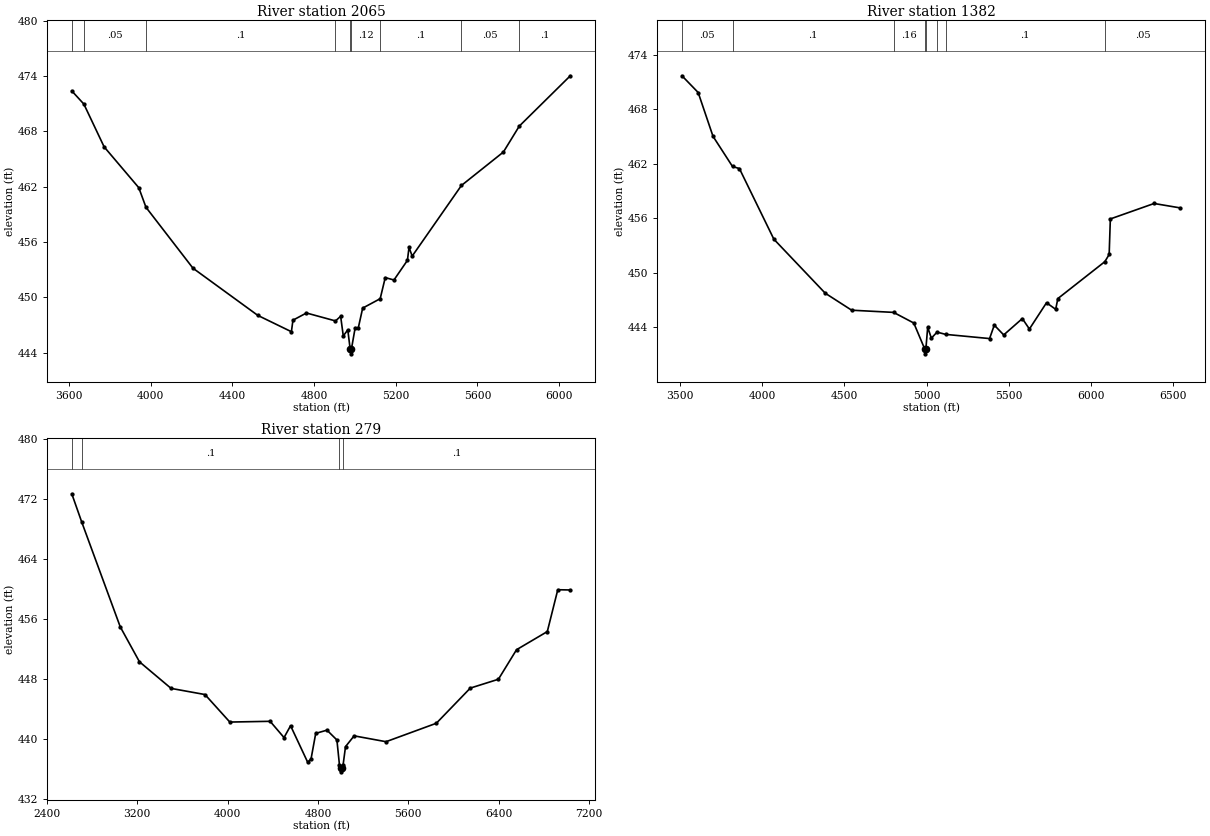
Type RM Length L Ch R = 1 ,2065    ,683,683,683
BEGIN DESCRIPTION:
Mapping XS 2bd06d10
END DESCRIPTION:
XS GIS Cut Line= 4
      2167025.39     13209187.54      2167363.94     13210138.09
      2167923.84     13210476.63      2168692.06     13210346.42
#Sta/Elev= 30
  3612.6  472.38  3671.8  470.95  3771.1  466.31  3940.9  461.88    3976  459.76
  4206.3  453.15    4524  448.03  4688.6  446.26  4696.2  447.51  4762.3  448.29
  4904.6  447.43  4929.9  447.93  4942.8   445.8  4964.9  446.46  4976.6  444.36
  4979.4  443.86  4982.6  444.36    5001  446.69  5016.5  446.69  5037.8  448.82
  5123.6  449.84  5148.4  452.13  5191.1  451.87  5257.1     454  5264.8  455.41
  5280.4  454.46  5521.6  462.12  5727.3  465.75  5805.1  468.56  6055.1  474.02
#Mann= 9 ,-1 , 0
  3612.6      .1       0  3671.8     .05       0    3976      .1       0
  4904.6     .12       0  4976.6     .07       0  4982.6     .12       0
  5123.6      .1       0  5521.6     .05       0  5805.1      .1       0
Bank Sta=4976.6,4982.6
XS Rating Curve= 0 ,0
Exp/Cntr=0.3,0.1

Type RM Length L Ch R = 1 ,1382    ,1103,1103,1103
BEGIN DESCRIPTION:
Mapping XS bdcfd1d3
END DESCRIPTION:
XS GIS Cut Line= 4
      2166921.23      13209278.7      2167038.42     13210554.75
      2167598.31     13211231.84      2168418.64     13210932.35
#Sta/Elev= 30
  3511.6  471.69  3610.2  469.85  3700.5  465.03  3819.2  461.71  3861.2  461.48
  4070.9  453.71  4383.4  447.77  4544.1   445.9  4799.3  445.66  4922.2  444.49
  4989.5   441.6  4992.2   441.1  4995.5   441.6  5006.8  444.03    5029  442.82
  5063.7  443.49    5116  443.24  5383.3  442.78  5411.9  444.26  5469.3  443.18
  5582.6  444.98  5625.6  443.83  5729.7  446.72  5785.5     446  5798.7  447.18
  6084.6  451.24  6110.9  452.03  6118.1  455.94  6384.2  457.64  6544.9  457.15
#Mann= 8 ,-1 , 0
  3511.6     .05       0  3819.2      .1       0  4799.3     .16       0
  4989.5     .07       0  4995.5     .16       0  5063.7     .12       0
    5116      .1       0  6084.6     .05       0
Bank Sta=4989.5,4995.5
XS Rating Curve= 0 ,0
Exp/Cntr=0.3,0.1

Type RM Length L Ch R = 1 ,279     ,0,0,0
BEGIN DESCRIPTION:
UNT 016 IN LACR 1.0
END DESCRIPTION:
XS GIS Cut Line= 4
      2166804.04     13209317.78      2166764.98     13210828.19
      2167246.75     13211947.98      2168703.71     13211102.43
#Sta/Elev= 30
  2620.3  472.74  2706.7  469.04  3049.5  454.99  3219.6  450.33  3499.7  446.78
  3799.8  445.96  4019.8  442.29  4376.6  442.39  4499.8  440.22  4557.7   441.8
  4709.8  436.91  4739.4   437.4  4780.4  440.78    4880  441.21    4968   439.9
  4990.5  436.58  5005.6  436.15  5008.4  435.65  5011.6  436.15  5022.4  436.52
  5044.2  439.01  5120.4  440.45  5402.9  439.67  5848.5  442.13  6149.2  446.82
  6398.1     448  6558.7  451.94  6831.1  454.36  6923.8  459.94  7034.8  459.91
#Mann= 4 ,-1 , 0
  2620.3     .05       0  2706.7      .1       0  4990.5     .07       0
  5022.4      .1       0
Bank Sta=5005.6,5011.6
XS Rating Curve= 0 ,0
Exp/Cntr=0.3,0.1

Chan Stop Cuts=-1
Use User Specified Reach Order=0
Composite Channel Slope=5