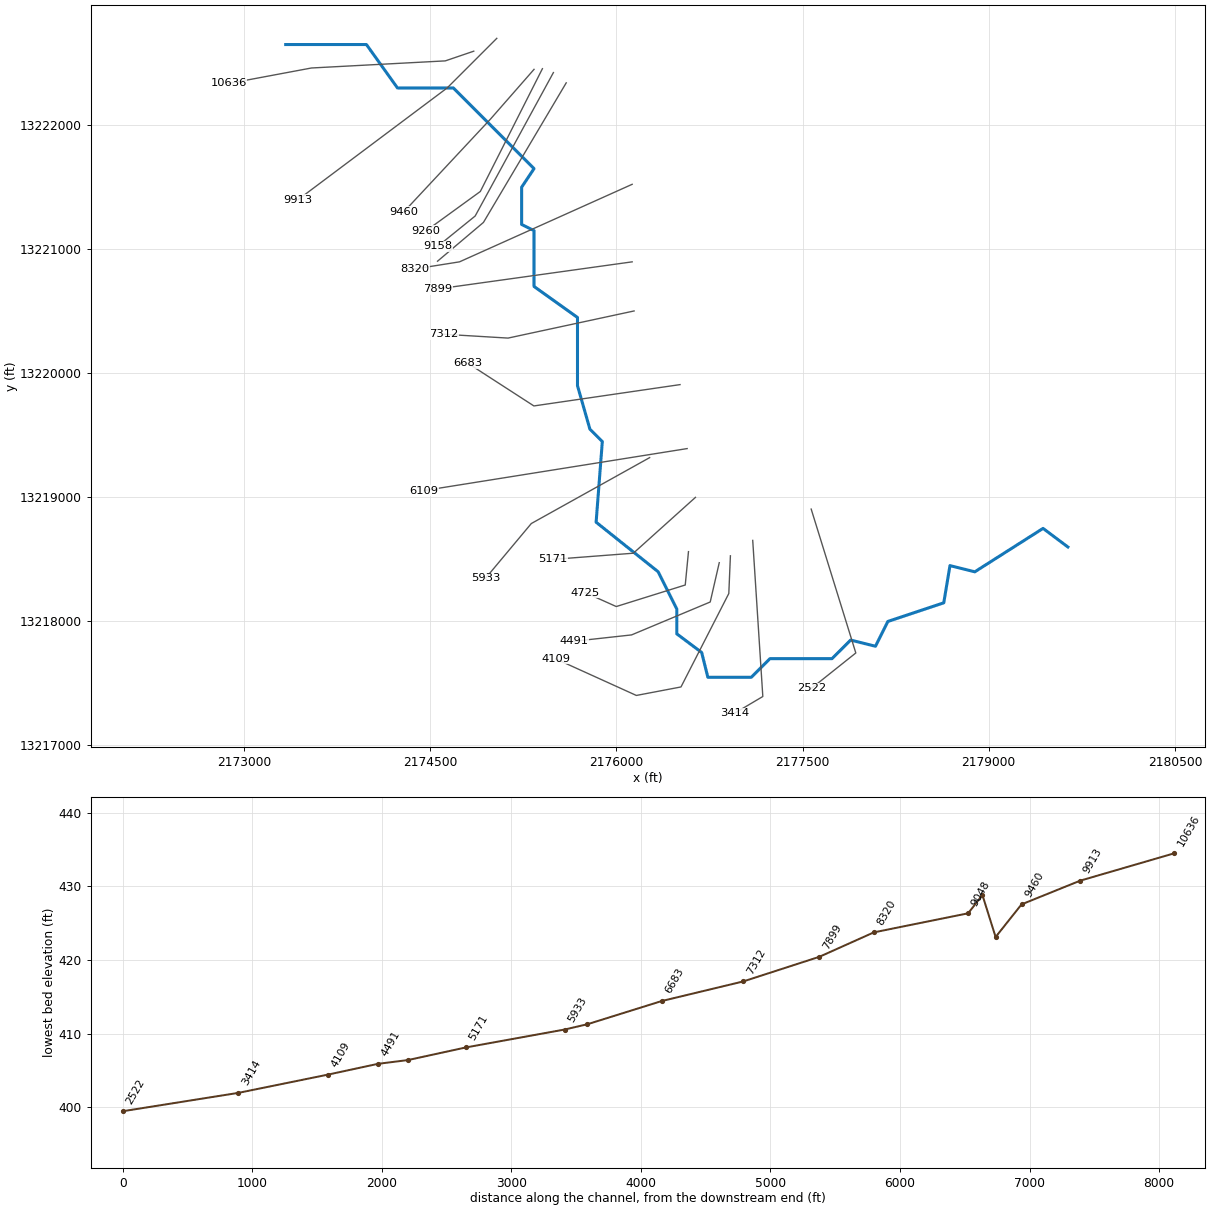
--- UNT 017 IN LACR.prj (project) ---

Proj Title=UNT 017 IN LACR Base Level Engineering
Current Plan=p01
Default Exp/Contr=0.3,0.1
English Units
Geom File=g01
Flow File=f01
Plan File=p01
Y Axis Title=Elevation
X Axis Title(PF)=Main Channel Distance
X Axis Title(XS)=Station
BEGIN DESCRIPTION:
UNT 017 IN LACR
END DESCRIPTION:
DSS Export Rating Curves= 0
DSS Export Rating Curve Sorted= 0
DSS Export Volume Flow Curves= 0
DXF OffsetX= 0
DXF OffsetY= 0
DXF ScaleX= 1
DXF ScaleY= 10

--- UNT 017 IN LACR.p01 (plan) ---

Plan Title=Multiple Run
Short Identifier=Multiple
Geom File=g01
Flow File=f01
Subcritical Flow
K Sum by GR= 0
Std Step Tol= 0.01
Critical Tol= 0.01
Num of Std Step Trials= 20
Max Error Tol= 0.3
Flow Tol Ratio= 0.001
Split Flow NTrial= 30
Split Flow Tol= 0.02
Split Flow Ratio= 0.02
Log Output Level= 0
Friction Slope Method= 1
Unsteady Friction Slope Method= 2
Unsteady Bridges Friction Slope Method= 1
Parabolic Critical Depth
Global Vel Dist=  1 , 1 , 1
Global Log Level= 0
CheckData=True
Encroach Param= -1, 0, 0, 0
BEGIN DESCRIPTION:
Multiple Run
END DESCRIPTION:

--- UNT 017 IN LACR.f01 (steady flow) ---

Flow Title=Multiple
Program Version=4.10
Number of Profiles= 7
Profile Names=10-year,25-year,50-year,1pct_min,100-year,1pct_plu,500-year
River Rch & RM=UNT 017 IN LACR,Reach-1         ,10636
     214     297     367     333     450     609     689
River Rch & RM=UNT 017 IN LACR,Reach-1         ,6109
     307     434     542     496     671     908    1049
River Rch & RM=UNT 017 IN LACR,Reach-1         ,5171
     307     434     542     496     671     908    1049
Boundary for River Rch & Prof#=UNT 017 IN LACR,Reach-1         , 1
Up Type= 0
Dn Type= 3
Dn Slope=0.005
Boundary for River Rch & Prof#=UNT 017 IN LACR,Reach-1         , 2
Up Type= 0
Dn Type= 3
Dn Slope=0.005
Boundary for River Rch & Prof#=UNT 017 IN LACR,Reach-1         , 3
Up Type= 0
Dn Type= 3
Dn Slope=0.005
Boundary for River Rch & Prof#=UNT 017 IN LACR,Reach-1         , 4
Up Type= 0
Dn Type= 3
Dn Slope=0.005
Boundary for River Rch & Prof#=UNT 017 IN LACR,Reach-1         , 5
Up Type= 0
Dn Type= 3
Dn Slope=0.005
Boundary for River Rch & Prof#=UNT 017 IN LACR,Reach-1         , 6
Up Type= 0
Dn Type= 3
Dn Slope=0.005
Boundary for River Rch & Prof#=UNT 017 IN LACR,Reach-1         , 7
Up Type= 0
Dn Type= 3
Dn Slope=0.005
DSS Import GetInterval= 0
DSS Import GetPeak= 0
DSS Import FillOption= 0

--- UNT 017 IN LACR.g01 (geometry) ---

Geom Title=Existing Conditions
Program Version=4.10

River Reach=UNT 017 IN LACR ,Reach-1
Reach XY= 30
      2173337.72     13222646.86      2173987.72     13222646.86
      2174237.72     13222296.85      2174687.72     13222296.85
      2175337.72     13221646.85      2175237.72     13221496.86
      2175237.72     13221196.86      2175337.72     13221146.85
      2175337.72     13220696.86      2175687.72     13220446.85
      2175687.72     13219896.85      2175787.72     13219546.86
      2175887.72     13219446.85      2175837.72     13218796.85
      2176337.72     13218396.86      2176487.72     13218096.85
      2176487.72     13217896.86      2176687.72     13217746.86
      2176737.72     13217546.85      2177087.72     13217546.85
      2177237.72     13217696.85      2177737.72     13217696.85
      2177887.72     13217846.85      2178087.72     13217796.85
      2178187.72     13217996.85      2178637.72     13218146.85
      2178687.72     13218446.85      2178887.72     13218396.86
      2179437.72     13218746.86      2179637.72     13218596.85

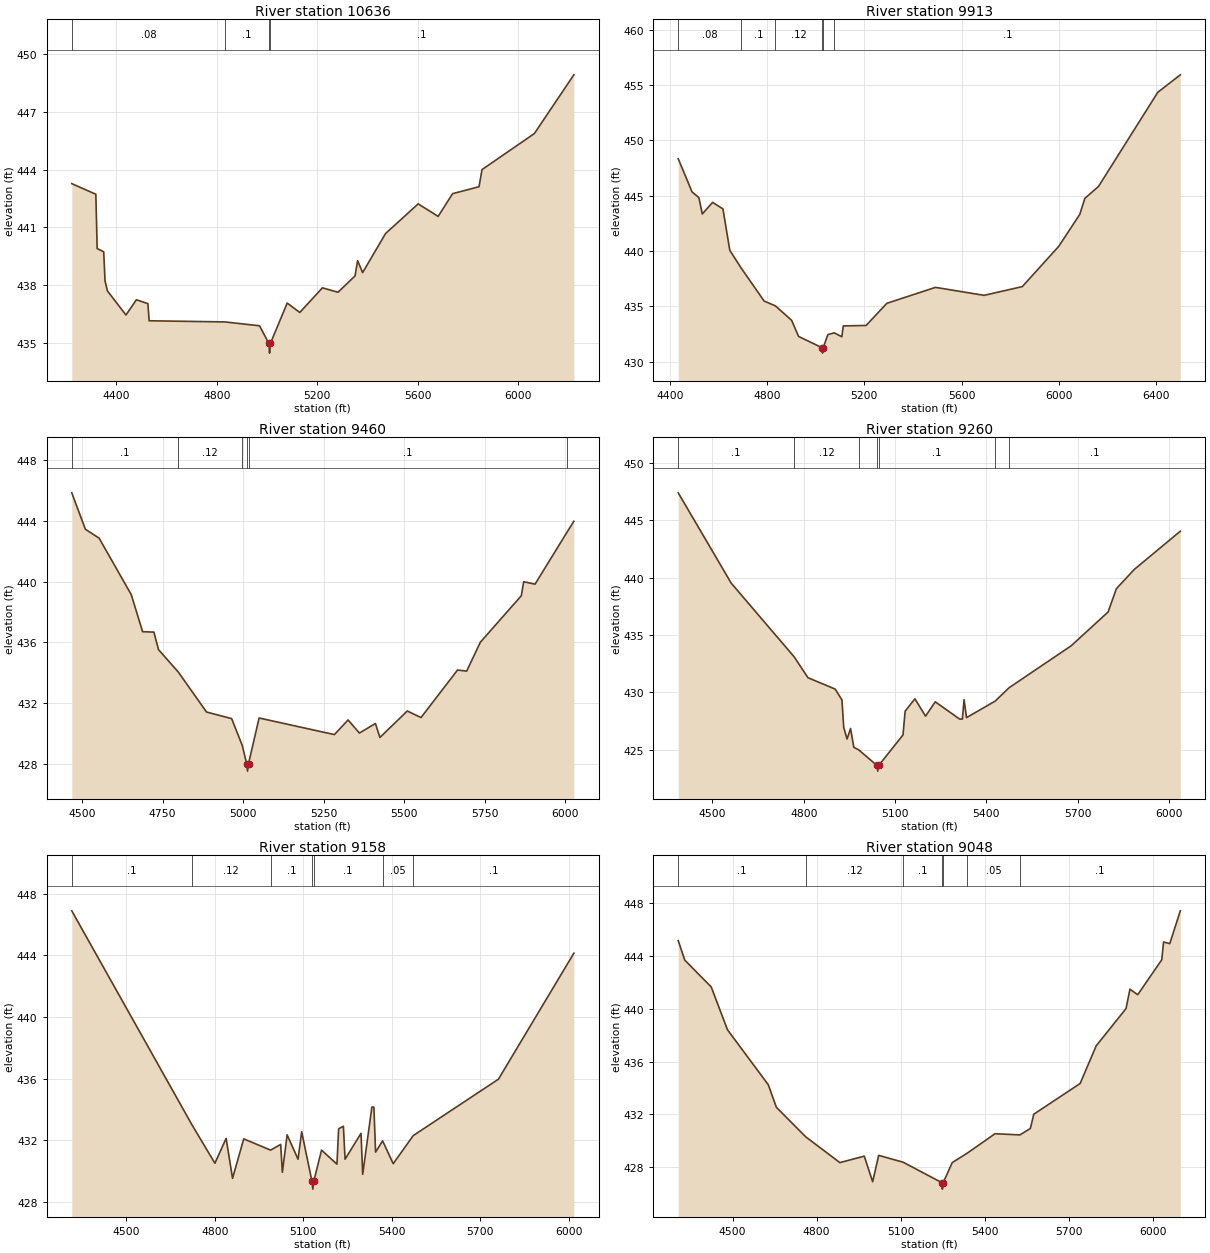
Type RM Length L Ch R = 1 ,10636   ,723,723,723
BEGIN DESCRIPTION:
UNT 017 IN LACR 15.0
END DESCRIPTION:
XS GIS Cut Line= 4
      2174852.12     13222593.25      2174622.97     13222515.14
      2173544.85     13222457.84       2172878.2     13222332.85
#Sta/Elev= 30
  4221.9  443.27  4317.8  442.72  4323.1   439.9  4349.1  439.73  4354.4  438.22
  4363.9   437.7  4437.8  436.45  4479.3  437.24  4525.1  437.04  4530.1  436.15
  4832.2  436.09    4970  435.89    5007  434.97  5009.8  434.47    5013  434.97
  5080.1  437.07  5130.2  436.58  5220.3  437.86  5282.5  437.63  5350.5  438.48
  5360.5  439.27  5380.5  438.65  5471.9  440.68  5601.8  442.22  5681.4  441.57
    5739  442.75  5844.2  443.11  5856.1     444  6064.6  445.87  6221.9  448.92
#Mann= 4 ,-1 , 0
  4221.9     .08       0  4832.2      .1       0    5007     .07       0
    5013      .1       0
Bank Sta=5007,5013
XS Rating Curve= 0 ,0
Exp/Cntr=0.3,0.1

Type RM Length L Ch R = 1 ,9913    ,453,453,453
BEGIN DESCRIPTION:
UNT 017 IN LACR 12.0
END DESCRIPTION:
XS GIS Cut Line= 3
      2175037.73     13222696.87      2174637.72     13222296.85
      2173437.72     13221396.85
#Sta/Elev= 30
  4434.3  448.33  4490.9  445.34  4519.2  444.82  4533.3  443.34  4575.7  444.39
  4618.2   443.8  4646.4  440.06  4693.1  438.46  4787.9  435.47  4833.9  435.04
    4901  433.73  4929.3  432.28  5025.1  431.27  5027.9  430.77  5031.1  431.27
    5050  432.45  5076.5   432.6  5107.3  432.25  5113.5  433.23  5207.3  433.27
  5292.7  435.27  5492.7  436.71  5692.7  435.99    5850  436.78    6000  440.42
  6086.5  443.31  6107.3  444.75  6163.5  445.83  6407.3  454.33    6500  455.91
#Mann= 6 ,-1 , 0
  4434.3     .08       0  4693.1      .1       0  4833.9     .12       0
  5025.1     .07       0  5031.1     .12       0  5076.5      .1       0
Bank Sta=5025.1,5031.1
XS Rating Curve= 0 ,0
Exp/Cntr=0.3,0.1

Type RM Length L Ch R = 1 ,9460    ,200,200,200
BEGIN DESCRIPTION:
UNT 017 IN LACR 11.0
END DESCRIPTION:
XS GIS Cut Line= 3
      2175337.72     13222446.85      2174987.72     13222046.85
      2174287.73     13221296.87
#Sta/Elev= 30
  4468.5  445.83  4510.7  443.44  4553.4  442.85  4653.1  439.14  4688.2  436.71
  4723.3  436.68  4737.6  435.53  4798.9  434.06  4886.6  431.43  4964.4     431
  4997.5  429.23  5010.9  428.05  5013.7  427.55  5016.9  428.05  5049.6  431.04
  5283.1  429.95  5325.6  430.91  5360.8  430.05  5410.4  430.68  5424.3  429.76
  5509.3   431.5  5551.8  431.07  5665.1  434.19  5693.5  434.12    5736  436.02
    5863  439.07  5870.3  439.99  5905.5  439.83  6005.5  443.27  6025.9  443.96
#Mann= 6 ,-1 , 0
  4468.5      .1       0  4798.9     .12       0  4997.5      .1       0
  5010.9     .07       0  5016.9      .1       0  6005.5     .05       0
Bank Sta=5010.9,5016.9
XS Rating Curve= 0 ,0
Exp/Cntr=0.3,0.1

Type RM Length L Ch R = 1 ,9260    ,102,102,102
BEGIN DESCRIPTION:
Mapping XS cb753123
END DESCRIPTION:
XS GIS Cut Line= 3
      2175405.19     13222452.15      2174905.17     13221462.52
      2174467.64     13221144.79
#Sta/Elev= 30
  4387.6  447.41  4561.6  439.53  4768.3   433.1    4814  431.27  4903.2  430.28
  4925.5  429.33  4931.3  426.94  4942.2  425.92  4953.7  426.84  4964.5   425.2
  4980.3  424.98  5040.4  423.62  5043.1  423.12  5046.4  423.62  5126.1  426.28
    5133  428.35  5165.1  429.43  5200.2  427.92    5232  429.17  5312.3  427.66
  5321.1  427.66  5326.7  429.36  5334.7  427.79  5428.8  429.23  5474.6   430.4
  5678.6  434.06  5799.9  437.01    5827  439.04  5885.7  440.72  6037.1  444.06
#Mann= 7 ,-1 , 0
  4387.6      .1       0  4768.3     .12       0  4980.3      .1       0
  5040.4     .07       0  5046.4      .1       0  5428.8     .05       0
  5474.6      .1       0
Bank Sta=5040.4,5046.4
XS Rating Curve= 0 ,0
Exp/Cntr=0.3,0.1

Type RM Length L Ch R = 1 ,9158    ,110,110,110
BEGIN DESCRIPTION:
UNT 017 IN LACR 10.0
END DESCRIPTION:
XS GIS Cut Line= 3
       2175493.7     13222420.84      2174863.51     13221264.61
      2174563.31     13221021.35
#Sta/Elev= 30
  4314.5  446.88    4722  433.01  4800.1  430.51  4838.1  432.12  4859.9  429.53
  4897.9  432.09    4989  431.36  5023.2  431.73  5028.9  429.92  5045.1  432.35
  5082.1  430.77  5094.4  432.55  5129.4  429.33  5132.2  428.83  5135.4  429.33
  5161.8  431.36  5214.1  430.45  5219.8  432.74  5235.9  432.91  5241.6  430.77
  5295.7  432.45  5301.4  429.79  5332.6  434.15  5339.4  434.15  5345.1  431.23
    5369  431.96  5404.9  430.48  5472.8   432.3  5761.9  435.96  6017.7  444.13
#Mann= 7 ,-1 , 0
  4314.5      .1       0    4722     .12       0    4989      .1       0
  5129.4     .07       0  5135.4      .1       0    5369     .05       0
  5472.8      .1       0
Bank Sta=5129.4,5135.4
XS Rating Curve= 0 ,0
Exp/Cntr=0.3,0.1

Type RM Length L Ch R = 1 ,9048    ,728,728,728
BEGIN DESCRIPTION:
Mapping XS 262ba2a0
END DESCRIPTION:
XS GIS Cut Line= 3
      2175596.94     13222338.07      2174930.26     13221213.05
      2174560.45     13220900.53
#Sta/Elev= 30
  4306.3  445.18  4329.7   443.7    4424  441.67  4482.1  438.42  4627.9  434.25
  4656.4  432.55  4761.6   430.3  4883.3  428.35  4970.3  428.84  5000.2   426.9
  5021.7   428.9  5109.1  428.38  5246.3  426.84    5249  426.34  5252.3  426.84
  5284.1  428.35  5336.6  429.05  5436.9  430.54  5525.8  430.45  5563.1  430.94
  5575.3  432.02  5740.8  434.35  5797.9   437.2  5904.5  440.03  5918.5   441.5
  5946.2  441.08    6032  443.73  6038.5  445.08  6060.6  444.95  6098.2  447.44
#Mann= 7 ,-1 , 0
  4306.3      .1       0  4761.6     .12       0  5109.1      .1       0
  5246.3     .07       0  5252.3      .1       0  5336.6     .05       0
  5525.8      .1       0
Bank Sta=5246.3,5252.3
XS Rating Curve= 0 ,0
Exp/Cntr=0.3,0.1

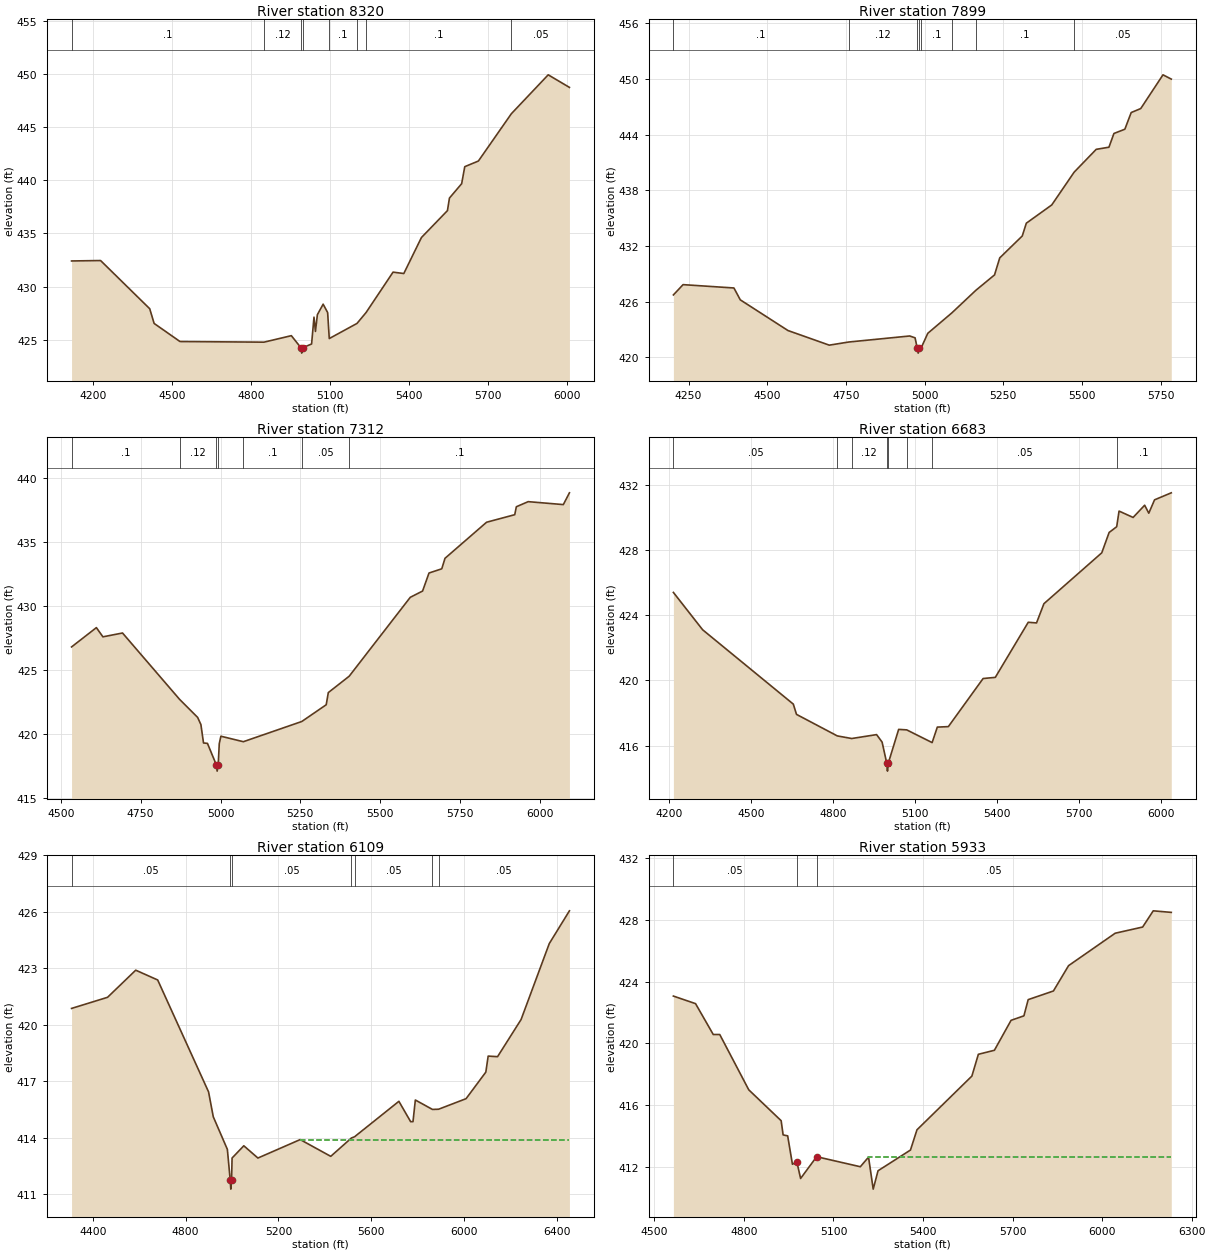
Type RM Length L Ch R = 1 ,8320    ,421,421,421
BEGIN DESCRIPTION:
UNT 017 IN LACR 9.0
END DESCRIPTION:
XS GIS Cut Line= 3
      2176128.17     13221520.34      2174737.55     13220895.34
       2174378.2     13220838.06
#Sta/Elev= 30
  4119.6  432.41  4229.7  432.45  4416.1  427.92  4432.8  426.54  4530.9  424.84
  4849.5  424.78  4953.3  425.39  4989.9  424.25  4992.6  423.75  4995.9  424.25
  5030.1  424.61  5039.2  427.13  5044.7  425.79    5052  427.36  5073.9  428.35
    5091  427.56  5097.1  425.12  5202.3  426.54  5236.6  427.56  5339.1  431.36
  5379.9  431.23  5446.7  434.61  5545.4  437.14    5553  438.32  5599.3  439.67
  5611.1  441.27  5662.8   441.8  5787.7  446.24  5927.6   449.9  6008.1  448.72
#Mann= 8 ,-1 , 0
  4119.6      .1       0  4849.5     .12       0  4989.9     .07       0
  4995.9     .12       0  5097.1      .1       0  5202.3     .05       0
  5236.6      .1       0  5787.7     .05       0
Bank Sta=4989.9,4995.9
XS Rating Curve= 0 ,0
Exp/Cntr=0.3,0.1

Type RM Length L Ch R = 1 ,7899    ,587,587,587
BEGIN DESCRIPTION:
UNT 017 IN LACR 8.0
END DESCRIPTION:
XS GIS Cut Line= 2
      2176128.16     13220895.34      2174561.64     13220676.76
#Sta/Elev= 30
  4201.9  426.71  4232.6  427.82  4394.2  427.46  4414.4  426.18  4565.8  422.87
  4697.1  421.29  4759.3  421.63  4952.7  422.28  4969.7  422.08  4976.8  420.93
  4979.6  420.43  4982.8  420.93  4988.1  420.93  5010.1  422.57  5086.8  424.78
  5162.5   427.2  5222.1  428.87  5238.7  430.71  5310.2  433.07  5323.1  434.45
  5403.9  436.42  5475.1  439.96  5545.2  442.42  5585.6  442.65  5601.4  444.13
  5636.1  444.59  5656.3  446.39  5686.6  446.82  5757.3  450.46  5783.6     450
#Mann= 8 ,-1 , 0
  4201.9      .1       0  4759.3     .12       0  4976.8     .07       0
  4982.8     .12       0  4988.1      .1       0  5086.8     .05       0
  5162.5      .1       0  5475.1     .05       0
Bank Sta=4976.8,4982.8
XS Rating Curve= 0 ,0
Exp/Cntr=0.3,0.1

Type RM Length L Ch R = 1 ,7312    ,629,629,629
BEGIN DESCRIPTION:
UNT 017 IN LACR 7.0
END DESCRIPTION:
XS GIS Cut Line= 3
      2176143.76      13220499.5      2175128.18     13220280.76
      2174608.69     13220311.93
#Sta/Elev= 30
  4533.5   426.8  4611.3  428.31  4631.7  427.59  4693.1  427.89  4871.9   422.7
  4928.4  421.29  4938.6  420.73  4946.8  419.29  4959.1  419.26  4986.8  417.59
  4989.5  417.09  4992.8  417.59  4996.1  419.23  5001.2  419.82  5071.5  419.39
  5254.5  420.97  5331.1  422.28  5337.6  423.23    5403  424.51  5594.3  430.68
  5632.9  431.17    5653  432.58    5693  432.91  5703.1  433.73  5833.3  436.55
  5921.5  437.14  5926.5  437.76  5963.5  438.16  6073.7  437.93  6092.8  438.85
#Mann= 7 ,-1 , 0
  4533.5      .1       0  4871.9     .12       0  4986.8     .07       0
  4992.8     .12       0  5071.5      .1       0  5254.5     .05       0
    5403      .1       0
Bank Sta=4986.8,4992.8
XS Rating Curve= 0 ,0
Exp/Cntr=0.3,0.1

Type RM Length L Ch R = 1 ,6683    ,574,574,574
BEGIN DESCRIPTION:
UNT 017 IN LACR 6.0
END DESCRIPTION:
XS GIS Cut Line= 3
      2176513.59     13219905.76      2175336.51     13219733.89
      2174805.29     13220077.62
#Sta/Elev= 30
  4215.9  425.39  4322.9   423.1  4654.8  418.54  4666.5  417.91  4815.8  416.59
  4868.6  416.43  4959.6  416.67  4979.8  416.21  4996.6  414.93  4999.4  414.43
  5002.6  414.93  5040.4  416.99    5070  416.96  5162.9  416.18  5181.9  417.13
  5222.3  417.16  5349.5  420.11  5394.1  420.18  5514.7  423.56    5545  423.52
  5572.1   424.7  5783.8  427.82  5810.8  429.07  5838.4  429.42  5847.1  430.38
  5898.5  429.99  5940.8  430.74  5955.9  430.25    5977  431.07  6038.2   431.5
#Mann= 8 ,-1 , 0
  4215.9     .05       0  4815.8      .1       0  4868.6     .12       0
  4996.6     .07       0  5002.6     .12       0    5070      .1       0
  5162.9     .05       0  5838.4      .1       0
Bank Sta=4996.6,5002.6
XS Rating Curve= 0 ,0
Exp/Cntr=0.3,0.1

Type RM Length L Ch R = 1 ,6109    ,176,176,176
BEGIN DESCRIPTION:
UNT 017 IN LACR 5.0
END DESCRIPTION:
XS GIS Cut Line= 2
      2176570.86     13219390.13      2174451.92     13219051.72
#Sta/Elev= 30
  4308.2  420.87  4463.3  421.46  4584.8   422.9  4679.4  422.38  4898.7  416.44
    4919  415.12  4979.7  413.39  4991.9  411.78  4994.6  411.28  4997.9  411.78
    5000  412.93  5050.6  413.58  5111.4  412.93  5293.7  413.91  5425.3  413.02
  5514.1  413.99    5528  414.06    5719  415.94  5769.6  414.86  5779.8  414.86
  5789.9  416.01  5863.6  415.51    5890  415.52  6008.5  416.08  6093.7  417.49
  6103.8  418.34  6144.3  418.31  6245.6  420.28  6367.1  424.31    6454  426.05
#Mann= 7 ,-1 , 0
  4308.2     .05       0  4991.9     .03       0  4997.9     .05       0
  5514.1     .12       0    5528     .05       0  5863.6      .1       0
    5890     .05       0
#XS Ineff= 2 , 0
                          5293.4          413.91
Permanent Ineff=
       F       F
Bank Sta=4991.9,4997.9
XS Rating Curve= 0 ,0
Exp/Cntr=0.3,0.1

Type RM Length L Ch R = 1 ,5933    ,762,762,762
BEGIN DESCRIPTION:
UNT 017 IN LACR 4.0
END DESCRIPTION:
XS GIS Cut Line= 3
      2176268.82     13219317.23      2175315.68     13218785.97
      2174945.91     13218343.28
#Sta/Elev= 30
  4563.7  423.06  4637.9  422.57  4697.3  420.57    4719  420.57  4816.2  416.99
  4924.7  414.99  4931.3  414.07  4946.5  414.01  4962.5  412.17  4977.1  412.34
  4989.9  411.25  5043.6  412.66  5189.9  412.01  5217.5  412.63  5233.1  410.56
  5249.3  411.75  5357.9  413.09  5379.7   414.4  5563.7  417.88  5585.4  419.29
  5639.1  419.55    5695  421.49    5738  421.78  5752.3  422.83  5836.9  423.39
  5887.6  425.03  6043.8  427.13  6135.8  427.53  6171.3  428.58  6231.7  428.48
#Mann= 3 , 0 , 0
  4563.7     .05       0  4977.1     .03       0  5043.6     .05       0
#XS Ineff= 2 , 0
                         5214.77          412.65
Permanent Ineff=
       F       F
Bank Sta=4977.1,5043.6
XS Rating Curve= 0 ,0
Exp/Cntr=0.3,0.1

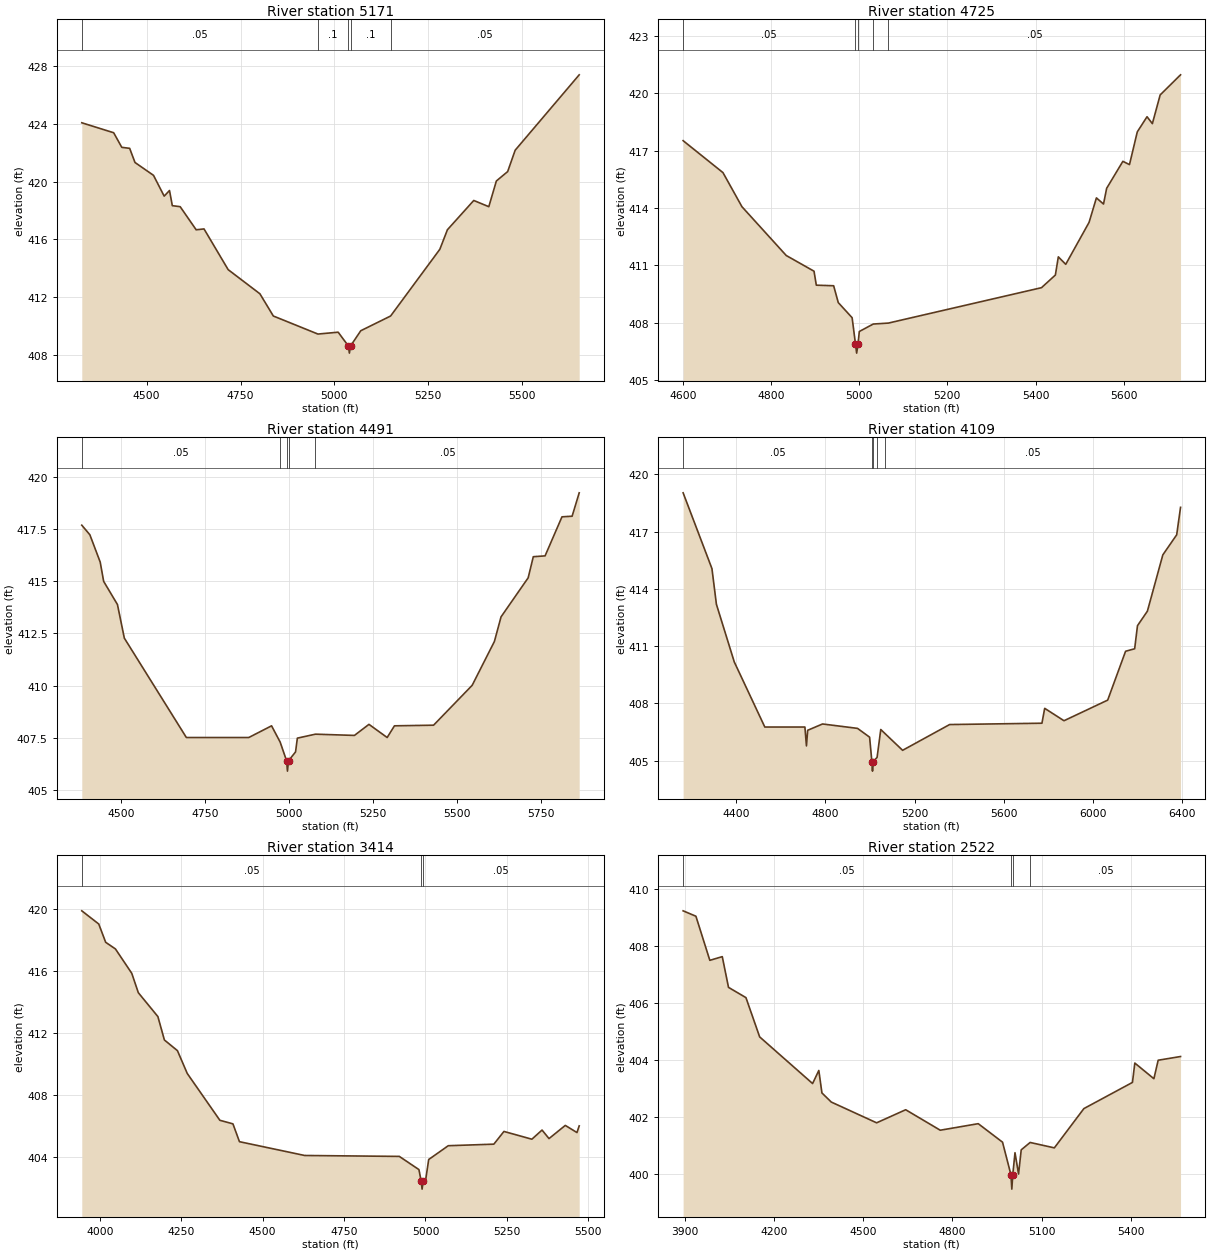
Type RM Length L Ch R = 1 ,5171    ,446,446,446
BEGIN DESCRIPTION:
UNT 017 IN LACR 2.0
END DESCRIPTION:
XS GIS Cut Line= 3
      2176637.73     13218996.87      2176137.72     13218546.86
      2175487.74     13218496.86
#Sta/Elev= 30
  4327.3  424.08  4412.2  423.39  4433.8  422.38  4454.8  422.31    4469  421.33
  4518.3  420.44  4546.7     419  4560.9  419.39  4568.4  418.34  4589.3  418.27
  4631.9  416.67  4652.8  416.73  4717.1  413.91  4801.6  412.24  4837.4   410.7
  4956.2  409.45    5010  409.58  5037.1  408.63  5039.9  408.13  5043.1  408.63
  5070.2  409.68  5149.7   410.7  5280.8  415.32  5300.9  416.67  5371.1   418.7
  5411.2  418.27  5431.3  420.05  5461.4   420.7  5481.4  422.18  5651.9   427.4
#Mann= 5 ,-1 , 0
  4327.3     .05       0  4956.2      .1       0  5037.1     .07       0
  5043.1      .1       0  5149.7     .05       0
Bank Sta=5037.1,5043.1
XS Rating Curve= 0 ,0
Exp/Cntr=0.3,0.1

Type RM Length L Ch R = 1 ,4725    ,234,234,234
BEGIN DESCRIPTION:
Mapping XS 0468fc7c
END DESCRIPTION:
XS GIS Cut Line= 4
      2176581.64     13218559.62       2176555.6     13218290.57
      2176000.04     13218116.95      2175748.34     13218229.79
#Sta/Elev= 30
  4600.7  417.52  4691.1  415.85  4734.1  414.07  4834.6  411.52  4897.6   410.7
  4902.8  409.97  4942.1  409.94  4952.6  409.06    4984  408.27  4991.5  406.92
  4994.3  406.42  4997.5  406.92  5000.3  407.55    5032  407.94  5066.3  407.99
  5413.6  409.84    5445   410.5  5451.7  411.45  5468.5  411.06  5521.4  413.25
  5538.1  414.53  5554.2  414.21  5561.3  415.03  5598.1  416.44  5613.1  416.27
  5630.8  417.98  5652.9  418.77    5665  418.41  5682.7  419.91  5728.9  420.96
#Mann= 5 ,-1 , 0
  4600.7     .05       0  4991.5     .03       0  4997.5     .05       0
    5032      .1       0  5066.3     .05       0
Bank Sta=4991.5,4997.5
XS Rating Curve= 0 ,0
Exp/Cntr=0.3,0.1

Type RM Length L Ch R = 1 ,4491    ,382,382,382
BEGIN DESCRIPTION:
Mapping XS d37a0ea9
END DESCRIPTION:
XS GIS Cut Line= 4
      2176829.47     13218470.32      2176756.72     13218153.62
      2176123.29     13217888.26      2175656.73      13217836.9
#Sta/Elev= 30
  4383.4  417.68  4407.5  417.22  4438.3  415.91  4448.5  414.99  4489.6  413.88
  4510.1  412.27  4694.8  407.51  4880.7  407.51  4948.5  408.07  4974.1  407.29
  4993.1   406.4  4995.8   405.9  4999.1   406.4  5019.9  406.82  5025.3  407.48
  5079.1  407.67  5195.2  407.61  5238.5  408.14  5292.7  407.51  5314.4  408.07
  5430.9   408.1  5545.8  410.01    5612  412.11  5631.8  413.29  5712.6  415.16
  5727.8  416.17  5762.9  416.21  5813.2  418.08  5843.4  418.11  5864.5  419.23
#Mann= 5 ,-1 , 0
  4383.4     .05       0  4974.1      .1       0  4993.1     .07       0
  4999.1      .1       0  5079.1     .05       0
Bank Sta=4993.1,4999.1
XS Rating Curve= 0 ,0
Exp/Cntr=0.3,0.1

Type RM Length L Ch R = 1 ,4109    ,695,695,695
BEGIN DESCRIPTION:
Mapping XS 659abff6
END DESCRIPTION:
XS GIS Cut Line= 5
      2176919.35     13218525.95      2176906.51      13218222.1
      2176521.32     13217468.83      2176161.81     13217400.35
      2175511.97     13217695.34
#Sta/Elev= 30
  4162.1  419.03  4291.3  415.06  4311.3  413.19  4391.4  410.17  4528.3  406.76
    4708  406.76  4714.9  405.77  4720.5  406.59  4787.1  406.92  4943.8  406.69
    4998  406.23  5008.2  404.95    5011  404.45  5014.2  404.95  5031.6  405.17
  5048.1  406.63  5068.7   406.4    5146  405.54  5356.6  406.89  5770.6  406.96
  5782.9  407.74  5869.4  407.09  6065.3  408.17  6145.5  410.73  6186.2  410.86
  6198.9  412.07  6243.3  412.83  6312.5  415.78  6374.6  416.83  6391.9  418.27
#Mann= 5 ,-1 , 0
  4162.1     .05       0  5008.2     .03       0  5014.2     .05       0
  5031.6      .1       0  5068.7     .05       0
Bank Sta=5008.2,5014.2
XS Rating Curve= 0 ,0
Exp/Cntr=0.3,0.1

Type RM Length L Ch R = 1 ,3414    ,892,892,892
BEGIN DESCRIPTION:
Mapping XS 6d549c2c
END DESCRIPTION:
XS GIS Cut Line= 3
      2177099.11     13218650.06      2177180.43     13217391.79
      2176950.98     13217255.82
#Sta/Elev= 30
  3944.6  419.91  3996.7  419.06    4018  417.88    4048  417.45  4098.1  415.88
  4118.2  414.63  4178.3  413.09  4198.3  411.58  4238.4  410.89  4268.5  409.42
  4368.7   406.4  4408.8  406.17  4428.8  405.02  4629.2  404.13  4919.8  404.07
    4980  403.22    4987  402.46  4989.7  401.96    4993  402.46    5000  402.46
    5010  403.87  5070.1  404.76    5210  404.86  5241.1  405.68  5326.9  405.18
  5358.1  405.77  5379.5  405.22  5429.5  406.07  5465.3  405.61  5472.2  406.04
#Mann= 3 ,-1 , 0
  3944.6     .05       0    4987     .03       0    4993     .05       0
Bank Sta=4987,4993
XS Rating Curve= 0 ,0
Exp/Cntr=0.3,0.1

Type RM Length L Ch R = 1 ,2522    ,0,0,0
BEGIN DESCRIPTION:
UNT 017 IN LACR 1.0
END DESCRIPTION:
XS GIS Cut Line= 3
       2177569.9      13218902.6      2177929.42     13217742.75
      2177571.28     13217457.09
#Sta/Elev= 30
  3894.7  409.25  3937.7  409.06  3984.5  407.51  4026.3  407.64  4047.3  406.56
  4105.9   406.2    4152  404.82    4330  403.18  4350.9  403.64  4361.4  402.85
  4392.8  402.53  4545.3   401.8    4643  402.26  4759.2  401.54  4886.9  401.77
  4968.6  401.12    4997  399.97  4999.8  399.47    5003  399.97  5010.5  400.75
  5022.5     400  5031.4  400.85  5061.4  401.11  5142.8  400.92  5242.1   402.3
  5405.4  403.22  5413.4   403.9  5477.5  403.35  5491.9     404  5567.1  404.13
#Mann= 4 ,-1 , 0
  3894.7     .05       0    4997     .03       0    5003     .05       0
  5061.4     .05       0
Bank Sta=4997,5003
XS Rating Curve= 0 ,0
Exp/Cntr=0.3,0.1

Chan Stop Cuts=-1
Use User Specified Reach Order=0
Composite Channel Slope=5