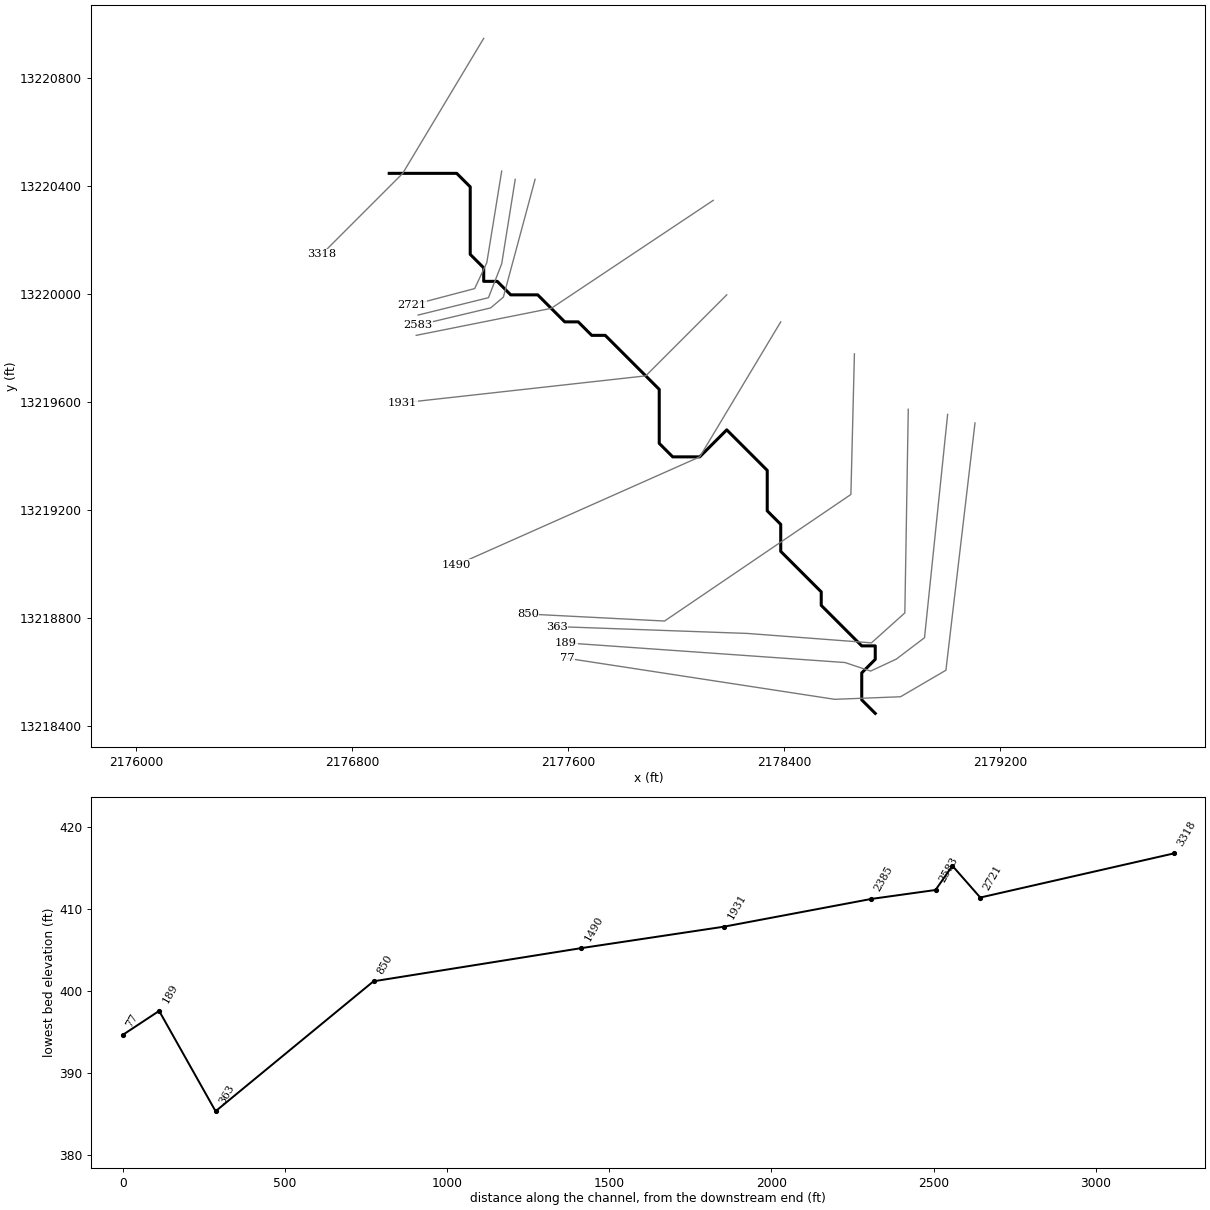
--- UNT 018 IN LACR.prj (project) ---

Proj Title=UNT 018 IN LACR Base Level Engineering
Current Plan=p01
Default Exp/Contr=0.3,0.1
English Units
Geom File=g01
Flow File=f01
Plan File=p01
BEGIN DESCRIPTION:
UNT 018 IN LACR
END DESCRIPTION:

--- UNT 018 IN LACR.p01 (plan) ---

Plan Title=Multiple Run
Short Identifier=Multiple
Geom File=g01
Flow File=f01
Subcritical Flow
K Sum by GR= 0
Std Step Tol= 0.01
Critical Tol= 0.01
Num of Std Step Trials= 20
Max Error Tol= 0.3
Flow Tol Ratio= 0.001
Split Flow NTrial= 30
Split Flow Tol= 0.02
Split Flow Ratio= 0.02
Log Output Level= 0
Friction Slope Method= 1
Unsteady Friction Slope Method= 2
Unsteady Bridges Friction Slope Method= 1
Parabolic Critical Depth
Global Vel Dist=  1 , 1 , 1
Global Log Level= 0
CheckData=True
Encroach Param= -1, 0, 0, 0
BEGIN DESCRIPTION:
Multiple Run
END DESCRIPTION:

--- UNT 018 IN LACR.f01 (steady flow) ---

Flow Title=Multiple
Number of Profiles=7
Profile Names=10-year,25-year,50-year,1pct_min,100-year,1pct_plu,500-year
River Rch & RM= UNT 018 IN LACR,Reach-1,3318
     176     244     300     272     368     498     562
Boundary for River Rch & Prof#=UNT 018 IN LACR,Reach-1,1
Up Type=0
Dn Type=3
Dn Slope=0.005
Boundary for River Rch & Prof#=UNT 018 IN LACR,Reach-1,2
Up Type=0
Dn Type=3
Dn Slope=0.005
Boundary for River Rch & Prof#=UNT 018 IN LACR,Reach-1,3
Up Type=0
Dn Type=3
Dn Slope=0.005
Boundary for River Rch & Prof#=UNT 018 IN LACR,Reach-1,4
Up Type=0
Dn Type=3
Dn Slope=0.005
Boundary for River Rch & Prof#=UNT 018 IN LACR,Reach-1,5
Up Type=0
Dn Type=3
Dn Slope=0.005
Boundary for River Rch & Prof#=UNT 018 IN LACR,Reach-1,6
Up Type=0
Dn Type=3
Dn Slope=0.005
Boundary for River Rch & Prof#=UNT 018 IN LACR,Reach-1,7
Up Type=0
Dn Type=3
Dn Slope=0.005

--- UNT 018 IN LACR.g01 (geometry) ---

Geom Title=Existing Conditions

River Reach=UNT 018 IN LACR,Reach-1
Reach XY= 30
      2176937.72     13220446.85      2177187.72     13220446.85
      2177237.72     13220396.85      2177237.72     13220146.85
      2177287.72     13220096.85      2177287.72     13220046.86
      2177337.72     13220046.86      2177387.72     13219996.85
      2177487.72     13219996.85      2177587.72     13219896.85
      2177637.72     13219896.85      2177687.72     13219846.85
      2177737.72     13219846.85      2177937.72     13219646.85
      2177937.72     13219446.85      2177987.72     13219396.86
      2178087.72     13219396.86      2178187.72     13219496.85
      2178337.72     13219346.85      2178337.72     13219196.85
      2178387.72     13219146.85      2178387.72     13219046.86
      2178537.72     13218896.86      2178537.72     13218846.85
      2178687.72     13218696.85      2178737.72     13218696.85
      2178737.72     13218646.85      2178687.72     13218596.85
      2178687.72     13218496.85      2178737.72     13218446.85

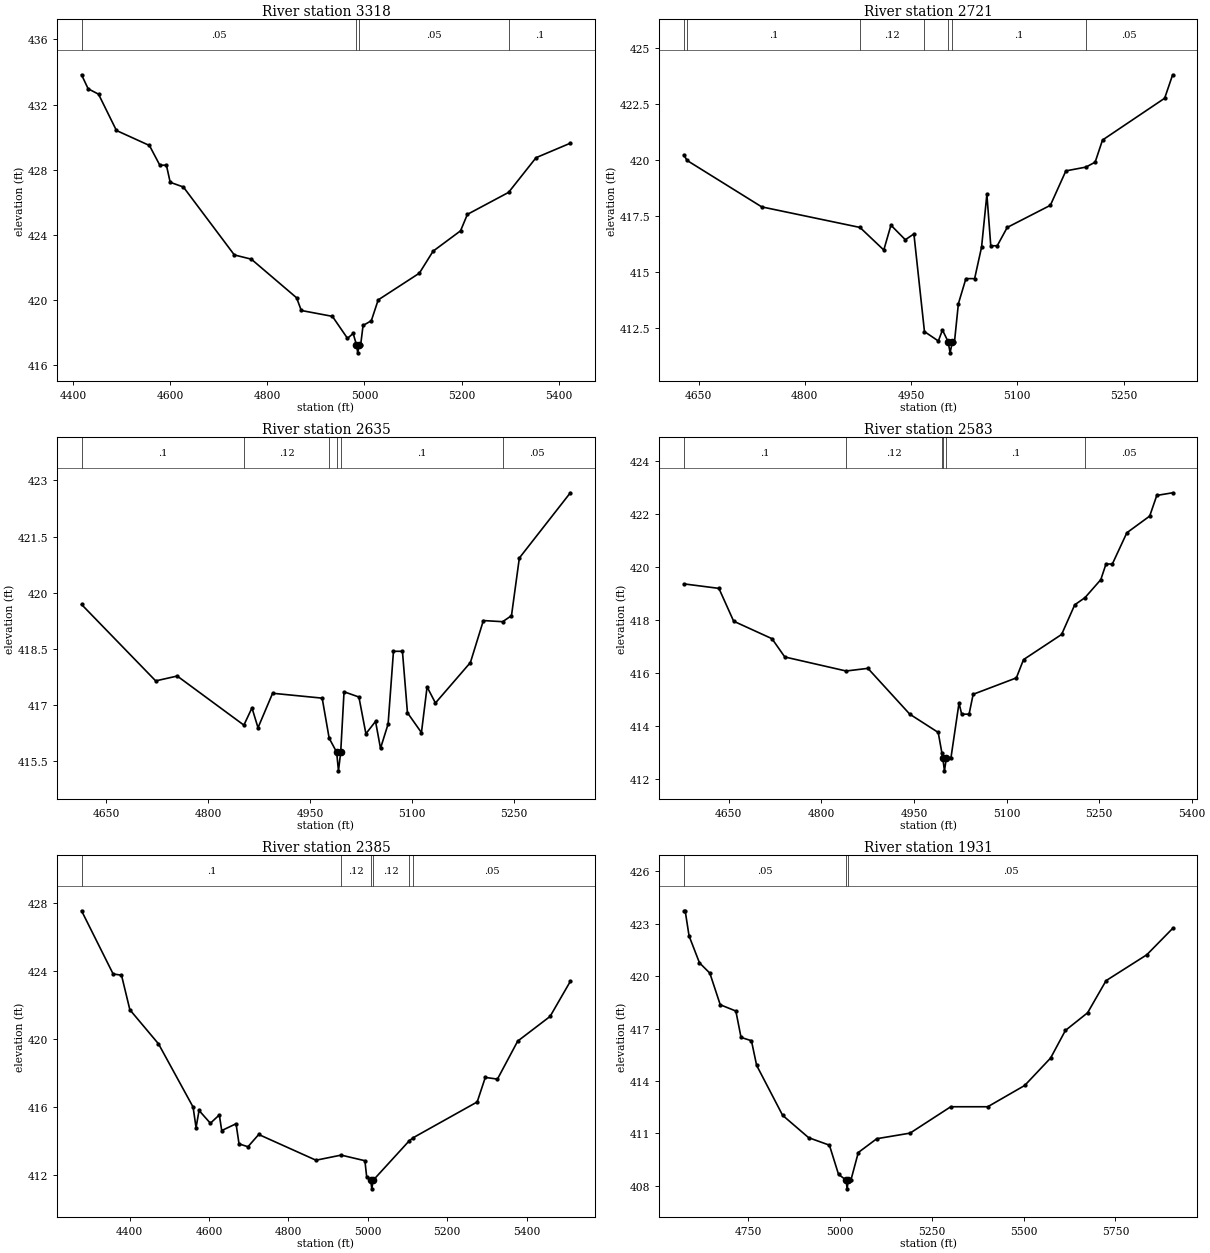
Type RM Length L Ch R = 1,3318,597,597,597
BEGIN DESCRIPTION:
UNT 018 IN LACR 6.0
END DESCRIPTION:
XS GIS Cut Line= 3
      2177287.72     13220946.86      2176987.72     13220446.85
      2176687.70     13220146.83
#Sta/Elev= 30
  4416.9  433.83  4430.5  432.97  4451.9  432.64  4488.8  430.41  4556.8  429.49
  4578.2  428.28  4591.8  428.28  4599.6  427.23  4626.8  426.94  4731.8  422.77
  4766.8  422.51  4860.1  420.14  4869.8  419.36  4933.9  419.00  4965.0  417.65
  4976.7  417.95  4983.4  417.26  4986.1  416.76  4989.4  417.26  4992.2  417.26
  4997.1  418.44  5014.1  418.73  5028.3  420.01  5113.1  421.65  5141.4  423.00
  5198.0  424.25  5212.1  425.26  5297.0  426.61  5353.6  428.74  5424.3  429.63
#Mann=4,-1,0
  4416.9    0.05       0  4983.4    0.03       0  4989.4    0.05       0
  5297.0     0.1       0
Bank Sta=4983.4,4989.4
Exp/Cntr=0.3,0.1

Type RM Length L Ch R = 1,2721,86,86,86
BEGIN DESCRIPTION:
Mapping XS d8dd77a0
END DESCRIPTION:
XS GIS Cut Line= 4
      2177354.35     13220455.35      2177299.18     13220116.13
      2177254.22     13220020.08      2177021.95     13219958.96
#Sta/Elev= 30
  4629.3  420.24  4633.7  419.99  4739.2  417.91  4877.9  416.99  4911.5  415.98
  4921.6  417.09  4941.9  416.44  4954.0  416.70  4968.9  412.33  4988.5  411.91
  4994.3  412.40  5002.3  411.88  5005.1  411.38  5008.3  411.88  5011.3  411.88
  5016.8  413.58  5027.4  414.70  5039.7  414.70  5049.5  416.11  5057.0  418.47
  5062.5  416.17  5071.6  416.17  5085.7  416.99  5146.6  417.98  5168.5  419.52
  5196.8  419.69  5209.8  419.91  5220.2  420.90  5307.9  422.77  5319.2  423.82
#Mann=7,-1,0
  4629.3    0.05       0  4633.7     0.1       0  4877.9    0.12       0
  4968.9     0.1       0  5002.3    0.07       0  5008.3     0.1       0
  5196.8    0.05       0
Bank Sta=5002.3,5008.3
Exp/Cntr=0.3,0.1

Type RM Length L Ch R = 1,2635,52,52,52
BEGIN DESCRIPTION:
UNT 018 IN LACR 5.0
END DESCRIPTION:
XS GIS Cut Line= 4
      2177404.42     13220424.68      2177354.36     13220112.05
      2177305.31     13219986.36      2177044.78     13219922.00
#Sta/Elev= 30
  4613.4  419.69  4722.6  417.65  4754.3  417.78  4852.5  416.47  4864.4  416.93
  4873.3  416.40  4894.8  417.32  4967.8  417.19  4978.1  416.12  4989.1  415.75
  4991.8  415.25  4995.1  415.75  5000.0  417.36  5021.9  417.22  5032.2  416.24
  5046.4  416.57  5053.7  415.85  5064.9  416.50  5072.8  418.44  5086.0  418.44
  5093.4  416.80  5114.0  416.27  5122.3  417.49  5134.6  417.06  5186.1  418.14
  5205.2  419.26  5233.6  419.23  5246.6  419.39  5258.2  420.93  5333.3  422.67
#Mann=6,-1,0
  4613.4     0.1       0  4852.5    0.12       0  4978.1     0.1       0
  4989.1    0.07       0  4995.1     0.1       0  5233.6    0.05       0
Bank Sta=4989.1,4995.1
Exp/Cntr=0.3,0.1

Type RM Length L Ch R = 1,2583,198,198,198
BEGIN DESCRIPTION:
Mapping XS b0c6b50e
END DESCRIPTION:
XS GIS Cut Line= 4
      2177478.01     13220424.77      2177360.49     13219988.40
      2177313.48     13219948.55      2177042.67     13219884.17
#Sta/Elev= 30
  4577.2  419.36  4634.0  419.19  4657.9  417.95  4720.0  417.29  4740.7  416.60
  4840.1  416.07  4875.4  416.17  4943.2  414.44  4989.3  413.75  4995.3  412.97
  4996.6  412.80  4999.4  412.30  5002.6  412.80  5010.0  412.80  5023.0  414.86
  5027.3  414.44  5039.3  414.44  5045.9  415.19  5115.9  415.81  5127.5  416.50
  5189.2  417.45  5210.5  418.57  5227.1  418.84  5252.7  419.52  5261.1  420.11
  5271.4  420.11  5294.9  421.29  5331.9  421.92  5343.4  422.70  5369.1  422.80
#Mann=6,-1,0
  4577.2     0.1       0  4840.1    0.12       0  4995.3     0.1       0
  4996.6    0.07       0  5002.6     0.1       0  5227.1    0.05       0
Bank Sta=4996.6,5002.6
Exp/Cntr=0.3,0.1

Type RM Length L Ch R = 1,2385,454,454,454
BEGIN DESCRIPTION:
UNT 018 IN LACR 4.0
END DESCRIPTION:
XS GIS Cut Line= 3
      2178137.71     13220346.85      2177537.72     13219946.85
      2177037.72     13219846.86
#Sta/Elev= 30
  4278.9  427.53  4358.5  423.82  4379.5  423.75  4400.6  421.72  4472.7  419.72
  4559.8  416.01  4567.3  414.80  4574.8  415.81  4603.4  415.06  4625.9  415.55
  4631.9  414.63  4668.0  415.03  4675.5  413.85  4698.0  413.68  4725.1  414.40
  4869.3  412.89  4932.7  413.19  4992.5  412.86  4997.0  411.91  5007.2  411.71
  5009.9  411.21  5013.2  411.71  5104.2  414.03  5114.1  414.21  5275.3  416.31
  5295.7  417.75  5326.3  417.65  5377.3  419.88  5458.9  421.33  5509.9  423.39
#Mann=6,-1,0
  4278.9     0.1       0  4932.7    0.12       0  5007.2    0.07       0
  5013.2    0.12       0  5104.2     0.1       0  5114.1    0.05       0
Bank Sta=5007.2,5013.2
Exp/Cntr=0.3,0.1

Type RM Length L Ch R = 1,1931,441,441,441
BEGIN DESCRIPTION:
UNT 018 IN LACR 3.0
END DESCRIPTION:
XS GIS Cut Line= 3
      2178187.75     13219996.88      2177887.72     13219696.86
      2176987.76     13219596.86
#Sta/Elev= 30
  4575.7  423.75  4579.3  423.75  4589.9  422.31  4618.2  420.77  4646.4  420.18
  4674.7  418.37  4717.2  418.01  4731.3  416.50  4759.6  416.31  4773.7  414.90
  4844.4  412.04  4915.1  410.76  4971.7  410.33  4996.5  408.66  5017.1  408.33
  5019.9  407.83  5023.1  408.33  5030.2  408.33  5050.3  409.91  5100.6  410.70
  5191.2  411.02  5301.8  412.53  5402.5  412.53  5503.1  413.75  5573.5  415.32
  5613.8  416.90  5674.1  417.91  5724.4  419.75  5835.1  421.23  5905.5  422.74
#Mann=3,-1,0
  4575.7    0.05       0  5017.1    0.03       0  5023.1    0.05       0
Bank Sta=5017.1,5023.1
Exp/Cntr=0.3,0.1

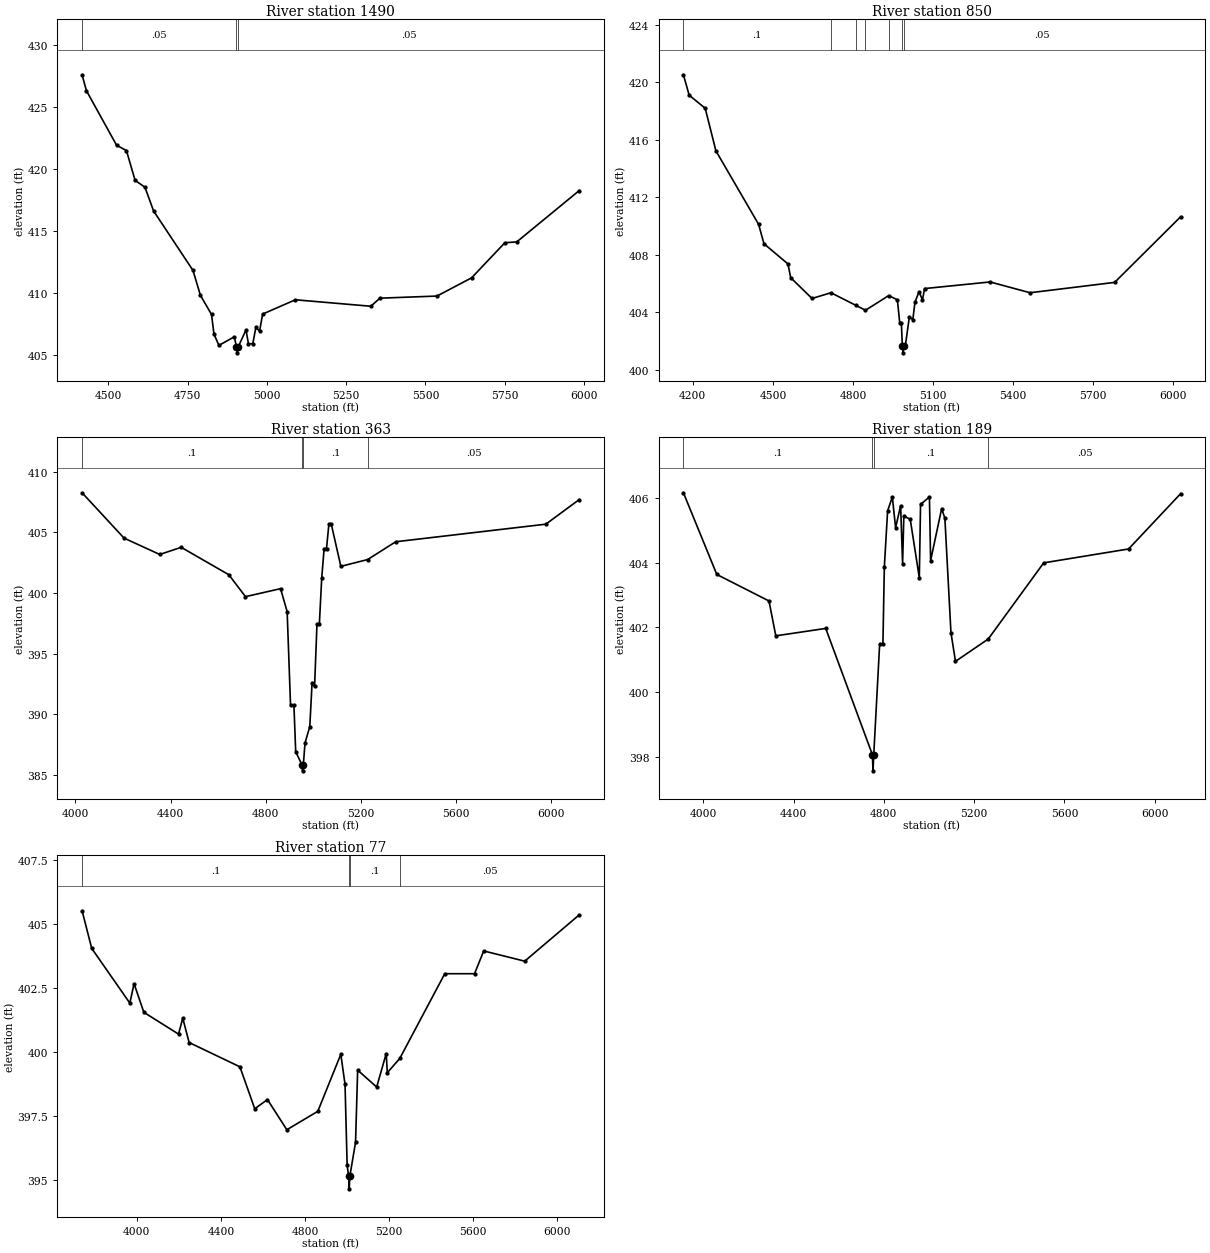
Type RM Length L Ch R = 1,1490,640,640,640
BEGIN DESCRIPTION:
UNT 018 IN LACR 2.0
END DESCRIPTION:
XS GIS Cut Line= 3
      2178387.72     13219896.86      2178087.72     13219396.86
      2177187.71     13218996.85
#Sta/Elev= 30
  4416.9  427.59  4430.5  426.31  4525.7  421.92  4556.8  421.49  4584.1  419.09
  4615.2  418.54  4642.4  416.63  4766.8  411.84  4790.1  409.84  4825.1  408.30
  4832.8  406.73  4848.4  405.81  4897.0  406.50  4903.7  405.71  4906.5  405.21
  4909.7  405.71  4933.9  407.05  4941.7  405.94  4955.3  405.94  4965.0  407.25
  4976.7  406.96  4986.4  408.33  5089.6  409.48  5327.6  408.96  5356.3  409.61
  5536.2  409.78  5645.6  411.25  5750.3  414.07  5787.9  414.14  5984.9  418.27
#Mann=3,-1,0
  4416.9    0.05       0  4903.7    0.03       0  4909.7    0.05       0
Bank Sta=4903.7,4909.7
Exp/Cntr=0.3,0.1

Type RM Length L Ch R = 1,850,487,487,487
BEGIN DESCRIPTION:
Mapping XS 21247b6d
END DESCRIPTION:
XS GIS Cut Line= 4
      2178660.60     13219778.39      2178647.58     13219257.59
      2177957.47     13218788.84      2177451.15     13218814.80
#Sta/Elev= 30
  4164.9  420.51  4186.4  419.09  4246.5  418.18  4286.5  415.22  4446.5  410.11
  4466.5  408.76  4556.6  407.35  4566.6  406.40  4646.6  404.95  4717.5  405.35
  4811.1  404.47  4846.8  404.13  4933.7  405.15  4966.4  404.86  4975.3  403.22
  4981.3  403.22  4984.9  401.67  4987.7  401.17  4990.9  401.67  4996.3  401.67
  5011.2  403.67  5024.2  403.48  5032.2  404.69  5047.2  405.41  5060.4  404.86
  5068.2  405.64  5313.6  406.10  5463.4  405.35  5780.2  406.07  6027.1  410.63
#Mann=7,-1,0
  4164.9     0.1       0  4717.5    0.12       0  4811.1     0.1       0
  4846.8    0.12       0  4933.7    0.05       0  4984.9    0.03       0
  4990.9    0.05       0
Bank Sta=4984.9,4990.9
Exp/Cntr=0.3,0.1

Type RM Length L Ch R = 1,363,174,174,174
BEGIN DESCRIPTION:
Mapping XS 26419869
END DESCRIPTION:
XS GIS Cut Line= 5
      2178860.04     13219573.12      2178847.36     13218818.94
      2178723.78     13218708.04      2178264.32     13218742.89
      2177557.69     13218768.25
#Sta/Elev= 30
  4028.4  408.27  4204.7  404.53  4354.7  403.18  4444.7  403.77  4644.7  401.51
  4714.8  399.70  4862.1  400.36  4889.8  398.46  4904.0  390.75  4918.2  390.75
  4925.7  386.91  4951.8  385.83  4954.6  385.33  4957.8  385.83  4964.8  387.63
  4984.9  388.98  4994.5  392.59  5005.0  392.29  5015.0  397.41  5025.0  397.41
  5035.0  401.25  5045.1  403.67  5055.1  403.67  5065.1  405.68  5075.2  405.68
  5115.3  402.20  5227.7  402.76  5345.9  404.23  5976.5  405.68  6116.6  407.71
#Mann=4,-1,0
  4028.4     0.1       0  4951.8    0.07       0  4957.8     0.1       0
  5227.7    0.05       0
Bank Sta=4951.8,4957.8
Exp/Cntr=0.3,0.1

Type RM Length L Ch R = 1,189,112,112,112
BEGIN DESCRIPTION:
Mapping XS e3976f9b
END DESCRIPTION:
XS GIS Cut Line= 6
      2179005.80     13219554.08      2178920.24     13218727.05
      2178815.68     13218647.83      2178720.61     13218603.47
      2178625.55     13218635.16      2177592.65     13218708.03
#Sta/Elev= 30
  3911.7  406.17  4059.7  403.64  4290.9  402.82  4321.1  401.74  4542.3  401.97
  4749.2  398.06  4751.9  397.56  4755.2  398.06  4781.3  401.48  4795.8  401.48
  4802.1  403.87  4816.6  405.61  4837.5  406.04  4852.0  405.09  4874.3  405.77
  4883.0  403.97  4888.5  405.45  4916.9  405.35  4957.1  403.54  4962.6  405.81
  5001.9  406.04  5007.2  404.07  5056.1  405.68  5070.4  405.38  5097.3  401.84
  5117.4  400.95  5262.4  401.64  5508.3  404.00  5884.6  404.43  6114.9  406.14
#Mann=4,-1,0
  3911.7     0.1       0  4749.2    0.07       0  4755.2     0.1       0
  5262.4    0.05       0
Bank Sta=4749.2,4755.2
Exp/Cntr=0.3,0.1

Type RM Length L Ch R = 1,77,0,0,0
BEGIN DESCRIPTION:
UNT 018 IN LACR 1.0
END DESCRIPTION:
XS GIS Cut Line= 5
      2179107.19     13219522.36      2178999.46     13218606.64
      2178831.52     13218508.41      2178587.53     13218498.90
      2177595.69     13218651.01
#Sta/Elev= 30
  3739.5  405.51  3785.3  404.04  3966.6  401.90  3986.7  402.66  4033.3  401.54
  4198.1  400.69  4218.3  401.31  4248.5  400.36  4490.1  399.41  4560.6  397.77
  4621.0  398.13  4713.2  396.95  4860.5  397.67  4970.0  399.90  4990.0  398.72
  5000.0  395.57  5007.0  395.14  5009.8  394.64  5013.0  395.14  5040.0  396.46
  5050.0  399.28  5140.5  398.62  5185.9  399.93  5191.1  399.18  5250.5  399.74
  5464.3  403.05  5605.9  403.05  5649.5  403.94  5844.5  403.54  6103.7  405.35
#Mann=4,-1,0
  3739.5     0.1       0  5007.0    0.07       0  5013.0     0.1       0
  5250.5    0.05       0
Bank Sta=5007,5013
Exp/Cntr=0.3,0.1

Chan Stop Cuts=-1