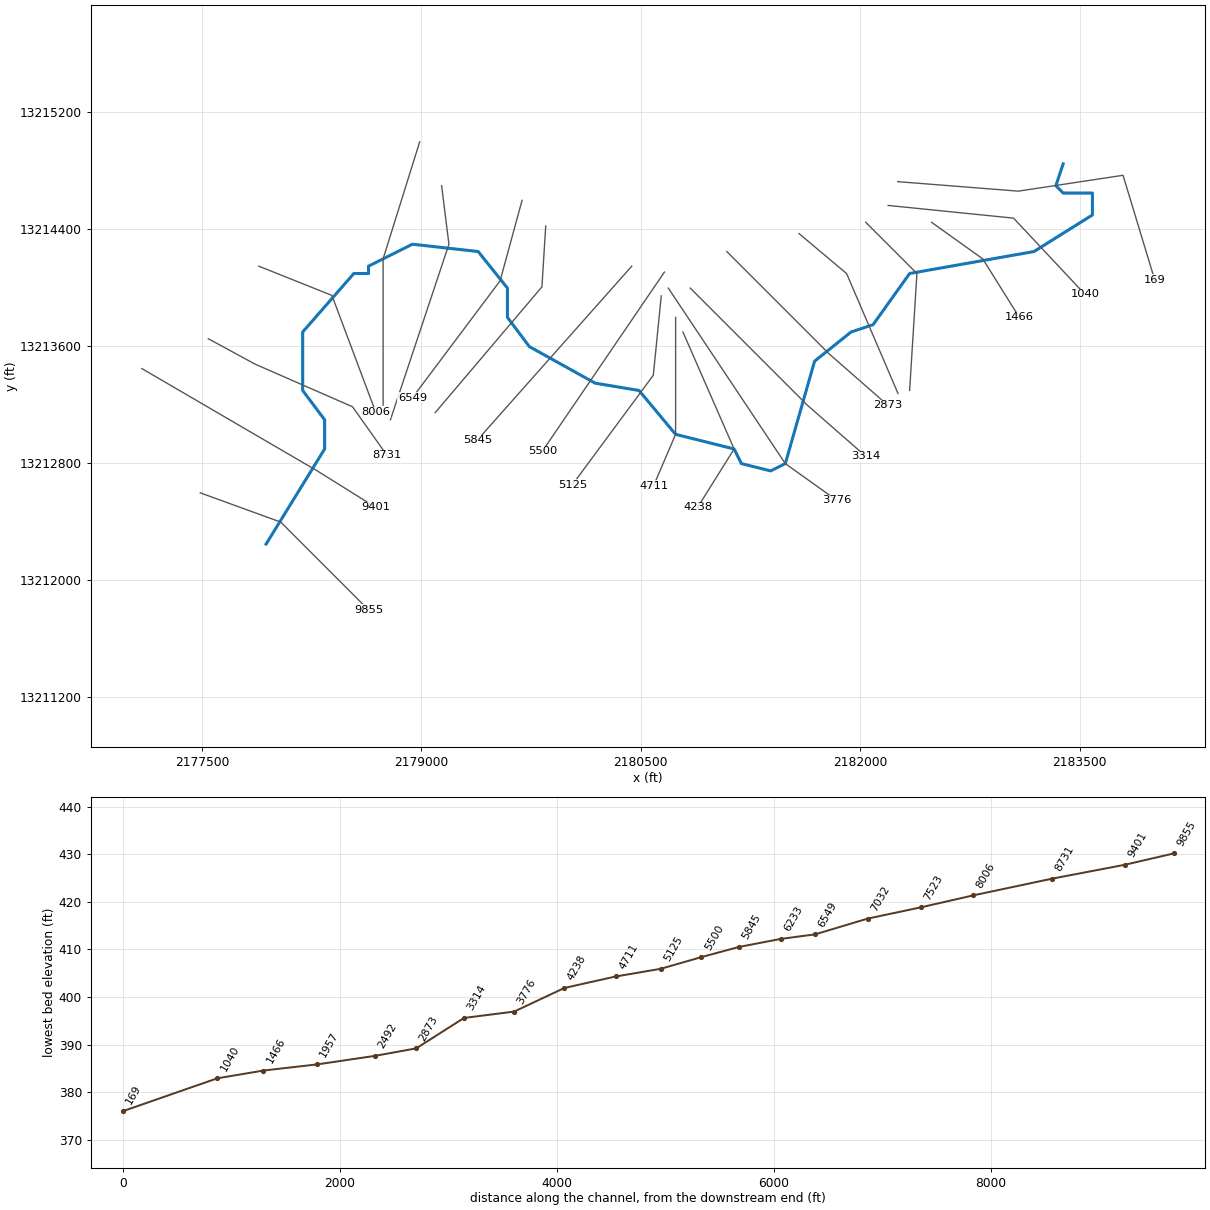
--- UNT 019 IN LACR.prj (project) ---

Proj Title=UNT 019 IN LACR Base Level Engineering
Current Plan=p01
Default Exp/Contr=0.3,0.1
English Units
Geom File=g01
Flow File=f01
Plan File=p01
BEGIN DESCRIPTION:
UNT 019 IN LACR
END DESCRIPTION:

--- UNT 019 IN LACR.p01 (plan) ---

Plan Title=Multiple Run
Short Identifier=Multiple
Geom File=g01
Flow File=f01
Subcritical Flow
K Sum by GR= 0
Std Step Tol= 0.01
Critical Tol= 0.01
Num of Std Step Trials= 20
Max Error Tol= 0.3
Flow Tol Ratio= 0.001
Split Flow NTrial= 30
Split Flow Tol= 0.02
Split Flow Ratio= 0.02
Log Output Level= 0
Friction Slope Method= 1
Unsteady Friction Slope Method= 2
Unsteady Bridges Friction Slope Method= 1
Parabolic Critical Depth
Global Vel Dist=  1 , 1 , 1
Global Log Level= 0
CheckData=True
Encroach Param= -1, 0, 0, 0
BEGIN DESCRIPTION:
Multiple Run
END DESCRIPTION:

--- UNT 019 IN LACR.f01 (steady flow) ---

Flow Title=Multiple
Number of Profiles=7
Profile Names=10-year,25-year,50-year,1pct_min,100-year,1pct_plu,500-year
River Rch & RM= UNT 019 IN LACR,Reach-1,9855
     191     266     329     299     405     547     622
River Rch & RM= UNT 019 IN LACR,Reach-1,9401
     218     304     376     342     463     626     713
River Rch & RM= UNT 019 IN LACR,Reach-1,5500
     270     381     475     435     588     795     918
Boundary for River Rch & Prof#=UNT 019 IN LACR,Reach-1,1
Up Type=0
Dn Type=3
Dn Slope=0.005
Boundary for River Rch & Prof#=UNT 019 IN LACR,Reach-1,2
Up Type=0
Dn Type=3
Dn Slope=0.005
Boundary for River Rch & Prof#=UNT 019 IN LACR,Reach-1,3
Up Type=0
Dn Type=3
Dn Slope=0.005
Boundary for River Rch & Prof#=UNT 019 IN LACR,Reach-1,4
Up Type=0
Dn Type=3
Dn Slope=0.005
Boundary for River Rch & Prof#=UNT 019 IN LACR,Reach-1,5
Up Type=0
Dn Type=3
Dn Slope=0.005
Boundary for River Rch & Prof#=UNT 019 IN LACR,Reach-1,6
Up Type=0
Dn Type=3
Dn Slope=0.005
Boundary for River Rch & Prof#=UNT 019 IN LACR,Reach-1,7
Up Type=0
Dn Type=3
Dn Slope=0.005

--- UNT 019 IN LACR.g01 (geometry) ---

Geom Title=Existing Conditions

River Reach=UNT 019 IN LACR,Reach-1
Reach XY= 30
      2177937.72     13212246.85      2178337.72     13212896.85
      2178337.72     13213096.85      2178187.72     13213296.86
      2178187.72     13213696.85      2178537.72     13214096.85
      2178637.72     13214096.85      2178637.72     13214146.86
      2178937.72     13214296.86      2179387.72     13214246.85
      2179587.72     13213996.85      2179587.72     13213796.86
      2179737.72     13213596.85      2180187.72     13213346.85
      2180487.72     13213296.86      2180737.72     13212996.86
      2181137.72     13212896.85      2181187.72     13212796.85
      2181387.72     13212746.85      2181487.72     13212796.85
      2181687.72     13213496.86      2181937.72     13213696.85
      2182087.72     13213746.85      2182337.72     13214096.85
      2183187.72     13214246.85      2183587.72     13214496.85
      2183587.72     13214646.85      2183387.72     13214646.85
      2183337.72     13214696.85      2183387.72     13214846.85

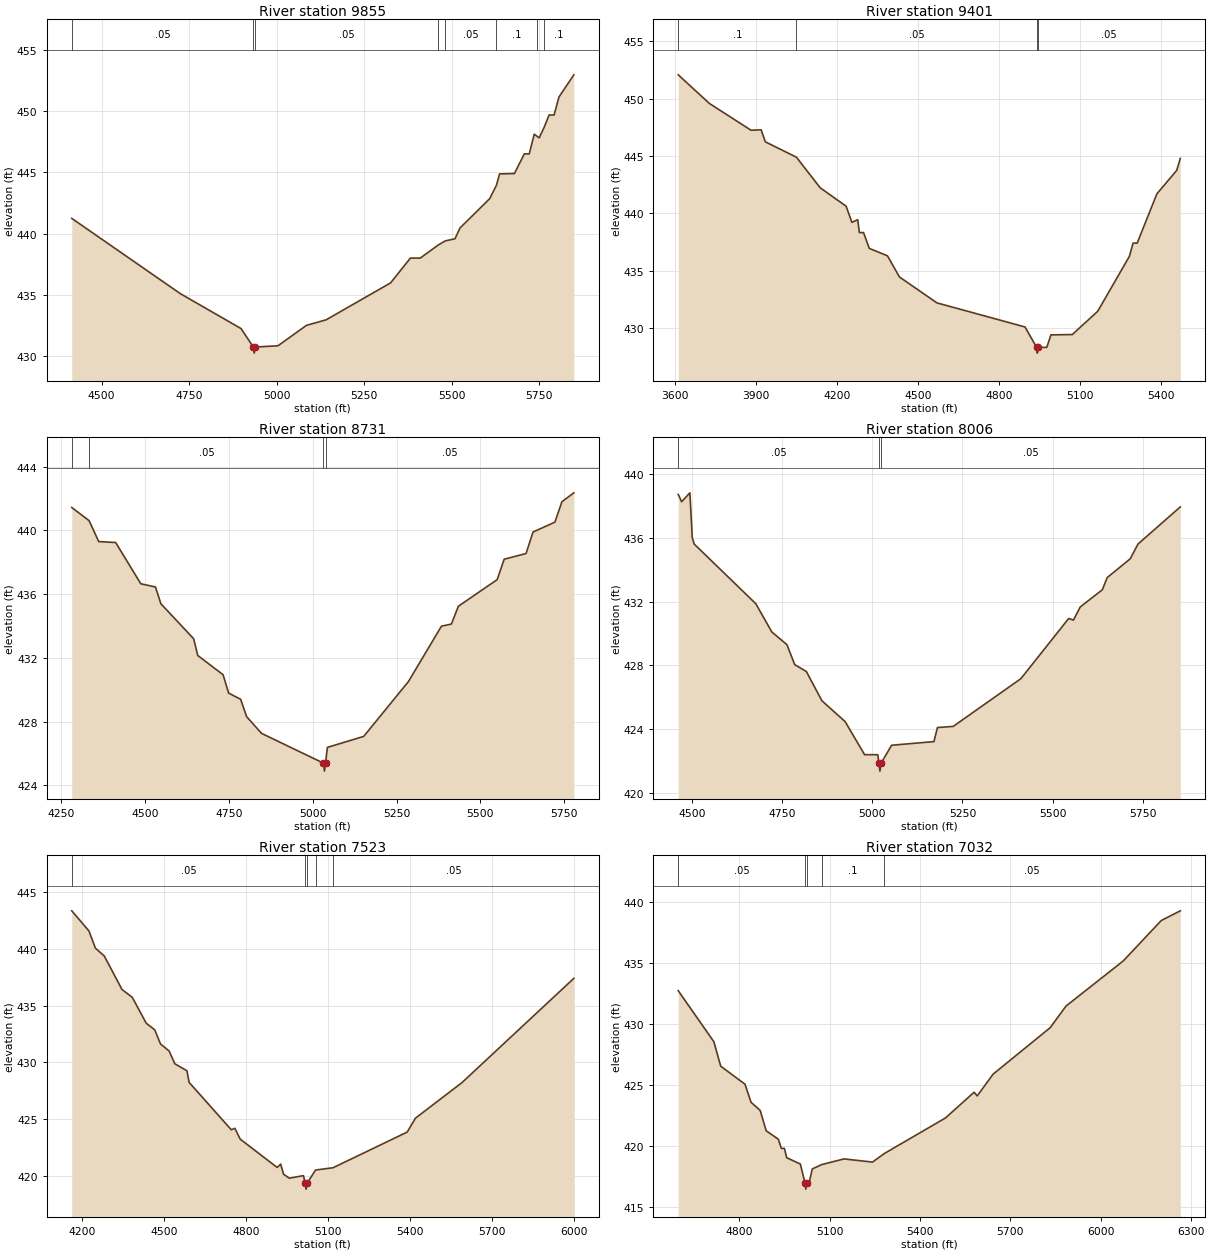
Type RM Length L Ch R = 1,9855,454,454,454
BEGIN DESCRIPTION:
UNT 019 IN LACR 19.0
END DESCRIPTION:
XS GIS Cut Line= 3
      2177487.75     13212596.84      2178037.72     13212396.85
      2178637.70     13211796.87
#Sta/Elev= 30
  4414.8  441.24  4725.3  435.07  4898.2  432.22  4933.2  430.71  4935.9  430.21
  4939.2  430.71  5003.5  430.81  5084.9  432.48  5141.4  432.94  5325.3  435.96
  5381.8  437.99  5410.1  437.99  5461.8  439.07  5481.7  439.40  5509.1  439.57
  5523.3  440.45  5608.1  442.85  5627.6  443.96  5636.4  444.88  5678.8  444.91
  5707.1  446.52  5721.2  446.52  5735.4  448.13  5742.5  447.98  5749.5  447.83
  5763.2  448.66  5777.8  449.70  5792.0  449.70  5806.1  451.18  5848.5  452.99
#Mann=8,-1,0
  4414.8    0.05       0  4933.2    0.03       0  4939.2    0.05       0
  5461.8     0.1       0  5481.7    0.05       0  5627.6     0.1       0
  5742.5    0.08       0  5763.2     0.1       0
Bank Sta=4933.2,4939.2
Exp/Cntr=0.3,0.1

Type RM Length L Ch R = 1,9401,670,670,670
BEGIN DESCRIPTION:
UNT 019 IN LACR 18.0
END DESCRIPTION:
XS GIS Cut Line= 3
      2177087.76     13213446.83      2178287.72     13212746.85
      2178687.72     13212496.85
#Sta/Elev= 30
  3610.8  452.07  3726.5  449.57  3880.7  447.24  3918.0  447.28  3933.7  446.23
  4048.8  444.89  4137.1  442.22  4233.0  440.62  4254.5  439.21  4276.0  439.44
  4282.2  438.32  4297.5  438.32  4319.0  436.94  4386.4  436.29  4430.7  434.45
  4569.6  432.19  4896.2  430.09  4939.1  428.31  4941.9  427.81  4945.1  428.31
  4976.8  428.31  4992.1  429.40  5071.3  429.43  5165.7  431.46  5283.0  436.25
  5296.6  437.40  5311.9  437.40  5385.0  441.70  5458.1  443.73  5471.7  444.78
#Mann=4,-1,0
  3610.8     0.1       0  4048.8    0.05       0  4939.1    0.03       0
  4945.1    0.05       0
Bank Sta=4939.1,4945.1
Exp/Cntr=0.3,0.1

Type RM Length L Ch R = 1,8731,725,725,725
BEGIN DESCRIPTION:
UNT 019 IN LACR 17.0
END DESCRIPTION:
XS GIS Cut Line= 4
      2177542.65     13213650.70      2177862.13     13213477.07
      2178528.79     13213185.40      2178763.82     13212853.59
#Sta/Elev= 30
  4281.0  441.44  4332.8  440.61  4361.5  439.30  4412.0  439.24  4487.0  436.65
  4530.7  436.45  4546.8  435.40  4644.6  433.20  4656.9  432.15  4732.5  430.94
  4749.0  429.79  4784.8  429.40  4802.7  428.31  4847.2  427.26  5032.0  425.39
  5034.8  424.89  5038.0  425.39  5043.7  426.38  5152.0  427.07  5285.3  430.51
  5384.0  433.99  5413.5  434.12  5434.4  435.24  5550.1  436.91  5571.0  438.19
  5636.3  438.55  5657.2  439.90  5722.4  440.52  5743.3  441.80  5778.9  442.36
#Mann=4,-1,0
  4281.0     0.1       0  4332.8    0.05       0  5032.0    0.03       0
  5038.0    0.05       0
Bank Sta=5032,5038
Exp/Cntr=0.3,0.1

Type RM Length L Ch R = 1,8006,483,483,483
BEGIN DESCRIPTION:
UNT 019 IN LACR 16.0
END DESCRIPTION:
XS GIS Cut Line= 3
      2177887.74     13214146.85      2178387.72     13213946.85
      2178687.72     13213146.86
#Sta/Elev= 30
  4461.5  438.71  4470.9  438.25  4493.8  438.81  4500.5  435.99  4505.9  435.60
  4676.9  431.86  4721.3  430.09  4763.1  429.30  4784.6  428.05  4816.9  427.62
  4860.0  425.79  4924.6  424.48  4978.5  422.41  5015.1  422.41  5018.4  421.88
  5021.1  421.38  5024.4  421.88  5053.4  423.00  5170.9  423.23  5180.7  424.11
  5224.3  424.18  5412.1  427.17  5544.7  430.94  5558.0  430.84  5576.7  431.66
  5638.1  432.74  5651.5  433.50  5715.6  434.68  5736.9  435.60  5854.4  437.93
#Mann=3,-1,0
  4461.5    0.05       0  5018.4    0.03       0  5024.4    0.05       0
Bank Sta=5018.4,5024.4
Exp/Cntr=0.3,0.1

Type RM Length L Ch R = 1,7523,491,491,491
BEGIN DESCRIPTION:
UNT 019 IN LACR 15.0
END DESCRIPTION:
XS GIS Cut Line= 3
      2178987.73     13214996.90      2178737.72     13214196.85
      2178737.72     13213196.85
#Sta/Elev= 30
  4161.8  443.34  4224.7  441.57  4248.3  440.06  4280.8  439.37  4345.7  436.42
  4383.4  435.73  4434.2  433.46  4465.7  432.87  4486.6  431.63  4518.6  431.00
  4539.0  429.89  4583.5  429.27  4591.4  428.25  4745.9  424.08  4759.0  424.21
  4778.4  423.26  4913.6  420.77  4926.7  421.06  4937.1  420.18  4958.1  419.82
  5010.0  420.05  5017.0  419.36  5019.8  418.86  5023.0  419.36  5054.3  420.54
  5118.3  420.74  5390.0  423.88  5420.0  425.10  5590.0  428.22  6000.0  437.40
#Mann=5,-1,0
  4161.8    0.05       0  5017.0    0.03       0  5023.0    0.05       0
  5054.3     0.1       0  5118.3    0.05       0
Bank Sta=5017,5023
Exp/Cntr=0.3,0.1

Type RM Length L Ch R = 1,7032,483,483,483
BEGIN DESCRIPTION:
UNT 019 IN LACR 14.0
END DESCRIPTION:
XS GIS Cut Line= 3
      2179137.72     13214696.84      2179187.72     13214296.86
      2178787.72     13213096.87
#Sta/Elev= 30
  4596.9  432.71  4715.3  428.54  4738.0  426.54  4818.6  425.07  4838.8  423.59
  4869.0  422.93  4889.1  421.26  4929.5  420.57  4939.5  419.82  4949.6  419.82
  4957.2  419.06  5002.6  418.54  5018.1  416.99  5020.8  416.49  5024.1  416.99
  5031.6  416.99  5042.2  418.14  5074.2  418.50  5147.6  418.96  5242.4  418.70
  5281.5  419.40  5484.9  422.31  5579.8  424.41  5590.3  424.11  5643.0  425.89
  5832.7  429.69  5885.4  431.46  6075.2  435.14  6201.7  438.45  6264.9  439.24
#Mann=5,-1,0
  4596.9    0.05       0  5018.1    0.03       0  5024.1    0.05       0
  5074.2     0.1       0  5281.5    0.05       0
Bank Sta=5018.1,5024.1
Exp/Cntr=0.3,0.1

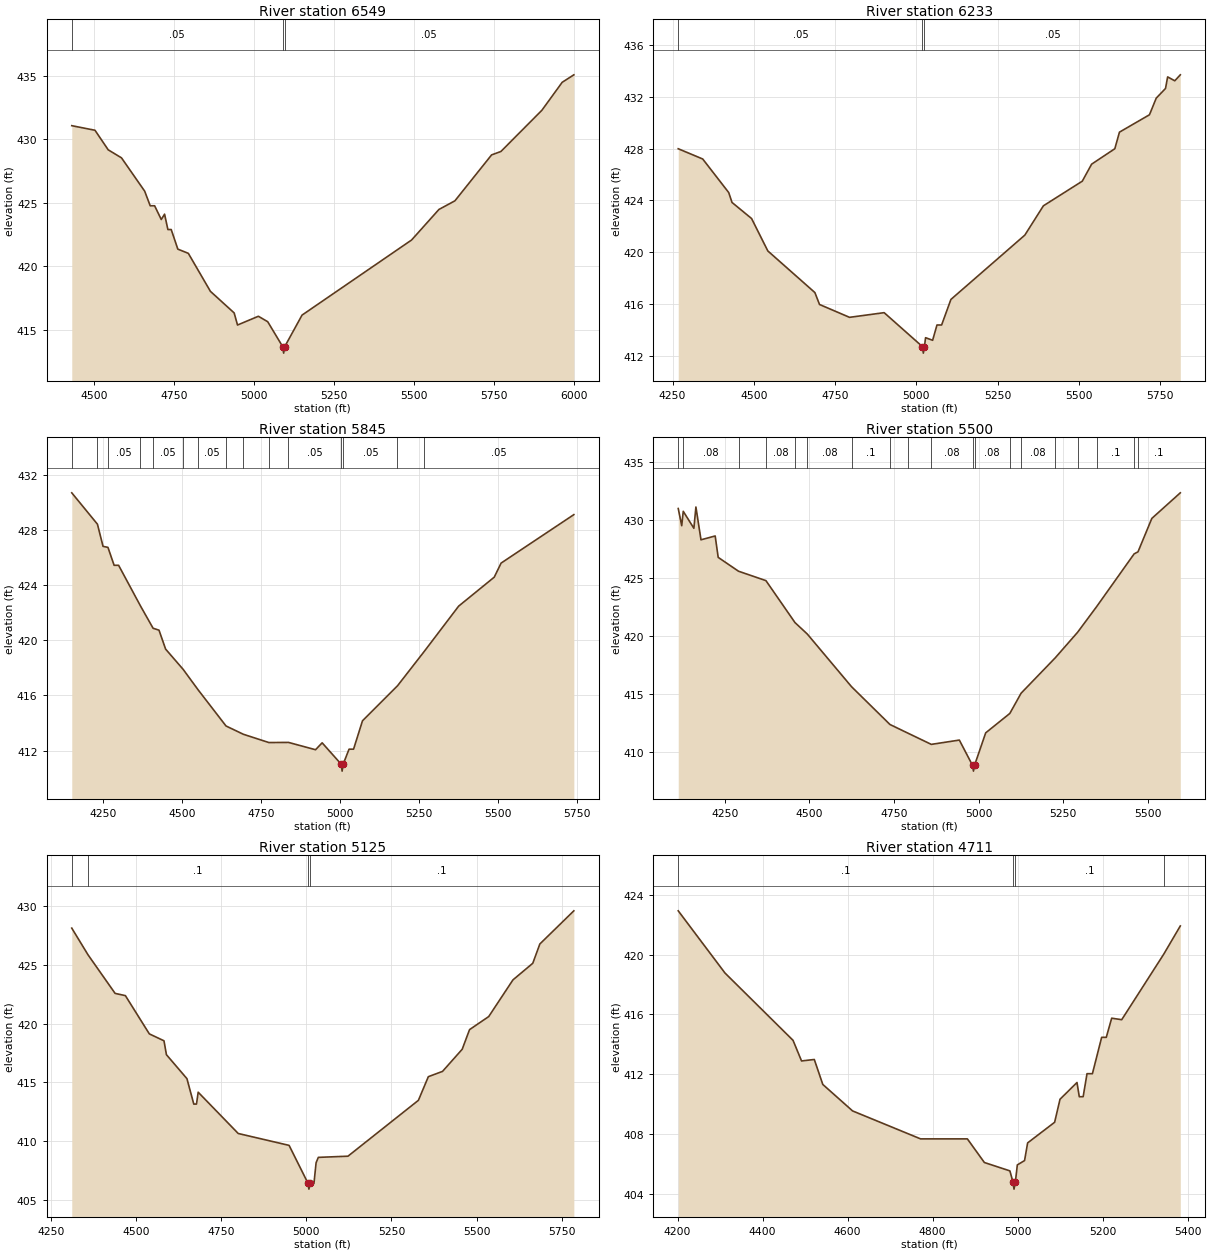
Type RM Length L Ch R = 1,6549,316,316,316
BEGIN DESCRIPTION:
UNT 019 IN LACR 13.0
END DESCRIPTION:
XS GIS Cut Line= 3
      2179687.72     13214596.87      2179537.72     13214046.85
      2178937.72     13213246.85
#Sta/Elev= 30
  4429.9  431.07  4502.5  430.71  4543.9  429.17  4585.4  428.54  4657.9  425.92
  4675.2  424.77  4689.0  424.77  4709.8  423.69  4720.1  424.11  4730.5  422.90
  4740.9  422.90  4761.6  421.36  4794.4  421.03  4863.5  418.04  4937.8  416.34
  4948.2  415.39  5013.5  416.08  5042.7  415.65  5089.7  413.68  5092.5  413.18
  5095.7  413.68  5150.0  416.17  5492.7  422.08  5578.1  424.48  5628.1  425.16
  5742.7  428.77  5771.9  429.04  5900.0  432.28  5963.5  434.48  6000.0  435.07
#Mann=3,-1,0
  4429.9    0.05       0  5089.7    0.03       0  5095.7    0.05       0
Bank Sta=5089.7,5095.7
Exp/Cntr=0.3,0.1

Type RM Length L Ch R = 1,6233,388,388,388
BEGIN DESCRIPTION:
Mapping XS bb10db74
END DESCRIPTION:
XS GIS Cut Line= 3
      2179849.60     13214421.97      2179823.56     13214005.26
      2179094.36     13213145.85
#Sta/Elev= 30
  4267.3  427.99  4342.6  427.20  4422.7  424.61  4432.7  423.85  4492.9  422.61
  4542.9  420.11  4687.7  416.90  4702.0  415.98  4794.3  414.99  4900.8  415.35
  5018.7  412.73  5021.4  412.23  5024.7  412.73  5028.2  413.42  5049.9  413.22
  5063.3  414.40  5077.6  414.40  5106.2  416.37  5333.6  421.33  5390.7  423.59
  5510.4  425.49  5539.0  426.80  5610.4  427.99  5624.7  429.27  5717.0  430.61
  5737.8  431.89  5766.4  432.64  5772.9  433.53  5794.9  433.23  5811.9  433.69
#Mann=3,-1,0
  4267.3    0.05       0  5018.7    0.03       0  5024.7    0.05       0
Bank Sta=5018.7,5024.7
Exp/Cntr=0.3,0.1

Type RM Length L Ch R = 1,5845,345,345,345
BEGIN DESCRIPTION:
UNT 019 IN LACR 12.0
END DESCRIPTION:
XS GIS Cut Line= 2
      2180437.70     13214146.83      2179381.74     13212957.31
#Sta/Elev= 30
  4150.0  430.68  4231.3  428.41  4249.1  426.80  4264.6  426.73  4284.2  425.43
  4298.4  425.43  4367.1  422.51  4407.6  420.87  4426.4  420.73  4447.3  419.36
  4502.9  417.89  4550.6  416.40  4638.7  413.79  4693.6  413.19  4774.5  412.59
  4836.6  412.60  4922.3  412.07  4943.2  412.57  5003.7  411.02  5006.5  410.52
  5009.7  411.02  5028.5  412.11  5042.7  412.11  5071.1  414.17  5181.9  416.70
  5265.6  419.16  5375.6  422.47  5488.4  424.57  5510.2  425.59  5740.6  429.10
#Mann=15,-1,0
  4150.0    0.05       0  4231.3    0.08       0  4264.6    0.05       0
  4367.1    0.08       0  4407.6    0.05       0  4502.9    0.08       0
  4550.6    0.05       0  4638.7    0.08       0  4693.6    0.05       0
  4774.5    0.08       0  4836.6    0.05       0  5003.7    0.03       0
  5009.7    0.05       0  5181.9    0.08       0  5265.6    0.05       0
Bank Sta=5003.7,5009.7
Exp/Cntr=0.3,0.1

Type RM Length L Ch R = 1,5500,375,375,375
BEGIN DESCRIPTION:
UNT 019 IN LACR 11.0
END DESCRIPTION:
XS GIS Cut Line= 2
      2180661.18     13214106.43      2179826.20     13212881.07
#Sta/Elev= 30
  4112.6  430.97  4122.9  429.49  4127.4  430.73  4158.8  429.27  4164.8  431.10
  4179.8  428.28  4221.7  428.61  4230.6  426.77  4290.6  425.58  4371.6  424.77
  4457.5  421.16  4493.7  420.18  4624.4  415.65  4737.9  412.40  4791.3  411.65
  4860.0  410.69  4942.8  411.06  4981.7  408.89  4984.5  408.39  4987.7  408.89
  5020.6  411.68  5091.9  413.35  5125.2  415.09  5226.3  418.14  5292.1  420.33
  5348.4  422.54  5459.0  427.07  5470.5  427.25  5511.3  430.12  5595.4  432.32
#Mann=19,-1,0
  4112.6     0.1       0  4127.4    0.08       0  4290.6     0.1       0
  4371.6    0.08       0  4457.5     0.1       0  4493.7    0.08       0
  4624.4     0.1       0  4737.9    0.08       0  4791.3     0.1       0
  4860.0    0.08       0  4981.7    0.07       0  4987.7    0.08       0
  5091.9     0.1       0  5125.2    0.08       0  5226.3     0.1       0
  5292.1    0.08       0  5348.4     0.1       0  5459.0    0.08       0
  5470.5     0.1       0
Bank Sta=4981.7,4987.7
Exp/Cntr=0.3,0.1

Type RM Length L Ch R = 1,5125,414,414,414
BEGIN DESCRIPTION:
UNT 019 IN LACR 10.0
END DESCRIPTION:
XS GIS Cut Line= 3
      2180639.47     13213943.65      2180585.22     13213401.11
      2180032.28     13212653.02
#Sta/Elev= 30
  4310.5  428.12  4358.3  425.85  4437.9  422.57  4468.1  422.38  4538.4  419.13
  4581.5  418.54  4588.7  417.36  4649.0  415.32  4669.1  413.16  4677.0  413.16
  4682.0  414.17  4799.7  410.66  4949.2  409.65  5004.7  406.43  5007.4  405.93
  5010.7  406.43  5022.3  406.43  5028.5  408.17  5035.1  408.63  5122.2  408.73
  5329.2  413.48  5358.4  415.49  5400.1  415.94  5457.9  417.82  5479.5  419.49
  5535.8  420.60  5607.1  423.72  5665.3  425.13  5686.1  426.77  5786.0  429.59
#Mann=4,-1,0
  4310.5    0.08       0  4358.3     0.1       0  5004.7    0.07       0
  5010.7     0.1       0
Bank Sta=5004.7,5010.7
Exp/Cntr=0.3,0.1

Type RM Length L Ch R = 1,4711,473,473,473
BEGIN DESCRIPTION:
UNT 019 IN LACR 9.0
END DESCRIPTION:
XS GIS Cut Line= 3
      2180737.72     13213796.87      2180737.72     13212996.86
      2180587.72     13212646.86
#Sta/Elev= 30
  4201.7  422.93  4311.7  418.77  4471.7  414.27  4491.7  412.89  4521.7  412.99
  4541.7  411.32  4611.7  409.55  4771.7  407.68  4881.7  407.68  4921.7  406.10
  4981.7  405.54  4988.7  404.82  4991.4  404.32  4994.7  404.82  4999.2  405.94
  5016.2  406.23  5023.4  407.41  5086.9  408.79  5099.6  410.33  5139.5  411.45
  5144.9  410.50  5154.0  410.50  5163.1  412.04  5175.8  412.04  5197.5  414.47
  5208.4  414.47  5221.1  415.75  5244.7  415.65  5343.3  420.02  5382.5  421.92
#Mann=4,-1,0
  4201.7     0.1       0  4988.7    0.07       0  4994.7     0.1       0
  5343.3    0.05       0
Bank Sta=4988.7,4994.7
Exp/Cntr=0.3,0.1

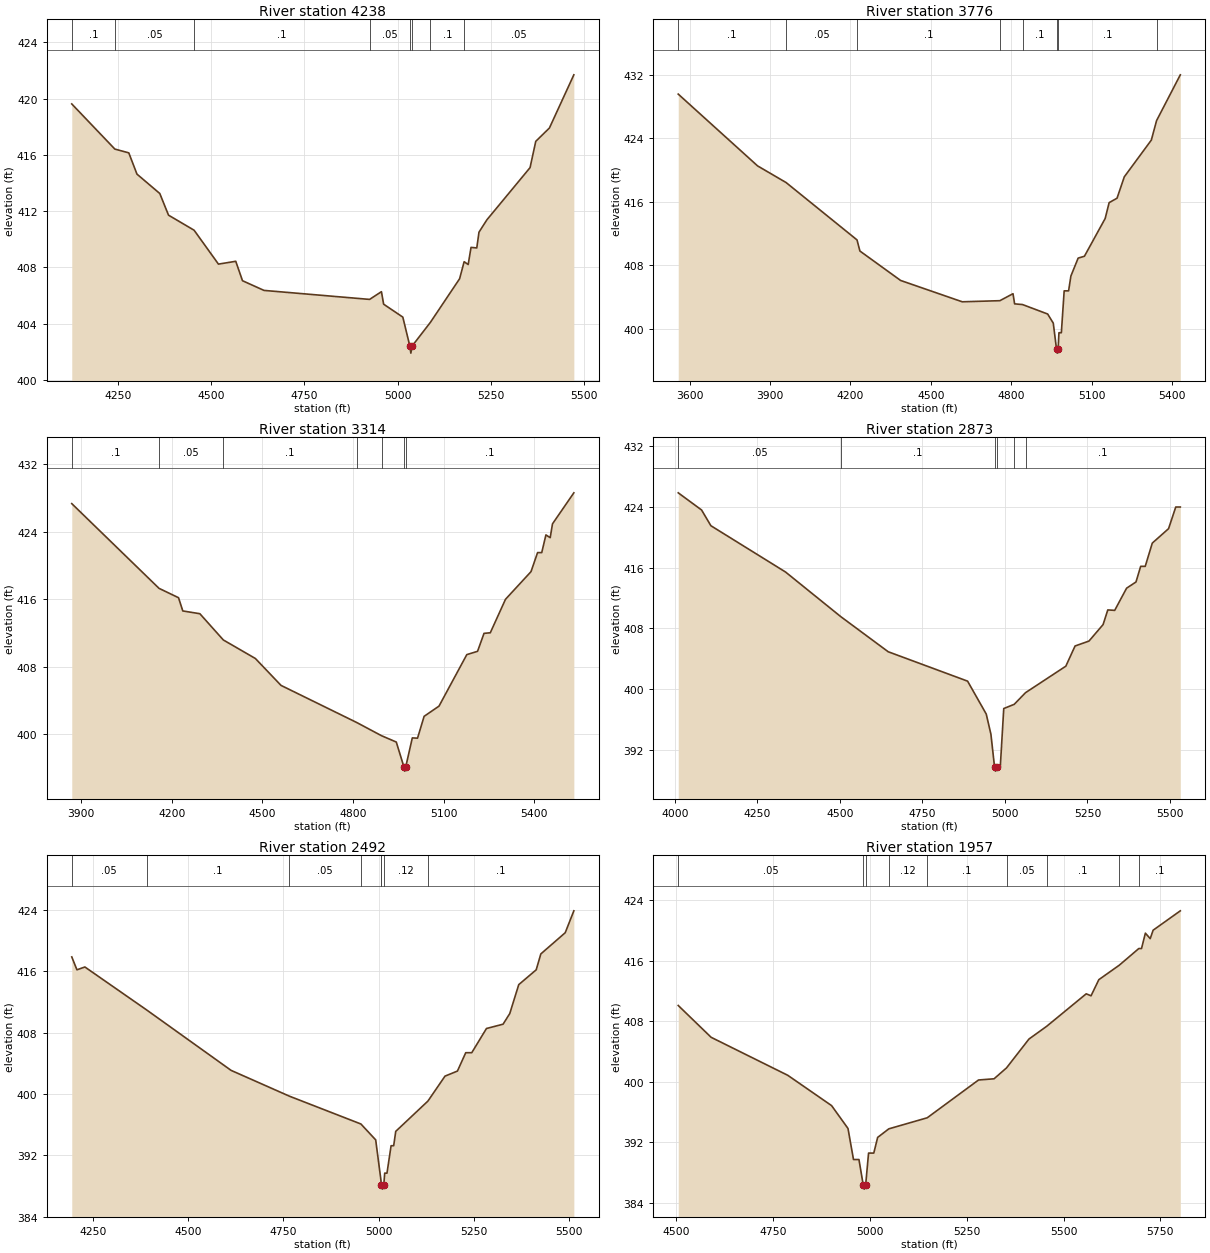
Type RM Length L Ch R = 1,4238,462,462,462
BEGIN DESCRIPTION:
UNT 019 IN LACR 8.0
END DESCRIPTION:
XS GIS Cut Line= 3
      2180787.73     13213696.84      2181137.72     13212896.85
      2180887.72     13212496.85
#Sta/Elev= 30
  4126.8  419.62  4242.2  416.41  4279.6  416.14  4301.4  414.63  4362.6  413.25
  4386.0  411.71  4454.5  410.64  4519.7  408.23  4566.1  408.43  4584.1  407.05
  4641.7  406.36  4924.6  405.72  4956.3  406.27  4962.2  405.38  5013.6  404.46
  5032.4  402.40  5035.1  401.90  5038.4  402.40  5087.5  404.09  5165.7  407.19
  5177.8  408.40  5188.7  408.20  5196.3  409.42  5211.7  409.38  5217.6  410.50
  5238.8  411.38  5354.4  415.09  5369.7  416.96  5406.3  417.91  5471.7  421.69
#Mann=8,-1,0
  4126.8     0.1       0  4242.2    0.05       0  4454.5     0.1       0
  4924.6    0.05       0  5032.4    0.03       0  5038.4    0.05       0
  5087.5     0.1       0  5177.8    0.05       0
Bank Sta=5032.4,5038.4
Exp/Cntr=0.3,0.1

Type RM Length L Ch R = 1,3776,462,462,462
BEGIN DESCRIPTION:
UNT 019 IN LACR 7.0
END DESCRIPTION:
XS GIS Cut Line= 3
      2180687.73     13213996.84      2181487.72     13212796.85
      2181837.71     13212546.86
#Sta/Elev= 30
  3557.8  429.59  3853.7  420.54  3960.1  418.44  4224.5  411.21  4235.3  409.81
  4387.1  406.10  4616.9  403.41  4757.2  403.55  4806.2  404.43  4812.2  403.15
  4841.9  403.06  4935.4  401.87  4956.4  400.72  4968.5  397.44  4971.2  396.94
  4974.5  397.44  4977.5  399.51  4986.5  399.51  4997.0  404.79  5013.5  404.79
  5022.1  406.66  5049.2  408.92  5072.5  409.15  5149.9  413.91  5164.7  415.91
  5194.2  416.47  5221.2  419.16  5322.0  423.79  5341.6  426.25  5430.1  432.02
#Mann=8,-1,0
  3557.8     0.1       0  3960.1    0.05       0  4224.5     0.1       0
  4757.2    0.05       0  4841.9     0.1       0  4968.5    0.07       0
  4974.5     0.1       0  5341.6    0.05       0
Bank Sta=4968.5,4974.5
Exp/Cntr=0.3,0.1

Type RM Length L Ch R = 1,3314,441,441,441
BEGIN DESCRIPTION:
UNT 019 IN LACR 6.0
END DESCRIPTION:
XS GIS Cut Line= 3
      2180837.70     13213996.88      2181637.72     13213196.85
      2182037.72     13212846.86
#Sta/Elev= 30
  3868.6  427.33  4157.6  417.28  4222.2  416.17  4236.3  414.60  4292.9  414.27
  4370.5  411.16  4476.7  408.96  4561.6  405.77  4812.2  401.37  4894.6  399.80
  4943.4  399.05  4968.7  396.10  4971.5  395.60  4974.7  396.10  4996.5  399.54
  5013.8  399.51  5035.6  402.10  5084.9  403.31  5177.0  409.42  5212.6  409.81
  5234.0  411.94  5254.8  412.01  5305.1  415.98  5389.6  419.26  5411.4  421.52
  5425.2  421.52  5439.0  423.62  5453.2  423.29  5460.8  424.93  5531.5  428.61
#Mann=7,-1,0
  3868.6     0.1       0  4157.6    0.05       0  4370.5     0.1       0
  4812.2    0.05       0  4894.6     0.1       0  4968.7    0.07       0
  4974.7     0.1       0
Bank Sta=4968.7,4974.7
Exp/Cntr=0.3,0.1

Type RM Length L Ch R = 1,2873,381,381,381
BEGIN DESCRIPTION:
UNT 019 IN LACR 5.0
END DESCRIPTION:
XS GIS Cut Line= 3
      2181087.76     13214246.82      2181787.72     13213546.85
      2182187.72     13213196.86
#Sta/Elev= 30
  4010.1  425.85  4080.8  423.59  4109.0  421.52  4335.3  415.42  4503.1  409.53
  4646.4  404.92  4886.9  401.05  4943.4  396.72  4957.6  394.06  4968.7  389.70
  4971.5  389.20  4974.7  389.70  4985.9  389.70  4996.5  397.44  5028.3  398.00
  5062.4  399.53  5184.6  403.02  5212.6  405.68  5254.8  406.33  5297.5  408.50
  5311.8  410.43  5332.7  410.37  5368.7  413.29  5397.2  414.11  5411.4  416.17
  5425.2  416.17  5446.6  419.23  5495.9  421.13  5517.7  423.98  5531.5  423.98
#Mann=6,-1,0
  4010.1    0.05       0  4503.1     0.1       0  4968.7    0.07       0
  4974.7     0.1       0  5028.3    0.12       0  5062.4     0.1       0
Bank Sta=4968.7,4974.7
Exp/Cntr=0.3,0.1

Type RM Length L Ch R = 1,2492,535,535,535
BEGIN DESCRIPTION:
UNT 019 IN LACR 4.0
END DESCRIPTION:
XS GIS Cut Line= 3
      2181581.39     13214369.83      2181906.89     13214096.40
      2182258.46     13213276.07
#Sta/Elev= 30
  4194.6  417.85  4208.2  416.17  4229.0  416.54  4391.0  410.95  4612.7  403.08
  4765.8  399.72  4953.4  396.10  4992.2  394.03  5005.5  388.96  5007.4  388.12
  5010.1  387.62  5013.4  388.12  5015.8  389.70  5021.8  389.70  5032.6  393.27
  5039.4  393.27  5044.8  395.14  5129.2  399.08  5174.1  402.33  5206.7  402.99
  5228.5  405.38  5244.3  405.38  5282.9  408.53  5326.4  409.09  5344.0  410.47
  5367.6  414.24  5413.4  416.17  5425.6  418.24  5489.6  421.00  5512.2  423.85
#Mann=8,-1,0
  4194.6    0.05       0  4391.0     0.1       0  4765.8    0.05       0
  4953.4     0.1       0  5005.5    0.12       0  5007.4    0.07       0
  5013.4    0.12       0  5129.2     0.1       0
Bank Sta=5007.4,5013.4
Exp/Cntr=0.3,0.1

Type RM Length L Ch R = 1,1957,491,491,491
BEGIN DESCRIPTION:
UNT 019 IN LACR 3.0
END DESCRIPTION:
XS GIS Cut Line= 3
      2182037.70     13214446.87      2182387.72     13214096.85
      2182337.72     13213296.82
#Sta/Elev= 30
  4505.0  410.07  4589.9  405.87  4787.9  400.85  4901.0  396.85  4943.4  393.83
  4957.6  389.73  4971.7  389.73  4982.9  386.32  4985.6  385.82  4988.9  386.32
  4996.5  390.58  5010.0  390.58  5020.0  392.65  5048.8  393.78  5148.0  395.24
  5280.5  400.23  5320.6  400.39  5352.8  401.83  5410.8  405.64  5456.5  407.32
  5558.6  411.61  5571.1  411.35  5591.2  413.48  5644.0  415.39  5694.4  417.59
  5701.4  417.59  5711.4  419.62  5723.9  418.90  5731.4  420.01  5801.6  422.57
#Mann=9,-1,0
  4505.0    0.05       0  4982.9    0.03       0  4988.9    0.05       0
  5048.8    0.12       0  5148.0     0.1       0  5352.8    0.05       0
  5456.5     0.1       0  5644.0    0.05       0  5694.4     0.1       0
Bank Sta=4982.9,4988.9
Exp/Cntr=0.3,0.1

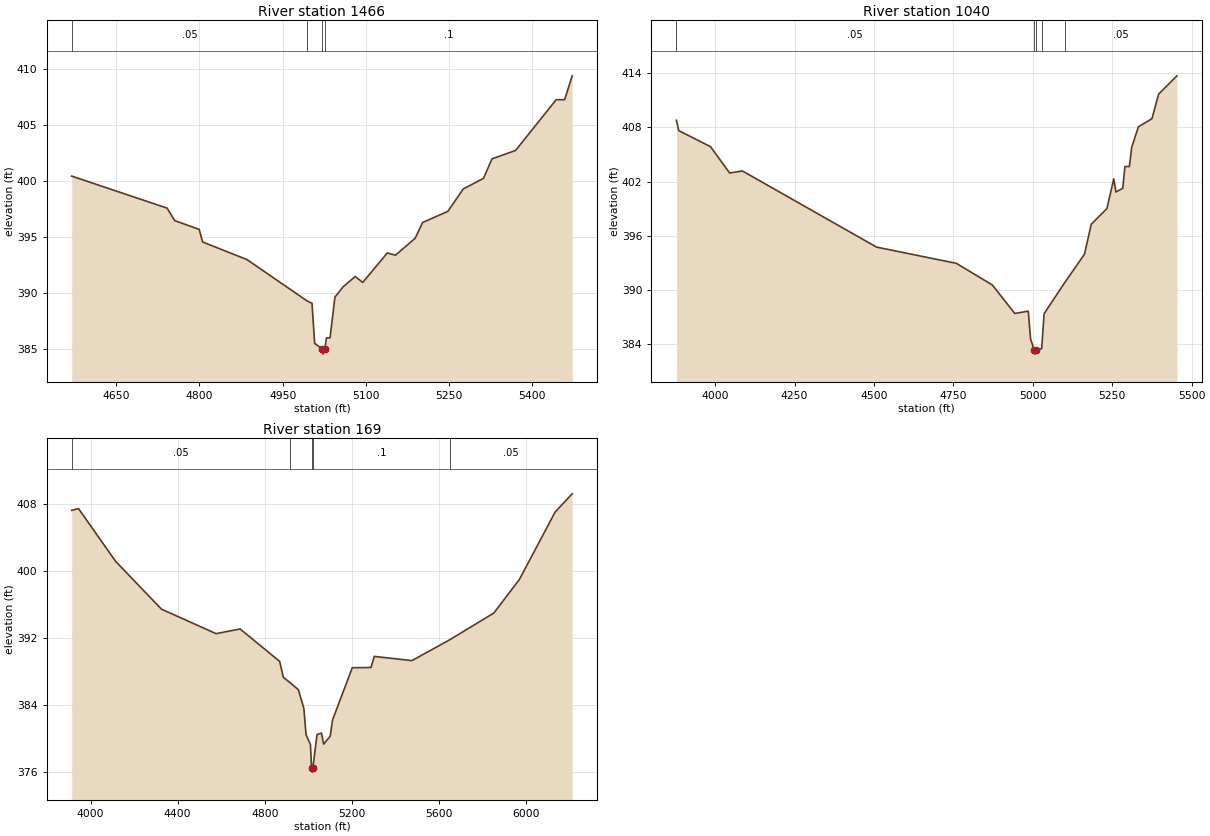
Type RM Length L Ch R = 1,1466,426,426,426
BEGIN DESCRIPTION:
UNT 019 IN LACR 2.0
END DESCRIPTION:
XS GIS Cut Line= 3
      2182487.73     13214446.85      2182837.72     13214196.85
      2183087.72     13213796.85
#Sta/Elev= 30
  4569.9  400.43  4741.9  397.57  4755.4  396.46  4799.7  395.67  4805.8  394.55
  4885.7  392.98  4994.0  389.29  5002.9  389.07  5007.7  385.50  5020.0  385.04
  5022.7  384.54  5026.0  385.04  5028.9  385.99  5035.4  385.99  5044.2  389.63
  5059.0  390.55  5080.8  391.47  5094.3  390.94  5138.6  393.57  5153.3  393.37
  5188.7  394.88  5202.2  396.29  5247.6  397.28  5275.4  399.28  5311.9  400.23
  5327.2  401.97  5369.7  402.72  5442.8  407.25  5458.1  407.25  5471.7  409.38
#Mann=4,-1,0
  4569.9    0.05       0  4994.0     0.1       0  5020.0    0.07       0
  5026.0     0.1       0
Bank Sta=5020,5026
Exp/Cntr=0.3,0.1

Type RM Length L Ch R = 1,1040,871,871,871
BEGIN DESCRIPTION:
Mapping XS 3cf9d76a
END DESCRIPTION:
XS GIS Cut Line= 3
      2182191.07     13214562.14      2183048.32     13214475.33
      2183536.63     13213954.47
#Sta/Elev= 30
  3878.1  408.79  3885.4  407.64  3985.3  405.87  4045.6  402.95  4085.8  403.18
  4508.0  394.75  4759.5  392.95  4872.8  390.55  4943.3  387.40  4985.7  387.66
  4993.0  384.58  5004.1  383.40  5006.9  382.90  5010.1  383.40  5027.9  383.50
  5035.5  387.37  5099.9  390.79  5162.6  393.96  5184.0  397.28  5233.3  399.02
  5254.8  402.30  5261.6  400.85  5283.1  401.25  5290.0  403.67  5304.1  403.67
  5311.4  405.81  5332.5  408.07  5375.0  408.96  5396.0  411.68  5453.7  413.71
#Mann=5,-1,0
  3878.1    0.05       0  5004.1    0.03       0  5010.1    0.05       0
  5027.9     0.1       0  5099.9    0.05       0
Bank Sta=5004.1,5010.1
Exp/Cntr=0.3,0.1

Type RM Length L Ch R = 1,169,0,0,0
BEGIN DESCRIPTION:
UNT 019 IN LACR 1.0
END DESCRIPTION:
XS GIS Cut Line= 4
      2182256.22     13214724.90      2183080.88     13214659.79
      2183797.02     13214768.30      2184014.02     13214052.20
#Sta/Elev= 30
  3913.0  407.25  3944.6  407.45  4115.1  401.15  4325.8  395.44  4576.6  392.52
  4686.9  393.08  4868.5  389.21  4885.6  387.30  4916.0  386.68  4954.4  385.83
  4979.8  383.60  4989.9  380.45  5010.1  379.27  5015.1  376.48  5017.8  375.98
  5021.1  376.48  5040.5  380.48  5060.7  380.64  5070.8  379.33  5101.1  380.28
  5111.3  382.19  5202.3  388.45  5288.1  388.48  5303.4  389.80  5476.5  389.30
  5650.7  391.80  5852.7  394.98  5969.9  398.98  6134.5  407.05  6212.8  409.22
#Mann=5,-1,0
  3913.0    0.05       0  4916.0     0.1       0  5015.1    0.07       0
  5021.1     0.1       0  5650.7    0.05       0
Bank Sta=5015.1,5021.1
Exp/Cntr=0.3,0.1

Chan Stop Cuts=-1