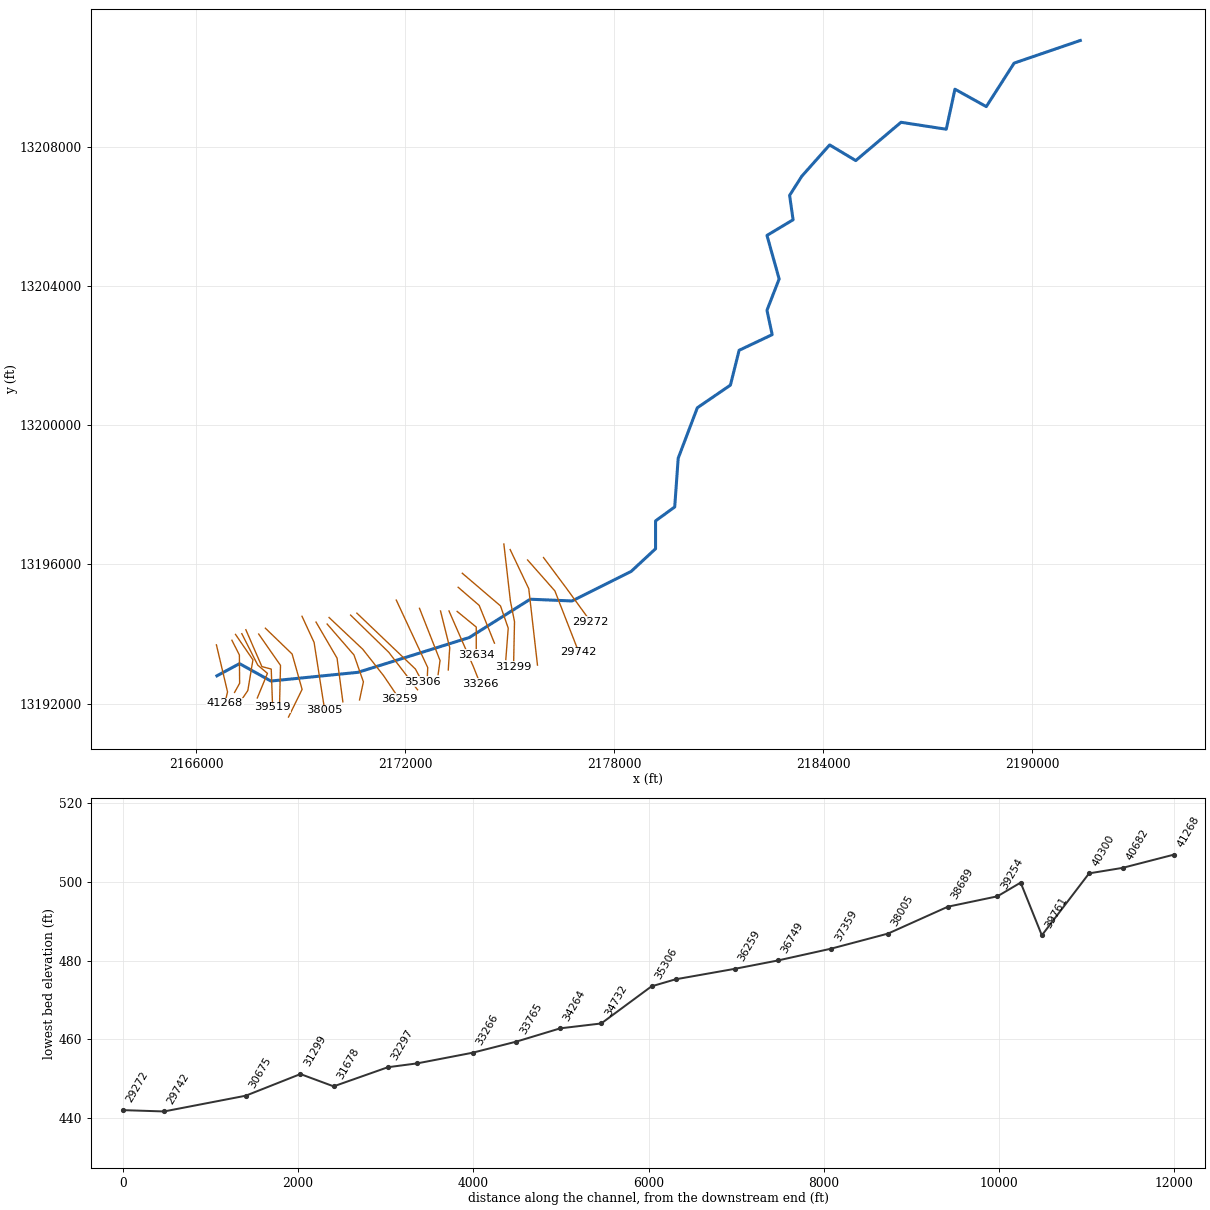
--- UNT 020 IN LACR.prj (project) ---

Proj Title=UNT 020 IN LACR Base Level Engineering
Current Plan=p01
Default Exp/Contr=0.3,0.1
English Units
Geom File=g01
Flow File=f01
Plan File=p01
Y Axis Title=Elevation
X Axis Title(PF)=Main Channel Distance
X Axis Title(XS)=Station
BEGIN DESCRIPTION:
UNT 020 IN LACR
END DESCRIPTION:
DSS Export Rating Curves= 0
DSS Export Rating Curve Sorted= 0
DSS Export Volume Flow Curves= 0
DXF OffsetX= 0
DXF OffsetY= 0
DXF ScaleX= 1
DXF ScaleY= 10

--- UNT 020 IN LACR.p01 (plan) ---

Plan Title=Multiple Run
Short Identifier=Multiple
Geom File=g01
Flow File=f01
Subcritical Flow
K Sum by GR= 0
Std Step Tol= 0.01
Critical Tol= 0.01
Num of Std Step Trials= 20
Max Error Tol= 0.3
Flow Tol Ratio= 0.001
Split Flow NTrial= 30
Split Flow Tol= 0.02
Split Flow Ratio= 0.02
Log Output Level= 0
Friction Slope Method= 1
Unsteady Friction Slope Method= 2
Unsteady Bridges Friction Slope Method= 1
Parabolic Critical Depth
Global Vel Dist=  1 , 1 , 1
Global Log Level= 0
CheckData=True
Encroach Param= -1, 0, 0, 0
BEGIN DESCRIPTION:
Multiple Run
END DESCRIPTION:

--- UNT 020 IN LACR.f01 (steady flow) ---

Flow Title=Multiple
Program Version=4.10
Number of Profiles= 7
Profile Names=10-year,25-year,50-year,1pct_min,100-year,1pct_plu,500-year
River Rch & RM=UNT 020 IN LACR,Reach-1         ,41268
     337     485     612     568     768    1038    1229
River Rch & RM=UNT 020 IN LACR,Reach-1         ,35580
     429     624     793     741    1003    1356    1628
River Rch & RM=UNT 020 IN LACR,Reach-1         ,35306
     468     682     868     811    1097    1484    1784
River Rch & RM=UNT 020 IN LACR,Reach-1         ,33266
     468     682     868     811    1097    1484    1784
River Rch & RM=UNT 020 IN LACR,Reach-1         ,32634
     468     682     868     811    1097    1484    1784
River Rch & RM=UNT 020 IN LACR,Reach-1         ,31299
     608     896    1149    1082    1463    1978    2411
River Rch & RM=UNT 020 IN LACR,Reach-1         ,30675
     608     896    1149    1082    1463    1978    2411
River Rch & RM=UNT 020 IN LACR,Reach-1         ,29742
     700    1038    1337    1263    1708    2309    2835
River Rch & RM=UNT 020 IN LACR,Reach-1         ,28409
     810    1205    1556    1473    1992    2693    3320
River Rch & RM=UNT 020 IN LACR,Reach-1         ,27471
     810    1205    1556    1473    1992    2693    3320
River Rch & RM=UNT 020 IN LACR,Reach-1         ,26989
     810    1205    1556    1473    1992    2693    3320
River Rch & RM=UNT 020 IN LACR,Reach-1         ,22844
     860    1279    1650    1559    2109    2852    3506
River Rch & RM=UNT 020 IN LACR,Reach-1         ,16899
     881    1310    1690    1597    2160    2921    3590
River Rch & RM=UNT 020 IN LACR,Reach-1         ,15537
     881    1310    1690    1597    2160    2921    3590
River Rch & RM=UNT 020 IN LACR,Reach-1         ,14329
    1004    1496    1932    1828    2472    3343    4115
River Rch & RM=UNT 020 IN LACR,Reach-1         ,8472
    1049    1564    2021    1912    2586    3497    4308
River Rch & RM=UNT 020 IN LACR,Reach-1         ,4001
    1047    1558    2011    1901    2571    3477    4274
Boundary for River Rch & Prof#=UNT 020 IN LACR,Reach-1         , 1
Up Type= 0
Dn Type= 3
Dn Slope=0.0017
Boundary for River Rch & Prof#=UNT 020 IN LACR,Reach-1         , 2
Up Type= 0
Dn Type= 3
Dn Slope=0.0017
Boundary for River Rch & Prof#=UNT 020 IN LACR,Reach-1         , 3
Up Type= 0
Dn Type= 3
Dn Slope=0.0017
Boundary for River Rch & Prof#=UNT 020 IN LACR,Reach-1         , 4
Up Type= 0
Dn Type= 3
Dn Slope=0.0017
Boundary for River Rch & Prof#=UNT 020 IN LACR,Reach-1         , 5
Up Type= 0
Dn Type= 3
Dn Slope=0.0017
Boundary for River Rch & Prof#=UNT 020 IN LACR,Reach-1         , 6
Up Type= 0
Dn Type= 3
Dn Slope=0.0017
Boundary for River Rch & Prof#=UNT 020 IN LACR,Reach-1         , 7
Up Type= 0
Dn Type= 3
Dn Slope=0.0017
DSS Import GetInterval= 0
DSS Import GetPeak= 0
DSS Import FillOption= 0

--- UNT 020 IN LACR.g01 (geometry) ---

Geom Title=Existing Conditions
Program Version=4.10

River Reach=UNT 020 IN LACR ,Reach-1
Reach XY= 30
      2166587.72     13192796.86      2167237.72     13193146.86
      2168137.72     13192646.86      2170637.72     13192896.85
      2173837.72     13193896.85      2175587.72     13194996.85
      2176787.72     13194946.86      2178487.72     13195796.85
      2179187.72     13196446.85      2179187.72     13197246.86
      2179737.72     13197646.85      2179837.72     13199046.86
      2180387.72     13200496.85      2181337.72     13201146.85
      2181587.72     13202146.86      2182537.72     13202596.85
      2182387.72     13203296.86      2182737.72     13204196.85
      2182387.72     13205446.86      2183137.72     13205896.85
      2183037.72     13206596.86      2183387.72     13207146.85
      2184187.72     13208046.86      2184937.72     13207596.85
      2186237.72     13208696.85      2187537.72     13208496.85
      2187787.72     13209646.85      2188687.72     13209146.85
      2189487.72     13210396.85      2191387.72     13211046.85

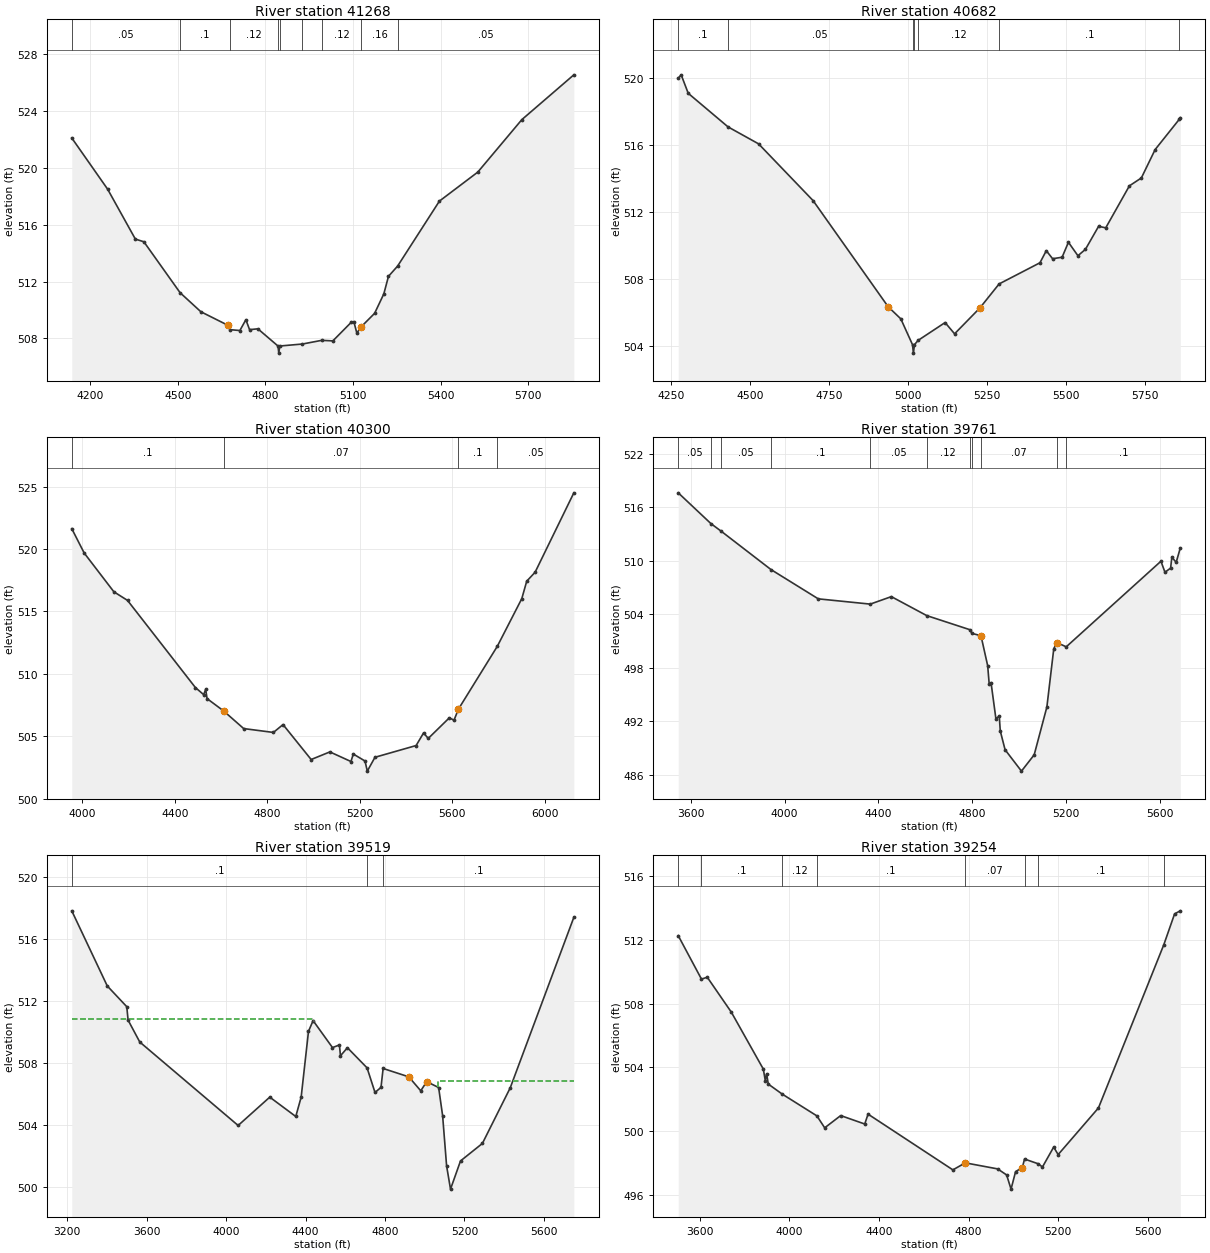
Type RM Length L Ch R = 1 ,41268   ,586,586,586
BEGIN DESCRIPTION:
UNT 020 IN LACR 75.0
END DESCRIPTION:
XS GIS Cut Line= 3
      2166573.55     13193687.29        2166893.     13192333.09
      2166816.62     13192013.66
#Sta/Elev= 30
  4136.5   522.1  4259.3   518.5  4354.3  514.99  4383.5   514.8  4507.5  511.22
  4578.7  509.88  4671.2  508.93  4677.9  508.62  4712.3  508.56  4732.9  509.32
  4745.5  508.62    4774  508.68  4842.9  507.47  4845.6  506.97  4848.9  507.47
  4926.5  507.61  4992.9  507.87  5030.8  507.83  5094.4  509.15  5102.7  509.18
    5113  508.38  5128.2  508.83  5173.9  509.77  5205.5  511.14  5221.3  512.37
  5252.6  513.09  5395.8  517.66  5527.3   519.7  5678.2  523.39  5856.3  526.54
#Mann= 9 ,-1 , 0
  4136.5     .05       0  4507.5      .1       0  4677.9     .12       0
  4842.9     .07       0  4848.9     .12       0  4926.5     .16       0
  4992.9     .12       0  5128.2     .16       0  5252.6     .05       0
Bank Sta=4671.2,5128.2
XS Rating Curve= 0 ,0
Exp/Cntr=0.3,0.1

Type RM Length L Ch R = 1 ,40682   ,382,382,382
BEGIN DESCRIPTION:
UNT 020 IN LACR 74.0
END DESCRIPTION:
XS GIS Cut Line= 4
      2167018.01     13193819.19      2167233.28     13193395.59
      2167240.22     13192583.09      2167095.11     13192320.51
#Sta/Elev= 30
  4273.8  519.97  4283.1  520.17  4305.4  519.07  4431.3  517.07  4527.9  516.06
  4700.3  512.68  4937.7  506.36  4977.7  505.64  5014.7   504.1  5017.5   503.6
  5020.7   504.1  5032.4  504.36  5117.7  505.42  5147.7  504.75  5227.7  506.29
  5288.5  507.72  5417.7  508.98  5437.7   509.7  5457.7  509.22  5487.7  509.31
  5507.7   510.2  5537.7   509.4  5561.5  509.78  5603.1  511.15  5625.7  511.06
  5700.5  513.56  5738.3  514.03  5781.9  515.72  5858.6  517.53  5861.5  517.62
#Mann= 7 ,-1 , 0
  4273.8      .1       0  4431.3     .05       0  5014.7     .03       0
  5020.7     .05       0  5032.4     .12       0  5288.5      .1       0
  5858.6     .05       0
Bank Sta=4937.7,5227.7
XS Rating Curve= 0 ,0
Exp/Cntr=0.3,0.1

Type RM Length L Ch R = 1 ,40300   ,539,539,539
BEGIN DESCRIPTION:
UNT 020 IN LACR 73.0
END DESCRIPTION:
XS GIS Cut Line= 4
      2167122.19     13193985.83      2167622.17      13193256.7
      2167476.34     13192374.75      2167254.09     13192048.34
#Sta/Elev= 30
  3953.9  521.63  4007.5  519.68  4136.1  516.57  4195.2  515.88  4488.8   508.9
  4524.6  508.33  4533.5  508.75  4539.5  508.01  4611.3  507.02  4697.9  505.61
  4826.5   505.3  4868.2  505.93  4989.9  503.13    5071  503.74  5162.2  502.97
  5172.3  503.57    5223  503.01  5232.9   502.2  5266.1  503.31  5444.2  504.25
  5476.4  505.26  5496.7  504.82  5587.9  506.47  5608.1  506.28  5627.4  507.17
  5795.5   512.2  5901.5  516.02  5922.9  517.42  5959.2  518.14  6126.8   524.5
#Mann= 4 ,-1 , 0
  3953.9      .1       0  4611.3     .07       0  5627.4      .1       0
  5795.5     .05       0
Bank Sta=4611.3,5627.4
XS Rating Curve= 0 ,0
Exp/Cntr=0.3,0.1

Type RM Length L Ch R = 1 ,39761   ,242,242,242
BEGIN DESCRIPTION:
UNT 020 IN LACR 72.0
END DESCRIPTION:
XS GIS Cut Line= 4
      2167303.22     13194006.46      2167761.56     13193103.66
      2168039.34     13192867.55       2167748.2     13192160.49
#Sta/Elev= 30
  3546.5  517.64  3685.9  514.19  3730.5  513.32  3941.8  509.04  4143.9  505.75
  4365.7  505.16  4455.6     506  4606.7  503.87  4789.4   502.3  4799.7  501.87
  4837.9  501.62  4866.5  498.25    4873  496.18  4880.8  496.36  4901.6   492.3
  4915.9  492.61  4920.2  490.94  4940.7  488.83  5010.6  486.43  5064.9  488.26
    5119  493.62  5148.5  500.17  5162.2  500.84  5201.6  500.37  5605.6  509.97
  5622.8  508.73  5646.8   509.2  5652.2  510.43  5670.5  509.84  5688.2  511.46
#Mann= 11 ,-1 , 0
  3546.5     .05       0  3685.9      .1       0  3730.5     .05       0
  3941.8      .1       0  4365.7     .05       0  4606.7     .12       0
  4789.4      .1       0  4799.7     .12       0  4837.9     .07       0
  5162.2     .12       0  5201.6      .1       0
Bank Sta=4837.9,5162.2
XS Rating Curve= 0 ,0
Exp/Cntr=0.3,0.1

Type RM Length L Ch R = 1 ,39519   ,265,265,265
BEGIN DESCRIPTION:
UNT 020 IN LACR 71.0
END DESCRIPTION:
XS GIS Cut Line= 4
      2167419.14     13194120.65      2167879.62     13193061.99
      2168147.98     13192990.96      2168187.72     13191896.85
#Sta/Elev= 30
  3223.6  517.82  3402.2  512.97  3500.4  511.63  3507.1  510.76  3565.8  509.35
  4060.9  503.96  4220.1  505.79    4351  504.54  4378.1  505.79    4415  510.04
  4438.2  510.73  4535.7  508.99  4570.7  509.16  4575.9  508.46    4611  508.98
  4709.8  507.68  4749.8  506.09  4779.9  506.42  4790.6  507.64  4919.9   507.1
    4980   506.2    5010  506.79    5070  506.41  5090.1  504.59  5110.1  501.35
  5129.8  499.85  5180.1  501.67  5290.2   502.8  5430.3  506.39  5750.5   517.4
#Mann= 3 ,-1 , 0
  3223.6      .1       0  4709.8     .07       0  4790.6      .1       0
#XS Ineff= 2 , 0
       0 4443.75  510.83 5065.91       0   506.8
Permanent Ineff=
       T       T
Bank Sta=4919.9,5010
XS Rating Curve= 0 ,0
Exp/Cntr=0.3,0.1

Type RM Length L Ch R = 1 ,39254   ,565,565,565
BEGIN DESCRIPTION:
UNT 020 IN LACR 70.0
END DESCRIPTION:
XS GIS Cut Line= 3
      2167787.75     13193996.82      2168414.34     13193096.72
      2168386.57     13191951.37
#Sta/Elev= 30
  3503.3  512.28  3607.1  509.55  3632.9  509.67  3740.2  507.48  3883.3   503.9
  3892.1  503.18  3898.2  503.61  3905.3  502.96  3967.6  502.33  4122.6  500.96
  4157.4  500.21  4228.9  500.98  4336.3  500.45  4351.1  501.07  4729.9  497.57
 4785.51  498.01    4930  497.63    4970  497.25  4989.7  496.36    5010  497.46
    5040  497.71    5050  498.25  5111.5  497.95    5130  497.75  5180.1     499
  5200.1  498.53  5380.1  501.46    5672  511.71  5720.2  513.65  5745.7  513.84
#Mann= 8 ,-1 , 0
  3503.3     .05       0  3607.1      .1       0  3967.6     .12       0
  4122.6      .1       0 4785.51     .07       0    5050     .12       0
  5111.5      .1       0    5672     .05       0
Bank Sta=4785.51,5040
XS Rating Curve= 0 ,0
Exp/Cntr=0.3,0.1

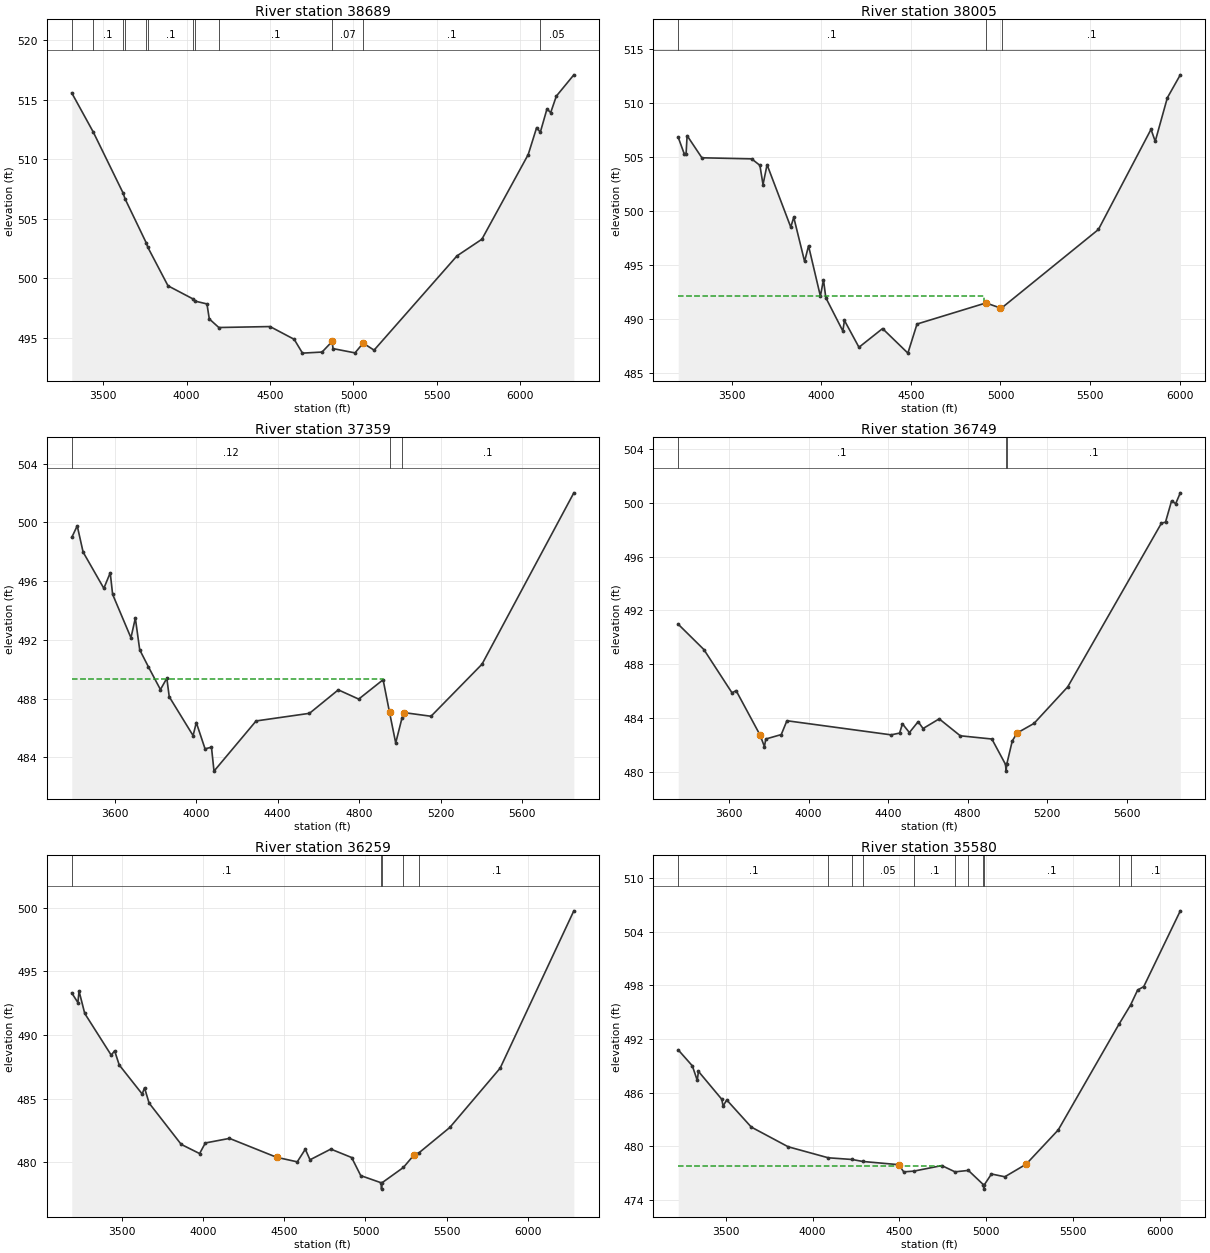
Type RM Length L Ch R = 1 ,38689   ,684,684,684
BEGIN DESCRIPTION:
UNT 020 IN LACR 69.0
END DESCRIPTION:
XS GIS Cut Line= 4
      2167979.98     13194164.45      2168748.19     13193422.27
      2169034.65     13192406.65      2168644.05     13191612.42
#Sta/Elev= 30
  3311.9  515.56    3441  512.27  3619.4  507.16  3630.9  506.68  3757.3     503
  3767.4  502.61  3888.6  499.37  4036.8  498.28  4052.5  498.08  4121.9  497.85
    4136  496.59  4193.1  495.87    4500  495.95  4644.6  494.88  4694.4  493.72
  4811.7  493.81  4872.2   494.7  4877.4   494.1  5009.1  493.74  5057.8  494.56
  5123.4  493.97    5620  501.88  5769.4  503.28    6047  510.39  6097.5  512.65
  6119.4  512.26  6159.3  514.21  6181.7  513.91  6215.4  515.29  6320.4  517.08
#Mann= 12 ,-1 , 0
  3311.9     .05       0    3441      .1       0  3619.4     .05       0
  3630.9      .1       0  3757.3     .05       0  3767.4      .1       0
  4036.8     .12       0  4052.5     .05       0  4193.1      .1       0
  4872.2     .07       0  5057.8      .1       0  6119.4     .05       0
Bank Sta=4872.2,5057.8
XS Rating Curve= 0 ,0
Exp/Cntr=0.3,0.1

Type RM Length L Ch R = 1 ,38005   ,646,646,646
BEGIN DESCRIPTION:
UNT 020 IN LACR 68.0
END DESCRIPTION:
XS GIS Cut Line= 3
       2169031.9     13194506.68      2169379.11      13193756.7
      2169684.66     13191805.34
#Sta/Elev= 30
    3202  506.82  3234.9  505.32  3245.9  505.32  3251.5  506.98    3334  504.93
  3611.8  504.83  3657.7  504.23  3675.1  502.45  3697.7  504.29  3829.9  498.52
  3846.5  499.43  3907.1  495.35  3929.1  496.79  3995.2  492.14  4012.5  493.64
  4025.6  491.99  4120.4  488.92  4129.5  489.89  4210.5  487.41  4342.1  489.14
  4483.5  486.87  4534.4  489.56    4919  491.51    5000  491.04  5010.1  491.09
  5546.6   498.3  5840.1  507.56  5863.6  506.45  5931.3  510.48  6003.6   512.6
#Mann= 3 ,-1 , 0
    3202      .1       0    4919     .07       0  5010.1      .1       0
#XS Ineff= 2 , 0
       0  4907.1  492.13               0
Permanent Ineff=
       T       F
Bank Sta=4919,5000
XS Rating Curve= 0 ,0
Exp/Cntr=0.3,0.1

Type RM Length L Ch R = 1 ,37359   ,610,610,610
BEGIN DESCRIPTION:
UNT 020 IN LACR 67.0
END DESCRIPTION:
XS GIS Cut Line= 3
      2169434.68     13194340.01      2170038.84     13193305.31
      2170205.28     13192050.07
#Sta/Elev= 30
  3389.8  498.98  3416.6  499.77  3445.5  497.98  3547.2  495.51  3578.6  496.57
  3590.3   495.1  3680.3  492.14  3701.8  493.48  3723.3  491.32  3766.3  490.15
    3825  488.61  3856.4  489.38  3868.2  488.12  3985.3  485.47  4001.1  486.36
    4044  484.57  4075.5  484.68    4088  483.05  4294.5  486.47  4556.6  486.99
    4698  488.59  4798.2  487.96    4918  489.28  4949.6  487.05  4979.8  484.97
  5010.1  486.64  5020.2  487.04  5153.2  486.79  5403.5  490.34  5854.2  502.02
#Mann= 3 ,-1 , 0
  3389.8     .12       0  4949.6     .07       0  5010.1      .1       0
#XS Ineff= 2 , 0
         4915.91  489.32
Permanent Ineff=
       F       F
Bank Sta=4949.6,5020.2
XS Rating Curve= 0 ,0
Exp/Cntr=0.3,0.1

Type RM Length L Ch R = 1 ,36749   ,490,490,490
BEGIN DESCRIPTION:
UNT 020 IN LACR 66.0
END DESCRIPTION:
XS GIS Cut Line= 4
      2169754.11     13194284.48      2170524.95     13193395.59
      2170795.78     13192624.75      2170684.68     13192103.97
#Sta/Elev= 30
  3343.8  490.96  3472.7  489.08  3614.2  485.86  3635.1  486.02  3755.7  482.71
  3777.5  481.85  3784.2  482.42  3862.1  482.75  3890.6  483.78  4414.8  482.73
  4457.5  482.86  4471.8  483.55  4506.9   482.9  4550.8  483.71  4575.7   483.2
  4656.8  483.92  4762.8  482.66  4921.8  482.42  4990.5  480.53  4993.3  480.03
  4996.5  480.53  5024.5  482.28    5049  482.87  5133.8  483.58  5303.4   486.3
  5774.9  498.48  5795.4  498.56    5826  500.14  5846.5  499.93  5869.9  500.74
#Mann= 3 ,-1 , 0
  3343.8      .1       0  4990.5     .07       0  4996.5      .1       0
Bank Sta=3755.7,5049
XS Rating Curve= 0 ,0
Exp/Cntr=0.3,0.1

Type RM Length L Ch R = 1 ,36259   ,679,679,679
BEGIN DESCRIPTION:
UNT 020 IN LACR 65.0
END DESCRIPTION:
XS GIS Cut Line= 4
      2169809.65       13194472.      2170774.95     13193562.25
      2171372.17     13192805.31      2171822.03      13192140.9
#Sta/Elev= 30
  3190.7   493.3  3228.5  492.54  3235.4  493.45  3270.6  491.69  3433.6  488.42
  3454.7  488.76    3483  487.65  3624.6  485.37  3638.8  485.86  3667.1  484.66
  3864.9  481.42  3978.2   480.7  4013.4  481.53  4162.3  481.89  4452.2  480.41
  4579.7  480.05  4629.4  481.04  4658.3  480.21  4786.6  481.05  4914.8  480.39
  4970.9  478.97  5096.2  478.41  5098.9  477.91  5102.2  478.41  5233.7  479.61
  5299.6   480.6  5331.6  480.78  5519.8  482.75  5829.7   487.4  6283.7  499.74
#Mann= 5 ,-1 , 0
  3190.7      .1       0  5096.2     .07       0  5102.2      .1       0
  5233.7     .12       0  5331.6      .1       0
Bank Sta=4452.2,5299.6
XS Rating Curve= 0 ,0
Exp/Cntr=0.3,0.1

Type RM Length L Ch R = 1 ,35580   ,274,274,274
BEGIN DESCRIPTION:
UNT 020 IN LACR 64.0
END DESCRIPTION:
XS GIS Cut Line= 3
       2170427.7     13194541.44      2171524.95     13193471.98
      2172351.31     13192395.63
#Sta/Elev= 30
  3226.8  490.78  3307.9     489  3336.2  487.38  3343.2  488.38  3477.6  485.26
  3484.6   484.5  3505.9  485.19  3647.2  482.16  3859.4  479.96  4090.2  478.73
  4227.5  478.54  4288.3  478.32  4495.9  477.96  4524.2  477.16  4582.7  477.24
  4743.4  477.86  4819.5  477.16  4896.4  477.32  4982.7  475.73  4985.4  475.23
  4988.7  475.73  5029.2  476.92  5106.2  476.61  5228.6  478.01  5413.5  481.84
  5762.2  493.62  5829.7  495.79  5870.3  497.46  5905.6  497.85    6116  506.31
#Mann= 11 ,-1 , 0
  3226.8      .1       0  4090.2     .12       0  4227.5      .1       0
  4288.3     .05       0  4582.7      .1       0  4819.5     .05       0
  4896.4      .1       0  4982.7     .07       0  4988.7      .1       0
  5762.2     .05       0  5829.7      .1       0
#XS Ineff= 2 , 0
         4742.55  477.86
Permanent Ineff=
       F       F
Bank Sta=4495.9,5228.6
XS Rating Curve= 0 ,0
Exp/Cntr=0.3,0.1

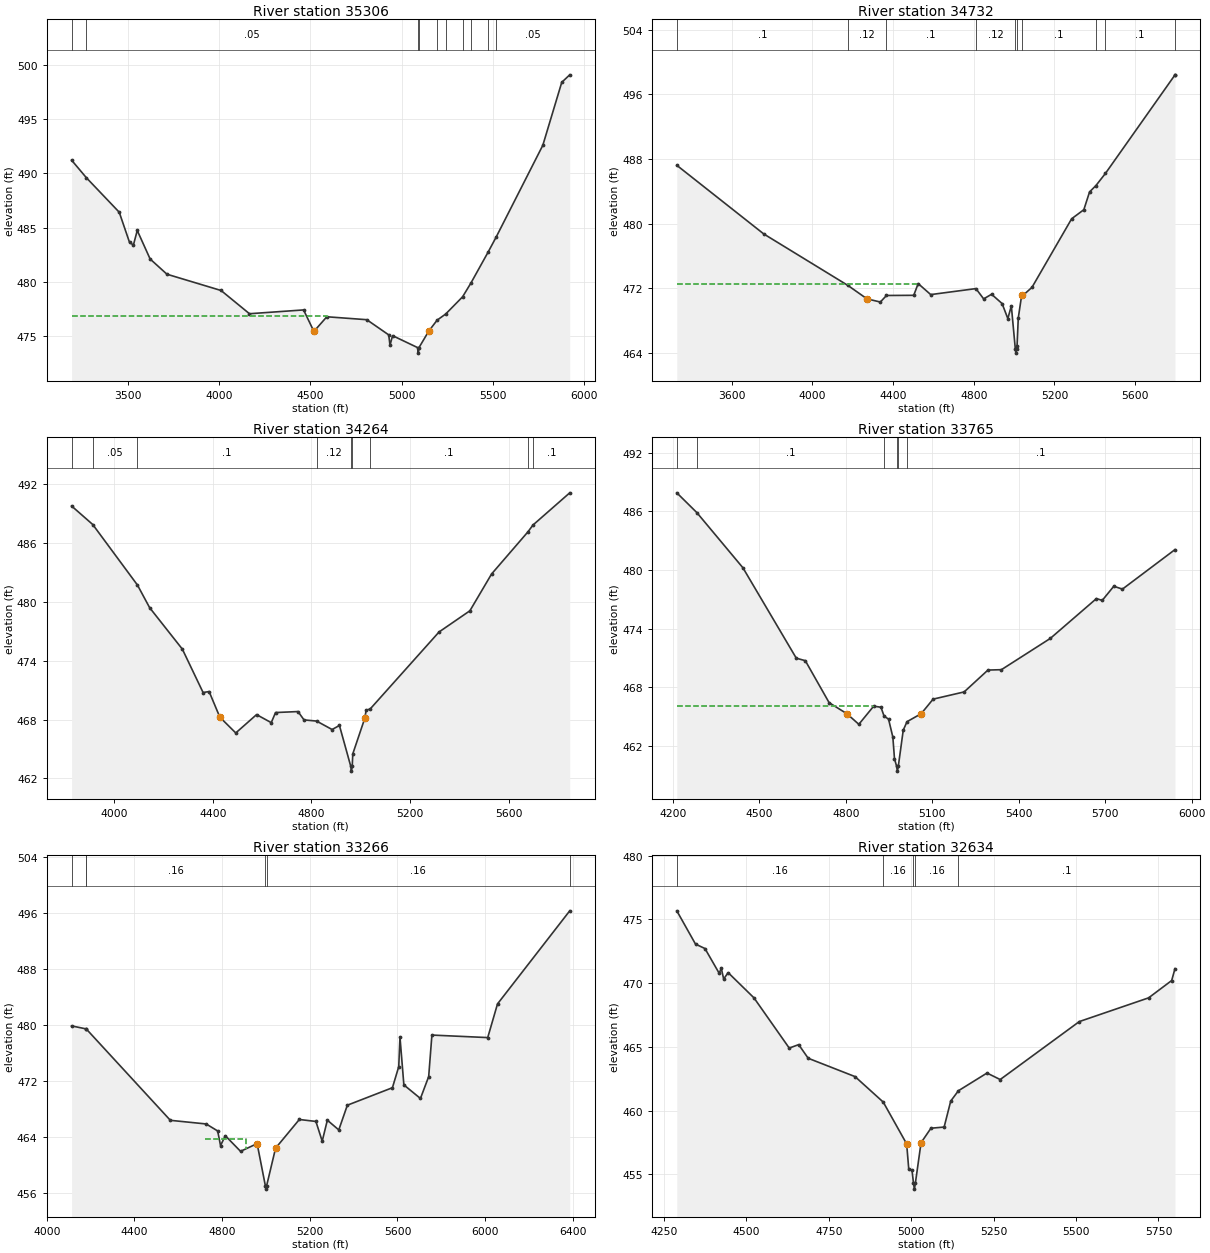
Type RM Length L Ch R = 1 ,35306   ,574,574,574
BEGIN DESCRIPTION:
UNT 020 IN LACR 63.0
END DESCRIPTION:
XS GIS Cut Line= 3
       2170608.3     13194596.96      2172288.84     13192992.81
      2172482.95     13192632.31
#Sta/Elev= 30
  3189.5  491.22  3270.6   489.6    3451  486.42  3507.3  483.65  3528.7   483.4
  3549.8  484.74  3620.5  482.11  3712.7  480.71  4009.6  479.21  4165.3  477.07
  4462.2  477.42  4518.8  475.44  4589.6  476.79  4808.8  476.52  4929.3  475.12
  4936.2  474.16  4950.3  475.05  5088.9  473.94  5091.6  473.44  5094.9  473.94
  5148.5  475.46  5194.8  476.48  5241.5  477.04  5334.5  478.63  5380.2   479.9
  5474.2  482.74  5517.6   484.1  5774.6  492.59  5878.4  498.39  5922.2  499.08
#Mann= 10 ,-1 , 0
  3189.5      .1       0  3270.6     .05       0  5088.9     .04       0
  5094.9     .05       0  5194.8      .1       0  5241.5     .05       0
  5334.5      .1       0  5380.2     .05       0  5474.2      .1       0
  5517.6     .05       0
#XS Ineff= 2 , 0
         4588.64  476.83
Permanent Ineff=
       F       F
Bank Sta=4518.8,5148.5
XS Rating Curve= 0 ,0
Exp/Cntr=0.3,0.1

Type RM Length L Ch R = 1 ,34732   ,468,468,468
BEGIN DESCRIPTION:
UNT 020 IN LACR 61.0
END DESCRIPTION:
XS GIS Cut Line= 3
      2171740.21       13194972.        2172643.     13193034.48
      2172629.13      13192701.5
#Sta/Elev= 30
  3327.3  487.22  3758.6  478.73    4176  472.36  4270.7   470.7  4336.9  470.31
  4367.3  471.12  4502.4  471.14  4524.5  472.59  4586.6  471.23  4810.8  471.97
  4849.2   470.7  4888.5  471.27  4940.7  470.12  4969.1  468.26  4986.5  469.83
  5006.3  464.49  5009.1  463.99  5012.3  464.49  5014.9   464.9  5020.9  468.33
  5037.7  471.14  5040.2  471.04    5089  472.13  5285.7  480.61  5346.1  481.73
  5374.5  483.93  5405.9  484.71    5453  486.21  5797.3  498.37  5798.1  498.41
#Mann= 10 ,-1 , 0
  3327.3      .1       0    4176     .12       0  4367.3      .1       0
  4810.8     .12       0  5006.3     .07       0  5012.3     .12       0
  5040.2      .1       0  5405.9     .05       0    5453      .1       0
  5797.3     .05       0
#XS Ineff= 2 , 0
         4522.16  472.52
Permanent Ineff=
       F       F
Bank Sta=4270.7,5037.7
XS Rating Curve= 0 ,0
Exp/Cntr=0.3,0.1

Type RM Length L Ch R = 1 ,34264   ,499,499,499
BEGIN DESCRIPTION:
UNT 020 IN LACR 60.0
END DESCRIPTION:
XS GIS Cut Line= 3
      2172406.88      13194735.9      2172997.17     13193235.87
      2172941.61     13192833.08
#Sta/Elev= 30
  3827.9  489.77  3913.7  487.88  4094.9  481.71  4144.1  479.41  4276.8  475.18
  4360.8  470.76  4385.2  470.86  4428.7  468.25  4493.2  466.64  4577.5  468.51
    4637  467.69  4654.4  468.72  4745.4  468.82  4769.8  467.97  4820.8  467.85
  4883.5  466.99  4913.3   467.4  4959.1  463.25  4961.8  462.75  4965.1  463.25
  4967.4  464.51  5016.2  468.15  5021.6  468.97  5037.4  469.07  5316.9  476.93
  5441.9  479.09  5529.8  482.84    5677  487.13  5697.6  487.83  5846.5  491.11
#Mann= 9 ,-1 , 0
  3827.9      .1       0  3913.7     .05       0  4094.9      .1       0
  4820.8     .12       0  4959.1     .07       0  4965.1     .12       0
  5037.4      .1       0    5677     .05       0  5697.6      .1       0
#XS Ineff= 2 , 0
         4654.83  468.72
Permanent Ineff=
       F       F
Bank Sta=4428.7,5016.2
XS Rating Curve= 0 ,0
Exp/Cntr=0.3,0.1

Type RM Length L Ch R = 1 ,33765   ,499,499,499
BEGIN DESCRIPTION:
UNT 020 IN LACR 59.0
END DESCRIPTION:
XS GIS Cut Line= 3
      2173011.06     13194659.48      2173274.95     13193603.92
      2173233.28     13192965.03
#Sta/Elev= 30
  4213.9  487.91  4283.2  485.89  4443.4  480.22  4628.4  470.96  4659.8   470.7
  4742.3   466.4  4804.2  465.26  4845.4  464.18  4896.9  466.04  4922.2  465.93
    4933  465.02  4948.5  464.71  4963.4  462.87  4969.1  460.66  4976.4  459.88
  4979.1  459.38  4982.4  459.88  4999.5  463.58  5012.6  464.45  5061.8  465.27
  5103.1  466.76  5210.8   467.5  5293.3  469.74  5340.1  469.78  5509.5  472.98
  5669.8  477.07  5689.8  476.88  5729.9  478.33    5760  478.04  5942.2  482.09
#Mann= 6 ,-1 , 0
  4213.9     .05       0  4283.2      .1       0    4933     .12       0
  4976.4     .07       0  4982.4     .12       0  5012.6      .1       0
#XS Ineff= 2 , 0
         4895.45  466.04
Permanent Ineff=
       F       F
Bank Sta=4804.2,5061.8
XS Rating Curve= 0 ,0
Exp/Cntr=0.3,0.1

Type RM Length L Ch R = 1 ,33266   ,632,632,632
BEGIN DESCRIPTION:
UNT 020 IN LACR 58.0
END DESCRIPTION:
XS GIS Cut Line= 3
       2173254.1      13194659.5      2173962.45     13193041.42
      2174149.42     13192570.51
#Sta/Elev= 30
  4112.9  479.87  4177.9  479.45    4180  479.43  4563.6  466.38  4727.1  465.86
  4779.5  464.86  4792.6  462.77  4814.4  464.18  4883.9  461.95  4959.5  463.05
    4997  457.05  4999.8  456.55    5003  457.05  5043.7   462.4  5152.1   466.5
  5227.7  466.22  5256.5   463.4  5279.9   466.4  5332.1  465.01  5371.2  468.54
  5576.9  471.04  5605.7  474.05  5611.3  478.27  5629.1  471.44  5704.7   469.5
  5742.3  472.63    5757  478.56  6011.7   478.2  6056.3  483.01  6385.9  496.31
#Mann= 6 ,-1 , 0
  4112.9     .05       0  4177.9      .1       0    4180     .16       0
    4997     .07       0    5003     .16       0  6385.9     .05       0
#XS Ineff= 1 ,-1
 4723.01 4907.67  463.77
Permanent Ineff=
       F
Bank Sta=4959.5,5043.7
XS Rating Curve= 0 ,0
Exp/Cntr=0.3,0.1

Type RM Length L Ch R = 1 ,32634   ,337,337,337
BEGIN DESCRIPTION:
UNT 020 IN LACR 57.0
END DESCRIPTION:
XS GIS Cut Line= 3
      2173487.75     13194646.83      2174037.72     13194196.85
      2174037.72     13193396.85
#Sta/Elev= 30
  4289.4  475.68  4346.1  473.07  4374.8  472.72  4417.9  470.78  4424.3  471.17
  4431.5  470.33  4445.1  470.83  4523.4  468.85  4630.3  464.91    4659  465.18
  4687.8  464.11  4829.9  462.67  4915.4  460.67  4986.4  457.39  4992.8  455.39
  5002.5  455.33    5007  454.34  5009.8  453.84    5013  454.34    5030  457.48
    5060  458.62    5100  458.71    5120  460.75  5143.3  461.56    5230  462.95
    5270  462.44    5510  466.99    5720  468.85    5790  470.21    5800  471.14
#Mann= 5 ,-1 , 0
  4289.4     .16       0  4915.4     .16       0    5007     .07       0
    5013     .16       0  5143.3      .1       0
#XS Ineff= 2 , 0
       0                    5230       0  462.95
Permanent Ineff=
       F       T
Bank Sta=4986.4,5030
XS Rating Curve= 0 ,0
Exp/Cntr=0.3,0.1

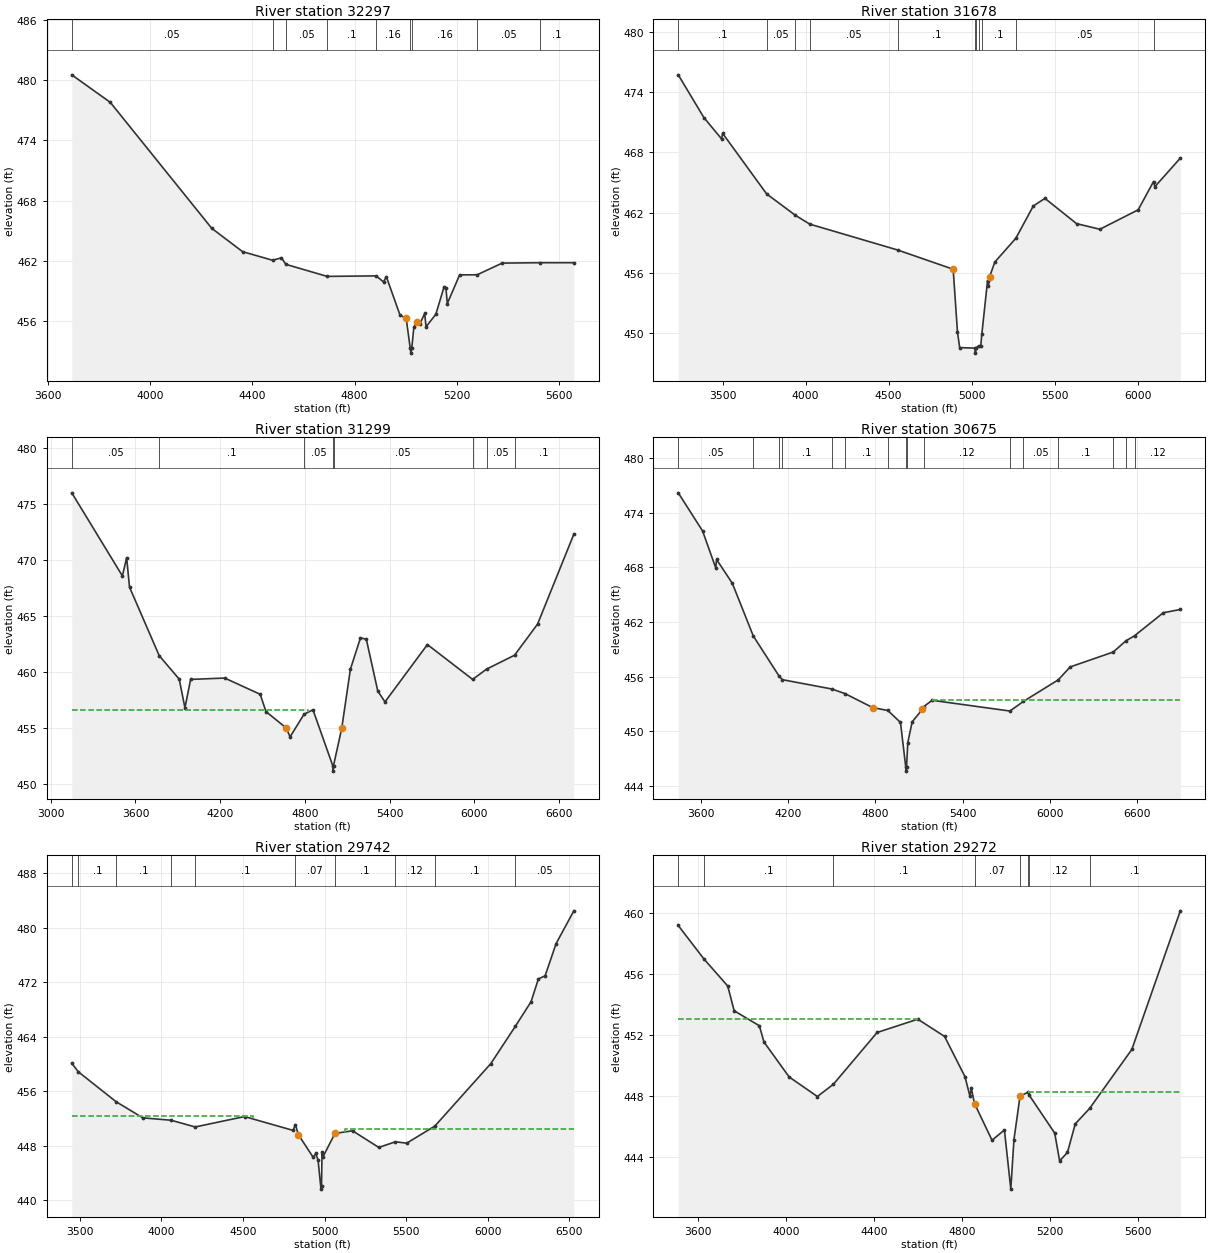
Type RM Length L Ch R = 1 ,32297   ,619,619,619
BEGIN DESCRIPTION:
UNT 020 IN LACR 56.0
END DESCRIPTION:
XS GIS Cut Line= 3
      2173517.99     13195340.04      2174122.17      13194819.2
      2174559.66      13193735.9
#Sta/Elev= 30
  3692.9  480.52  3843.8  477.78    4241  465.26  4361.6  462.94  4479.8  462.08
    4514  462.33    4531  461.68  4692.7  460.48  4884.8  460.53  4913.7  459.93
  4924.6  460.46  4978.4  456.62  5002.4  456.31  5018.2  453.35  5020.9  452.85
  5024.2  453.35  5032.4  455.41  5043.1  455.93  5056.1  455.77  5074.8  456.79
  5080.2  455.47  5118.6  456.72    5151  459.47    5158  459.34  5163.4  457.78
  5211.7  460.63  5280.4  460.64  5378.1   461.8  5526.8  461.84  5658.9  461.84
#Mann= 9 ,-1 , 0
  3692.9     .05       0  4479.8      .1       0    4531     .05       0
  4692.7      .1       0  4884.8     .16       0  5018.2     .07       0
  5024.2     .16       0  5280.4     .05       0  5526.8      .1       0
Bank Sta=5002.4,5043.1
XS Rating Curve= 0 ,0
Exp/Cntr=0.3,0.1

Type RM Length L Ch R = 1 ,31678   ,379,379,379
BEGIN DESCRIPTION:
UNT 020 IN LACR 55.0
END DESCRIPTION:
XS GIS Cut Line= 4
      2173636.09     13195742.79      2174733.28     13194805.31
       2174955.5     13194166.42      2174886.06     13193263.68
#Sta/Elev= 30
  3232.5  475.75  3386.9  471.49  3493.4  469.36    3500  469.91    3765  463.87
  3938.5  461.73  4025.4  460.85  4554.6  458.27    4889  456.35  4914.9   450.1
  4928.1  448.53  5020.4  448.48  5023.2  447.98  5026.4  448.48  5042.5  448.72
  5055.2  448.68  5061.4  449.84  5096.2  455.22  5101.5  454.71  5108.1  455.58
  5139.9  457.07  5266.5  459.44  5371.7  462.66  5441.9  463.42  5632.5   460.9
  5772.9  460.34  6003.6  462.28  6096.1   465.1  6103.9  464.58  6257.5  467.44
#Mann= 11 ,-1 , 0
  3232.5      .1       0    3765     .05       0  3938.5      .1       0
  4025.4     .05       0  4554.6      .1       0  5020.4     .07       0
  5026.4      .1       0  5042.5     .12       0  5061.4      .1       0
  5266.5     .05       0  6096.1      .1       0
Bank Sta=4889,5108.1
XS Rating Curve= 0 ,0
Exp/Cntr=0.3,0.1

Type RM Length L Ch R = 1 ,31299   ,624,624,624
BEGIN DESCRIPTION:
UNT 020 IN LACR 54.0
END DESCRIPTION:
XS GIS Cut Line= 4
      2174830.51     13196583.06        2175018.      13194944.2
      2175136.06     13194353.92      2175108.32     13193050.13
#Sta/Elev= 30
  3149.2  475.96  3507.7  468.54  3537.9  470.17  3558.1  467.54  3768.5  461.42
  3910.3  459.32  3950.6  456.76  3990.9   459.3  4232.4  459.42  4483.7  457.97
  4524.3  456.43  4667.3  454.97  4695.4  454.17  4793.5  456.18  4857.2  456.59
    4997  451.61  4999.7  451.11    5003  451.61  5061.2  454.95  5122.4  460.21
  5193.8  463.01  5235.2  462.89  5316.1  458.27  5367.1  457.29  5667.8  462.41
  5988.1   459.3    6087  460.22  6284.8  461.46    6448  464.24  6704.8  472.27
#Mann= 8 ,-1 , 0
  3149.2     .05       0  3768.5      .1       0  4793.5     .05       0
    4997     .03       0    5003     .05       0  5988.1      .1       0
    6087     .05       0  6284.8      .1       0
#XS Ineff= 2 , 0
         4822.73  456.57
Permanent Ineff=
       F       F
Bank Sta=4667.3,5061.2
XS Rating Curve= 0 ,0
Exp/Cntr=0.3,0.1

Type RM Length L Ch R = 1 ,30675   ,933,933,933
BEGIN DESCRIPTION:
UNT 020 IN LACR 53.0
END DESCRIPTION:
XS GIS Cut Line= 3
      2175011.07     13196423.34      2175545.78     13195298.37
      2175795.78     13193103.94
#Sta/Elev= 30
  3444.1  476.21  3611.4  472.02  3702.3  467.95  3707.8  468.88  3815.9  466.27
  3960.6  460.46  4138.8  456.03  4159.9  455.66  4502.2  454.63  4592.2  454.12
  4781.8  452.59  4886.2  452.27    4973  450.96  5009.1   446.1  5011.9   445.6
  5015.1   446.1  5023.3  448.73  5053.5  451.02    5124   452.4  5131.7  452.68
  5191.1  453.39  5726.3  452.21    5818  453.26  6058.7  455.64  6140.5  457.06
  6436.9   458.7  6523.8  459.93  6583.5  460.49  6781.3  463.02  6898.3  463.38
#Mann= 16 ,-1 , 0
  3444.1     .05       0  3960.6      .1       0  4138.8     .05       0
  4159.9      .1       0  4502.2     .05       0  4592.2      .1       0
  4886.2     .12       0  5009.1     .07       0  5015.1     .12       0
  5131.7     .12       0  5726.3      .1       0    5818     .05       0
  6058.7      .1       0  6436.9     .05       0  6523.8      .1       0
  6583.5     .12       0
#XS Ineff= 2 , 0
                         5191.15           453.4
Permanent Ineff=
       F       F
Bank Sta=4781.8,5124
XS Rating Curve= 0 ,0
Exp/Cntr=0.3,0.1

Type RM Length L Ch R = 1 ,29742   ,470,470,470
BEGIN DESCRIPTION:
UNT 020 IN LACR 52.0
END DESCRIPTION:
XS GIS Cut Line= 3
      2175511.03     13196124.78      2176295.78     13195235.87
        2176983.     13193472.71
#Sta/Elev= 30
  3450.4  460.09  3491.1  458.83  3722.9  454.43  3886.1  452.07  4059.1  451.72
  4207.1  450.73  4509.4  452.26  4806.8  450.23  4821.7  451.07    4839  449.62
  4930.4  446.27  4946.3  446.84  4960.3  445.88  4978.3  441.59  4981.5  442.09
  4984.8  447.09  4990.2  446.32  5063.7  449.78  5171.7  450.17  5332.7  447.72
  5434.7  448.55    5504  448.35  5676.8  450.87  6019.6  460.05  6169.3  465.51
  6266.5  469.16  6311.1   472.5  6352.3  472.95  6419.8   477.7  6528.5  482.51
#Mann= 10 ,-1 , 0
  3450.4     .05       0  3491.1      .1       0  3722.9      .1       0
  4059.1      .1       0  4207.1      .1       0  4821.7     .07       0
  5063.7      .1       0  5434.7     .12       0  5676.8      .1       0
  6169.3     .05       0
#XS Ineff= 2 , 0
       0 4558.58  452.31 5123.48       0  450.36
Permanent Ineff=
       T       T
Bank Sta=4839,5063.7
XS Rating Curve= 0 ,0
Exp/Cntr=0.3,0.1

Type RM Length L Ch R = 1 ,29272   ,526,526,526
BEGIN DESCRIPTION:
UNT 020 IN LACR 50.0
END DESCRIPTION:
XS GIS Cut Line= 3
      2175969.41     13196194.18      2176622.17      13195319.2
      2177323.12     13194354.52
#Sta/Elev= 30
  3509.9  459.18  3626.3     457  3735.1  455.22  3764.3   453.6    3879  452.62
  3899.8  451.56  4014.5  449.27  4142.9  447.99  4215.6  448.79  4414.8  452.18
  4599.9  453.05  4721.7  451.92  4814.6  449.28  4836.9  448.01  4843.1  448.53
  4857.8  447.53  4937.4  445.13  4993.8   445.8  5022.9  441.93  5037.1  445.16
  5064.9  448.02  5101.7  448.27  5107.4  448.06  5222.5   445.6    5245  443.78
  5280.5  444.33  5316.1   446.2  5381.3  447.21  5573.5  451.07    5794  460.14
#Mann= 8 ,-1 , 0
  3509.9     .05       0  3626.3      .1       0  4215.6      .1       0
  4857.8     .07       0  5064.9     .12       0  5101.7      .1       0
  5107.4     .12       0  5381.3      .1       0
#XS Ineff= 2 , 0
       0 4601.48  453.08 5100.85       0  448.29
Permanent Ineff=
       T       T
Bank Sta=4857.8,5064.9
XS Rating Curve= 0 ,0
Exp/Cntr=0.3,0.1