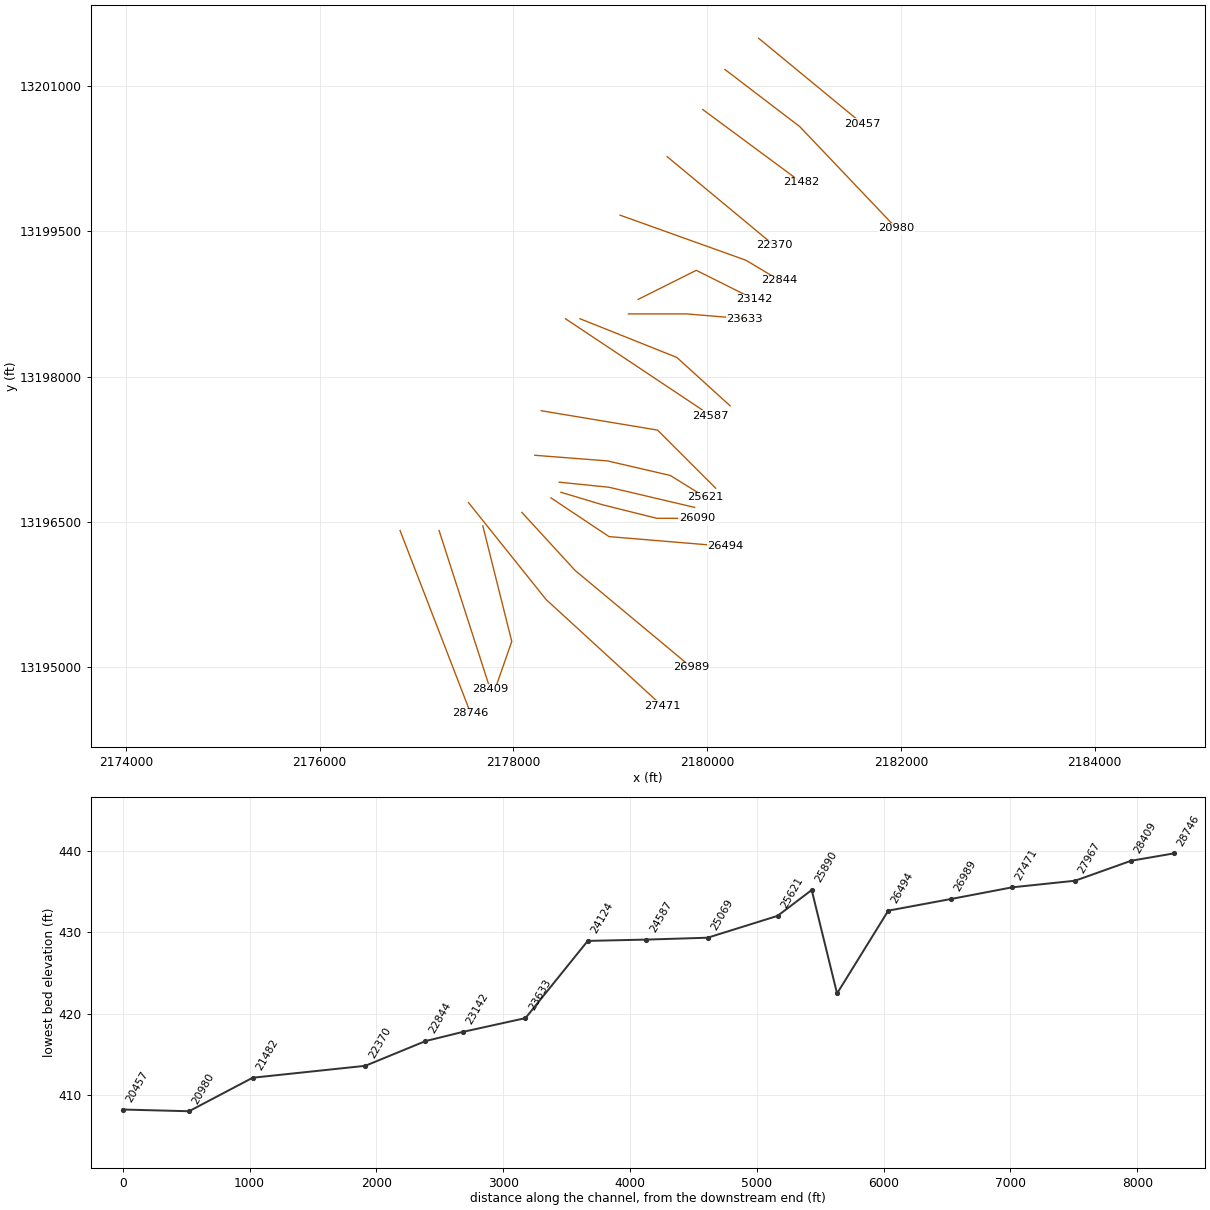
HEC-RAS study UNT 020 IN LACR.prj: UNT 020 IN LACR Base Level Engineering

--- UNT 020 IN LACR.g01 (geometry) --- (continued)

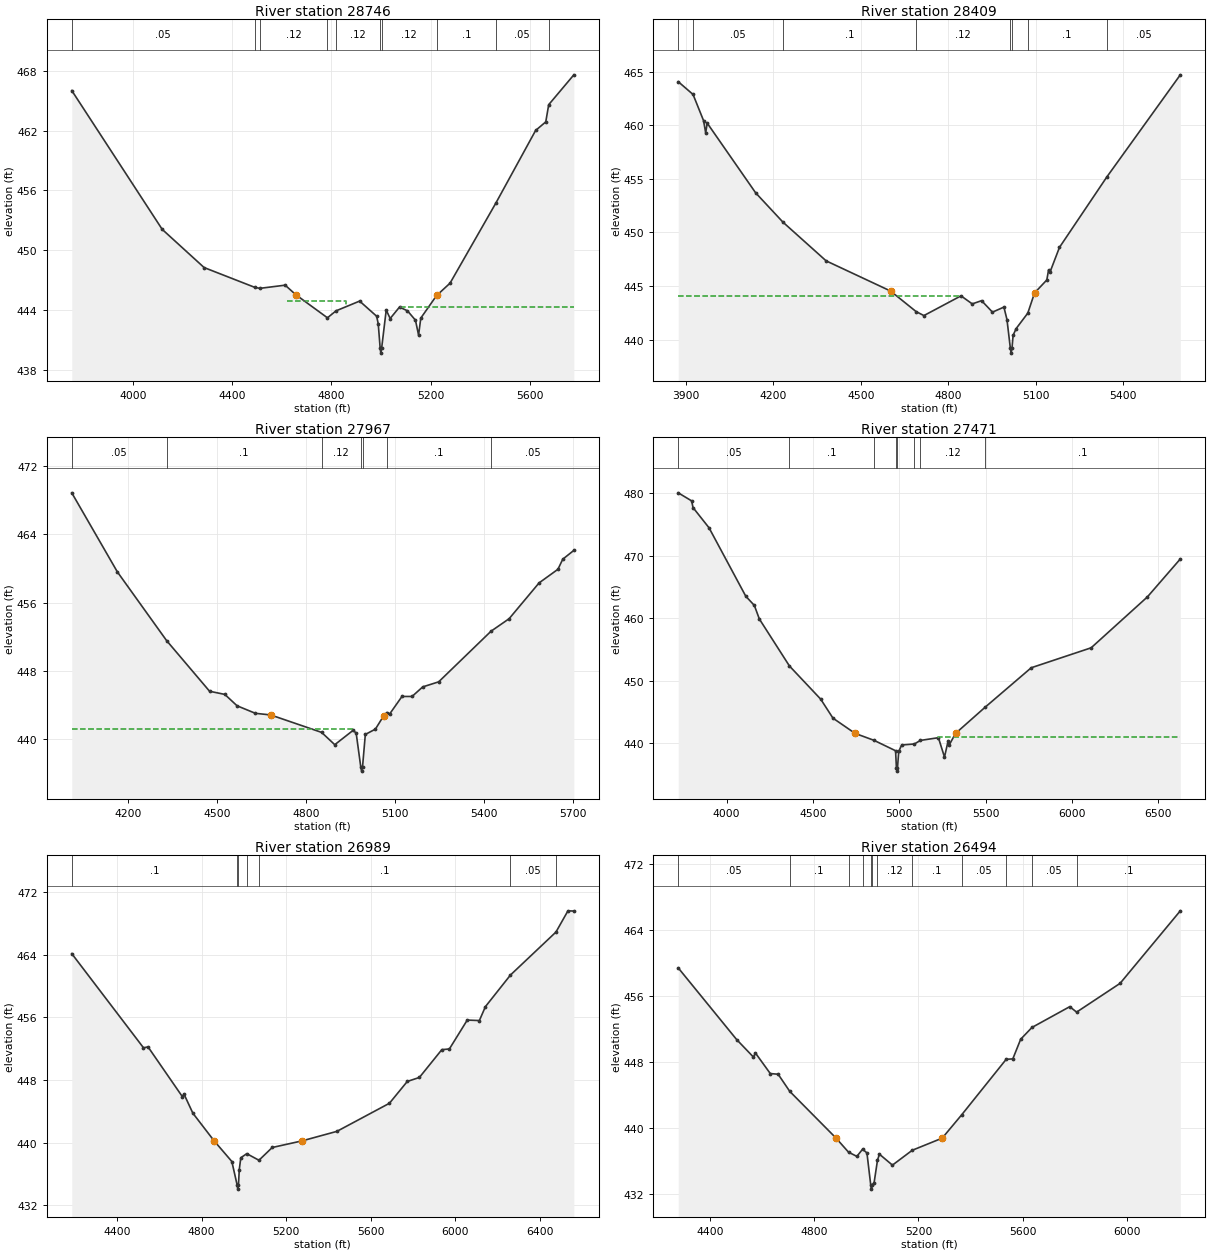
Type RM Length L Ch R = 1 ,28746   ,337,337,337
BEGIN DESCRIPTION:
UNT 020 IN LACR 49.0
END DESCRIPTION:
XS GIS Cut Line= 2
      2176830.52     13196409.44      2177559.42     13194521.24
#Sta/Elev= 30
  3753.8  466.04  4118.3  452.09  4287.3  448.25  4490.6  446.27  4511.8  446.16
  4614.1  446.48    4657  445.52  4784.5   443.2  4819.1   443.9  4914.2  444.88
  4982.8  443.36  4989.3  442.59    4997  440.15  4999.7  439.65    5003  440.15
  5021.4  443.98  5037.4  443.13    5075  444.28  5107.2   443.9  5139.3  442.96
  5151.9  441.46  5160.8  443.17  5225.1  445.46  5225.5  445.46  5278.7  446.68
  5463.4  454.73  5623.7  462.03  5664.6  462.89  5676.5  464.62  5777.8  467.62
#Mann= 10 ,-1 , 0
  3753.8     .05       0  4490.6      .1       0  4511.8     .12       0
  4784.5      .1       0  4819.1     .12       0    4997     .07       0
    5003     .12       0  5225.5      .1       0  5463.4     .05       0
  5676.5      .1       0
#XS Ineff= 2 ,-1
 4620.74  4860.8   444.9  5076.7  5777.8  444.33
Permanent Ineff=
       F       F
Bank Sta=4657,5225.1
XS Rating Curve= 0 ,0
Exp/Cntr=0.3,0.1

Type RM Length L Ch R = 1 ,28409   ,442,442,442
BEGIN DESCRIPTION:
UNT 020 IN LACR 48.0
END DESCRIPTION:
XS GIS Cut Line= 2
      2177233.28     13196409.49      2177760.85     13194771.24
#Sta/Elev= 30
  3873.9  464.05  3924.7  462.86  3960.7  460.42    3968  459.28  3973.2  460.19
  4139.3  453.69  4232.8  450.96  4380.9  447.35  4601.6  444.54  4689.4  442.62
  4716.1  442.25  4843.2  444.09  4881.7  443.34  4913.8  443.64  4951.1  442.57
  4990.3  443.04  5000.8  441.88  5012.2  439.25    5015  438.75  5018.2  439.25
  5021.8  440.41  5032.3  441.04  5072.2  442.48  5095.3  444.36  5137.4  445.57
  5143.5  446.52  5148.7  446.33  5180.8  448.61  5342.6  455.15    5595  464.69
#Mann= 8 ,-1 , 0
  3873.9      .1       0  3924.7     .05       0  4232.8      .1       0
  4689.4     .12       0  5012.2     .07       0  5018.2     .12       0
  5072.2      .1       0  5342.6     .05       0
#XS Ineff= 2 , 0
          4844.2  444.09
Permanent Ineff=
       F       F
Bank Sta=4601.6,5095.3
XS Rating Curve= 0 ,0
Exp/Cntr=0.3,0.1

Type RM Length L Ch R = 1 ,27967   ,496,496,496
BEGIN DESCRIPTION:
UNT 020 IN LACR 47.0
END DESCRIPTION:
XS GIS Cut Line= 3
      2177684.67     13196458.07      2177983.28     13195263.64
       2177830.5     13194826.14
#Sta/Elev= 30
  4009.2  468.84    4163   459.6  4329.1  451.57  4474.3  445.64  4525.8  445.27
  4567.1  443.94  4628.9  443.06  4680.5  442.87  4852.4  440.83  4896.9  439.39
  4958.8  441.07  4969.1  440.75  4984.6   436.8  4987.4   436.3  4990.6   436.8
    5000  440.59    5034  441.21  5061.8  442.76  5072.6  443.15  5082.5     443
  5123.7  445.03  5157.7  445.03  5193.8  446.15  5247.6  446.74  5424.3  452.66
  5485.3  454.12  5586.5  458.31  5650.1   459.9  5666.4  461.08  5703.8  462.11
#Mann= 7 ,-1 , 0
  4009.2     .05       0  4329.1      .1       0  4852.4     .12       0
  4984.6     .07       0  4990.6     .12       0  5072.6      .1       0
  5424.3     .05       0
#XS Ineff= 2 , 0
          4958.3  441.18
Permanent Ineff=
       F       F
Bank Sta=4680.5,5061.8
XS Rating Curve= 0 ,0
Exp/Cntr=0.3,0.1

Type RM Length L Ch R = 1 ,27471   ,482,482,482
BEGIN DESCRIPTION:
UNT 020 IN LACR 46.0
END DESCRIPTION:
XS GIS Cut Line= 3
      2177537.74     13196696.84      2178337.72     13195696.85
      2179537.73     13194596.84
#Sta/Elev= 30
  3719.4   480.1    3797  478.81    3805  477.74  3897.9  474.49  4110.8  463.52
  4160.4  462.05  4189.2  459.88  4363.7  452.34  4544.6  447.03  4615.8  443.98
  4743.9  441.54  4853.2  440.43  4978.4  438.76  4983.4  435.99  4986.1  435.49
  4989.4  435.99  4996.8  438.66  5013.9  439.68  5087.2  439.84  5122.1  440.41
  5226.6  440.85  5261.8  437.74  5283.3  440.38  5290.1  439.73  5325.6  441.53
  5495.8   445.7  5764.3  452.06  6111.5  455.26    6437  463.41  6627.9   469.5
#Mann= 8 ,-1 , 0
  3719.4     .05       0  4363.7      .1       0  4853.2     .12       0
  4983.4     .07       0  4989.4     .12       0  5087.2      .1       0
  5122.1     .12       0  5495.8      .1       0
#XS Ineff= 2 , 0
                         5224.15          440.89
Permanent Ineff=
       F       F
Bank Sta=4743.9,5325.6
XS Rating Curve= 0 ,0
Exp/Cntr=0.3,0.1

Type RM Length L Ch R = 1 ,26989   ,495,495,495
BEGIN DESCRIPTION:
UNT 020 IN LACR 45.0
END DESCRIPTION:
XS GIS Cut Line= 3
      2178087.75     13196596.82      2178637.72     13195996.85
      2179837.68     13194996.89
#Sta/Elev= 30
  4186.1  464.15  4525.5  452.12  4547.1  452.23  4709.9  445.86  4716.7  446.23
  4759.2  443.76  4858.5  440.27  4943.6  437.59  4968.9  434.56  4971.7  434.06
  4974.9  434.56  4978.7  436.55  4986.1  438.07  5014.2  438.59  5071.9  437.75
  5134.7  439.38  5276.6  440.23  5440.6  441.44  5689.3  445.03  5773.9  447.82
  5831.1  448.33  5937.2  451.88    5973  451.97  6057.6  455.66  6114.9   455.6
  6143.6  457.38  6262.2  461.42  6477.4  466.91  6534.1  469.62    6562  469.59
#Mann= 7 ,-1 , 0
  4186.1      .1       0  4968.9     .07       0  4974.9      .1       0
  5014.2     .12       0  5071.9      .1       0  6262.2     .05       0
  6477.4      .1       0
Bank Sta=4858.5,5276.6
XS Rating Curve= 0 ,0
Exp/Cntr=0.3,0.1

Type RM Length L Ch R = 1 ,26494   ,404,404,404
BEGIN DESCRIPTION:
UNT 020 IN LACR 44.0
END DESCRIPTION:
XS GIS Cut Line= 3
      2178387.73     13196746.85      2178987.72     13196346.85
      2180187.76     13196246.85
#Sta/Elev= 30
  4278.9  459.45  4502.7  450.77  4567.3  448.64  4574.8  449.14  4631.9  446.64
    4662  446.56  4706.6  444.48  4884.3  438.81  4931.9  437.11  4963.9   436.6
  4985.8  437.47  5002.5  437.02  5017.1  433.13  5019.8  432.63  5023.1  433.13
  5030.1  433.43  5042.9  436.12  5050.2  436.87  5100.3  435.54  5176.2  437.34
    5291  438.81  5366.1  441.65  5536.5  448.37  5561.9  448.42    5592   450.8
  5635.3  452.23  5780.2  454.75  5806.6  454.09  5973.4  457.58  6204.2  466.37
#Mann= 12 ,-1 , 0
  4278.9     .05       0  4706.6      .1       0  4931.9     .12       0
  4985.8     .16       0  5017.1     .07       0  5023.1     .16       0
  5042.9     .12       0  5176.2      .1       0  5366.1     .05       0
  5536.5     .08       0  5635.3     .05       0  5806.6      .1       0
Bank Sta=4884.3,5291
XS Rating Curve= 0 ,0
Exp/Cntr=0.3,0.1

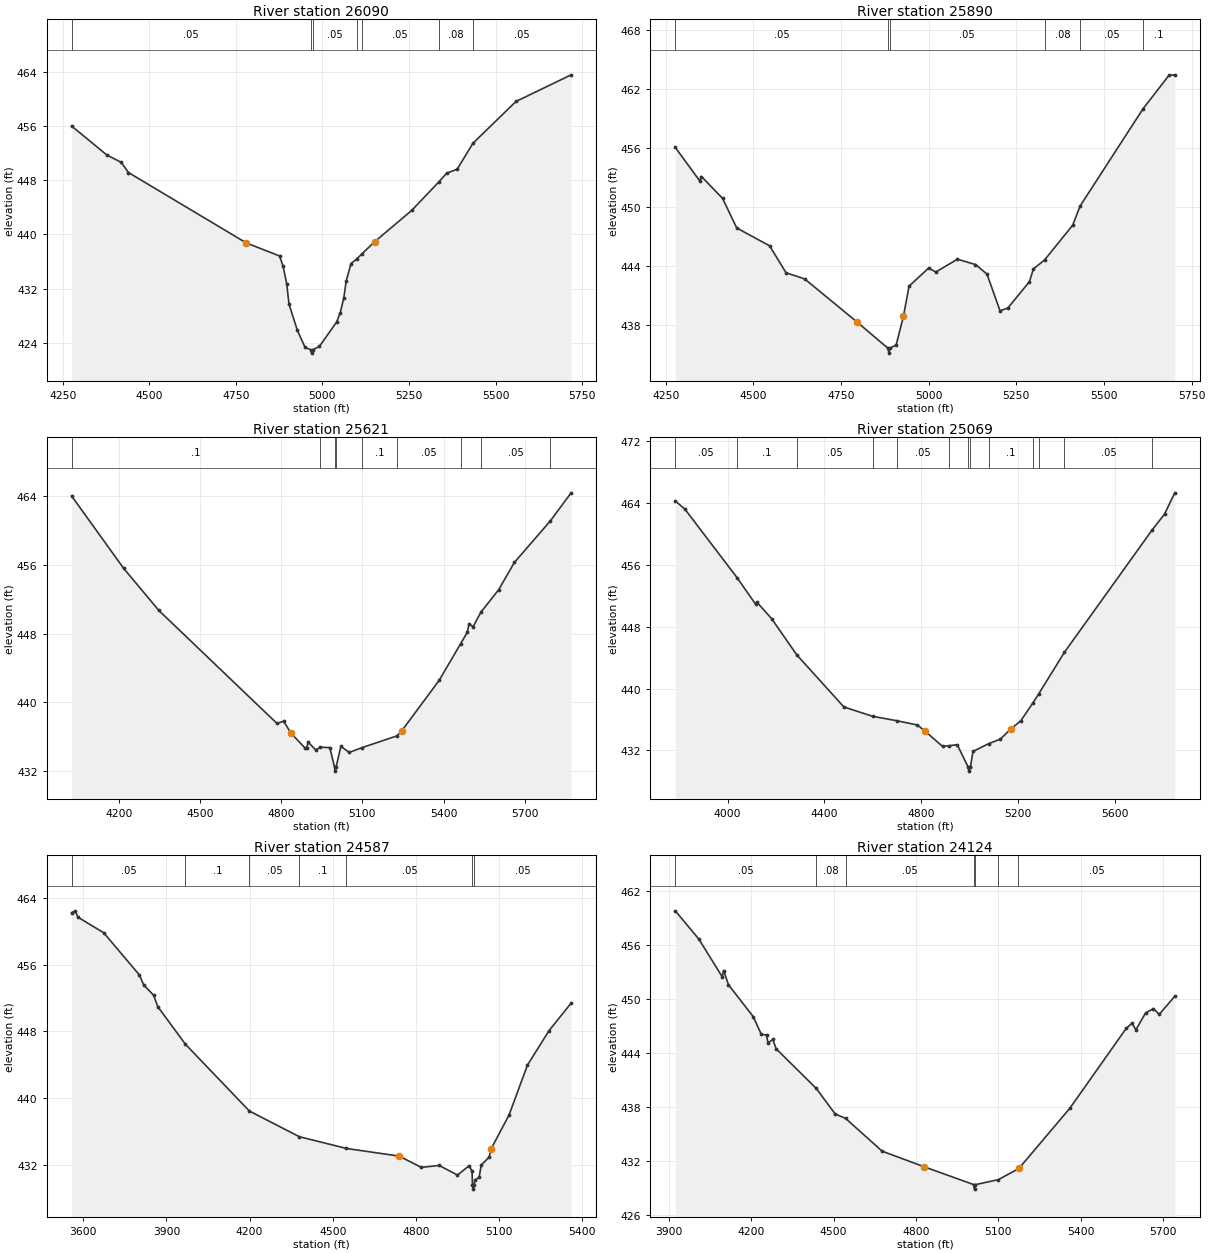
Type RM Length L Ch R = 1 ,26090   ,200,200,200
BEGIN DESCRIPTION:
UNT 020 IN LACR 43.0
END DESCRIPTION:
XS GIS Cut Line= 4
      2178490.72     13196804.75      2178914.44     13196677.22
      2179480.31     13196535.65        2179897.     13196535.65
#Sta/Elev= 30
  4275.8  455.96  4377.1  451.71  4418.9  450.61  4439.8  449.11    4780  438.73
  4876.3   436.8  4886.6  435.25  4896.9   432.7  4903.6  429.68  4927.8  425.81
    4950  423.31  4966.1  422.97  4968.8  422.47  4972.1  422.97  4991.2  423.45
  5041.2  427.07  5051.5  428.43  5061.8  430.62  5068.5  433.06  5082.5  435.67
  5098.5  436.35    5113  437.05  5150.9  438.91  5257.7  443.51  5336.7  447.75
    5359  449.02    5389  449.59  5434.8  453.43    5559  459.59  5718.3  463.52
#Mann= 7 ,-1 , 0
  4275.8     .05       0  4966.1     .03       0  4972.1     .05       0
  5098.5      .1       0    5113     .05       0  5336.7     .08       0
  5434.8     .05       0
Bank Sta=4780,5150.9
XS Rating Curve= 0 ,0
Exp/Cntr=0.3,0.1

Type RM Length L Ch R = 1 ,25890   ,269,269,269
BEGIN DESCRIPTION:
Mapping XS 2ed1d341
END DESCRIPTION:
XS GIS Cut Line= 3
      2178473.38     13196908.91      2178985.52     13196856.83
      2179870.96     13196648.49
#Sta/Elev= 30
  4277.5  456.08  4347.2  452.68  4352.2  453.12  4412.5  450.89  4452.7  447.89
  4546.6  446.07  4593.5  443.33  4646.3  442.71    4796  438.32    4884  435.66
  4886.7  435.16    4890  435.66  4907.5     436  4928.1  438.89  4944.2  441.97
    5000  443.81  5020.5  443.41  5082.2  444.71  5133.6  444.17  5166.4   443.2
  5203.6  439.46    5226  439.75  5287.6  442.43  5298.7  443.72  5330.5  444.63
  5410.9  448.17    5432  450.12  5611.1  459.99  5685.2   463.4  5701.9  463.46
#Mann= 6 ,-1 , 0
  4277.5     .05       0    4884     .03       0    4890     .05       0
  5330.5     .08       0    5432     .05       0  5611.1      .1       0
Bank Sta=4796,4928.1
XS Rating Curve= 0 ,0
Exp/Cntr=0.3,0.1

Type RM Length L Ch R = 1 ,25621   ,552,552,552
BEGIN DESCRIPTION:
UNT 020 IN LACR 42.0
END DESCRIPTION:
XS GIS Cut Line= 4
      2178221.62     13197186.69      2178970.81     13197128.78
       2179619.2     13196978.36      2179983.25     13196752.99
#Sta/Elev= 30
  4025.9  464.01    4218  455.59  4348.1  450.69  4784.4  437.54    4809   437.8
  4835.8  436.42  4887.1  434.71  4894.3  434.67  4899.5  435.37  4928.1  434.44
  4943.5  434.77  4979.5  434.73    4997  432.49  4999.7  431.99    5003  432.49
  5020.5  434.88  5051.3  434.16    5098  434.72  5227.4  436.09  5245.9   436.7
  5384.1  442.58    5463  446.83  5487.8  448.16  5493.7   449.1  5509.1  448.81
  5537.8  450.49  5603.6  453.11  5661.5  456.28  5793.7  461.09  5871.1  464.38
#Mann= 9 ,-1 , 0
  4025.9      .1       0  4943.5     .12       0    4997     .07       0
    5003     .12       0    5098      .1       0  5227.4     .05       0
    5463     .08       0  5537.8     .05       0  5793.7      .1       0
Bank Sta=4835.8,5245.9
XS Rating Curve= 0 ,0
Exp/Cntr=0.3,0.1

Type RM Length L Ch R = 1 ,25069   ,482,482,482
BEGIN DESCRIPTION:
UNT 020 IN LACR 41.0
END DESCRIPTION:
XS GIS Cut Line= 3
      2178287.67     13197646.86      2179487.72     13197446.85
       2180087.7     13196846.87
#Sta/Elev= 30
  3783.4   464.3    3824   463.2  4039.7  454.32  4115.5  450.92  4120.5   451.2
  4181.4  449.06  4286.1  444.35  4480.4  437.62  4600.2   436.4  4700.2  435.83
  4784.6  435.28  4817.5  434.45  4888.5  432.51  4913.1  432.59  4949.3  432.73
  4994.5  429.81  4997.2  429.31  5000.5  429.81  5003.5  429.81  5014.1  431.86
  5078.8  432.86  5127.3  433.45  5169.7  434.74  5212.1  435.84    5263  438.18
  5286.5  439.34  5392.4   444.7  5755.6  460.56  5806.1  462.58  5848.5  465.34
#Mann= 13 ,-1 , 0
  3783.4     .05       0  4039.7      .1       0  4286.1     .05       0
  4600.2      .1       0  4700.2     .05       0  4913.1     .12       0
  4994.5     .07       0  5000.5     .12       0  5078.8      .1       0
    5263     .05       0  5286.5      .1       0  5392.4     .05       0
  5755.6      .1       0
Bank Sta=4817.5,5169.7
XS Rating Curve= 0 ,0
Exp/Cntr=0.3,0.1

Type RM Length L Ch R = 1 ,24587   ,463,463,463
BEGIN DESCRIPTION:
UNT 020 IN LACR 40.0
END DESCRIPTION:
XS GIS Cut Line= 3
      2178537.74     13198596.84      2179737.72     13197796.85
      2180037.76     13197596.83
#Sta/Elev= 30
  3557.8  462.25  3571.3  462.47  3580.3  461.71  3673.5  459.84  3802.7  454.76
  3817.7  453.59  3853.7  452.34  3868.8  450.97  3968.6  446.46  4199.3  438.45
  4379.5  435.37  4549.8  433.96  4740.1  433.04  4819.7  431.69  4884.3  431.92
  4950.4  430.77  4992.5  431.89    5003  431.22  5004.5  429.58  5007.3  429.08
  5010.5  429.58  5013.5  430.17  5028.5  430.49  5036.1  431.97  5064.6  432.92
  5072.1  433.93  5136.7  437.99  5202.8  443.95  5280.9   448.1  5360.6   451.4
#Mann= 7 ,-1 , 0
  3557.8     .05       0  3968.6      .1       0  4199.3     .05       0
  4379.5      .1       0  4549.8     .05       0  5004.5     .03       0
  5010.5     .05       0
Bank Sta=4740.1,5072.1
XS Rating Curve= 0 ,0
Exp/Cntr=0.3,0.1

Type RM Length L Ch R = 1 ,24124   ,491,491,491
BEGIN DESCRIPTION:
UNT 020 IN LACR 39.0
END DESCRIPTION:
XS GIS Cut Line= 3
      2178687.75     13198596.84      2179687.72     13198196.85
      2180237.72     13197696.86
#Sta/Elev= 30
    3923  459.79  4009.1  456.65  4093.9  452.48  4099.3  453.17  4116.8  451.59
    4207  448.06  4236.7  446.08  4255.5  446.02  4260.9  445.14  4278.4  445.52
  4290.5  444.49  4436.6   440.1  4505.9  437.25  4543.6  436.77  4676.9  433.13
    4829  431.41  5010.9  429.42  5013.6  428.92  5016.9  429.42  5100.1  429.97
  5172.4  431.16  5176.7  431.26  5361.2   437.9  5566.6  446.76  5587.5  447.32
  5601.7   446.6  5636.9  448.46  5665.3  448.94  5686.9  448.31  5743.3  450.31
#Mann= 7 ,-1 , 0
    3923     .05       0  4436.6     .08       0  4543.6     .05       0
  5010.9     .03       0  5016.9     .05       0  5100.1      .1       0
  5172.4     .05       0
Bank Sta=4829,5176.7
XS Rating Curve= 0 ,0
Exp/Cntr=0.3,0.1

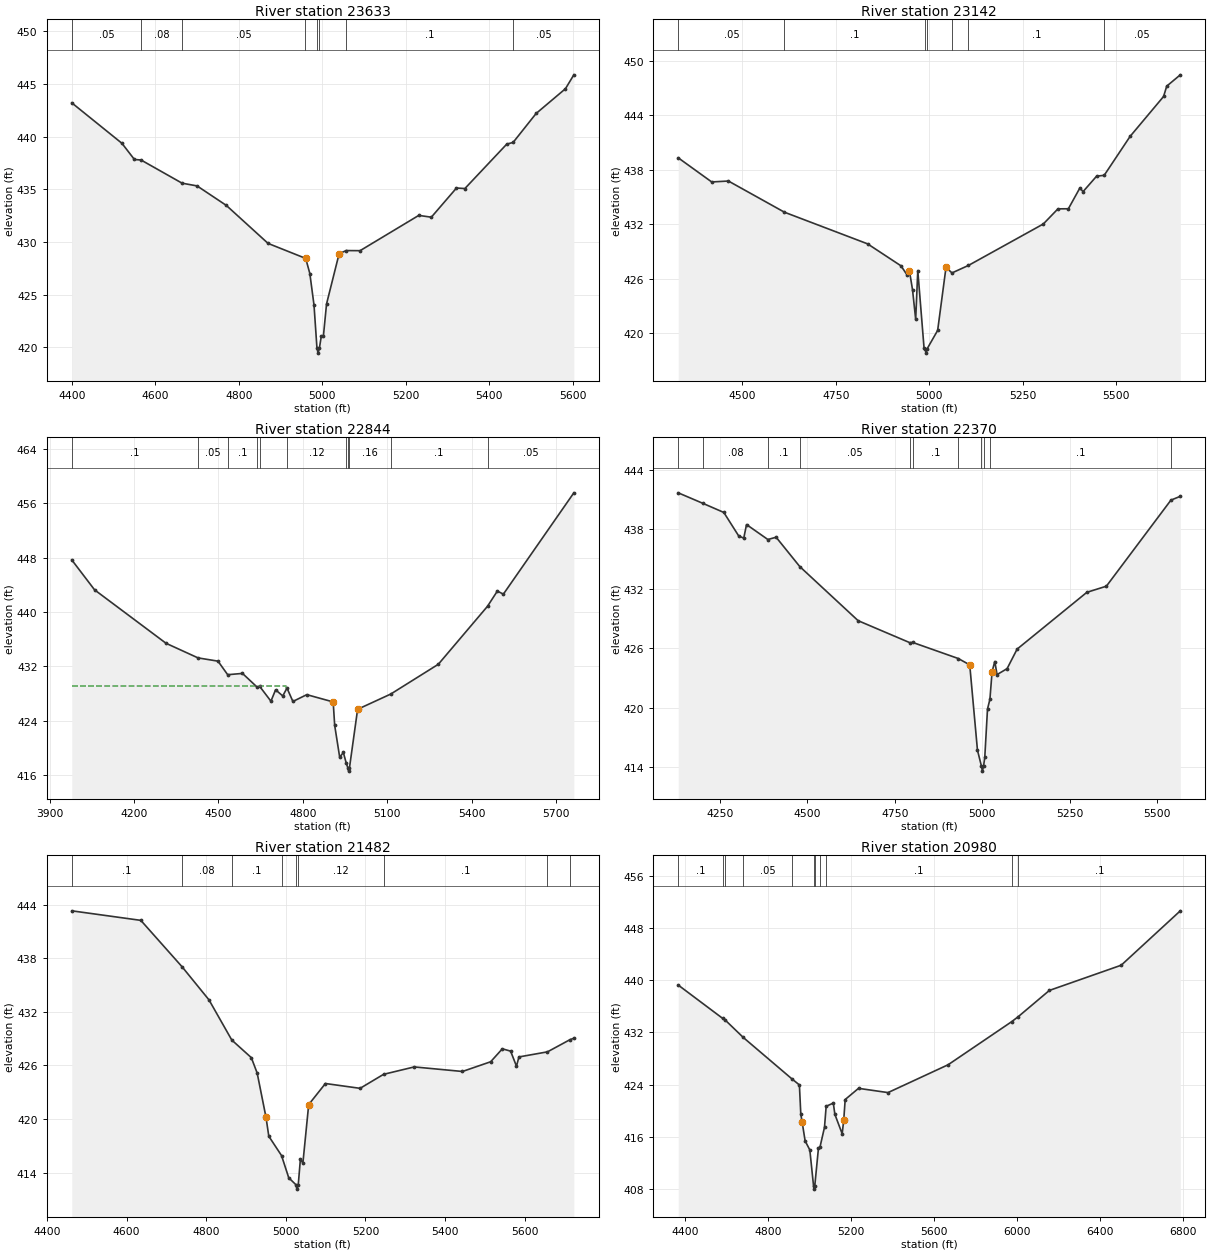
Type RM Length L Ch R = 1 ,23633   ,491,491,491
BEGIN DESCRIPTION:
UNT 020 IN LACR 38.0
END DESCRIPTION:
XS GIS Cut Line= 3
      2179187.72     13198646.85      2179787.72     13198646.85
      2180387.74     13198596.85
#Sta/Elev= 30
    4400  443.22    4520  439.38    4550  437.84  4565.9  437.79  4664.1  435.59
    4700  435.33    4770  433.48    4870  429.87  4958.5  428.47    4960  428.46
    4970  427.01    4980  424.01    4987  419.95  4989.7  419.45    4993  419.95
  4997.5  421.08  5002.5  421.08    5010  424.12  5040.1  428.89    5057  429.19
  5090.3  429.18  5230.8  432.53  5260.9  432.36  5321.1  435.13  5341.2  435.08
  5441.5   439.3  5456.7  439.46  5511.8  442.21    5582  444.56  5602.1  445.88
#Mann= 8 ,-1 , 0
    4400     .05       0  4565.9     .08       0  4664.1     .05       0
  4958.5     .12       0    4987     .07       0    4993     .12       0
    5057      .1       0  5456.7     .05       0
Bank Sta=4960,5040.1
XS Rating Curve= 0 ,0
Exp/Cntr=0.3,0.1

Type RM Length L Ch R = 1 ,23142   ,298,298,298
BEGIN DESCRIPTION:
UNT 020 IN LACR 37.0
END DESCRIPTION:
XS GIS Cut Line= 3
      2179287.74     13198796.86      2179887.72     13199096.85
       2180487.7     13198796.86
#Sta/Elev= 30
  4329.2  439.32  4418.6  436.66  4463.3  436.76    4613  433.32  4835.1  429.83
  4924.5   427.4  4941.3  426.36  4946.9  426.87  4955.3  424.75  4963.7  421.49
  4969.3  426.88    4986  418.36  4988.6  418.27  4991.4  417.77  4994.6  418.27
  5022.4  420.28  5044.7  427.23  5060.7  426.62  5104.8  427.45  5304.7  432.02
  5343.8  433.69  5371.7   433.7  5402.5     436  5410.9  435.59  5447.2   437.3
  5467.4  437.39  5536.7  441.69  5626.1  446.09  5634.5  447.23  5670.8  448.48
#Mann= 7 ,-1 , 0
  4329.2     .05       0    4613      .1       0  4988.6     .07       0
  4994.6      .1       0  5060.7     .16       0  5104.8      .1       0
  5467.4     .05       0
Bank Sta=4946.9,5044.7
XS Rating Curve= 0 ,0
Exp/Cntr=0.3,0.1

Type RM Length L Ch R = 1 ,22844   ,474,474,474
BEGIN DESCRIPTION:
UNT 020 IN LACR 36.0
END DESCRIPTION:
XS GIS Cut Line= 3
      2179101.35     13199666.42      2180399.95     13199201.14
      2180747.21     13198992.79
#Sta/Elev= 30
  3978.7  447.65  4059.8  443.25  4313.9   435.4  4427.4  433.26  4498.4  432.78
  4532.8  430.79  4585.4  430.98  4638.2  428.94  4646.3  429.09  4686.5   426.9
  4703.1  428.57  4728.6  427.67  4743.6  428.83  4764.6  426.86    4814  427.86
  4907.8  426.79  4913.1  423.35  4930.9  418.67  4943.9  419.37  4954.4  417.78
  4959.7  417.13  4962.5  416.63  4965.7  417.13  4994.6  425.71  5112.4  427.95
  5281.4  432.32  5456.3  440.84  5491.2  443.07  5512.6  442.62  5763.1   457.5
#Mann= 11 ,-1 , 0
  3978.7      .1       0  4427.4     .05       0  4532.8      .1       0
  4638.2     .12       0  4646.3     .08       0  4743.6     .12       0
  4954.4     .16       0  4959.7     .07       0  4965.7     .16       0
  5112.4      .1       0  5456.3     .05       0
#XS Ineff= 2 , 0
         4740.06  429.15
Permanent Ineff=
       F       F
Bank Sta=4907.8,4994.6
XS Rating Curve= 0 ,0
Exp/Cntr=0.3,0.1

Type RM Length L Ch R = 1 ,22370   ,888,888,888
BEGIN DESCRIPTION:
UNT 020 IN LACR 35.0
END DESCRIPTION:
XS GIS Cut Line= 2
      2179587.46     13200270.57      2180691.64      13199353.9
#Sta/Elev= 30
  4130.8  441.68  4201.2  440.62  4261.1   439.7  4303.8  437.32  4318.1  437.11
    4326  438.48    4387  436.97  4410.6   437.2  4478.2  434.24    4645  428.78
  4792.8  426.56  4800.6  426.59  4931.4  424.96    4964  424.32  4986.1  415.71
  4997.5   414.1  5000.2   413.6  5003.5   414.1    5007  414.99  5014.8  419.87
  5021.7  420.85  5027.9  423.65  5035.6  424.66  5042.1  423.34  5070.8  423.94
  5099.4  425.91  5298.7  431.64  5354.6  432.26    5539  440.94  5565.9  441.33
#Mann= 11 ,-1 , 0
  4130.8      .1       0  4201.2     .08       0    4387      .1       0
  4478.2     .05       0  4792.8     .08       0  4800.6      .1       0
  4931.4     .12       0  4997.5     .07       0  5003.5     .12       0
  5021.7      .1       0    5539     .08       0
Bank Sta=4964,5027.9
XS Rating Curve= 0 ,0
Exp/Cntr=0.3,0.1

Type RM Length L Ch R = 1 ,21482   ,502,502,502
BEGIN DESCRIPTION:
UNT 020 IN LACR 34.0
END DESCRIPTION:
XS GIS Cut Line= 2
      2179955.52     13200756.69      2180969.38     13200006.71
#Sta/Elev= 30
  4462.4  443.34  4635.9  442.27  4739.6  437.06    4807  433.36  4864.4  428.85
  4913.4  426.88  4928.1  425.15  4950.2  420.21  4957.3  418.07  4989.3   415.9
  5007.4  413.41  5025.3  412.64    5028  412.14  5031.3  412.64  5036.7  415.52
  5042.9  415.05  5057.5  421.62  5099.5  423.98  5186.6  423.44  5245.6  425.01
  5322.6  425.84  5443.7  425.33  5514.6  426.42  5543.9  427.87  5564.7  427.61
  5579.4  425.92  5585.6  426.96  5657.3  427.53  5712.7  428.87  5723.5  429.06
#Mann= 9 ,-1 , 0
  4462.4      .1       0  4739.6     .08       0  4864.4      .1       0
  4989.3     .12       0  5025.3     .07       0  5031.3     .12       0
  5245.6      .1       0  5657.3     .05       0  5712.7      .1       0
Bank Sta=4950.2,5057.5
XS Rating Curve= 0 ,0
Exp/Cntr=0.3,0.1

Type RM Length L Ch R = 1 ,20980   ,523,523,523
BEGIN DESCRIPTION:
UNT 020 IN LACR 33.0
END DESCRIPTION:
XS GIS Cut Line= 3
      2180183.46     13201171.05      2180956.01     13200580.79
      2181954.28     13199530.43
#Sta/Elev= 30
  4365.4  439.25    4579  434.17  4589.2  433.98  4679.2  431.23  4913.9  424.89
  4949.7  423.97  4956.5  419.48  4962.8  418.33  4977.3  415.41    5000  414.02
  5017.9  408.53  5020.6  408.03  5023.9  408.53  5041.7  414.33  5048.6  414.41
  5070.8   417.5  5078.8   420.7  5113.3   421.2  5120.7  419.48    5156   416.5
  5163.6  418.62  5170.5  421.74  5234.9  423.45    5377   422.8    5667  427.06
    5973  433.64  6004.9  434.41  6155.2  438.43  6501.8  442.29  6786.7  450.61
#Mann= 11 ,-1 , 0
  4365.4      .1       0    4579     .05       0  4589.2     .08       0
  4679.2     .05       0  4913.9      .1       0  5017.9     .07       0
  5023.9      .1       0  5048.6     .12       0  5078.8      .1       0
    5973     .08       0  6004.9      .1       0
Bank Sta=4962.8,5163.6
XS Rating Curve= 0 ,0
Exp/Cntr=0.3,0.1

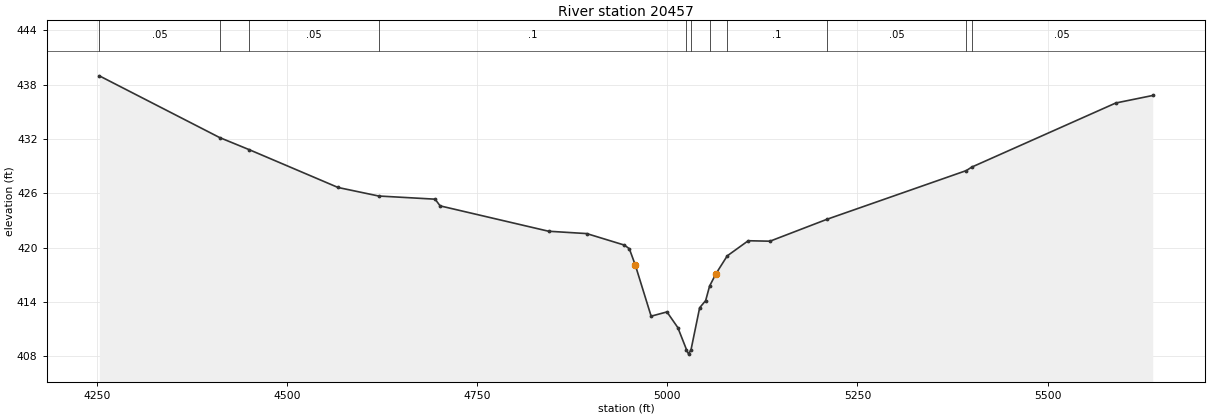
Type RM Length L Ch R = 1 ,20457   ,486,486,486
BEGIN DESCRIPTION:
UNT 020 IN LACR 32.0
END DESCRIPTION:
XS GIS Cut Line= 2
      2180531.93     13201492.78      2181600.76     13200611.34
#Sta/Elev= 30
  4252.9  438.97  4411.2  432.15  4450.2  430.81  4566.9  426.64  4620.2   425.7
  4694.5  425.35  4701.1  424.61  4843.7  421.81  4893.9  421.55  4943.4  420.28
  4949.9  419.88  4957.8  418.07  4978.6  412.43  4999.4   412.9  5013.7  411.17
  5025.1  408.74  5027.8  408.24  5031.1  408.74  5042.4  413.36  5050.3  414.15
  5055.5  415.76    5064  417.14  5078.7  419.09  5106.3  420.76  5134.9  420.71
  5209.9  423.13  5393.2  428.51  5400.2  428.89  5589.7  435.97  5638.3   436.8
#Mann= 11 ,-1 , 0
  4252.9     .05       0  4411.2     .08       0  4450.2     .05       0
  4620.2      .1       0  5025.1     .07       0  5031.1      .1       0
  5055.5     .12       0  5078.7      .1       0  5209.9     .05       0
  5393.2      .1       0  5400.2     .05       0
Bank Sta=4957.8,5064
XS Rating Curve= 0 ,0
Exp/Cntr=0.3,0.1