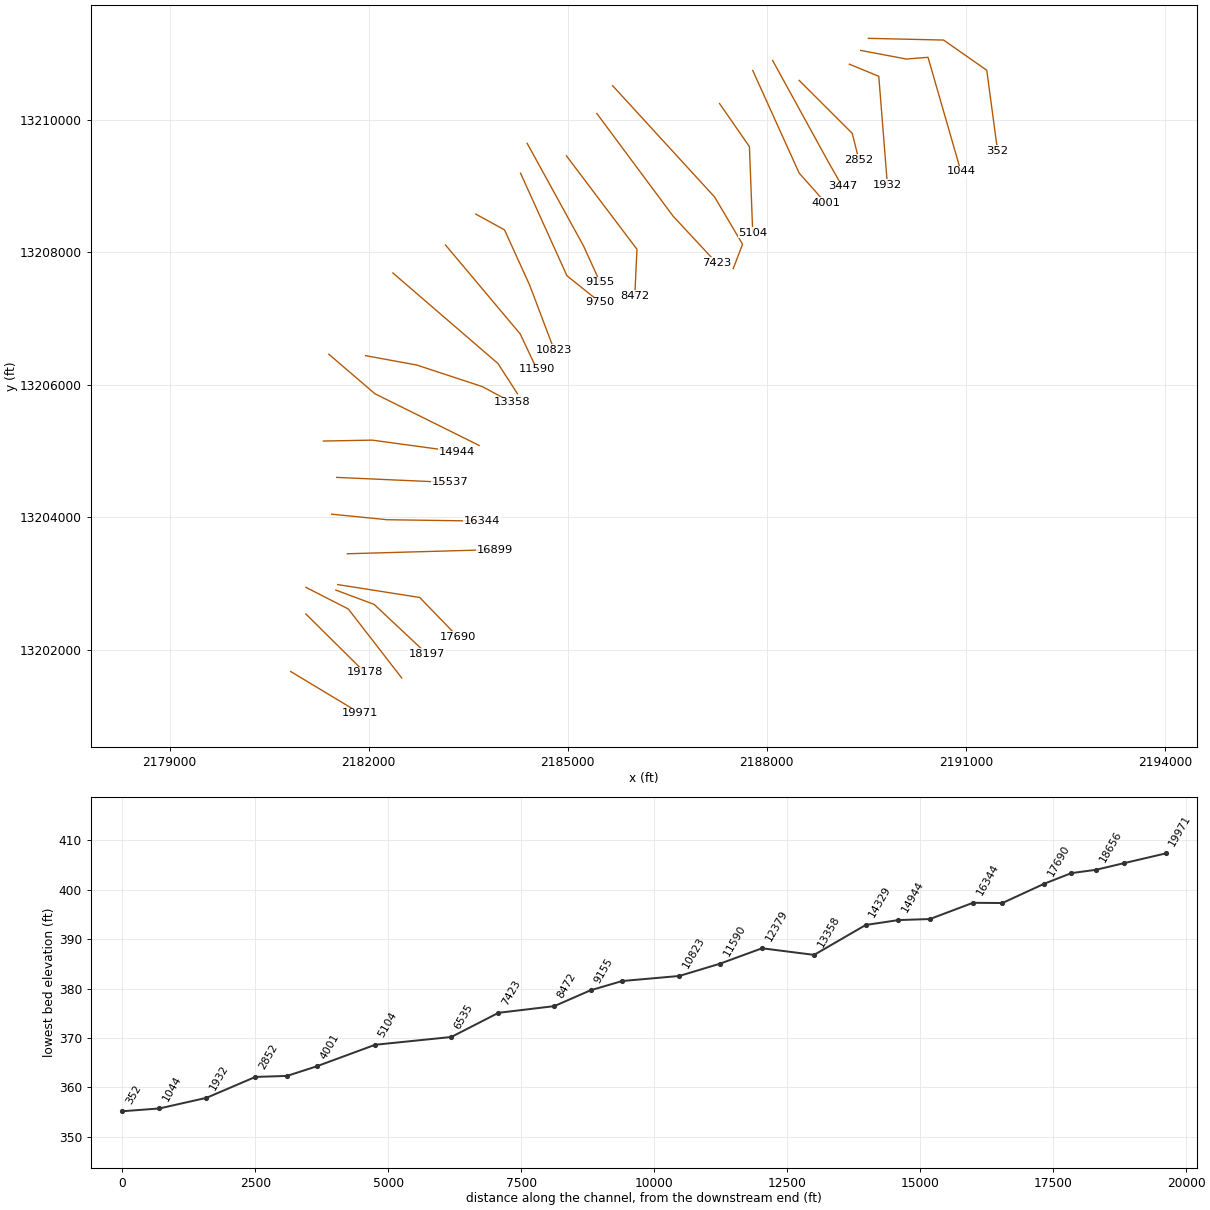
HEC-RAS study UNT 020 IN LACR.prj: UNT 020 IN LACR Base Level Engineering

--- UNT 020 IN LACR.g01 (geometry) --- (continued)

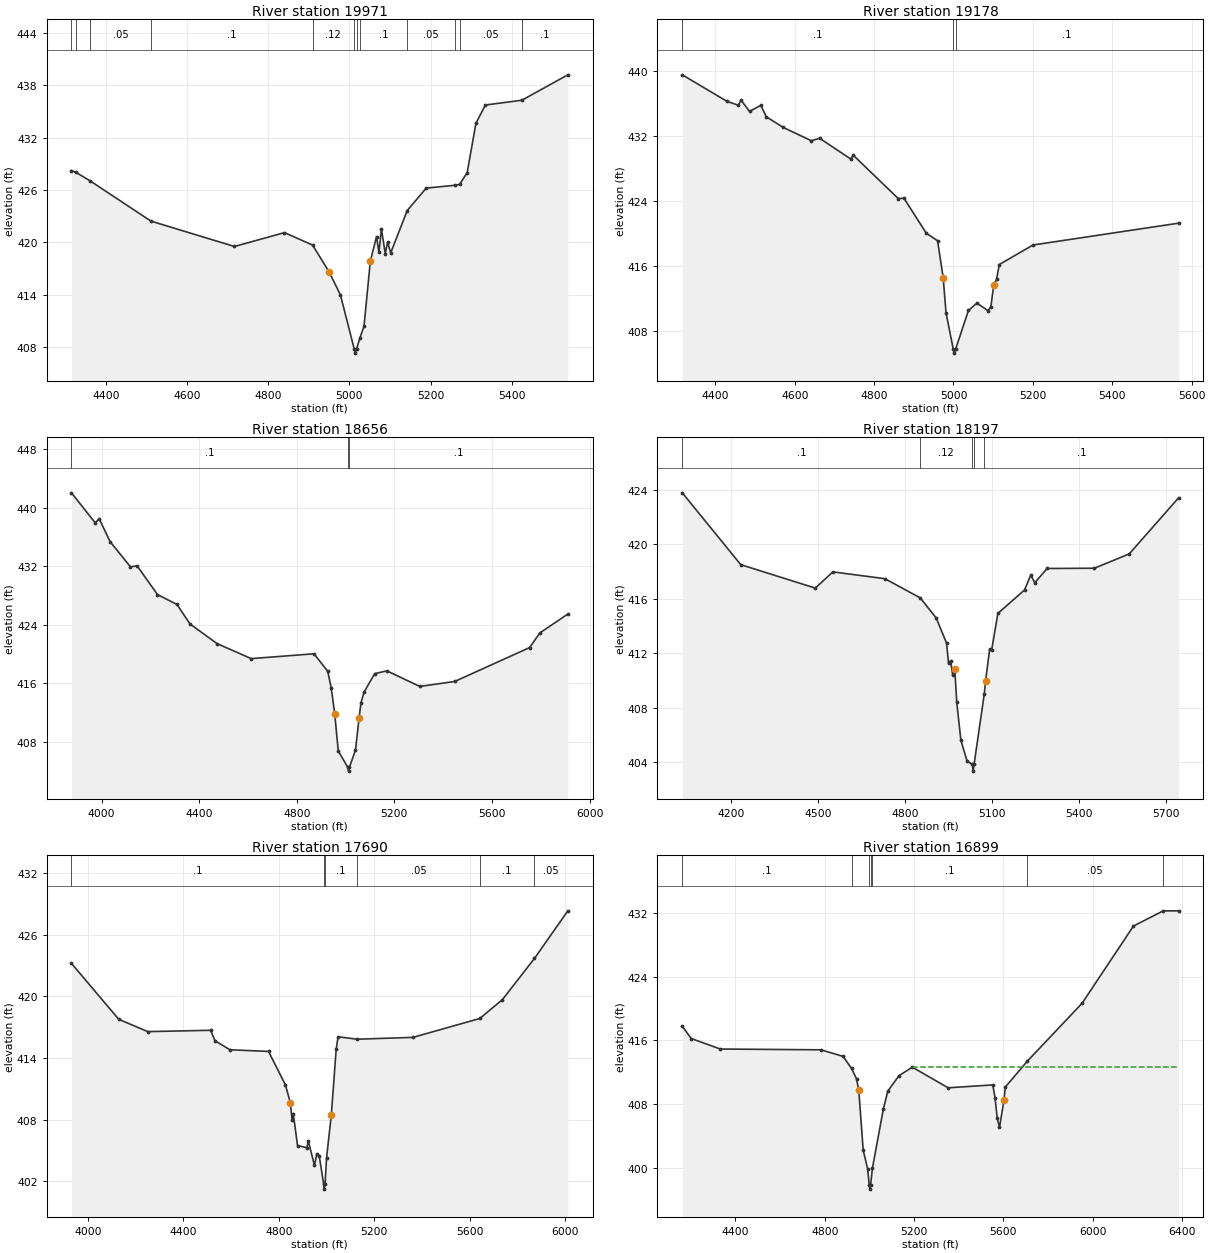
Type RM Length L Ch R = 1 ,19971   ,793,793,793
BEGIN DESCRIPTION:
UNT 020 IN LACR 31.0
END DESCRIPTION:
XS GIS Cut Line= 2
      2180823.55     13201673.37      2181871.81     13201041.64
#Sta/Elev= 30
  4314.7  428.24  4325.7  428.03  4360.3  427.07  4510.5  422.45  4716.5  419.54
  4839.9  421.13  4909.2   419.7    4950  416.62  4977.8     414  5011.7  407.82
  5014.4  407.32  5017.7  407.82  5025.9  409.06    5036  410.39  5051.6  417.86
  5066.8  420.66  5072.9  418.87  5078.8  421.56  5088.4  418.73  5094.3  420.05
  5101.8  418.81  5142.6  423.66  5189.4  426.23  5259.3  426.55  5271.5  426.65
  5290.4     428    5312  433.66  5335.3  435.75  5425.2   436.3  5538.6  439.21
#Mann= 12 ,-1 , 0
  4314.7     .05       0  4325.7     .08       0  4360.3     .05       0
  4510.5      .1       0  4909.2     .12       0  5011.7     .07       0
  5017.7     .12       0  5025.9      .1       0  5142.6     .05       0
  5259.3      .1       0  5271.5     .05       0  5425.2      .1       0
Bank Sta=4950,5051.6
XS Rating Curve= 0 ,0
Exp/Cntr=0.3,0.1

Type RM Length L Ch R = 1 ,19178   ,522,522,522
BEGIN DESCRIPTION:
UNT 020 IN LACR 29.0
END DESCRIPTION:
XS GIS Cut Line= 2
      2181052.73     13202541.41      2181940.43     13201660.65
#Sta/Elev= 30
  4316.8  439.59  4429.6  436.32  4457.9  435.85  4464.9  436.47  4486.2  435.09
  4514.5  435.83  4528.6  434.42    4571  433.12  4641.8  431.48  4662.9  431.78
  4740.7  429.24  4747.8  429.68  4860.9  424.36  4875.1  424.41  4931.6  420.09
  4959.9  419.17  4974.1  414.61  4981.2  410.32  4999.4  405.83  5002.1  405.33
  5005.4  405.83  5037.7  410.58  5058.9  411.49  5087.2  410.55  5094.3  411.06
  5101.4  413.71  5108.5  414.42  5115.5  416.24  5200.4  418.64  5567.3  421.33
#Mann= 3 ,-1 , 0
  4316.8      .1       0  4999.4     .07       0  5005.4      .1       0
Bank Sta=4974.1,5101.4
XS Rating Curve= 0 ,0
Exp/Cntr=0.3,0.1

Type RM Length L Ch R = 1 ,18656   ,459,459,459
BEGIN DESCRIPTION:
UNT 020 IN LACR 28.0
END DESCRIPTION:
XS GIS Cut Line= 3
      2181052.69     13202944.22      2181691.61     13202617.81
      2182497.18     13201576.13
#Sta/Elev= 30
  3876.8  442.02  3973.9  437.93  3990.5  438.47  4034.9  435.36  4118.2  431.92
    4146  432.04  4229.3  428.12  4309.2  426.77  4362.6   424.1  4473.7  421.42
  4613.4  419.37  4870.6  420.03  4926.7  417.65  4941.2  415.39  4955.7   411.8
  4970.2  406.75  5009.6   404.5  5012.4     404  5015.6   404.5  5040.8  406.88
  5055.3  411.22  5063.2  413.34  5076.1  414.81  5119.6  417.32  5169.4   417.7
  5304.3  415.57  5447.4  416.25  5754.4  420.88  5796.4  422.88  5911.1  425.46
#Mann= 3 ,-1 , 0
  3876.8      .1       0  5009.6     .07       0  5015.6      .1       0
Bank Sta=4955.7,5055.3
XS Rating Curve= 0 ,0
Exp/Cntr=0.3,0.1

Type RM Length L Ch R = 1 ,18197   ,507,507,507
BEGIN DESCRIPTION:
UNT 020 IN LACR 27.0
END DESCRIPTION:
XS GIS Cut Line= 3
      2181504.13     13202902.52       2182080.5     13202687.25
      2182879.09     13201937.28
#Sta/Elev= 30
  4032.7  423.79  4234.3  418.51  4491.1  416.79  4551.7  417.98  4731.1  417.48
  4852.9  416.07  4907.9  414.59  4943.5  412.75  4950.4  411.25  4957.7  411.46
  4964.6   410.4  4971.9  410.82  4978.7  408.39  4992.9  405.61  5014.4  404.07
  5032.4  403.84  5035.1  403.34  5038.4  403.84  5073.4  408.98  5077.9  409.94
    5092   412.3  5098.9  412.22  5120.4  414.93  5212.2  416.65  5233.7  417.74
  5247.8  417.18  5289.9  418.23    5453  418.25  5573.1   419.3  5743.5  423.43
#Mann= 5 ,-1 , 0
  4032.7      .1       0  4852.9     .12       0  5032.4     .07       0
  5038.4     .12       0  5073.4      .1       0
Bank Sta=4971.9,5077.9
XS Rating Curve= 0 ,0
Exp/Cntr=0.3,0.1

Type RM Length L Ch R = 1 ,17690   ,791,791,791
BEGIN DESCRIPTION:
UNT 020 IN LACR 26.0
END DESCRIPTION:
XS GIS Cut Line= 3
       2181531.9     13202985.86        2182768.     13202791.42
      2183343.56     13202195.06
#Sta/Elev= 30
  3931.2  423.22  4129.4  417.77  4250.9  416.57  4514.1   416.7  4532.7  415.68
  4595.1   414.8    4757  414.64  4827.9  411.37  4848.2  409.65  4855.6     408
  4860.6  408.58  4878.5  405.46  4918.1  405.25  4923.2  405.95  4949.4  403.52
  4959.5  404.67  4969.6  404.43  4987.8  401.71  4990.5  401.21  4993.8  401.71
    5000  404.23  5020.2  408.47  5040.5  414.84  5048.3  416.07  5128.2  415.83
  5362.3  416.01  5642.3  417.85  5737.1  419.69  5871.5  423.71  6011.3  428.35
#Mann= 6 ,-1 , 0
  3931.2      .1       0  4987.8     .07       0  4993.8      .1       0
  5128.2     .05       0  5642.3      .1       0  5871.5     .05       0
Bank Sta=4848.2,5020.2
XS Rating Curve= 0 ,0
Exp/Cntr=0.3,0.1

Type RM Length L Ch R = 1 ,16899   ,555,555,555
BEGIN DESCRIPTION:
UNT 020 IN LACR 24.0
END DESCRIPTION:
XS GIS Cut Line= 2
      2181677.71     13203451.14      2183899.93     13203513.64
#Sta/Elev= 30
  4161.8  417.75  4201.8  416.21  4331.9  414.89  4782.1  414.79  4882.1  413.97
  4919.7  412.45  4942.1  411.15  4952.1  409.75  4972.1  402.17  4992.1  399.82
  4999.1  397.79  5001.9  397.29  5005.1  397.79  5013.4  399.94  5062.2  407.34
  5082.2   409.6  5132.2  411.54  5192.2  412.61  5352.3  410.02  5552.4  410.38
  5562.4  408.79  5572.4   406.2  5582.4  405.04  5602.4  408.45  5608.6  410.12
  5707.7  413.38  5952.5  420.64  6182.6  430.34  6315.3  432.24  6384.9  432.25
#Mann= 7 ,-1 , 0
  4161.8      .1       0  4919.7     .12       0  4999.1     .07       0
  5005.1     .12       0  5013.4      .1       0  5707.7     .05       0
  6315.3      .1       0
#XS Ineff= 2 , 0
                         5191.76          412.62
Permanent Ineff=
       F       F
Bank Sta=4952.1,5602.4
XS Rating Curve= 0 ,0
Exp/Cntr=0.3,0.1

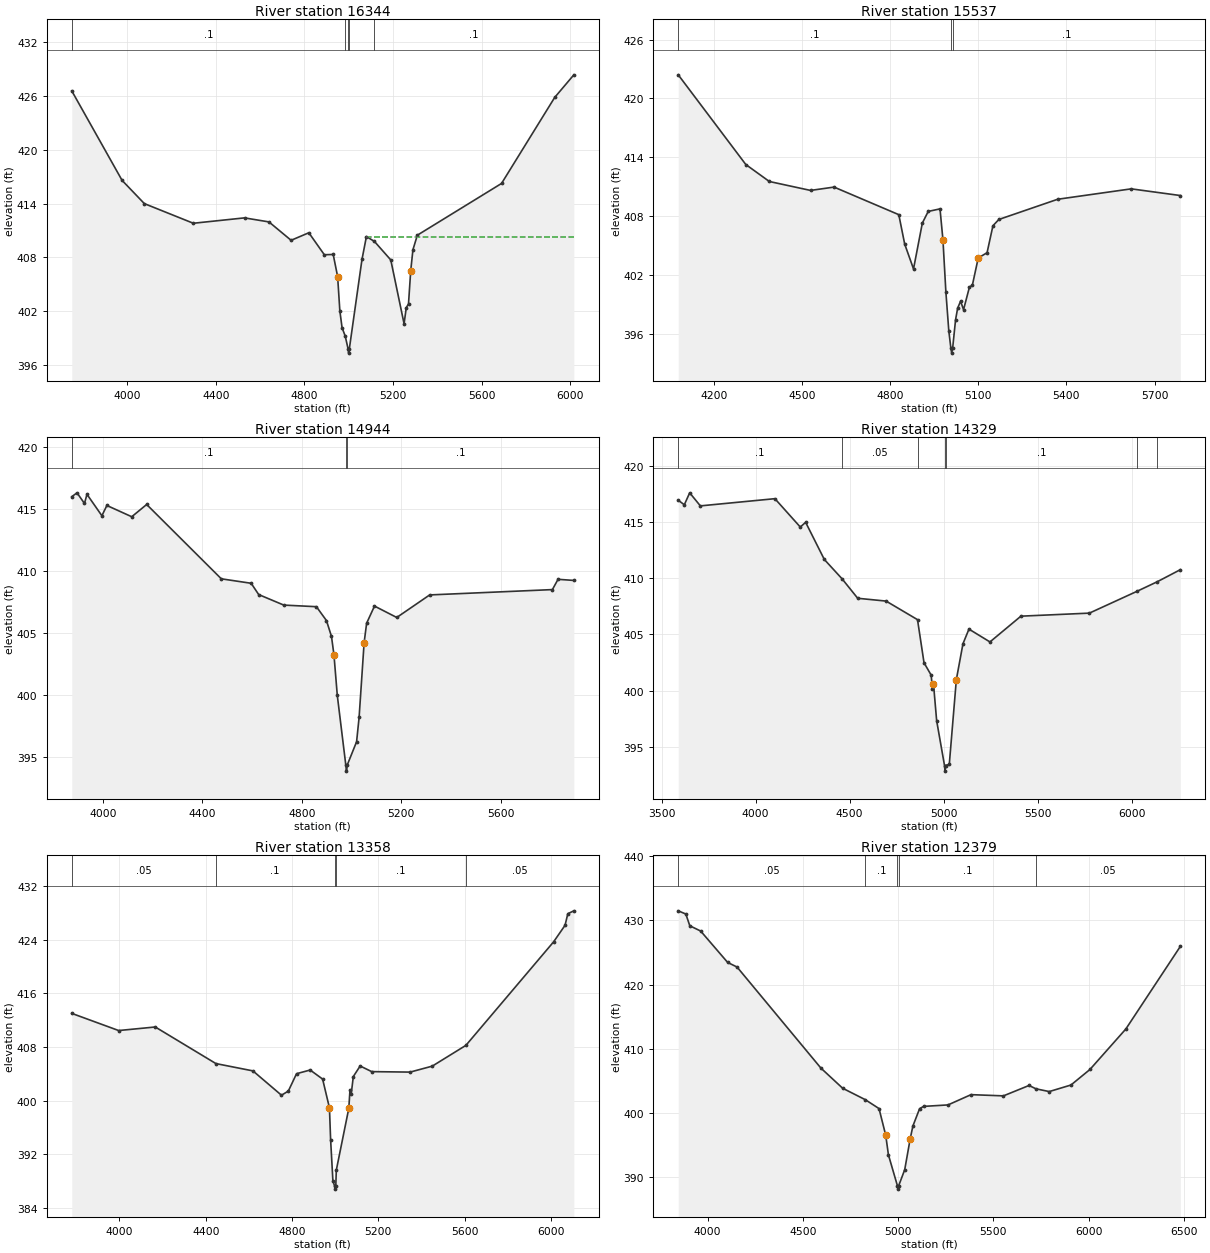
Type RM Length L Ch R = 1 ,16344   ,807,807,807
BEGIN DESCRIPTION:
UNT 020 IN LACR 23.0
END DESCRIPTION:
XS GIS Cut Line= 3
      2181441.62     13204048.37      2182274.95     13203965.03
      2183704.11     13203944.22
#Sta/Elev= 30
  3749.7  426.57  3976.9  416.59  4077.4     414  4298.5  411.81  4529.7  412.41
    4640  411.96    4740  409.91    4820  410.75    4890   408.3    4930  408.33
    4950  405.87    4960  402.05    4970  400.17  4984.3  399.23    4997  397.83
  4999.7  397.33    5003  397.83    5060  407.78    5080  410.33  5116.3  409.78
    5190  407.72    5250  400.61    5260   402.4    5270  402.82    5280  406.51
    5290  408.86    5310  410.48  5690.1  416.25  5930.1  425.84  6016.5  428.36
#Mann= 5 ,-1 , 0
  3749.7      .1       0  4984.3     .12       0    4997     .07       0
    5003     .12       0  5116.3      .1       0
#XS Ineff= 2 , 0
                         5080.11          410.33
Permanent Ineff=
       F       F
Bank Sta=4950,5280
XS Rating Curve= 0 ,0
Exp/Cntr=0.3,0.1

Type RM Length L Ch R = 1 ,15537   ,593,593,593
BEGIN DESCRIPTION:
UNT 020 IN LACR 22.0
END DESCRIPTION:
XS GIS Cut Line= 2
      2181518.04     13204603.92      2183224.53     13204527.61
#Sta/Elev= 30
  4079.4  422.41  4309.3  413.27  4389.4  411.54  4529.5  410.63  4609.6  410.97
  4829.8  408.16  4849.9  405.16  4879.9  402.63  4909.9   407.3  4929.9  408.49
    4970  408.75    4980   405.6    4990  400.28    5000   396.3    5007  394.55
  5009.8  394.05    5013  394.55    5023  397.46    5030  398.63    5040  399.34
  5050.1  398.48  5070.1  400.77  5080.1  400.97  5100.1  403.75  5130.1  404.28
  5150.1  407.03  5170.2  407.67  5370.4  409.73  5620.6  410.79  5787.6  410.11
#Mann= 3 ,-1 , 0
  4079.4      .1       0    5007     .07       0    5013      .1       0
Bank Sta=4980,5100.1
XS Rating Curve= 0 ,0
Exp/Cntr=0.3,0.1

Type RM Length L Ch R = 1 ,14944   ,615,615,615
BEGIN DESCRIPTION:
UNT 020 IN LACR 21.0
END DESCRIPTION:
XS GIS Cut Line= 3
      2181316.63     13205152.53      2182052.72     13205166.42
       2183323.1     13204992.87
#Sta/Elev= 30
  3875.2  415.99  3896.3   416.3  3926.3  415.44  3936.3  416.18  3996.3  414.45
  4016.3  415.28  4116.3  414.37  4176.3  415.36  4476.4  409.36  4596.4     409
  4626.6  408.09  4727.5  407.24  4858.7  407.11  4899.1  405.99  4919.3  404.71
  4929.3  403.21  4942.6  399.96  4976.8  394.34  4979.6  393.84  4982.8  394.34
  5020.2  396.21  5030.3  398.17  5050.5  404.21  5060.6  405.78  5092.2  407.16
  5181.7  406.24    5314  408.06  5807.4  408.49    5830  409.32  5893.6  409.23
#Mann= 3 ,-1 , 0
  3875.2      .1       0  4976.8     .07       0  4982.8      .1       0
Bank Sta=4929.3,5050.5
XS Rating Curve= 0 ,0
Exp/Cntr=0.3,0.1

Type RM Length L Ch R = 1 ,14329   ,971,971,971
BEGIN DESCRIPTION:
UNT 020 IN LACR 20.0
END DESCRIPTION:
XS GIS Cut Line= 3
       2181398.5     13206463.24      2182092.93     13205866.46
      2183664.51     13205086.08
#Sta/Elev= 30
  3588.7  416.92  3621.1  416.52  3649.6  417.58  3706.3  416.42  4102.8  417.06
  4237.8  414.54  4266.3  414.96  4365.6  411.66    4460  409.94  4543.2  408.21
  4694.2  407.96  4861.3  406.31  4895.9  402.48  4933.9  401.38  4940.7  400.16
  4946.3  400.59  4963.1  397.33  5004.9  393.35  5007.7  392.85  5010.9  393.35
  5030.3  393.45  5067.9  400.99  5103.1  404.17  5134.9  405.47  5246.6  404.33
  5411.3  406.62  5775.4  406.89  6028.8  408.83  6136.5  409.68    6259  410.75
#Mann= 7 ,-1 , 0
  3588.7      .1       0    4460     .05       0  4861.3      .1       0
  5004.9     .07       0  5010.9      .1       0  6028.8     .05       0
  6136.5      .1       0
Bank Sta=4946.3,5067.9
XS Rating Curve= 0 ,0
Exp/Cntr=0.3,0.1

Type RM Length L Ch R = 1 ,13358   ,979,979,979
BEGIN DESCRIPTION:
UNT 020 IN LACR 19.0
END DESCRIPTION:
XS GIS Cut Line= 4
      2181951.92     13206441.53      2182722.27     13206300.48
      2183709.69     13205974.96      2184153.66     13205736.73
#Sta/Elev= 30
  3779.4  413.02  3996.7  410.46  4166.4  410.99  4447.4  405.53  4618.9  404.44
  4751.2  400.81    4783  401.43    4821  404.02  4884.2  404.57  4941.8  403.22
  4973.5  398.93  4978.9   394.2  4989.5  388.04    4997   387.3  4999.7   386.8
    5003   387.3  5005.3  389.63  5063.2  398.85  5068.8  401.64  5074.1  400.92
  5084.2   403.6  5115.8  405.17  5169.4  404.33  5347.5  404.26    5450  405.15
  5605.9  408.25  6012.5   423.7  6065.3  426.16  6078.2  427.89  6106.1  428.32
#Mann= 5 ,-1 , 0
  3779.4     .05       0  4447.4      .1       0    4997     .07       0
    5003      .1       0  5605.9     .05       0
Bank Sta=4973.5,5063.2
XS Rating Curve= 0 ,0
Exp/Cntr=0.3,0.1

Type RM Length L Ch R = 1 ,12379   ,789,789,789
BEGIN DESCRIPTION:
UNT 020 IN LACR 17.0
END DESCRIPTION:
XS GIS Cut Line= 3
      2182364.23     13207689.35       2183948.4     13206322.18
      2184241.36     13205866.47
#Sta/Elev= 30
  3846.2   431.5  3886.1     431  3906.9  429.17  3963.9  428.35  4105.5  423.46
  4154.9  422.74  4594.7     407  4708.8  403.86    4828  402.07  4899.7  400.69
  4934.8  396.54  4949.1  393.47  4996.5  388.64  4999.2  388.14  5002.5  388.64
  5034.6  391.18  5063.1  395.96  5077.4  397.97  5112.5  400.67  5133.4  401.03
  5261.7  401.26  5382.4  402.86  5552.4  402.67  5686.9  404.29    5723  403.77
  5792.7  403.34  5906.7  404.36  6006.3  406.78  6194.7  413.09  6480.5  425.95
#Mann= 5 ,-1 , 0
  3846.2     .05       0    4828      .1       0  4996.5     .07       0
  5002.5      .1       0    5723     .05       0
Bank Sta=4934.8,5063.1
XS Rating Curve= 0 ,0
Exp/Cntr=0.3,0.1

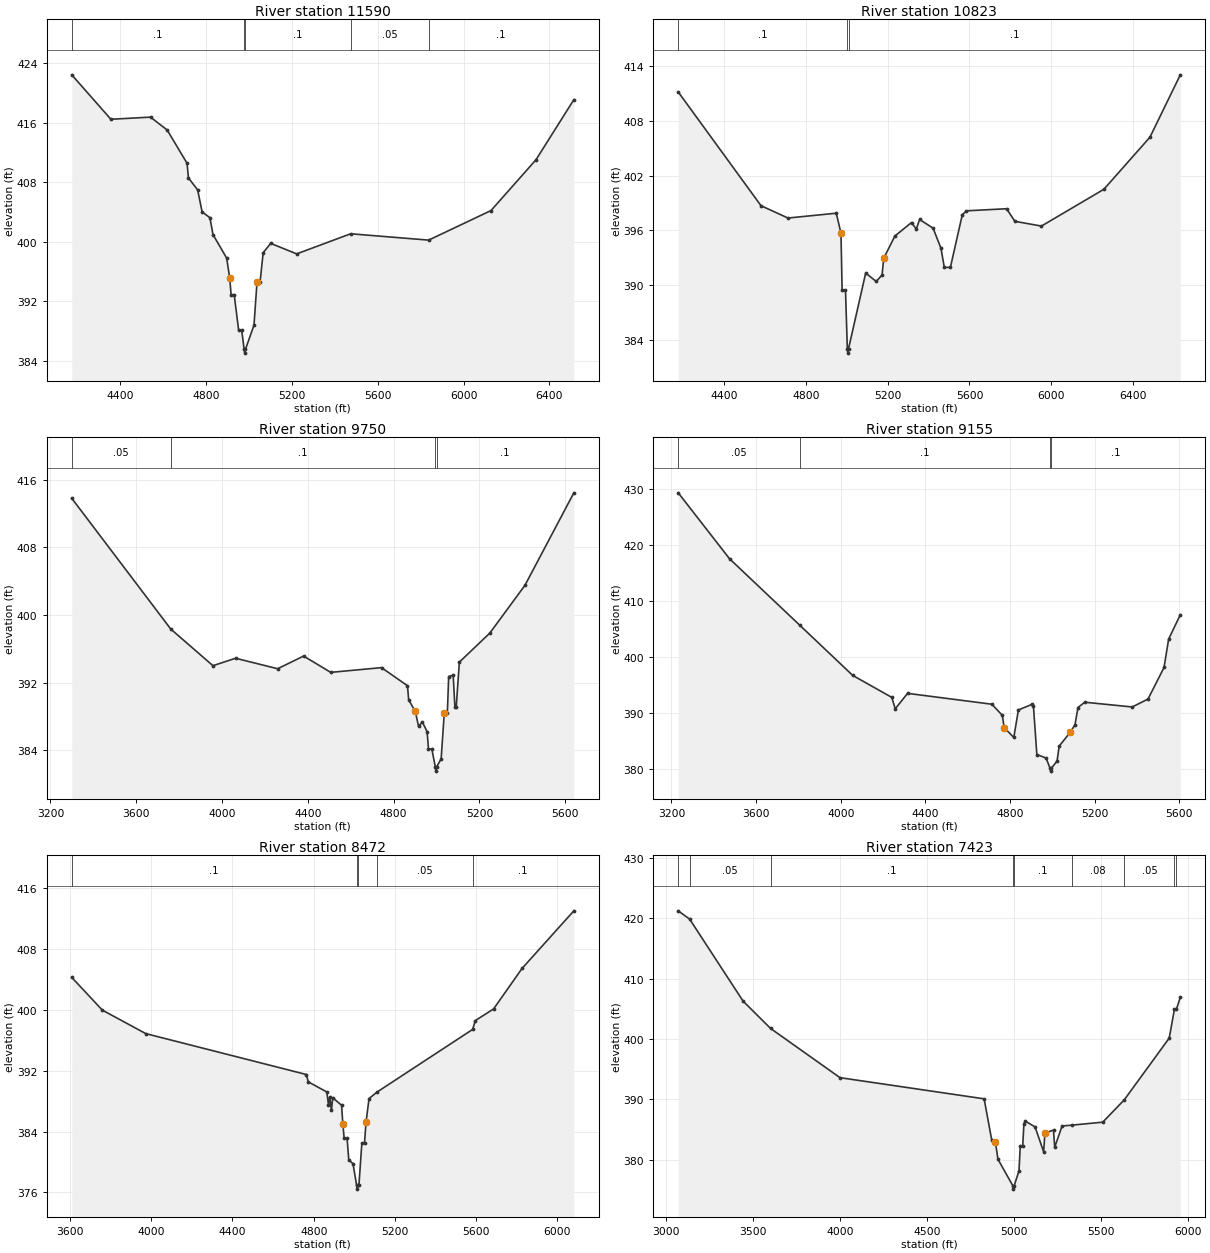
Type RM Length L Ch R = 1 ,11590   ,767,767,767
BEGIN DESCRIPTION:
UNT 020 IN LACR 15.0
END DESCRIPTION:
XS GIS Cut Line= 3
      2183156.28     13208112.58      2184284.77     13206767.06
      2184533.51     13206237.14
#Sta/Elev= 30
    4173  422.41  4355.4  416.44  4540.2  416.73  4618.2  414.99  4710.6  410.53
  4717.1  408.56    4760  406.96  4780.9     404  4817.3  403.22  4831.6  400.95
  4895.3   397.8  4909.6  395.11  4916.1  392.88  4930.5  392.88  4951.3  388.09
  4965.6  388.09  4976.9  385.53  4979.6  385.03  4982.9  385.53  5022.8  388.78
  5037.1  394.65  5051.4  394.65  5065.7  398.52  5100.9  399.77  5221.9  398.36
  5473.7  401.06  5837.3  400.21  6128.2  404.18  6338.1  411.01  6514.5  419.07
#Mann= 5 ,-1 , 0
    4173      .1       0  4976.9     .07       0  4982.9      .1       0
  5473.7     .05       0  5837.3      .1       0
Bank Sta=4909.6,5037.1
XS Rating Curve= 0 ,0
Exp/Cntr=0.3,0.1

Type RM Length L Ch R = 1 ,10823   ,1073,1073,1073
BEGIN DESCRIPTION:
UNT 020 IN LACR 14.0
END DESCRIPTION:
XS GIS Cut Line= 4
      2183612.05     13208579.12      2184046.06     13208340.41
      2184425.83     13207504.91      2184794.08     13206530.14
#Sta/Elev= 30
    4176  411.15  4580.8  398.69  4712.6  397.34  4948.8  397.87  4971.8  395.67
  4977.4  389.44  4993.8  389.44  5002.9  383.04  5005.7  382.54  5008.9  383.04
  5092.6  391.31  5144.3  390.39  5172.9  391.11  5180.5  392.91  5235.4  395.37
  5316.8  396.85  5339.9  396.13  5356.3  397.18  5422.2  396.23  5460.7  394.03
  5477.1  391.93  5506.8  391.93    5565   397.7  5585.3  398.13  5781.6  398.36
  5822.2  396.98    5952  396.46  6257.3  400.49  6482.7   406.2  6631.1  413.03
#Mann= 3 ,-1 , 0
    4176      .1       0  5002.9     .07       0  5008.9      .1       0
Bank Sta=4971.8,5180.5
XS Rating Curve= 0 ,0
Exp/Cntr=0.3,0.1

Type RM Length L Ch R = 1 ,9750    ,595,595,595
BEGIN DESCRIPTION:
UNT 020 IN LACR 12.0
END DESCRIPTION:
XS GIS Cut Line= 3
      2184287.73     13209196.82      2184987.72     13207646.85
      2185487.71     13207246.86
#Sta/Elev= 30
  3299.3  413.81  3761.1  398.33  3957.6     394  4063.2  394.88  4259.2  393.64
  4380.3  395.14  4506.8  393.21  4743.5  393.77  4864.6  391.63  4870.1  389.96
  4901.2  388.58  4916.3  386.81    4934  387.34  4956.1  386.19  4962.6  384.15
  4978.1  384.15  4994.3  382.02    4997  381.52  5000.3  382.02  5021.6  382.97
    5036  388.35  5050.4  388.35  5056.8  392.72  5077.6  392.88  5085.6  389.14
    5092  389.14  5106.5  394.42  5248.9  397.87  5412.2  403.51  5640.3  414.46
#Mann= 4 ,-1 , 0
  3299.3     .05       0  3761.1      .1       0  4994.3     .07       0
  5000.3      .1       0
Bank Sta=4901.2,5036
XS Rating Curve= 0 ,0
Exp/Cntr=0.3,0.1

Type RM Length L Ch R = 1 ,9155    ,683,683,683
BEGIN DESCRIPTION:
UNT 020 IN LACR 11.0
END DESCRIPTION:
XS GIS Cut Line= 3
       2184387.7     13209646.88      2185237.72     13208096.85
      2185487.74     13207546.81
#Sta/Elev= 30
  3232.2  429.36  3474.4  417.59  3805.6  405.74  4056.4  396.75  4241.2  392.82
  4257.3  390.78  4315.7  393.54  4714.2   391.6  4763.5   389.6  4771.9  387.43
  4817.5  385.66  4839.3  390.58  4904.7   391.6  4910.4  391.21  4926.5  382.61
  4970.1  381.99  4988.9  380.15  4991.7  379.65  4994.9  380.15    5022  381.46
  5031.9  384.12  5083.5  386.55  5106.6  387.93  5120.8  391.01  5152.7  391.96
  5376.8  391.11  5451.5  392.52  5527.3  398.16  5549.2  403.25  5604.2  407.58
#Mann= 4 ,-1 , 0
  3232.2     .05       0  3805.6      .1       0  4988.9     .07       0
  4994.9      .1       0
Bank Sta=4771.9,5083.5
XS Rating Curve= 0 ,0
Exp/Cntr=0.3,0.1

Type RM Length L Ch R = 1 ,8472    ,1049,1049,1049
BEGIN DESCRIPTION:
UNT 020 IN LACR 10.0
END DESCRIPTION:
XS GIS Cut Line= 3
      2184979.25       13209458.      2186042.59     13208047.45
      2186010.04     13207342.15
#Sta/Elev= 30
  3608.5  404.27  3758.9  399.97  3973.1  396.88  4764.4   391.5  4772.7  390.55
  4864.4  389.21  4872.7  387.53  4878.9  388.58  4887.2  386.78  4893.5  388.45
  4937.2  387.47  4943.5  384.94  4949.9  383.14  4964.3  383.14  4972.6  380.28
  4993.4  379.79  5011.2  376.94    5014  376.44  5017.2  376.94  5022.6  376.94
  5037.1  382.51  5050.1  382.51  5057.9   385.3  5072.5  388.35  5112.5  389.21
  5582.5  397.43  5595.8  398.59  5685.9  400.13    5826  405.45    6081  413.02
#Mann= 5 ,-1 , 0
  3608.5      .1       0  5011.2     .07       0  5017.2      .1       0
  5112.5     .05       0  5582.5      .1       0
Bank Sta=4943.5,5057.9
XS Rating Curve= 0 ,0
Exp/Cntr=0.3,0.1

Type RM Length L Ch R = 1 ,7423    ,888,888,888
BEGIN DESCRIPTION:
UNT 020 IN LACR 8.0
END DESCRIPTION:
XS GIS Cut Line= 3
      2185437.74     13210096.83      2186587.72     13208546.86
      2187237.69     13207846.89
#Sta/Elev= 30
    3070  421.23  3135.7  419.85  3442.4  406.27  3600.7  401.73  3999.5  393.57
  4827.8  390.06  4871.7   383.2  4892.5  382.91  4907.2  380.05  4993.9  375.59
  4996.6  375.09  4999.9  375.59  5028.1  378.12  5035.4  382.22  5049.6  382.22
  5056.4  385.89  5063.8  386.38  5120.5   385.4  5169.8  381.27  5177.1  384.38
  5226.5  384.88  5233.3  382.02  5275.8  385.56  5332.4   385.7  5509.4  386.19
  5633.3   389.9  5891.5  400.13  5921.3  404.89  5932.5  404.89  5955.2  406.89
#Mann= 9 ,-1 , 0
    3070      .1       0  3135.7     .05       0  3600.7      .1       0
  4993.9     .07       0  4999.9      .1       0  5332.4     .08       0
  5633.3     .05       0  5921.3      .1       0  5932.5     .05       0
Bank Sta=4892.5,5177.1
XS Rating Curve= 0 ,0
Exp/Cntr=0.3,0.1

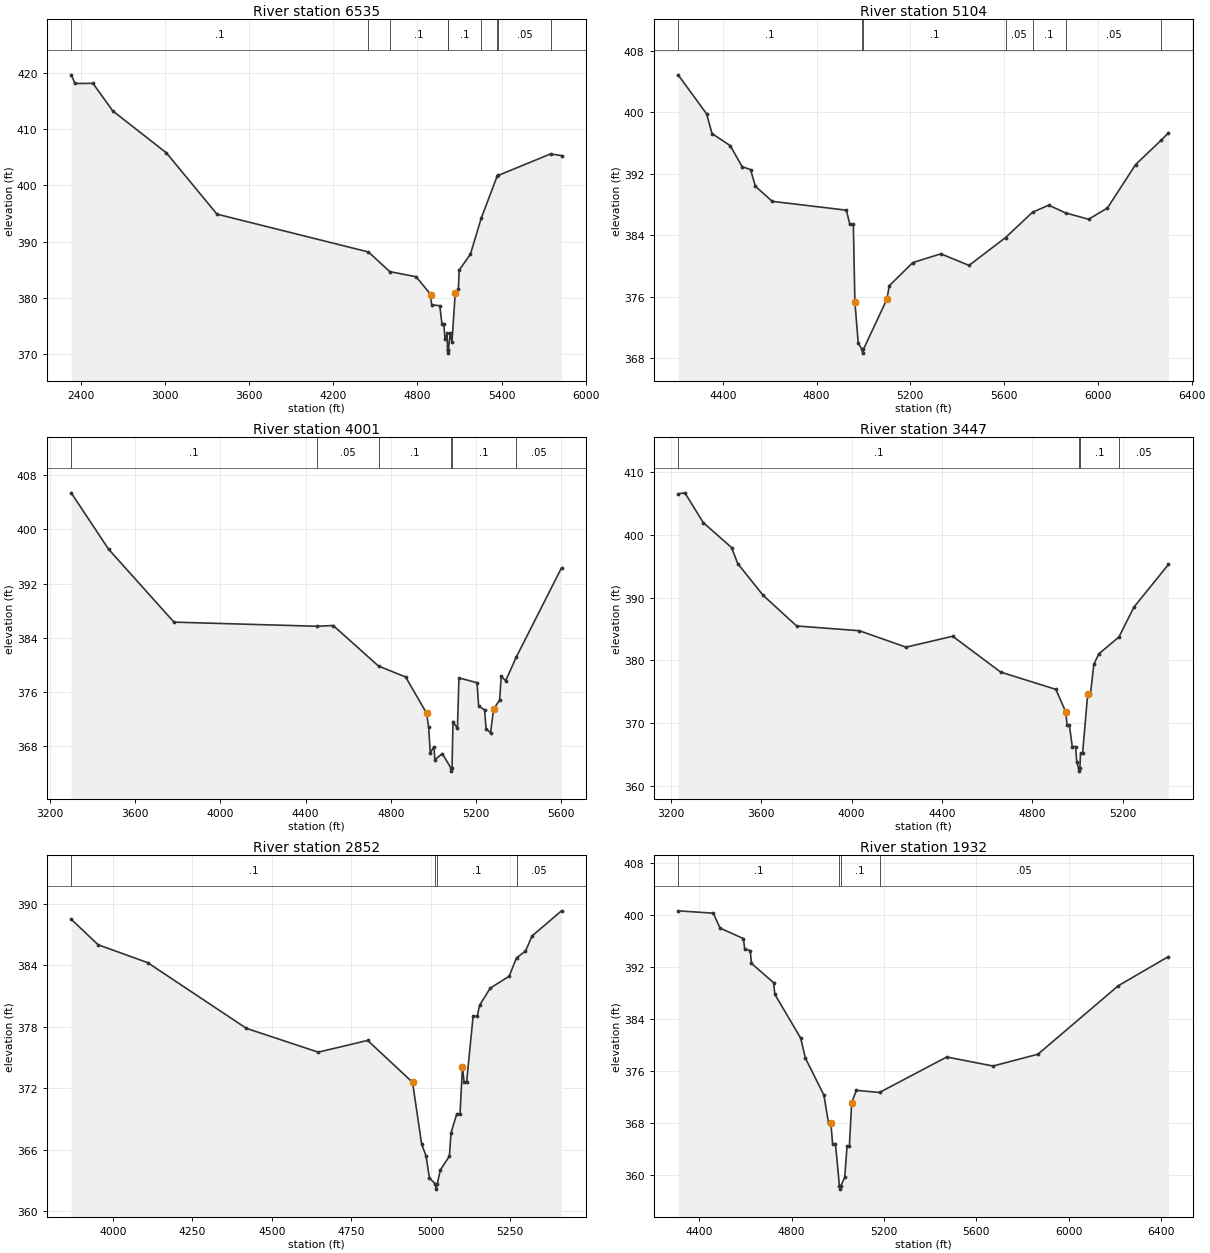
Type RM Length L Ch R = 1 ,6535    ,1431,1431,1431
BEGIN DESCRIPTION:
UNT 020 IN LACR 7.0
END DESCRIPTION:
XS GIS Cut Line= 4
      2185677.07     13210515.38       2187213.5     13208835.72
      2187634.17     13208123.22      2187493.43     13207755.43
#Sta/Elev= 30
  2330.1  419.62  2357.6  418.08  2485.3  418.11  2626.5  413.22  3008.9  405.77
  3370.2  394.88  4450.7  388.16  4602.7  384.67    4791  383.76  4894.8  380.61
  4900.6  378.81  4959.2  378.61  4974.8  375.43  4988.4  375.43  4996.3  372.74
  5011.6  373.69  5014.7   370.7  5017.5   370.2  5020.7   370.7  5033.3  373.69
  5046.5  372.21  5069.7  380.91  5091.9  381.53  5097.7  384.94  5177.7  387.76
  5256.1  394.24  5368.9  401.64  5377.6  401.77  5749.2  405.57  5827.7  405.28
#Mann= 9 ,-1 , 0
  2330.1      .1       0  4450.7     .05       0  4602.7      .1       0
  5014.7     .07       0  5020.7      .1       0  5256.1     .05       0
  5368.9     .08       0  5377.6     .05       0  5749.2     .08       0
Bank Sta=4894.8,5069.7
XS Rating Curve= 0 ,0
Exp/Cntr=0.3,0.1

Type RM Length L Ch R = 1 ,5104    ,1103,1103,1103
BEGIN DESCRIPTION:
UNT 020 IN LACR 6.0
END DESCRIPTION:
XS GIS Cut Line= 3
       2187287.7     13210246.88      2187737.72     13209596.85
      2187787.72     13208296.82
#Sta/Elev= 30
  4209.4  404.86  4331.1  399.77    4354  397.21  4431.7  395.64  4482.4  392.91
  4518.2  392.52  4539.2  390.35  4610.8  388.39    4927  387.24  4941.9   385.4
  4956.8   385.4  4963.5  375.26  4977.7  369.91    4994  369.13  4996.7  368.63
    5000  369.13  5100.1  375.66  5110.1   377.4  5210.2  380.41  5330.2  381.56
  5450.3  380.05  5606.4  383.68  5721.5  386.98  5790.6  387.89  5862.3  386.88
  5960.7  386.06  6040.8  387.53  6160.9  393.18  6270.3  396.36    6301  397.31
#Mann= 7 ,-1 , 0
  4209.4      .1       0    4994     .07       0    5000      .1       0
  5606.4     .05       0  5721.5      .1       0  5862.3     .05       0
  6270.3     .08       0
Bank Sta=4963.5,5100.1
XS Rating Curve= 0 ,0
Exp/Cntr=0.3,0.1

Type RM Length L Ch R = 1 ,4001    ,554,554,554
BEGIN DESCRIPTION:
UNT 020 IN LACR 5.0
END DESCRIPTION:
XS GIS Cut Line= 3
      2187787.73     13210746.82      2188487.72     13209196.86
      2188887.73     13208746.84
#Sta/Elev= 30
  3299.3  405.41  3474.8  397.08  3782.1  386.29    4454  385.68  4529.9  385.79
  4742.9  379.79  4870.1  378.18  4968.1  372.83  4978.1  370.77  4985.7  366.99
  5003.3  367.88  5007.1  365.94  5042.2  366.86  5081.9  364.76  5084.6  364.26
  5087.9  364.76  5092.4  371.59  5113.3  370.57  5120.4  378.05  5205.3  377.33
  5212.8  373.92  5240.8  373.29  5247.9  370.54  5268.8  369.91  5283.1  373.43
  5311.5  374.77    5319  378.28  5339.9  377.62  5388.8  381.07  5602.1  394.32
#Mann= 6 ,-1 , 0
  3299.3      .1       0    4454     .05       0  4742.9      .1       0
  5081.9     .07       0  5087.9      .1       0  5388.8     .05       0
Bank Sta=4968.1,5283.1
XS Rating Curve= 0 ,0
Exp/Cntr=0.3,0.1

Type RM Length L Ch R = 1 ,3447    ,595,595,595
BEGIN DESCRIPTION:
UNT 020 IN LACR 4.0
END DESCRIPTION:
XS GIS Cut Line= 3
       2188087.7     13210896.88      2188937.72     13209346.85
      2189137.71     13208996.87
#Sta/Elev= 30
  3232.2  406.53  3262.1  406.69  3343.6  401.94  3468.7  397.97  3496.2  395.41
  3608.6  390.35  3756.9  385.47  4034.6  384.71  4241.2  382.09  4447.9  383.83
  4660.2  378.12  4904.7  375.36  4948.3  371.78  4954.4  369.69  4964.4  369.69
  4977.2  366.24  4991.9  366.24  4997.1  363.78  5004.9  362.83  5007.7  362.33
  5010.9  362.83  5013.7  365.19    5023  365.19  5045.4  374.57  5057.6  374.57
  5072.7  379.33  5094.3     381    5184  383.72  5249.8  388.45  5403.1  395.28
#Mann= 4 ,-1 , 0
  3232.2      .1       0  5004.9     .07       0  5010.9      .1       0
    5184     .05       0
Bank Sta=4948.3,5045.4
XS Rating Curve= 0 ,0
Exp/Cntr=0.3,0.1

Type RM Length L Ch R = 1 ,2852    ,920,920,920
BEGIN DESCRIPTION:
UNT 020 IN LACR 3.0
END DESCRIPTION:
XS GIS Cut Line= 3
       2188487.7     13210596.88      2189287.72     13209796.85
      2189387.72     13209396.87
#Sta/Elev= 30
  3868.6  388.52  3953.5  386.02    4109  384.28  4420.2  377.85  4646.4  375.52
    4802  376.67  4943.4  372.57  4971.7  366.57  4985.9  365.35  4996.5  363.22
    5015  362.63  5017.8  362.13    5021  362.63  5030.9  364.01  5059.3  365.35
  5064.4  367.62  5082.5  369.49  5092.8  369.49  5100.5  374.11  5105.7  372.57
  5113.4  372.57    5134  379.04  5146.9  379.04  5154.6  380.12  5188.1  381.79
  5247.4  382.94  5270.6  384.74  5298.9   385.4  5319.5  386.88  5412.3  389.34
#Mann= 4 ,-1 , 0
  3868.6      .1       0    5015     .07       0    5021      .1       0
  5270.6     .05       0
Bank Sta=4943.4,5100.5
XS Rating Curve= 0 ,0
Exp/Cntr=0.3,0.1

Type RM Length L Ch R = 1 ,1932    ,888,888,888
BEGIN DESCRIPTION:
UNT 020 IN LACR 2.0
END DESCRIPTION:
XS GIS Cut Line= 3
      2189244.77     13210840.92      2189687.46     13210658.63
      2189817.52     13209019.94
#Sta/Elev= 30
  4308.8  400.62    4461  400.26  4490.3  397.97  4591.5  396.36  4596.9  394.78
  4620.9  394.52  4626.3  392.55  4722.1   389.6  4727.5   387.8  4839.5  381.07
  4859.6  378.02  4939.8  372.34  4959.9  368.04  4969.9  368.04  4977.7  364.83
    4990  364.83    5007   358.4  5009.8   357.9    5013   358.4  5030.1  359.71
  5040.1  364.53  5050.2  364.53  5060.2  371.19  5080.3  373.06  5180.6  372.74
  5471.5  378.18  5672.1   376.8  5866.5  378.61  6213.8  389.11  6431.4   393.6
#Mann= 4 ,-1 , 0
  4308.8      .1       0    5007     .07       0    5013      .1       0
  5180.6     .05       0
Bank Sta=4969.9,5060.2
XS Rating Curve= 0 ,0
Exp/Cntr=0.3,0.1

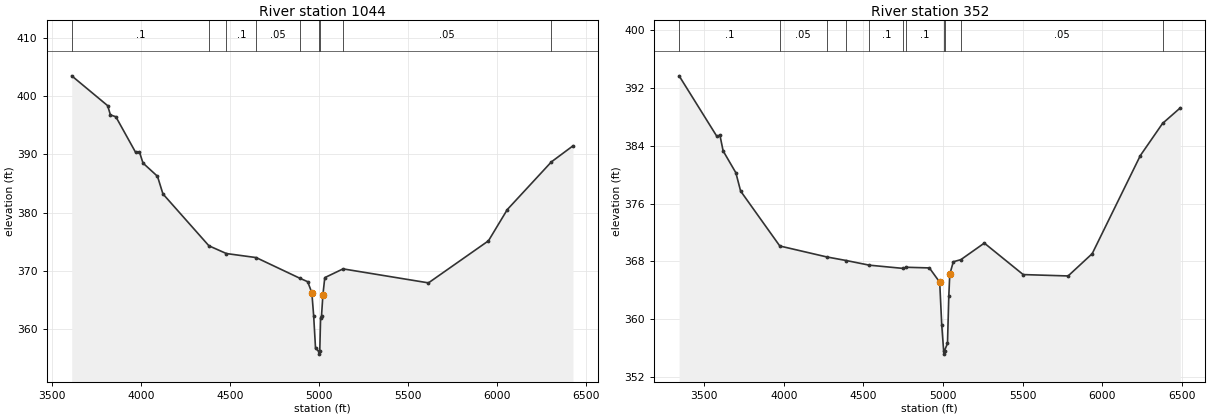
Type RM Length L Ch R = 1 ,1044    ,692,692,692
BEGIN DESCRIPTION:
Mapping XS 048be9e6
END DESCRIPTION:
XS GIS Cut Line= 4
      2189414.05     13211049.26      2190104.13     13210919.05
      2190429.65     13210945.09      2190924.45     13209226.32
#Sta/Elev= 30
  3608.8  403.48  3810.8  398.36  3826.2  396.78  3856.8  396.46    3968  390.35
  3989.1  390.45  4009.4  388.52  4090.8  386.25  4121.4  383.23  4379.9  374.33
  4478.1     373  4645.3  372.31  4889.8  368.78  4935.1  368.17  4958.4  366.29
  4968.8  362.29  4979.2  356.75    4997  356.25  4999.7  355.75    5003  356.25
  5007.7     362  5012.9  362.33  5020.8  365.97  5031.2  368.87    5134  370.37
    5614  367.97  5951.1  375.18  6057.3  380.55  6304.9  388.72  6426.2  391.47
#Mann= 9 ,-1 , 0
  3608.8      .1       0  4379.9     .05       0  4478.1      .1       0
  4645.3     .05       0  4889.8      .1       0    4997     .07       0
    5003      .1       0    5134     .05       0  6304.9     .08       0
Bank Sta=4958.4,5020.8
XS Rating Curve= 0 ,0
Exp/Cntr=0.3,0.1

Type RM Length L Ch R = 1 ,352     ,0,0,0
BEGIN DESCRIPTION:
UNT 020 IN LACR 1.0
END DESCRIPTION:
XS GIS Cut Line= 4
      2189531.18     13211231.55      2190664.02     13211205.51
      2191315.07     13210749.78      2191477.47     13209537.66
#Sta/Elev= 30
    3341  393.64  3577.6   385.3  3597.6  385.43  3617.6  383.27  3697.6  380.25
  3727.6  377.72  3973.9  370.13  4268.7  368.62  4392.1  368.12  4536.7  367.48
  4750.6  367.03  4768.1  367.19  4914.2   367.1  4979.1  365.13  4991.8  359.26
  5003.7  355.69  5006.4  355.19  5009.7  355.69    5028  356.67  5036.3  363.23
  5042.4  366.22  5064.6  367.95  5111.8  368.24  5259.5  370.53  5503.9  366.18
  5786.4  365.99  5937.7  369.07  6240.4  382.63  6380.1  387.07  6491.8  389.22
#Mann= 11 ,-1 , 0
    3341      .1       0  3973.9     .05       0  4268.7      .1       0
  4392.1     .05       0  4536.7      .1       0  4750.6     .05       0
  4768.1      .1       0  5003.7     .07       0  5009.7      .1       0
  5111.8     .05       0  6380.1     .08       0
Bank Sta=4979.1,5042.4
XS Rating Curve= 0 ,0
Exp/Cntr=0.3,0.1

Chan Stop Cuts=-1
Use User Specified Reach Order=0
Composite Channel Slope=5