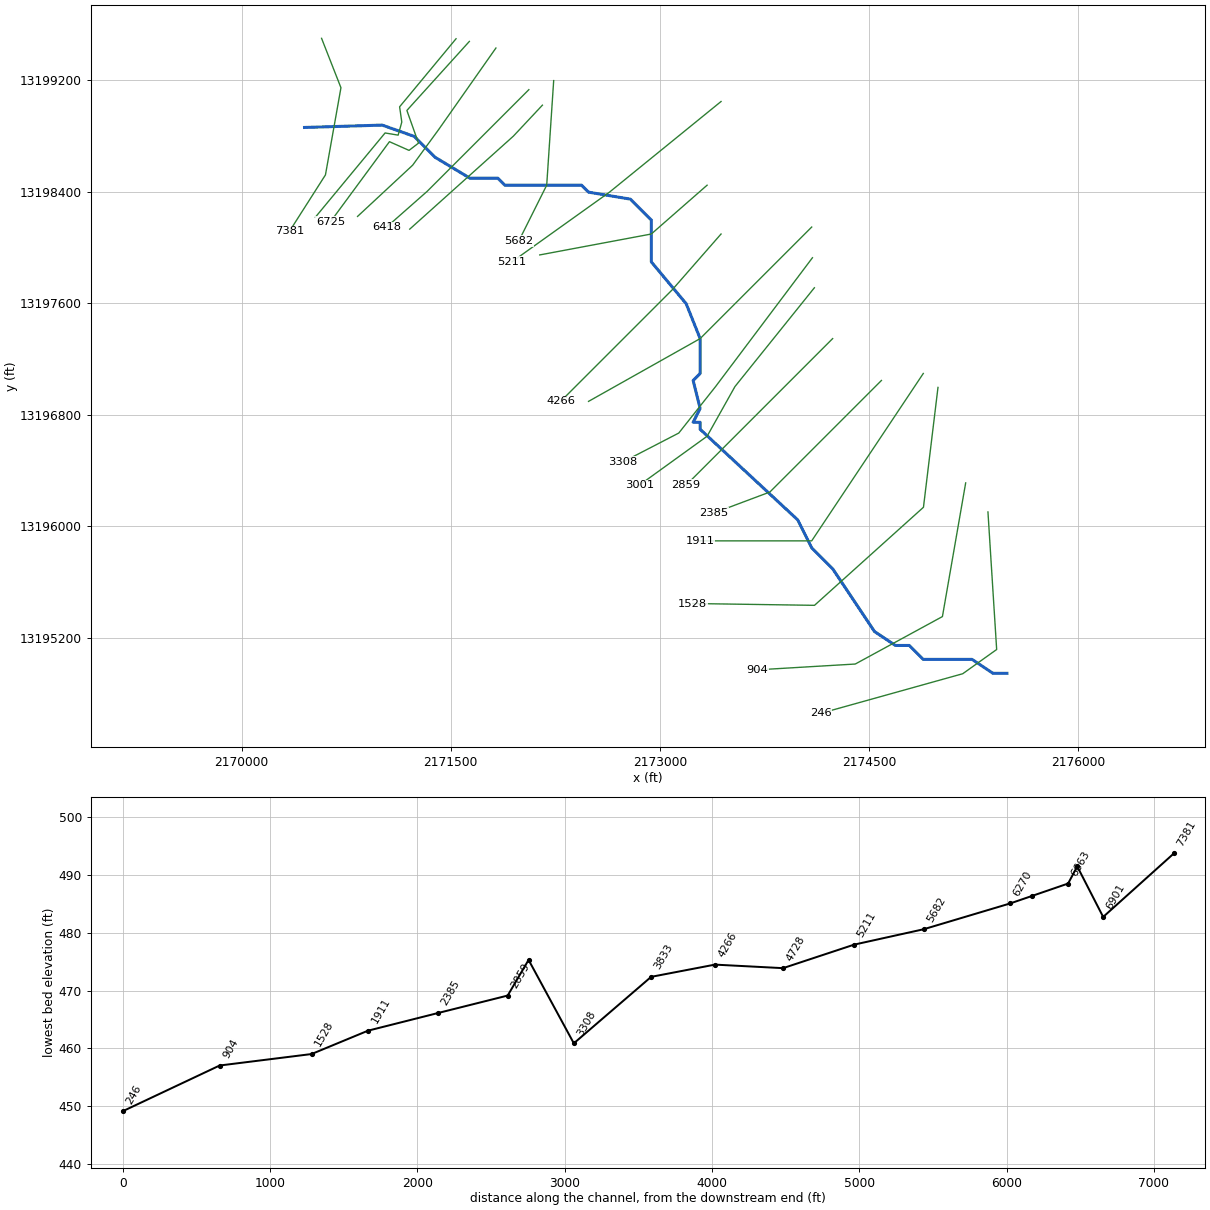
--- UNT 021 IN LACR.prj (project) ---

Proj Title=UNT 021 IN LACR Base Level Engineering
Current Plan=p01
Default Exp/Contr=0.3,0.1
English Units
Geom File=g01
Flow File=f01
Plan File=p01
Y Axis Title=Elevation
X Axis Title(PF)=Main Channel Distance
X Axis Title(XS)=Station
BEGIN DESCRIPTION:
UNT 021 IN LACR
END DESCRIPTION:
DSS Export Rating Curves= 0
DSS Export Rating Curve Sorted= 0
DSS Export Volume Flow Curves= 0
DXF OffsetX= 0
DXF OffsetY= 0
DXF ScaleX= 1
DXF ScaleY= 10

--- UNT 021 IN LACR.p01 (plan) ---

Plan Title=Multiple Run
Short Identifier=Multiple
Geom File=g01
Flow File=f01
Subcritical Flow
K Sum by GR= 0
Std Step Tol= 0.01
Critical Tol= 0.01
Num of Std Step Trials= 20
Max Error Tol= 0.3
Flow Tol Ratio= 0.001
Split Flow NTrial= 30
Split Flow Tol= 0.02
Split Flow Ratio= 0.02
Log Output Level= 0
Friction Slope Method= 1
Unsteady Friction Slope Method= 2
Unsteady Bridges Friction Slope Method= 1
Parabolic Critical Depth
Global Vel Dist=  1 , 1 , 1
Global Log Level= 0
CheckData=True
Encroach Param= -1, 0, 0, 0
BEGIN DESCRIPTION:
Multiple Run
END DESCRIPTION:

--- UNT 021 IN LACR.f01 (steady flow) ---

Flow Title=Multiple
Program Version=4.10
Number of Profiles= 7
Profile Names=10-year,25-year,50-year,1pct_min,100-year,1pct_plu,500-year
River Rch & RM=UNT 021 IN LACR,Reach-1         ,7381
     187     258     318     287     389     526     592
River Rch & RM=UNT 021 IN LACR,Reach-1         ,6270
     236     330     409     372     504     681     778
Boundary for River Rch & Prof#=UNT 021 IN LACR,Reach-1         , 1
Up Type= 0
Dn Type= 3
Dn Slope=0.005
Boundary for River Rch & Prof#=UNT 021 IN LACR,Reach-1         , 2
Up Type= 0
Dn Type= 3
Dn Slope=0.005
Boundary for River Rch & Prof#=UNT 021 IN LACR,Reach-1         , 3
Up Type= 0
Dn Type= 3
Dn Slope=0.005
Boundary for River Rch & Prof#=UNT 021 IN LACR,Reach-1         , 4
Up Type= 0
Dn Type= 3
Dn Slope=0.005
Boundary for River Rch & Prof#=UNT 021 IN LACR,Reach-1         , 5
Up Type= 0
Dn Type= 3
Dn Slope=0.005
Boundary for River Rch & Prof#=UNT 021 IN LACR,Reach-1         , 6
Up Type= 0
Dn Type= 3
Dn Slope=0.005
Boundary for River Rch & Prof#=UNT 021 IN LACR,Reach-1         , 7
Up Type= 0
Dn Type= 3
Dn Slope=0.005
DSS Import GetInterval= 0
DSS Import GetPeak= 0
DSS Import FillOption= 0

--- UNT 021 IN LACR.g01 (geometry) ---

Geom Title=Existing Conditions
Program Version=4.10

River Reach=UNT 021 IN LACR ,Reach-1
Reach XY= 30
      2170451.23     13198860.73      2171007.95     13198877.71
      2171237.72     13198796.85      2171387.72     13198646.85
      2171637.72     13198496.85      2171837.72     13198496.85
      2171887.72     13198446.85      2172437.72     13198446.85
      2172487.72     13198396.86      2172787.72     13198346.85
      2172937.72     13198196.85      2172937.72     13197896.86
      2173187.72     13197596.85      2173287.72     13197346.85
      2173287.72     13197096.85      2173237.72     13197046.85
      2173287.72     13196846.85      2173237.72     13196746.86
      2173287.72     13196746.86      2173287.72     13196696.85
      2173987.72     13196046.85      2174087.72     13195846.85
      2174237.72     13195696.85      2174537.72     13195246.85
      2174687.72     13195146.85      2174787.72     13195146.85
      2174887.72     13195046.85      2175237.72     13195046.85
      2175387.72     13194946.86      2175487.72     13194946.86

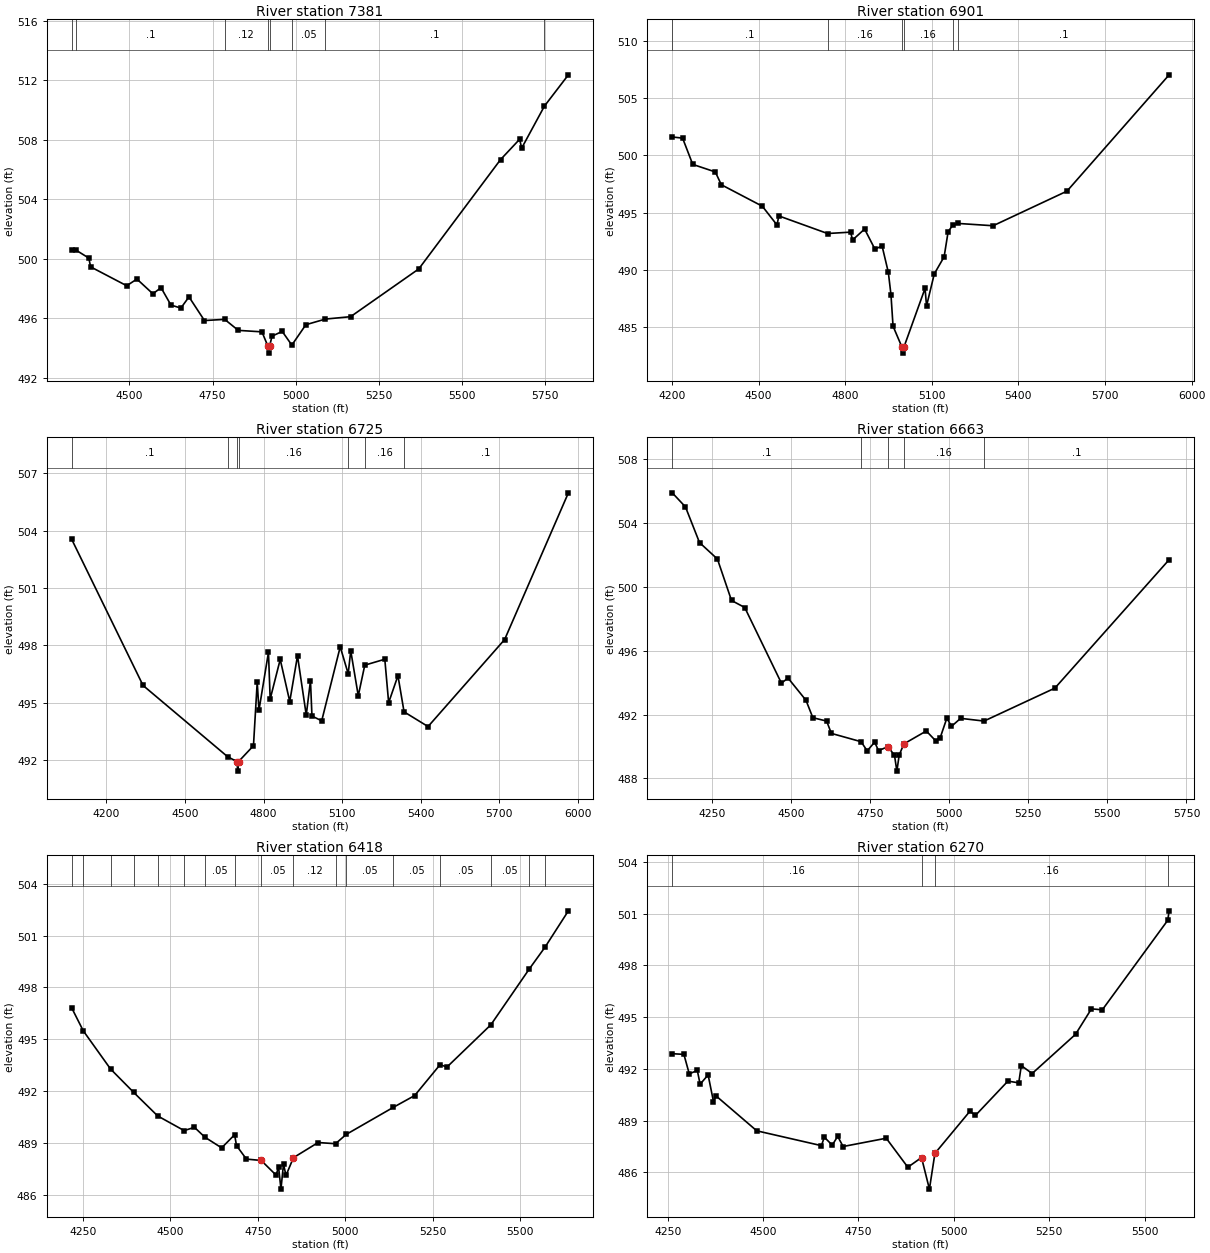
Type RM Length L Ch R = 1 ,7381    ,480,480,480
BEGIN DESCRIPTION:
UNT 021 IN LACR 14.0
END DESCRIPTION:
XS GIS Cut Line= 4
      2170573.55     13199499.79      2170712.45     13199145.59
      2170601.34     13198520.59       2170344.4     13198117.82
#Sta/Elev= 30
  4326.1   500.6    4340  500.58  4378.1  500.05  4383.5  499.46    4492  498.19
  4522.6  498.64  4570.6  497.65  4595.1  498.06  4624.9  496.89  4654.7  496.69
  4679.1  497.44  4725.6  495.85  4786.3  495.93  4827.2  495.19  4898.3  495.09
  4915.6  494.16  4918.3  493.66  4921.6  494.16  4928.6   494.8  4959.2  495.12
  4988.1   494.2  5030.3  495.57    5089  495.95  5164.7  496.11  5369.5  499.32
  5615.2  506.67  5672.7  508.04  5678.7  507.44  5747.2  510.27  5819.1  512.37
#Mann= 8 ,-1 , 0
  4326.1     .05       0    4340      .1       0  4786.3     .12       0
  4915.6     .04       0  4921.6     .12       0  4988.1     .05       0
    5089      .1       0  5747.2     .05       0
Bank Sta=4915.6,4921.6
XS Rating Curve= 0 ,0
Exp/Cntr=0.3,0.1

Type RM Length L Ch R = 1 ,6901    ,176,176,176
BEGIN DESCRIPTION:
UNT 021 IN LACR 13.0
END DESCRIPTION:
XS GIS Cut Line= 6
       2171537.7     13199496.83      2171133.09     13199008.83
      2171148.71     13198899.45      2171122.67      13198805.7
      2171028.92     13198821.33      2170528.91     13198217.15
#Sta/Elev= 30
    4201  501.62  4236.8  501.52  4271.9  499.22  4350.1  498.56  4370.9  497.44
  4512.9  495.56  4563.7  493.92  4570.2  494.71  4738.9  493.17  4818.9  493.29
  4825.4   492.6  4867.2  493.56  4902.8  491.81  4927.8  492.07  4949.4  489.77
  4958.5  487.82  4965.7  485.06    4997   483.2  4999.7   482.7    5003   483.2
  5076.6  488.37  5081.7  486.83  5108.6  489.64  5142.6  491.13  5156.5  493.33
  5171.9  493.88  5191.8  494.05  5312.3  493.85  5568.2  496.88    5922  507.06
#Mann= 6 ,-1 , 0
    4201      .1       0  4738.9     .16       0    4997     .07       0
    5003     .16       0  5171.9     .05       0  5191.8      .1       0
Bank Sta=4997,5003
XS Rating Curve= 0 ,0
Exp/Cntr=0.3,0.1

Type RM Length L Ch R = 1 ,6725    ,62,62,62
BEGIN DESCRIPTION:
Mapping XS eec92ad4
END DESCRIPTION:
XS GIS Cut Line= 6
       2171633.1     13199477.59      2171185.17     13198982.78
      2171268.51     13198748.41       2171200.8     13198696.33
      2171060.17     13198758.83      2170638.31     13198185.92
#Sta/Elev= 30
  4066.8  503.56  4339.9   495.9  4663.1  492.17  4698.6  491.92  4701.3  491.42
  4704.6  491.92  4761.5  492.75  4775.8  496.08  4782.4   494.6  4818.7  497.63
  4825.3  495.19  4863.6  497.26    4900  495.06  4929.6  497.45    4963  494.35
  4979.1  496.15  4984.8   494.3    5022  494.05  5092.7  497.92  5123.1  496.51
  5132.9  497.71  5161.6  495.36  5186.4  496.96  5262.9  497.27  5277.6     495
  5313.1  496.41  5336.4  494.52    5428  493.75  5720.4   498.3  5963.8  505.97
#Mann= 7 ,-1 , 0
  4066.8      .1       0  4663.1     .16       0  4698.6     .07       0
  4704.6     .16       0  5123.1      .1       0  5186.4     .16       0
  5336.4      .1       0
Bank Sta=4698.6,4704.6
XS Rating Curve= 0 ,0
Exp/Cntr=0.3,0.1

Type RM Length L Ch R = 1 ,6663    ,245,245,245
BEGIN DESCRIPTION:
Mapping XS 2e1896b7
END DESCRIPTION:
XS GIS Cut Line= 4
      2171823.58     13199430.34      2171413.84     13198846.98
      2171226.34     13198590.03      2170831.58     13198222.98
#Sta/Elev= 30
  4125.2  505.86  4166.9  504.98  4211.3  502.75  4267.9  501.72  4312.4  499.13
  4354.2  498.69  4470.1  493.96    4491  494.28  4547.7  492.89  4569.4   491.8
    4613  491.59  4627.8  490.82  4721.8   490.3  4741.1  489.73  4764.6  490.27
  4777.1  489.74  4806.5  489.99  4827.4  489.45  4834.9  488.46  4842.2  489.46
  4856.9  490.16  4927.9  490.97  4957.3  490.36    4972  490.56  4992.8  491.77
  5007.5  491.26  5036.3  491.76  5110.4  491.59  5334.2  493.65  5695.2  501.68
#Mann= 5 ,-1 , 0
  4125.2      .1       0  4721.8     .16       0  4806.5     .07       0
  4856.9     .16       0  5110.4      .1       0
Bank Sta=4806.5,4856.9
XS Rating Curve= 0 ,0
Exp/Cntr=0.3,0.1

Type RM Length L Ch R = 1 ,6418    ,148,148,148
BEGIN DESCRIPTION:
UNT 021 IN LACR 12.0
END DESCRIPTION:
XS GIS Cut Line= 3
      2172059.65     13199131.68       2171330.5     13198402.53
      2171038.82     13198145.57
#Sta/Elev= 30
  4217.4  496.84    4251  495.49  4328.9  493.28  4395.2  491.92  4463.6  490.56
  4539.3  489.71  4568.7   489.9  4598.4  489.33  4646.4  488.71  4683.5  489.47
  4688.9  488.84  4717.2  488.06  4759.6  487.98    4802  487.13  4809.1  487.61
  4815.9  486.32  4823.2  487.77  4830.3  487.11  4851.5  488.14  4922.2  489.02
  4971.8  488.95  5002.5  489.49  5137.3  491.06    5198  491.74  5270.7  493.53
  5290.3  493.39  5415.8  495.84  5525.5  499.07  5570.7  500.34  5637.3  502.44
#Mann= 17 ,-1 , 0
  4217.4     .05       0    4251      .1       0  4328.9     .05       0
  4395.2      .1       0  4463.6     .05       0  4539.3      .1       0
  4598.4     .05       0  4683.5     .12       0  4759.6     .05       0
  4851.5     .12       0  4971.8      .1       0  5002.5     .05       0
  5137.3     .05       0  5270.7     .05       0  5415.8     .05       0
  5525.5      .1       0  5570.7     .05       0
Bank Sta=4759.6,4851.5
XS Rating Curve= 0 ,0
Exp/Cntr=0.3,0.1

Type RM Length L Ch R = 1 ,6270    ,588,588,588
BEGIN DESCRIPTION:
UNT 021 IN LACR 11.0
END DESCRIPTION:
XS GIS Cut Line= 3
      2172156.87     13199020.56      2171948.56     13198798.37
      2171205.62      13198131.8
#Sta/Elev= 30
  4261.8  492.88  4292.3  492.84  4306.4  491.71  4327.5  491.91  4334.8  491.11
  4355.8  491.65  4369.9   490.1  4376.8  490.43  4483.3  488.41  4652.9  487.55
  4660.4  488.04  4681.3  487.58  4695.5  488.09  4709.7   487.5  4822.8  487.98
  4879.4   486.3  4915.3  486.86    4936  485.03  4950.4   487.1  5042.4  489.55
  5056.6   489.3  5141.8  491.29  5170.2  491.19  5176.9  492.19  5205.3  491.73
    5319     494  5360.8  495.48  5389.2  495.42  5560.8  500.61  5564.5  501.16
#Mann= 4 ,-1 , 0
  4261.8     .16       0  4915.3     .07       0  4950.4     .16       0
  5560.8     .05       0
Bank Sta=4915.3,4950.4
XS Rating Curve= 0 ,0
Exp/Cntr=0.3,0.1

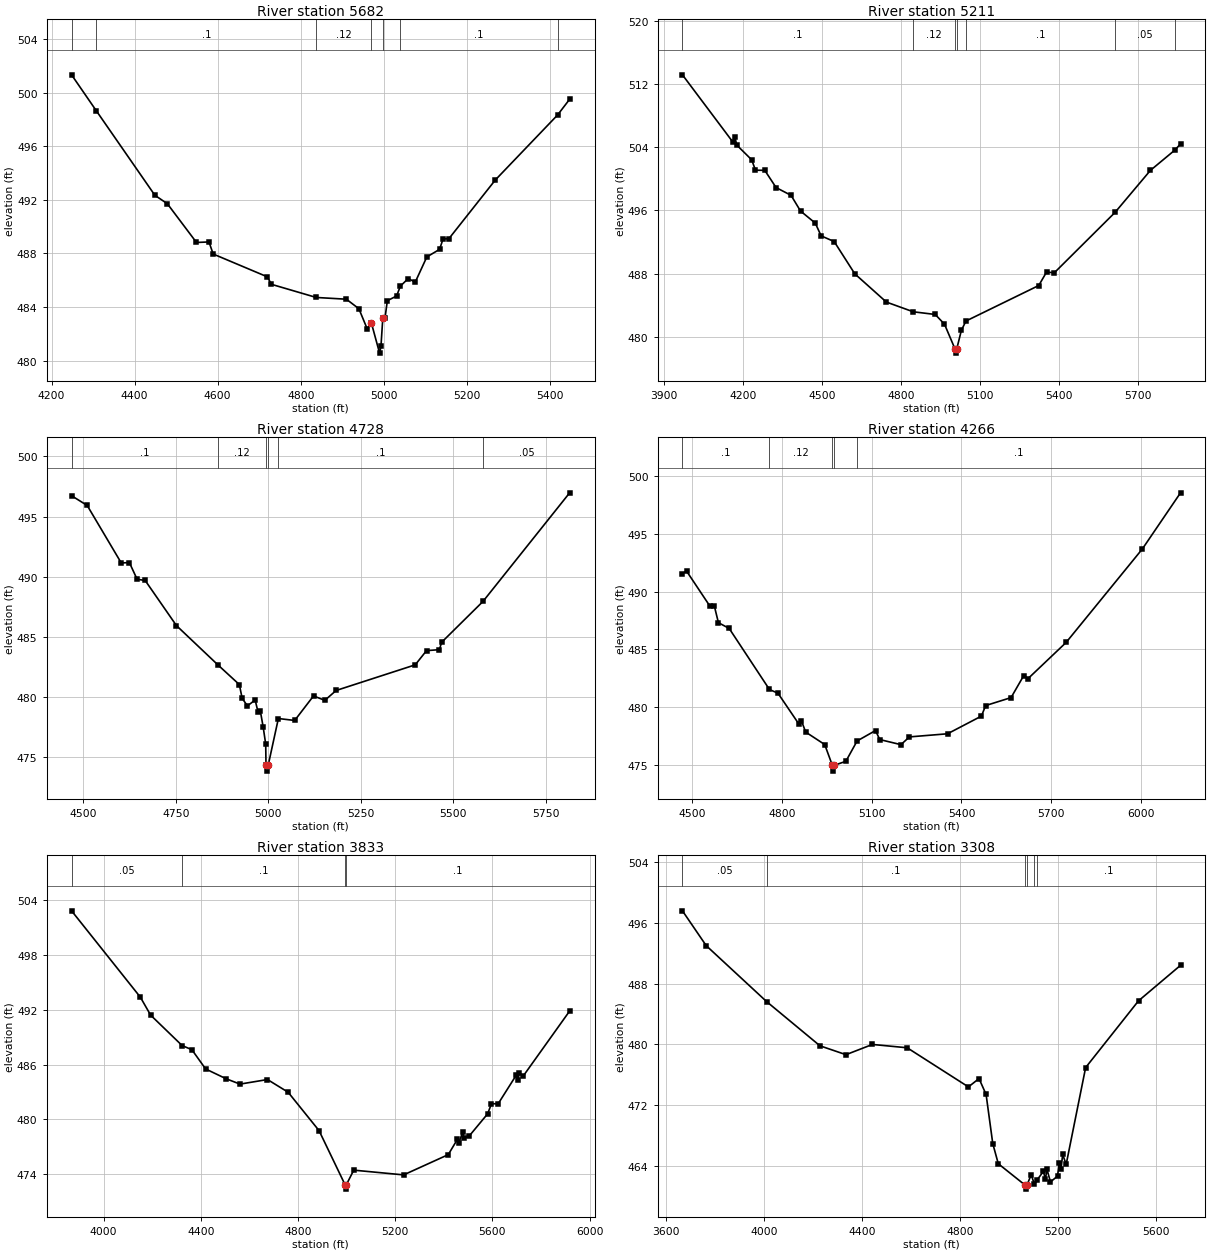
Type RM Length L Ch R = 1 ,5682    ,471,471,471
BEGIN DESCRIPTION:
UNT 021 IN LACR 10.0
END DESCRIPTION:
XS GIS Cut Line= 3
      2172237.72     13199196.89      2172187.72     13198446.85
      2171987.73     13198046.87
#Sta/Elev= 30
  4248.3  501.32  4308.3  498.62  4448.8  492.34  4478.8  491.71    4549  488.82
  4579.1  488.86  4589.1  487.96  4719.4  486.26  4729.4   485.7  4837.3  484.72
  4909.8  484.59  4939.9  483.88  4959.9  482.38  4969.9  482.83  4989.7  480.57
    4993  481.07  4997.5   483.2  5002.8   483.2  5008.4  484.48  5030.7  484.83
  5039.8  485.57  5058.7  486.13  5075.5  485.86  5103.4  487.74  5134.2  488.31
  5142.5  489.09  5156.5   489.1  5268.3  493.48    5418  498.32  5447.2   499.5
#Mann= 7 ,-1 , 0
  4248.3     .05       0  4308.3      .1       0  4837.3     .12       0
  4969.9     .07       0  4997.5     .12       0  5039.8      .1       0
    5418     .05       0
Bank Sta=4969.9,4997.5
XS Rating Curve= 0 ,0
Exp/Cntr=0.3,0.1

Type RM Length L Ch R = 1 ,5211    ,483,483,483
BEGIN DESCRIPTION:
UNT 021 IN LACR 9.0
END DESCRIPTION:
XS GIS Cut Line= 3
      2173437.74     13199046.87      2172637.72     13198396.86
      2171937.75     13197896.87
#Sta/Elev= 30
  3969.2  513.19  4161.8  504.62  4168.2  505.32  4175.4  504.29  4232.1  502.42
  4246.5   501.1  4281.7  501.09  4324.8   498.9  4381.5  497.92  4417.5  495.93
  4473.5   494.4  4495.8  492.78  4545.3  492.06  4623.6  487.97  4743.5  484.39
  4845.4  483.16  4928.9  482.82  4964.1  481.59  5004.4  478.42  5007.1  477.92
  5010.4  478.42  5028.3  480.82  5045.7  481.99    5322  486.49  5351.5  488.19
    5381   488.1  5611.5  495.75  5745.9  501.08  5838.3  503.64  5860.2  504.43
#Mann= 7 ,-1 , 0
  3969.2      .1       0  4845.4     .12       0  5004.4     .07       0
  5010.4     .12       0  5045.7      .1       0  5611.5     .05       0
  5838.3      .1       0
Bank Sta=5004.4,5010.4
XS Rating Curve= 0 ,0
Exp/Cntr=0.3,0.1

Type RM Length L Ch R = 1 ,4728    ,462,462,462
BEGIN DESCRIPTION:
UNT 021 IN LACR 8.0
END DESCRIPTION:
XS GIS Cut Line= 3
      2173337.72     13198446.85      2172937.72     13198096.85
      2172137.76     13197946.86
#Sta/Elev= 30
  4468.5  496.74  4510.7  495.93  4602.8  491.15  4624.6  491.19  4645.5   489.8
  4667.3   489.7  4751.8  485.95    4864  482.68  4921.7  481.05  4929.3  479.91
  4943.5  479.28  4964.4  479.77    4972  478.79  4978.6  478.82  4986.2   477.5
  4992.9   476.1  4993.7  474.36  4996.4  473.86  4999.7  474.36  5027.1  478.23
  5071.2  478.07  5122.1  480.11  5152.6  479.74  5183.1  480.56  5396.8  482.69
  5427.3  483.87  5462.1  483.95    5468  484.56  5579.9  487.96  5813.9  496.98
#Mann= 6 ,-1 , 0
  4468.5      .1       0    4864     .12       0  4993.7     .07       0
  4999.7     .12       0  5027.1      .1       0  5579.9     .05       0
Bank Sta=4993.7,4999.7
XS Rating Curve= 0 ,0
Exp/Cntr=0.3,0.1

Type RM Length L Ch R = 1 ,4266    ,433,433,433
BEGIN DESCRIPTION:
UNT 021 IN LACR 7.0
END DESCRIPTION:
XS GIS Cut Line= 3
      2173437.72     13198096.85      2173087.72     13197696.85
       2172287.7     13196896.83
#Sta/Elev= 30
  4468.5  491.56  4482.3  491.77    4561  488.71  4574.8  488.77  4588.6  487.31
  4624.6  486.81    4759  481.53  4787.4  481.21  4858.1  478.51  4865.7  478.83
  4879.9  477.85  4943.5  476.77    4969  474.97  4971.8  474.47    4975  474.97
  5014.1  475.32  5051.7  477.08  5113.1  477.98  5127.3   477.2    5198  476.76
  5226.3  477.43  5353.6   477.7  5466.7  479.23  5480.8  480.14  5565.7  480.83
  5608.1  482.74  5622.3  482.47  5749.5   485.6  6004.1  493.69  6131.4  498.54
#Mann= 5 ,-1 , 0
  4468.5      .1       0    4759     .12       0    4969     .07       0
    4975     .12       0  5051.7      .1       0
Bank Sta=4969,4975
XS Rating Curve= 0 ,0
Exp/Cntr=0.3,0.1

Type RM Length L Ch R = 1 ,3833    ,525,525,525
BEGIN DESCRIPTION:
UNT 021 IN LACR 6.0
END DESCRIPTION:
XS GIS Cut Line= 3
      2174087.74     13198146.88      2173287.72     13197346.85
       2172487.7     13196896.84
#Sta/Elev= 30
  3868.6  502.86  4151.5   493.4  4193.9  491.43  4323.6  488.09  4363.6  487.64
  4420.2  485.53    4505  484.45  4561.6  483.87  4674.7  484.37  4759.6  482.98
  4886.9  478.77  4993.5  472.86  4996.2  472.36  4999.5  472.86  5029.6  474.44
  5234.9  473.92  5418.5  476.14  5456.1  477.82  5461.8  477.42  5477.7  478.59
  5483.5  477.91  5505.2   478.2  5580.4  480.61  5596.3  481.72  5623.7  481.71
  5698.9  484.88  5704.7  484.28  5711.4  485.11  5726.3  484.73  5917.9  491.88
#Mann= 4 ,-1 , 0
  3868.6     .05       0  4323.6      .1       0  4993.5     .07       0
  4999.5      .1       0
Bank Sta=4993.5,4999.5
XS Rating Curve= 0 ,0
Exp/Cntr=0.3,0.1

Type RM Length L Ch R = 1 ,3308    ,307,307,307
BEGIN DESCRIPTION:
Mapping XS 713f469b
END DESCRIPTION:
XS GIS Cut Line= 4
      2174092.99     13197926.71      2173398.54      13197003.1
      2173134.65     13196669.76      2172732.74     13196461.88
#Sta/Elev= 30
  3665.9  497.59  3762.9     493  4009.2  485.63  4227.3  479.79  4333.5  478.62
  4441.4  479.97  4583.4  479.53  4833.3  474.37  4876.6  475.47  4905.5  473.37
  4932.7   466.9  4955.2  464.24  5065.9  461.39  5068.7  460.89  5071.9  461.39
  5089.7   462.8  5102.5  461.53  5112.6  462.06  5139.4  463.22  5147.5  462.19
  5153.9  463.49  5168.3  461.84  5197.2  462.61  5203.5  464.33  5211.6   463.6
    5218  465.46  5232.4  464.16  5311.8  476.92  5527.6  485.72  5699.1   490.4
#Mann= 6 ,-1 , 0
  3665.9     .05       0  4009.2      .1       0  5065.9     .07       0
  5071.9      .1       0  5102.5     .16       0  5112.6      .1       0
Bank Sta=5065.9,5071.9
XS Rating Curve= 0 ,0
Exp/Cntr=0.3,0.1

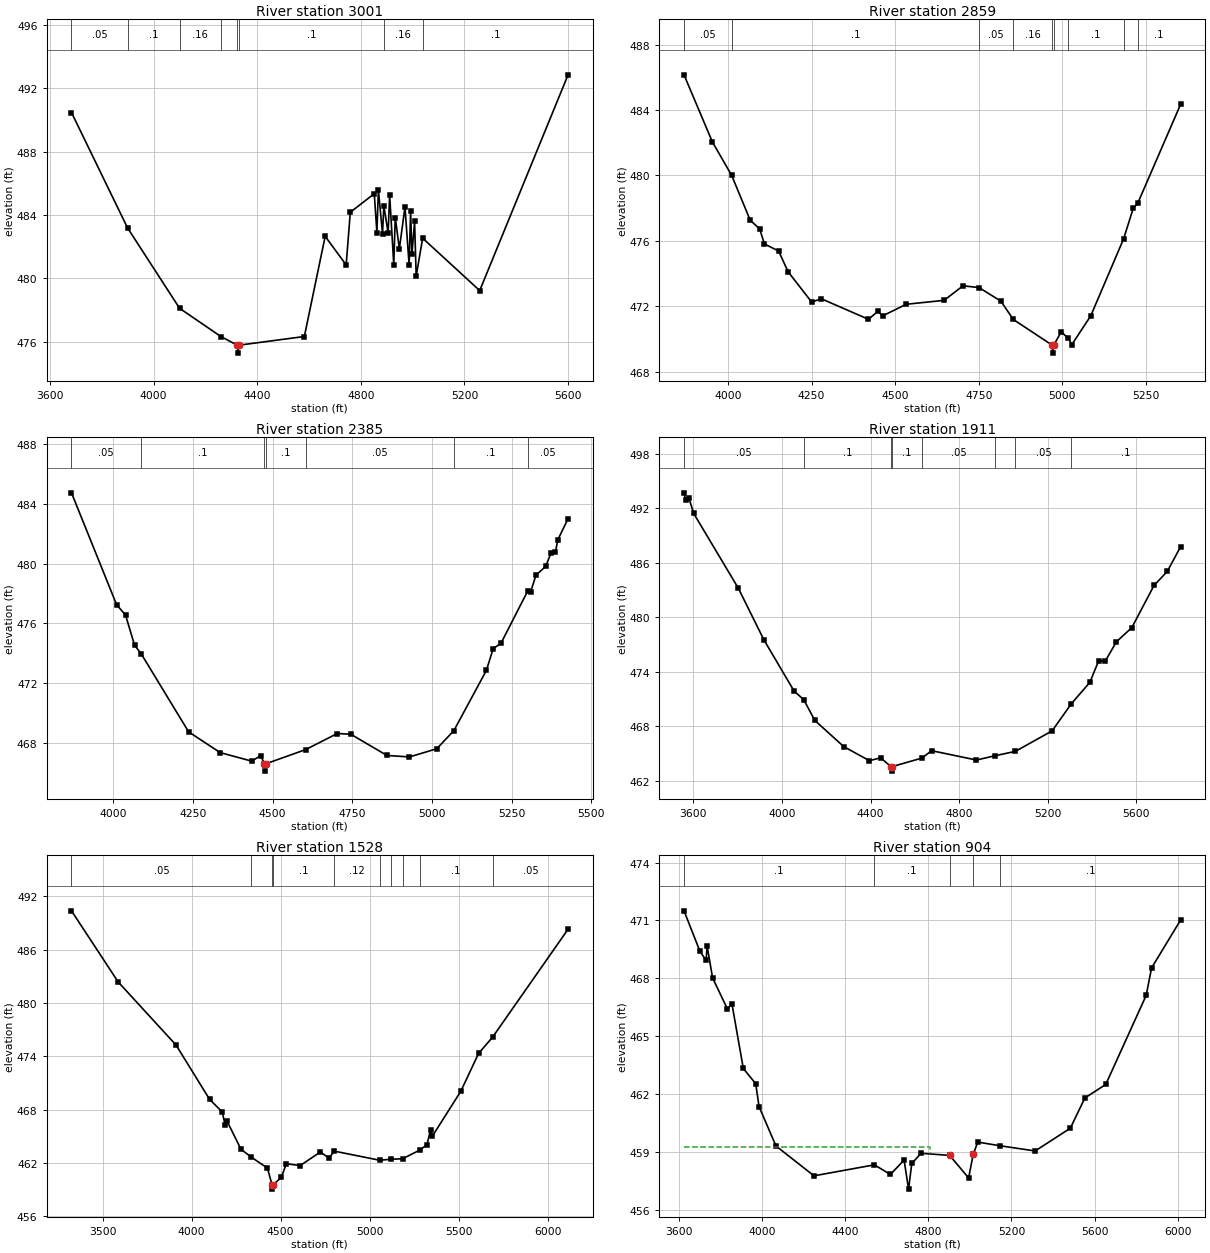
Type RM Length L Ch R = 1 ,3001    ,142,142,142
BEGIN DESCRIPTION:
UNT 021 IN LACR 5.0
END DESCRIPTION:
XS GIS Cut Line= 4
      2174106.84     13197711.39      2173537.43      13197003.1
      2173337.72     13196646.85       2172851.3     13196295.75
#Sta/Elev= 30
  3682.8  490.48  3899.2  483.19  4100.2  478.11  4259.5  476.33  4322.8  475.78
  4325.5  475.28  4328.8  475.78  4581.8  476.33  4662.2  482.66  4743.2  480.85
  4759.2  484.18  4851.7  485.35  4861.9  482.89  4867.6   485.6  4883.6  482.81
  4888.7  484.59  4905.3  482.86    4911  485.28    4927  480.87  4932.7  483.84
  4948.6  481.88  4970.3  484.51  4986.3  480.84    4992  484.24  4997.1  481.53
  5007.4   483.6  5013.5  480.14  5038.5  482.54  5258.8  479.23  5599.9  492.86
#Mann= 8 ,-1 , 0
  3682.8     .05       0  3899.2      .1       0  4100.2     .16       0
  4259.5      .1       0  4322.8     .07       0  4328.8      .1       0
  4888.7     .16       0  5038.5      .1       0
Bank Sta=4322.8,4328.8
XS Rating Curve= 0 ,0
Exp/Cntr=0.3,0.1

Type RM Length L Ch R = 1 ,2859    ,474,474,474
BEGIN DESCRIPTION:
UNT 021 IN LACR 4.0
END DESCRIPTION:
XS GIS Cut Line= 3
      2174237.74     13197346.88      2173437.72     13196546.85
      2173187.69     13196296.82
#Sta/Elev= 30
  3868.6  486.16  3953.5  482.05    4011  480.01  4066.6  477.26  4094.9  476.73
    4109  475.81  4151.5  475.38  4179.8  474.11  4250.5  472.25  4278.8  472.46
  4420.2   471.2  4448.5  471.69  4462.6  471.41  4533.3  472.12  4646.4  472.36
    4703  473.25    4751  473.14  4816.2  472.31  4853.3  471.19  4968.7  469.63
  4971.5  469.13  4974.7  469.63  4996.5  470.43  5018.3  470.03  5028.3  469.65
  5084.9  471.41  5183.3  476.13  5212.1     478  5225.2  478.29  5353.6  484.35
#Mann= 9 ,-1 , 0
  3868.6     .05       0    4011      .1       0    4751     .05       0
  4853.3     .16       0  4968.7     .07       0  4974.7     .16       0
  5018.3      .1       0  5183.3     .16       0  5225.2      .1       0
Bank Sta=4968.7,4974.7
XS Rating Curve= 0 ,0
Exp/Cntr=0.3,0.1

Type RM Length L Ch R = 1 ,2385    ,474,474,474
BEGIN DESCRIPTION:
UNT 021 IN LACR 3.0
END DESCRIPTION:
XS GIS Cut Line= 3
      2174587.74     13197046.88      2173787.72     13196246.86
      2173387.72     13196096.86
#Sta/Elev= 30
  3868.6  484.75  4010.1  477.26  4038.3  476.56  4066.6  474.54    4087  473.98
  4236.3  468.74  4335.3  467.35  4434.3  466.78  4462.6  467.15  4473.7  466.61
  4476.5  466.11  4479.7  466.61  4603.2  467.55    4703  468.63  4745.4  468.58
  4858.6  467.16  4929.3  467.06  5015.1  467.61  5068.7  468.82  5170.9  472.86
  5192.2  474.32  5216.3  474.66  5300.2  478.16  5309.7  478.12  5326.6  479.24
  5356.9  479.82  5373.8  480.73  5387.2  480.76  5395.2  481.61  5427.2  483.02
#Mann= 7 ,-1 , 0
  3868.6     .05       0    4087      .1       0  4473.7     .03       0
  4479.7      .1       0  4603.2     .05       0  5068.7      .1       0
  5300.2     .05       0
Bank Sta=4473.7,4479.7
XS Rating Curve= 0 ,0
Exp/Cntr=0.3,0.1

Type RM Length L Ch R = 1 ,1911    ,383,383,383
BEGIN DESCRIPTION:
UNT 021 IN LACR 2.0
END DESCRIPTION:
XS GIS Cut Line= 3
      2174887.71     13197096.84      2174087.72     13195896.85
      2173287.72     13195896.85
#Sta/Elev= 30
  3557.8  493.68  3565.3  492.86  3580.3  493.07  3601.3  491.42  3802.7   483.2
  3918.3  477.52    4055  471.87  4098.5  470.93  4148.2  468.65  4278.9  465.77
  4394.6  464.22  4445.6  464.53  4492.2  463.57    4495  463.07  4498.2  463.57
  4632.5  464.51  4675.5  465.32  4878.3  464.29  4961.5  464.76  5053.9  465.24
    5220   467.5  5307.2   470.5    5390  472.82    5430   475.2    5460  475.17
    5510  477.29    5580  478.86    5680  483.49    5740  485.04    5800  487.75
#Mann= 8 ,-1 , 0
  3557.8     .05       0  4098.5      .1       0  4492.2     .07       0
  4498.2      .1       0  4632.5     .05       0  4961.5      .1       0
  5053.9     .05       0  5307.2      .1       0
Bank Sta=4492.2,4498.2
XS Rating Curve= 0 ,0
Exp/Cntr=0.3,0.1

Type RM Length L Ch R = 1 ,1528    ,624,624,624
BEGIN DESCRIPTION:
Mapping XS 35f5a7ee
END DESCRIPTION:
XS GIS Cut Line= 4
      2174993.15     13196996.98      2174888.99     13196137.65
      2174107.74     13195434.52      2173235.33     13195447.54
#Sta/Elev= 30
  3325.7  490.36  3587.7  482.36  3913.1  475.25  4101.5  469.14    4172  467.73
  4189.2  466.24  4199.9  466.67  4277.6  463.53  4336.2  462.63  4426.3  461.41
  4451.7  459.54  4454.5  459.04  4457.7  459.54  4504.1  460.35  4532.5   461.9
  4610.2  461.69  4723.8  463.22  4773.1  462.51  4800.2  463.32  5057.3  462.29
  5118.5   462.4  5185.9  462.46  5281.7  463.43  5322.4  464.04  5342.4  465.71
  5352.4  464.99  5512.4  470.05  5612.4  474.32  5690.9  476.14  6114.9  488.29
#Mann= 10 ,-1 , 0
  3325.7     .05       0  4336.2      .1       0  4451.7     .07       0
  4457.7      .1       0  4800.2     .12       0  5057.3     .05       0
  5118.5      .1       0  5185.9     .05       0  5281.7      .1       0
  5690.9     .05       0
Bank Sta=4451.7,4457.7
XS Rating Curve= 0 ,0
Exp/Cntr=0.3,0.1

Type RM Length L Ch R = 1 ,904     ,658,658,658
BEGIN DESCRIPTION:
Mapping XS 7d55299a
END DESCRIPTION:
XS GIS Cut Line= 4
      2175191.62     13196312.27      2175024.95     13195353.92
      2174399.95     13195013.64      2173698.54     13194971.98
#Sta/Elev= 30
    3626   471.5  3702.5   469.4  3732.1  468.93  3737.2  469.66  3763.4  468.02
  3834.5  466.41  3856.4  466.67    3911  463.32  3970.6  462.53  3986.7  461.34
    4068   459.3  4250.7  457.75    4541  458.32  4618.3  457.82  4683.8  458.57
  4705.4  457.06  4720.8  458.39  4765.5  458.92    4903  458.81  4994.1  457.64
  5016.2  458.87  5038.1   459.5  5144.9  459.31    5314  459.04  5482.9  460.22
    5553  461.79  5653.2  462.49  5847.5  467.11  5873.6  468.54    6013  471.02
#Mann= 5 ,-1 , 0
    3626      .1       0    4541      .1       0    4903     .07       0
  5016.2      .1       0  5144.9      .1       0
#XS Ineff= 2 , 0
         4809.09  459.22
Permanent Ineff=
       F       F
Bank Sta=4903,5016.2
XS Rating Curve= 0 ,0
Exp/Cntr=0.3,0.1

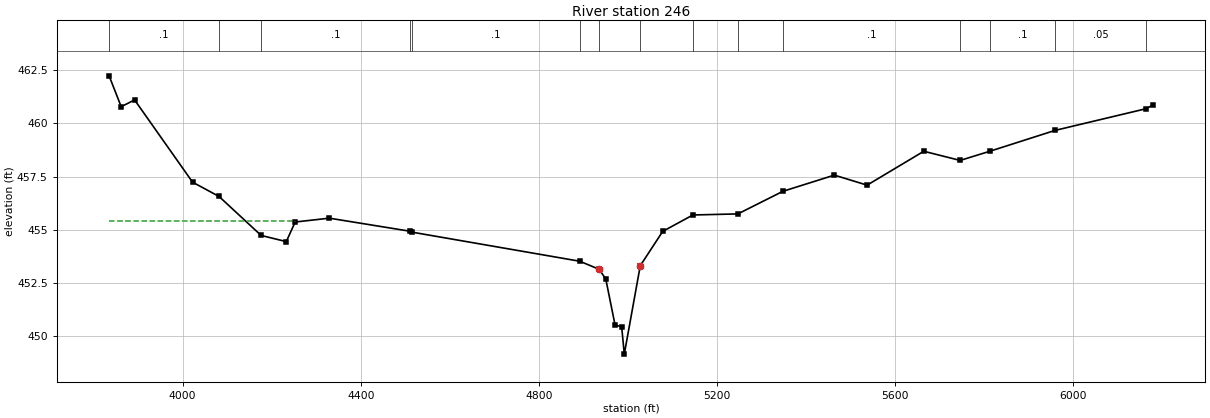
Type RM Length L Ch R = 1 ,246     ,0,0,0
BEGIN DESCRIPTION:
UNT 021 IN LACR 1.0
END DESCRIPTION:
XS GIS Cut Line= 4
      2175351.34     13196103.92      2175413.84     13195117.81
      2175170.78      13194944.2      2174151.37     13194659.87
#Sta/Elev= 30
  3834.8  462.23  3861.9  460.78    3892   461.1  4022.2  457.24  4081.6  456.57
  4176.2  454.74  4232.7  454.45  4252.7  455.37  4329.4  455.55  4509.8  454.94
  4516.2  454.89  4891.7  453.53  4935.6  453.15  4950.4  452.69  4971.2  450.53
    4986  450.46  4991.9  449.17  5027.8  453.32  5078.2  454.93    5146   455.7
    5247  455.75  5348.1  456.81  5463.7  457.57  5537.3   457.1  5664.6  458.69
  5746.3  458.26  5814.4   458.7  5959.6  459.67  6164.5  460.69  6179.9  460.87
#Mann= 15 ,-1 , 0
  3834.8      .1       0  4081.6     .05       0  4176.2      .1       0
  4509.8     .05       0  4516.2      .1       0  4891.7     .12       0
  4935.6     .07       0  5027.8     .12       0    5146      .1       0
    5247     .05       0  5348.1      .1       0  5746.3     .05       0
  5814.4      .1       0  5959.6     .05       0  6164.5      .1       0
#XS Ineff= 2 , 0
         4253.41  455.41
Permanent Ineff=
       F       F
Bank Sta=4935.6,5027.8
XS Rating Curve= 0 ,0
Exp/Cntr=0.3,0.1

Chan Stop Cuts=-1
Use User Specified Reach Order=0
Composite Channel Slope=5