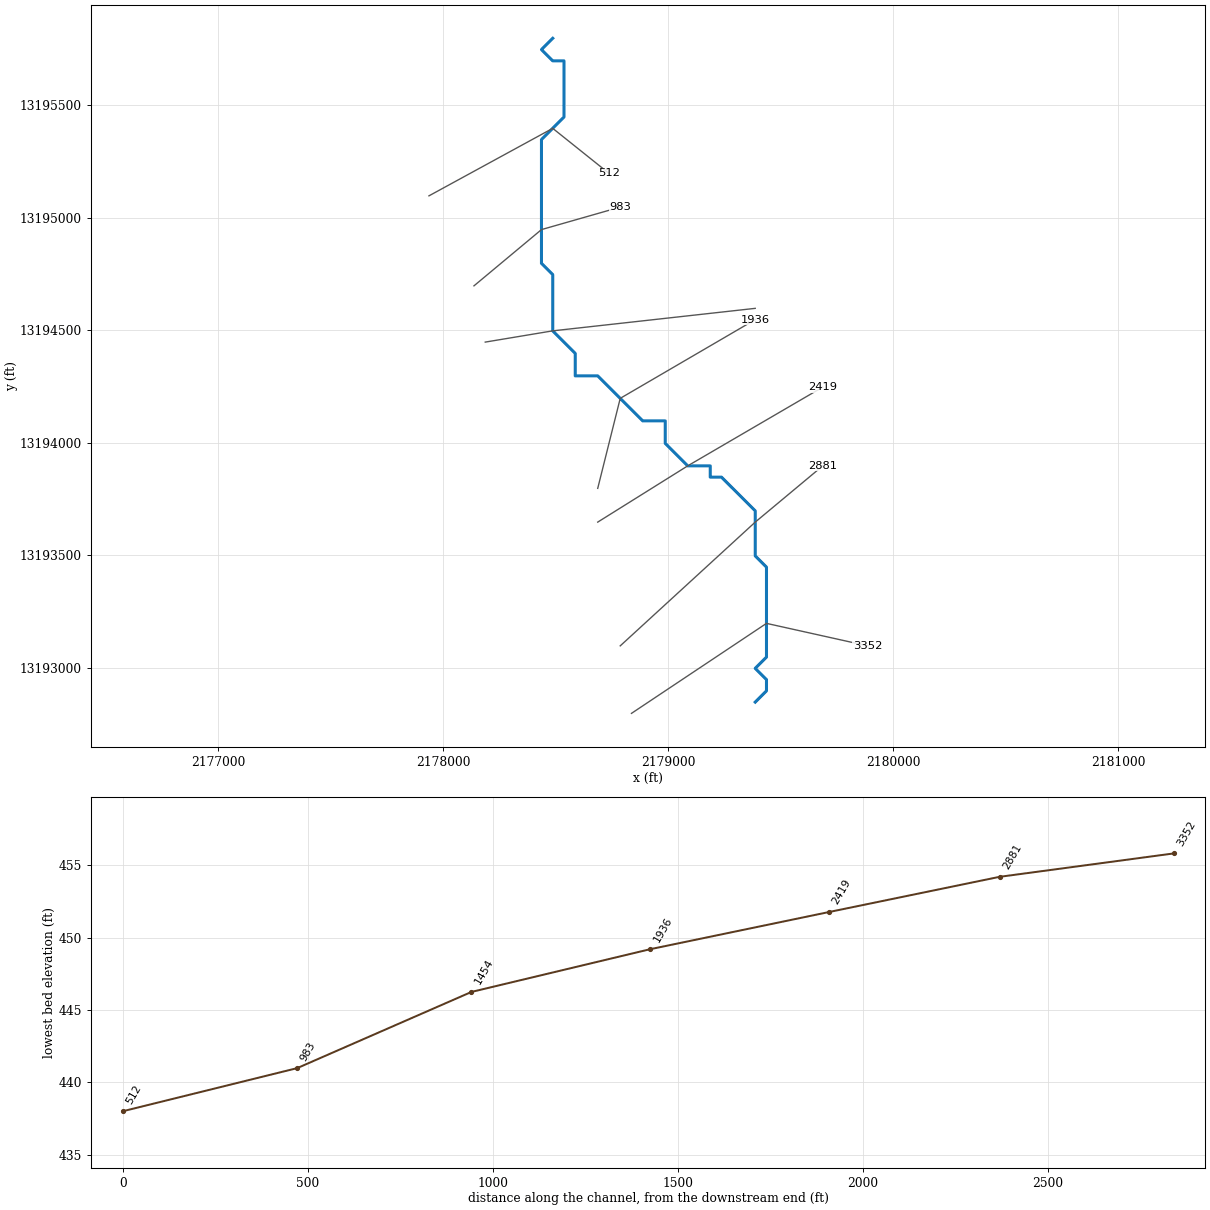
--- UNT 022 IN LACR.prj (project) ---

Proj Title=UNT 022 IN LACR Base Level Engineering
Current Plan=p01
Default Exp/Contr=0.3,0.1
English Units
Geom File=g01
Flow File=f01
Plan File=p01
BEGIN DESCRIPTION:
UNT 022 IN LACR
END DESCRIPTION:

--- UNT 022 IN LACR.p01 (plan) ---

Plan Title=Multiple Run
Short Identifier=Multiple
Geom File=g01
Flow File=f01
Subcritical Flow
K Sum by GR= 0
Std Step Tol= 0.01
Critical Tol= 0.01
Num of Std Step Trials= 20
Max Error Tol= 0.3
Flow Tol Ratio= 0.001
Split Flow NTrial= 30
Split Flow Tol= 0.02
Split Flow Ratio= 0.02
Log Output Level= 0
Friction Slope Method= 1
Unsteady Friction Slope Method= 2
Unsteady Bridges Friction Slope Method= 1
Parabolic Critical Depth
Global Vel Dist=  1 , 1 , 1
Global Log Level= 0
CheckData=True
Encroach Param= -1, 0, 0, 0
BEGIN DESCRIPTION:
Multiple Run
END DESCRIPTION:

--- UNT 022 IN LACR.f01 (steady flow) ---

Flow Title=Multiple
Number of Profiles=7
Profile Names=10-year,25-year,50-year,1pct_min,100-year,1pct_plu,500-year
River Rch & RM= UNT 022 IN LACR,Reach-1,3352
     177     244     300     272     367     497     559
Boundary for River Rch & Prof#=UNT 022 IN LACR,Reach-1,1
Up Type=0
Dn Type=3
Dn Slope=0.005
Boundary for River Rch & Prof#=UNT 022 IN LACR,Reach-1,2
Up Type=0
Dn Type=3
Dn Slope=0.005
Boundary for River Rch & Prof#=UNT 022 IN LACR,Reach-1,3
Up Type=0
Dn Type=3
Dn Slope=0.005
Boundary for River Rch & Prof#=UNT 022 IN LACR,Reach-1,4
Up Type=0
Dn Type=3
Dn Slope=0.005
Boundary for River Rch & Prof#=UNT 022 IN LACR,Reach-1,5
Up Type=0
Dn Type=3
Dn Slope=0.005
Boundary for River Rch & Prof#=UNT 022 IN LACR,Reach-1,6
Up Type=0
Dn Type=3
Dn Slope=0.005
Boundary for River Rch & Prof#=UNT 022 IN LACR,Reach-1,7
Up Type=0
Dn Type=3
Dn Slope=0.005

--- UNT 022 IN LACR.g01 (geometry) ---

Geom Title=Existing Conditions

River Reach=UNT 022 IN LACR,Reach-1
Reach XY= 30
      2179387.72     13192846.85      2179437.72     13192896.85
      2179437.72     13192946.85      2179387.72     13192996.85
      2179437.72     13193046.85      2179437.72     13193446.86
      2179387.72     13193496.85      2179387.72     13193696.85
      2179287.72     13193796.86      2179237.72     13193846.85
      2179187.72     13193846.85      2179187.72     13193896.85
      2179087.72     13193896.85      2179037.72     13193946.86
      2178987.72     13193996.85      2178987.72     13194096.85
      2178887.72     13194096.85      2178687.72     13194296.86
      2178587.72     13194296.86      2178587.72     13194396.85
      2178537.72     13194446.86      2178487.72     13194496.85
      2178487.72     13194746.85      2178437.72     13194796.86
      2178437.72     13195346.85      2178537.72     13195446.86
      2178537.72     13195696.85      2178487.72     13195696.85
      2178437.72     13195746.86      2178487.72     13195796.85

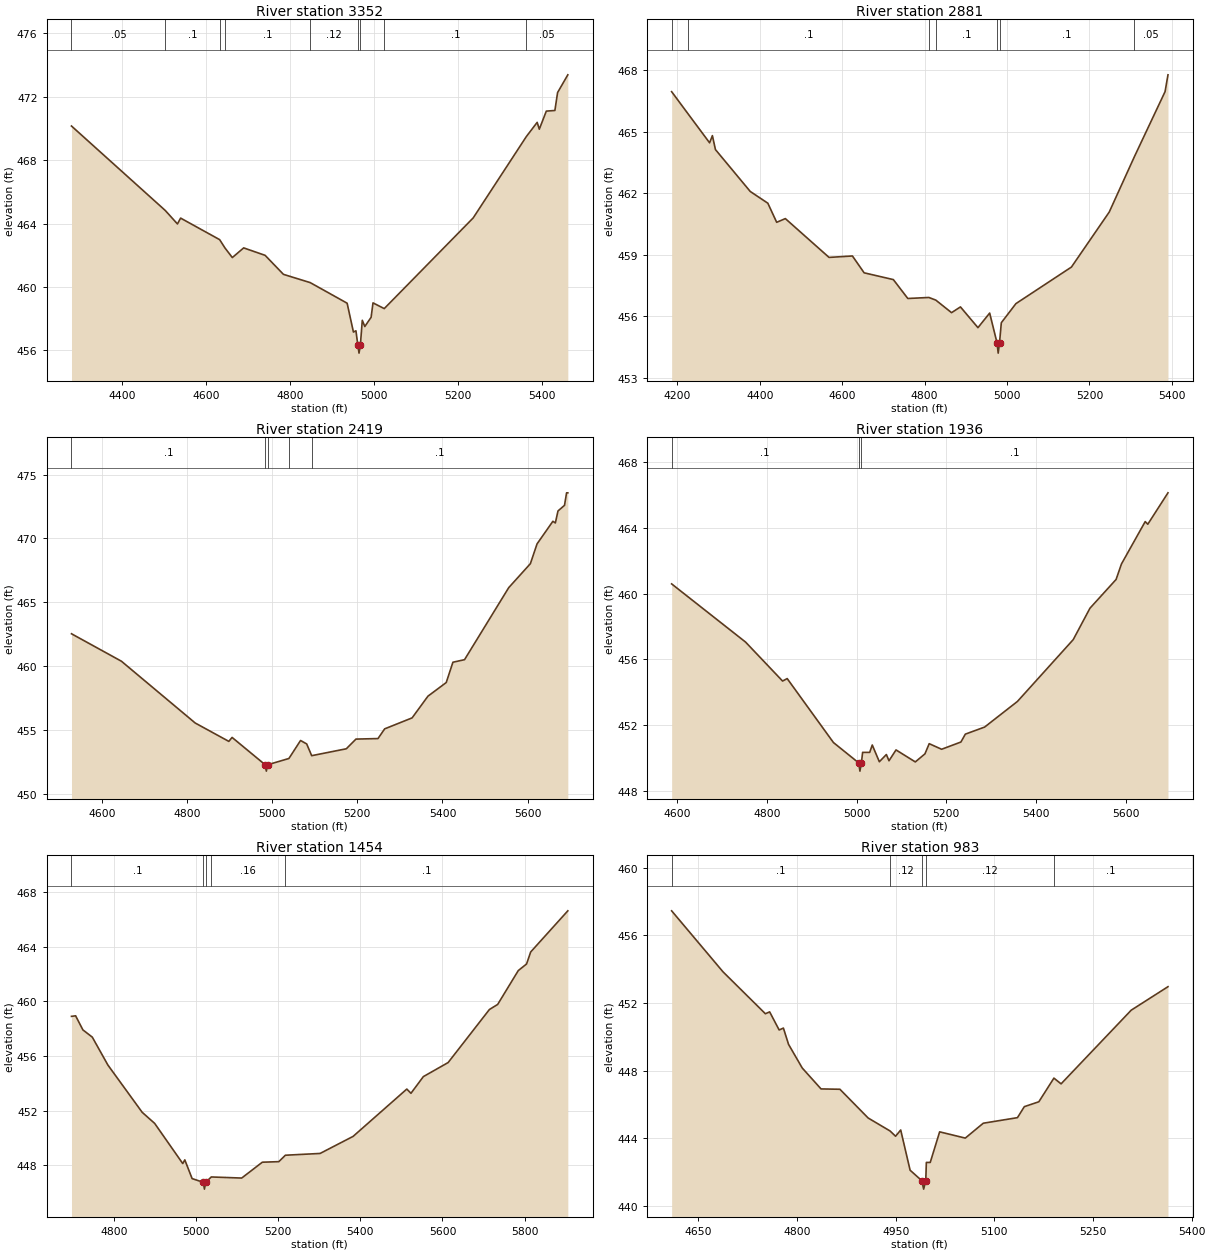
Type RM Length L Ch R = 1,3352,471,471,471
BEGIN DESCRIPTION:
UNT 022 IN LACR 7.0
END DESCRIPTION:
XS GIS Cut Line= 3
      2178837.73     13192796.86      2179437.72     13193196.85
      2179887.74     13193096.85
#Sta/Elev= 30
  4278.9  470.16  4502.3  464.83  4531.3  463.98  4538.8  464.35  4631.8  462.99
  4644.6  462.46  4662.0  461.86  4689.0  462.47  4740.1  462.00  4783.7  460.80
  4847.4  460.28  4935.4  458.98  4950.4  457.16  4956.4  457.24  4960.9  456.33
  4963.7  455.83  4966.9  456.33  4971.5  457.90  4977.5  457.51  4992.5  458.09
  4997.0  459.00  5023.8  458.64  5235.6  464.36  5362.1  469.49  5388.0  470.39
  5393.1  469.96  5409.8  471.10  5430.2  471.14  5436.6  472.27  5461.0  473.39
#Mann=9,-1,0
  4278.9    0.05       0  4502.3     0.1       0  4631.8    0.05       0
  4644.6     0.1       0  4847.4    0.12       0  4960.9    0.07       0
  4966.9    0.12       0  5023.8     0.1       0  5362.1    0.05       0
Bank Sta=4960.9,4966.9
Exp/Cntr=0.3,0.1

Type RM Length L Ch R = 1,2881,462,462,462
BEGIN DESCRIPTION:
UNT 022 IN LACR 6.0
END DESCRIPTION:
XS GIS Cut Line= 3
      2178787.75     13193096.88      2179387.72     13193646.86
      2179687.71     13193896.85
#Sta/Elev= 30
  4186.1  466.94  4225.6  465.87  4278.2  464.45  4285.0  464.80  4292.4  464.12
  4376.9  462.08  4419.5  461.51  4441.0  460.58  4462.0  460.76  4568.1  458.87
  4624.8  458.94  4653.2  458.12  4724.1  457.79  4759.2  456.87  4810.3  456.92
  4827.2  456.79  4865.3  456.18  4886.9  456.46  4929.4  455.45  4957.8  456.16
  4975.7  454.71  4978.5  454.21  4981.7  454.71  4986.1  455.69  5021.5  456.62
  5156.2  458.40  5248.0  461.08  5308.9  463.77  5383.4  466.94  5390.5  467.76
#Mann=7,-1,0
  4186.1    0.05       0  4225.6     0.1       0  4810.3    0.12       0
  4827.2     0.1       0  4975.7    0.07       0  4981.7     0.1       0
  5308.9    0.05       0
Bank Sta=4975.7,4981.7
Exp/Cntr=0.3,0.1

Type RM Length L Ch R = 1,2419,483,483,483
BEGIN DESCRIPTION:
UNT 022 IN LACR 5.0
END DESCRIPTION:
XS GIS Cut Line= 3
      2178687.72     13193646.85      2179087.72     13193896.85
      2179687.70     13194246.84
#Sta/Elev= 30
  4528.3  462.53  4645.6  460.38  4819.0  455.54  4898.0  454.10  4905.7  454.41
  4983.4  452.27  4986.2  451.77  4989.4  452.27  5039.2  452.76  5066.6  454.17
  5081.0  453.90  5092.7  452.98  5174.1  453.52  5196.8  454.28  5248.5  454.32
  5264.2  455.08  5328.7  455.94  5365.9  457.64  5408.9  458.71  5424.6  460.30
  5451.9  460.50  5555.7  466.14  5606.6  468.02  5622.3  469.57  5659.5  471.34
  5665.3  471.21  5671.5  472.15  5686.8  472.59  5691.7  473.57  5694.6  473.57
#Mann=5,-1,0
  4528.3     0.1       0  4983.4    0.07       0  4989.4     0.1       0
  5039.2    0.12       0  5092.7     0.1       0
Bank Sta=4983.4,4989.4
Exp/Cntr=0.3,0.1

Type RM Length L Ch R = 1,1936,482,482,482
BEGIN DESCRIPTION:
UNT 022 IN LACR 4.0
END DESCRIPTION:
XS GIS Cut Line= 3
      2178687.72     13193796.87      2178787.72     13194196.85
      2179387.70     13194546.84
#Sta/Elev= 30
  4587.7  460.59  4752.6  457.05  4835.1  454.68  4845.4  454.83  4948.5  450.94
  5004.9  449.70  5007.6  449.20  5010.9  449.70  5013.6  450.34  5029.4  450.34
  5035.1  450.79  5050.9  449.77  5066.6  450.21  5072.4  449.83  5088.1  450.49
  5131.1  449.76  5152.6  450.25  5162.1  450.87  5189.8  450.53  5232.8  450.97
  5242.7  451.45  5285.7  451.88  5358.9  453.44  5483.3  457.20  5520.6  459.11
  5578.9  460.86  5590.8  461.80  5643.8  464.38  5649.6  464.22  5694.6  466.13
#Mann=3,-1,0
  4587.7     0.1       0  5004.9    0.07       0  5010.9     0.1       0
Bank Sta=5004.9,5010.9
Exp/Cntr=0.3,0.1

Type RM Length L Ch R = 1,1454,471,471,471
BEGIN DESCRIPTION:
UNT 022 IN LACR 3.0
END DESCRIPTION:
XS GIS Cut Line= 3
      2178187.76     13194446.86      2178487.72     13194496.85
      2179387.68     13194596.85
#Sta/Elev= 30
  4695.9  458.89  4706.0  458.93  4723.7  457.90  4746.6  457.37  4784.6  455.33
  4868.2  451.87  4898.6  451.06  4967.1  448.12  4972.1  448.39  4989.9  447.02
  5017.1  446.75  5019.9  446.25  5023.1  446.75  5036.6  447.14  5110.7  447.06
  5161.0  448.22  5201.2  448.26  5217.2  448.73  5301.8  448.86  5382.3  450.11
  5513.1  453.57  5523.2  453.26  5553.4  454.48  5613.8  455.51  5714.4  459.39
  5734.5  459.76  5784.8  462.24  5804.9  462.72  5815.0  463.60  5905.5  466.61
#Mann=5,-1,0
  4695.9     0.1       0  5017.1    0.07       0  5023.1     0.1       0
  5036.6    0.16       0  5217.2     0.1       0
Bank Sta=5017.1,5023.1
Exp/Cntr=0.3,0.1

Type RM Length L Ch R = 1,983,471,471,471
BEGIN DESCRIPTION:
UNT 022 IN LACR 2.0
END DESCRIPTION:
XS GIS Cut Line= 3
      2178137.73     13194696.86      2178437.72     13194946.86
      2178787.72     13195046.85
#Sta/Elev= 30
  4609.5  457.45  4687.6  453.84  4752.0  451.36  4758.5  451.47  4772.9  450.40
  4779.4  450.51  4787.2  449.55  4808.0  448.15  4836.6  446.91  4865.3  446.89
  4908.2  445.19  4941.6  444.42  4949.9  444.11  4957.7  444.48  4972.0  442.10
  4989.8  441.48  4992.6  440.98  4995.8  441.48  4996.7  442.56  5002.6  442.56
  5016.9  444.37  5055.9  444.00  5083.2  444.88  5135.2  445.21  5145.6  445.86
  5167.7  446.15  5190.6  447.55  5201.5  447.21  5308.1  451.57  5364.0  452.96
#Mann=5,-1,0
  4609.5     0.1       0  4941.6    0.12       0  4989.8    0.07       0
  4995.8    0.12       0  5190.6     0.1       0
Bank Sta=4989.8,4995.8
Exp/Cntr=0.3,0.1

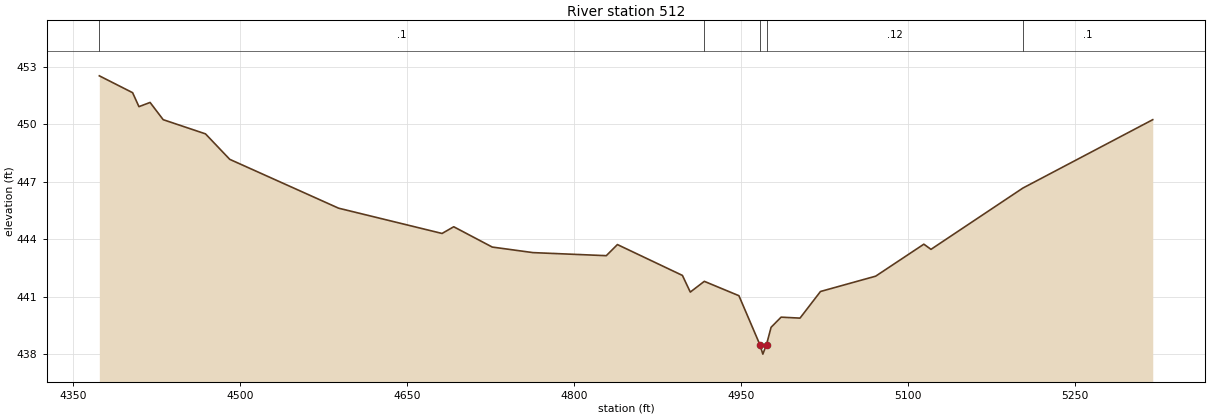
Type RM Length L Ch R = 1,512,0,0,0
BEGIN DESCRIPTION:
UNT 022 IN LACR 1.0
END DESCRIPTION:
XS GIS Cut Line= 3
      2177937.72     13195096.85      2178487.72     13195396.85
      2178737.75     13195196.83
#Sta/Elev= 30
  4373.5  452.53  4403.4  451.65  4409.1  450.92  4419.1  451.14  4430.9  450.24
  4468.9  449.50  4490.7  448.17  4588.5  445.62  4681.5  444.30  4692.0  444.65
  4726.6  443.59  4763.2  443.30  4829.1  443.14  4839.1  443.72  4897.5  442.11
  4904.6  441.24  4917.2  441.80  4948.3  441.05  4967.1  438.50  4969.8  438.00
  4973.1  438.50  4977.2  439.40  4986.2  439.93  5003.2  439.88  5021.6  441.27
  5071.2  442.07  5114.5  443.74  5120.9  443.47  5203.5  446.67  5320.2  450.24
#Mann=5,-1,0
  4373.5     0.1       0  4917.2    0.12       0  4967.1    0.07       0
  4973.1    0.12       0  5203.5     0.1       0
Bank Sta=4967.1,4973.1
Exp/Cntr=0.3,0.1

Chan Stop Cuts=-1