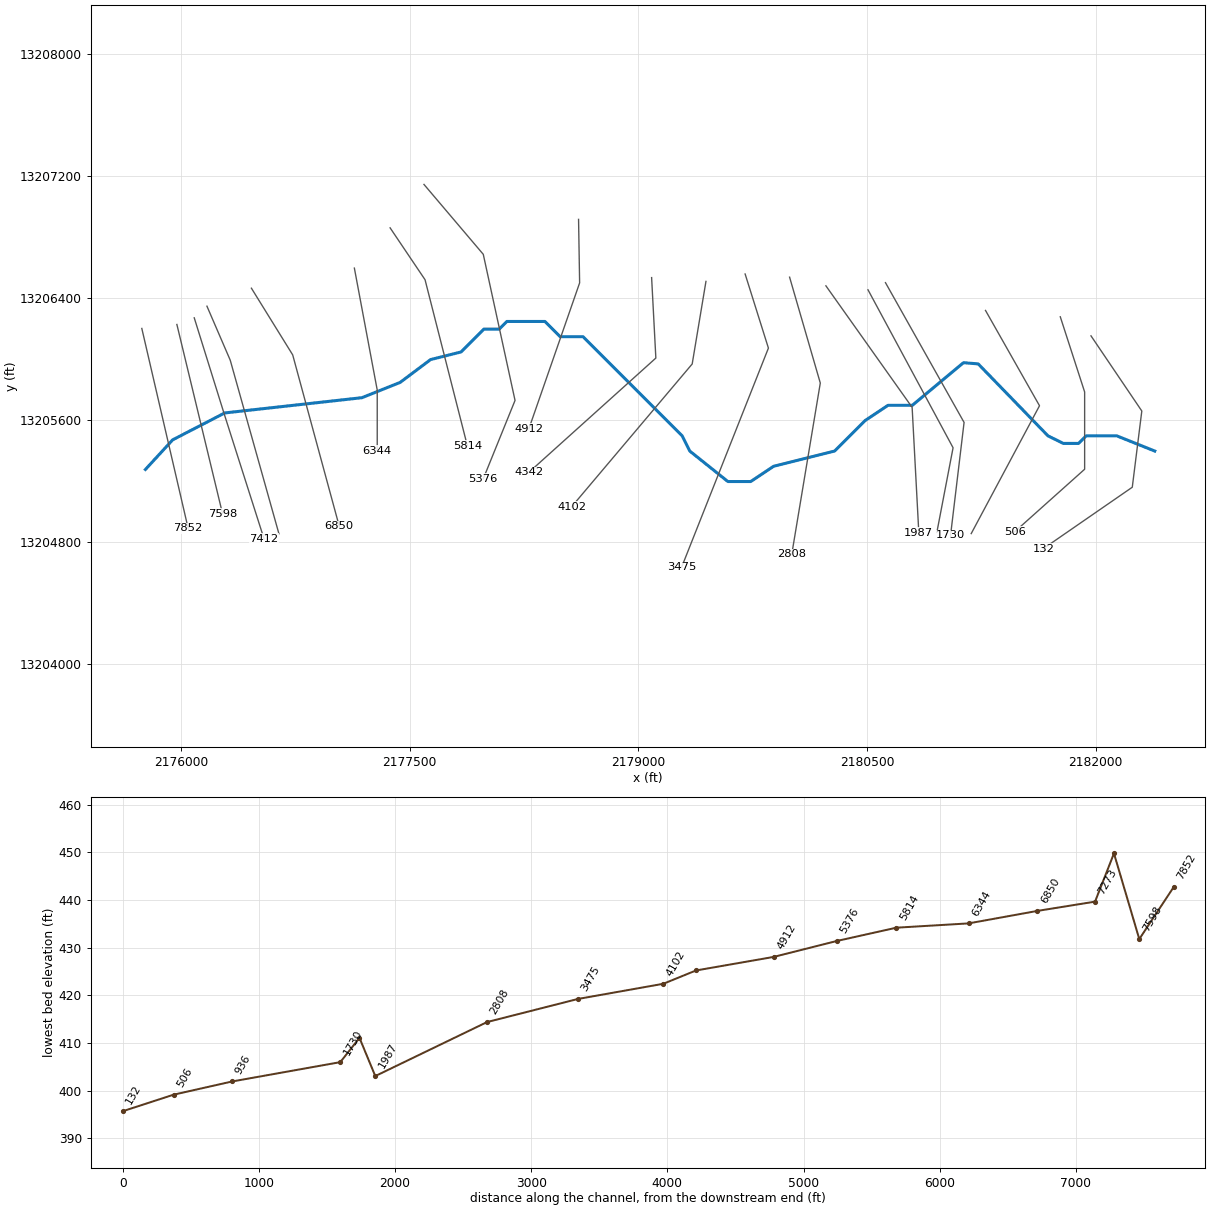
--- UNT 023 IN LACR.prj (project) ---

Proj Title=UNT 023 IN LACR Base Level Engineering
Current Plan=p01
Default Exp/Contr=0.3,0.1
English Units
Geom File=g01
Flow File=f01
Plan File=p01
BEGIN DESCRIPTION:
UNT 023 IN LACR
END DESCRIPTION:

--- UNT 023 IN LACR.p01 (plan) ---

Plan Title=Multiple Run
Short Identifier=Multiple
Geom File=g01
Flow File=f01
Subcritical Flow
K Sum by GR= 0
Std Step Tol= 0.01
Critical Tol= 0.01
Num of Std Step Trials= 20
Max Error Tol= 0.3
Flow Tol Ratio= 0.001
Split Flow NTrial= 30
Split Flow Tol= 0.02
Split Flow Ratio= 0.02
Log Output Level= 0
Friction Slope Method= 1
Unsteady Friction Slope Method= 2
Unsteady Bridges Friction Slope Method= 1
Parabolic Critical Depth
Global Vel Dist=  1 , 1 , 1
Global Log Level= 0
CheckData=True
Encroach Param= -1, 0, 0, 0
BEGIN DESCRIPTION:
Multiple Run
END DESCRIPTION:

--- UNT 023 IN LACR.f01 (steady flow) ---

Flow Title=Multiple
Number of Profiles=7
Profile Names=10-year,25-year,50-year,1pct_min,100-year,1pct_plu,500-year
River Rch & RM= UNT 023 IN LACR,Reach-1,7852
     224     317     395     363     492     665     772
River Rch & RM= UNT 023 IN LACR,Reach-1,7598
     322     461     579     536     724     980    1151
Boundary for River Rch & Prof#=UNT 023 IN LACR,Reach-1,1
Up Type=0
Dn Type=3
Dn Slope=0.005
Boundary for River Rch & Prof#=UNT 023 IN LACR,Reach-1,2
Up Type=0
Dn Type=3
Dn Slope=0.005
Boundary for River Rch & Prof#=UNT 023 IN LACR,Reach-1,3
Up Type=0
Dn Type=3
Dn Slope=0.005
Boundary for River Rch & Prof#=UNT 023 IN LACR,Reach-1,4
Up Type=0
Dn Type=3
Dn Slope=0.005
Boundary for River Rch & Prof#=UNT 023 IN LACR,Reach-1,5
Up Type=0
Dn Type=3
Dn Slope=0.005
Boundary for River Rch & Prof#=UNT 023 IN LACR,Reach-1,6
Up Type=0
Dn Type=3
Dn Slope=0.005
Boundary for River Rch & Prof#=UNT 023 IN LACR,Reach-1,7
Up Type=0
Dn Type=3
Dn Slope=0.005

--- UNT 023 IN LACR.g01 (geometry) ---

Geom Title=Existing Conditions

River Reach=UNT 023 IN LACR,Reach-1
Reach XY= 30
      2175767.02     13205275.84      2175945.84     13205470.28
      2176287.72     13205646.85      2177187.72     13205746.86
      2177437.72     13205846.85      2177637.72     13205996.85
      2177837.72     13206046.85      2177987.72     13206196.85
      2178087.72     13206196.85      2178137.72     13206246.86
      2178387.72     13206246.86      2178487.72     13206146.85
      2178637.72     13206146.85      2179287.72     13205496.85
      2179337.72     13205396.85      2179587.72     13205196.85
      2179737.72     13205196.85      2179887.72     13205296.85
      2180287.72     13205396.85      2180487.72     13205596.86
      2180637.72     13205696.85      2180797.54     13205696.85
      2181132.74     13205976.37      2181229.44     13205968.63
      2181686.88     13205496.85      2181787.72     13205446.86
      2181887.72     13205446.86      2181937.72     13205496.85
      2182137.72     13205496.85      2182387.72     13205396.85

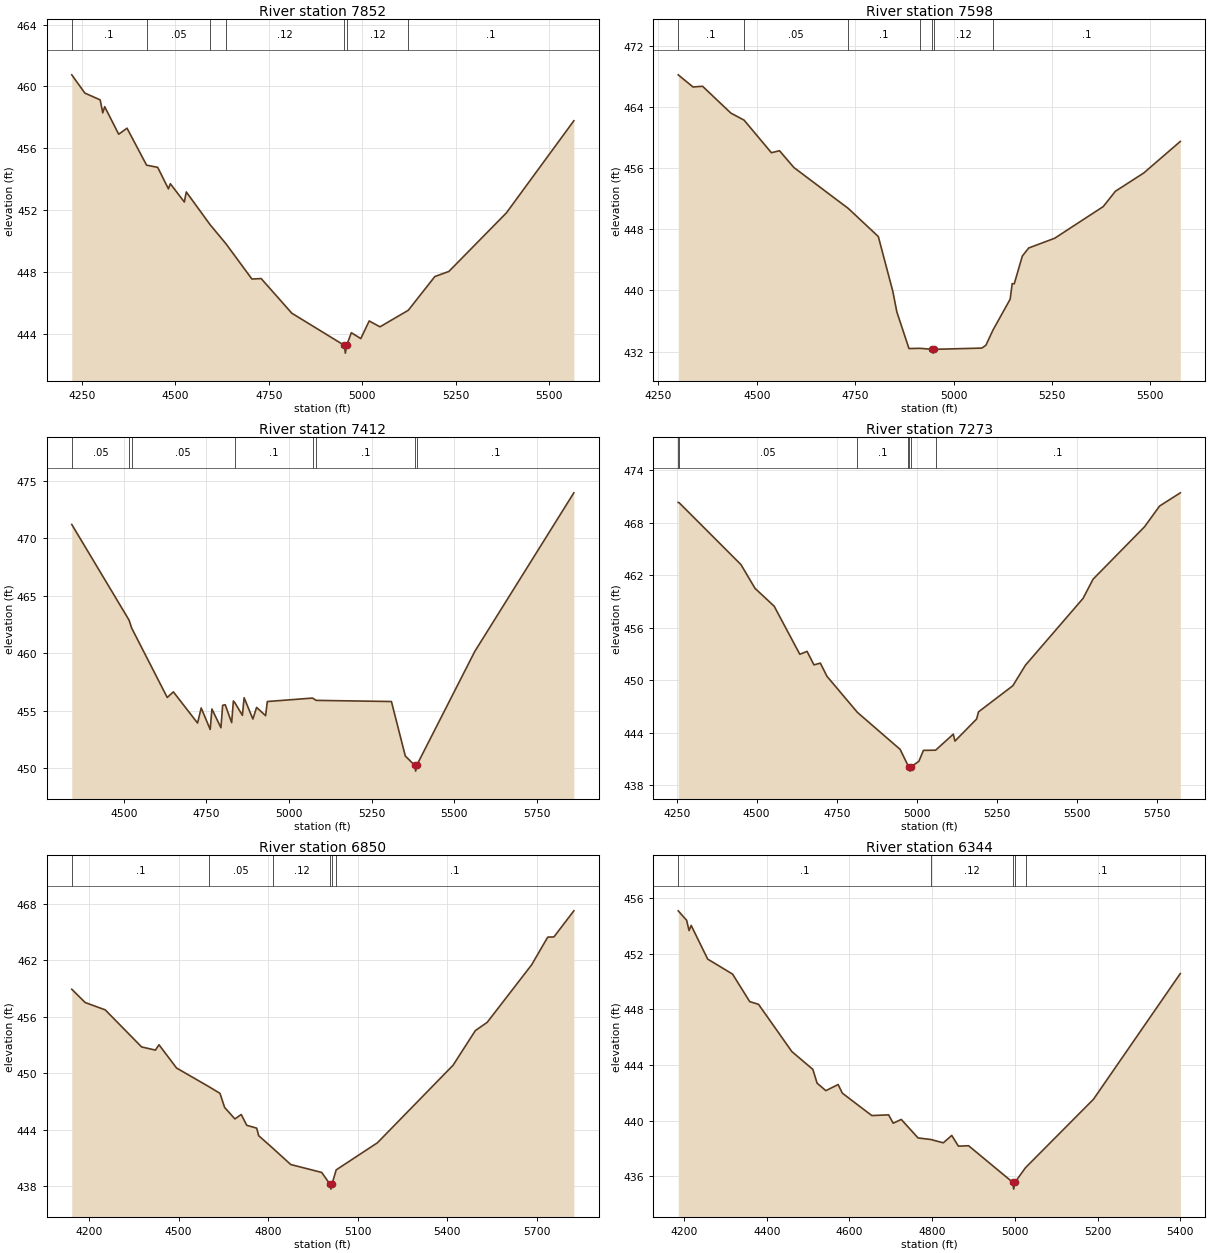
Type RM Length L Ch R = 1,7852,254,254,254
BEGIN DESCRIPTION:
UNT 023 IN LACR 14.0
END DESCRIPTION:
XS GIS Cut Line= 2
      2175743.56     13206201.01      2176047.20     13204891.04
#Sta/Elev= 30
  4222.2  460.75  4257.3  459.57  4298.3  459.13  4305.2  458.29  4310.4  458.69
  4347.9  456.91  4370.2  457.30  4422.6  454.91  4452.3  454.77  4481.1  453.38
  4486.2  453.71  4523.7  452.53  4528.9  453.18  4592.8  451.06  4635.5  449.82
  4704.7  447.55  4729.5  447.58  4811.6  445.34  4952.3  443.26  4955.0  442.76
  4958.3  443.26  4971.0  444.08  4996.3  443.70  5018.8  444.84  5047.7  444.46
  5123.5  445.53  5194.6  447.71  5232.2  448.04  5386.4  451.83  5566.9  457.78
#Mann=7,-1,0
  4222.2     0.1       0  4422.6    0.05       0  4592.8     0.1       0
  4635.5    0.12       0  4952.3    0.07       0  4958.3    0.12       0
  5123.5     0.1       0
Bank Sta=4952.3,4958.3
Exp/Cntr=0.3,0.1

Type RM Length L Ch R = 1,7598,186,186,186
BEGIN DESCRIPTION:
Mapping XS 63251c88
END DESCRIPTION:
XS GIS Cut Line= 2
      2175973.60     13206227.04      2176272.91     13204986.43
#Sta/Elev= 30
  4300.3  468.27  4337.8  466.68  4362.2  466.77  4434.2  463.25  4467.7  462.33
  4537.1  458.06  4557.7  458.32  4594.3  456.12  4732.7  450.75  4808.9  447.07
  4845.7  439.90  4856.0  437.19  4886.8  432.39  4914.9  432.42  4945.6  432.29
  4948.3  431.79  4951.6  432.29  5072.0  432.45  5082.3  432.82  5100.2  434.80
  5144.0  438.86  5149.2  440.90  5154.4  440.88  5174.9  444.51  5191.1  445.57
  5257.2  446.85  5380.6  451.00  5411.5  453.01  5483.5  455.40  5576.5  459.54
#Mann=7,-1,0
  4300.3     0.1       0  4467.7    0.05       0  4732.7     0.1       0
  4914.9    0.12       0  4945.6    0.07       0  4951.6    0.12       0
  5100.2     0.1       0
Bank Sta=4945.6,4951.6
Exp/Cntr=0.3,0.1

Type RM Length L Ch R = 1,7412,139,139,139
BEGIN DESCRIPTION:
UNT 023 IN LACR 13.0
END DESCRIPTION:
XS GIS Cut Line= 3
      2176087.44     13206270.62      2176288.84     13205624.75
      2176545.36     13204820.51
#Sta/Elev= 30
  4342.0  471.19  4515.7  462.87  4523.0  462.21  4631.2  456.15  4649.7  456.64
  4723.0  453.93  4734.0  455.24  4761.3  453.37  4766.5  455.15  4793.8  453.52
  4799.0  455.47  4806.8  455.52  4826.3  453.97  4831.5  455.85  4836.4  455.68
  4858.8  454.60  4864.0  456.13  4890.6  454.28  4901.8  455.29  4929.1  454.57
  4934.3  455.80  5071.2  456.10  5082.1  455.90  5310.2  455.80  5352.2  451.07
  5380.7  450.25  5383.5  449.75  5386.7  450.25  5562.6  460.15  5862.7  473.94
#Mann=8,-1,0
  4342.0    0.05       0  4515.7     0.1       0  4523.0    0.05       0
  4836.4     0.1       0  5071.2    0.12       0  5082.1     0.1       0
  5380.7    0.07       0  5386.7     0.1       0
Bank Sta=5380.7,5386.7
Exp/Cntr=0.3,0.1

Type RM Length L Ch R = 1,7273,423,423,423
BEGIN DESCRIPTION:
UNT 023 IN LACR 12.0
END DESCRIPTION:
XS GIS Cut Line= 3
      2176170.79     13206346.96      2176323.56     13205992.81
      2176642.86     13204854.44
#Sta/Elev= 30
  4255.0  470.31  4257.0  470.31  4451.1  463.21  4494.7  460.51  4554.6  458.47
  4634.7  452.98  4657.3  453.31  4678.9  451.77  4698.8  451.97  4719.6  450.46
  4814.5  446.35  4948.1  442.12  4971.5  440.36  4976.2  440.14  4979.0  439.64
  4982.2  440.14  5006.5  440.76  5020.8  442.01  5058.8  442.03  5114.0  443.86
  5119.2  443.07  5186.9  445.59  5192.6  446.40  5300.0  449.39  5339.3  451.73
  5519.3  459.36  5550.5  461.55  5711.4  467.54  5758.2  469.90  5823.0  471.41
#Mann=7,-1,0
  4255.0     0.1       0  4257.0    0.05       0  4814.5     0.1       0
  4971.5    0.12       0  4976.2    0.07       0  4982.2    0.12       0
  5058.8     0.1       0
Bank Sta=4976.2,4982.2
Exp/Cntr=0.3,0.1

Type RM Length L Ch R = 1,6850,506,506,506
BEGIN DESCRIPTION:
Mapping XS 2f3e9f3c
END DESCRIPTION:
XS GIS Cut Line= 3
      2176462.45     13206465.03      2176733.28     13206027.53
      2177038.84     13204902.53
#Sta/Elev= 30
  4142.8  458.91  4187.7  457.50  4254.8  456.72  4376.5  452.79  4422.7  452.45
  4434.7  453.02  4493.5  450.55  4602.4  448.56  4638.9  447.86  4654.3  446.37
  4688.7  445.15  4709.9  445.62  4728.5  444.47  4761.7  444.17  4768.3  443.37
  4817.1  442.00  4875.7  440.31  4979.3  439.47  5007.4  438.20  5010.1  437.70
  5013.4  438.20  5027.7  439.74  5165.8  442.62  5419.0  450.85  5493.4  454.52
  5533.2  455.40  5682.0  461.51  5735.7  464.44  5756.4  464.46  5823.1  467.23
#Mann=6,-1,0
  4142.8     0.1       0  4602.4    0.05       0  4817.1    0.12       0
  5007.4    0.07       0  5013.4    0.12       0  5027.7     0.1       0
Bank Sta=5007.4,5013.4
Exp/Cntr=0.3,0.1

Type RM Length L Ch R = 1,6344,530,530,530
BEGIN DESCRIPTION:
UNT 023 IN LACR 11.0
END DESCRIPTION:
XS GIS Cut Line= 3
      2177137.73     13206596.81      2177287.72     13205796.85
      2177287.72     13205396.85
#Sta/Elev= 30
  4186.1  455.09  4206.4  454.41  4212.3  453.67  4217.4  454.04  4257.3  451.62
  4317.5  450.54  4359.0  448.56  4380.2  448.37  4460.8  444.97  4511.6  443.69
  4521.8  442.70  4543.0  442.16  4572.7  442.60  4582.9  441.98  4654.1  440.37
  4694.8  440.42  4705.8  439.82  4725.3  440.09  4766.0  438.76  4796.5  438.65
  4827.0  438.41  4847.4  438.94  4863.5  438.17  4888.1  438.20  4994.5  435.58
  4997.2  435.08  5000.5  435.58  5025.7  436.62  5190.0  441.54  5400.0  450.58
#Mann=5,-1,0
  4186.1     0.1       0  4796.5    0.12       0  4994.5    0.07       0
  5000.5    0.12       0  5025.7     0.1       0
Bank Sta=4994.5,5000.5
Exp/Cntr=0.3,0.1

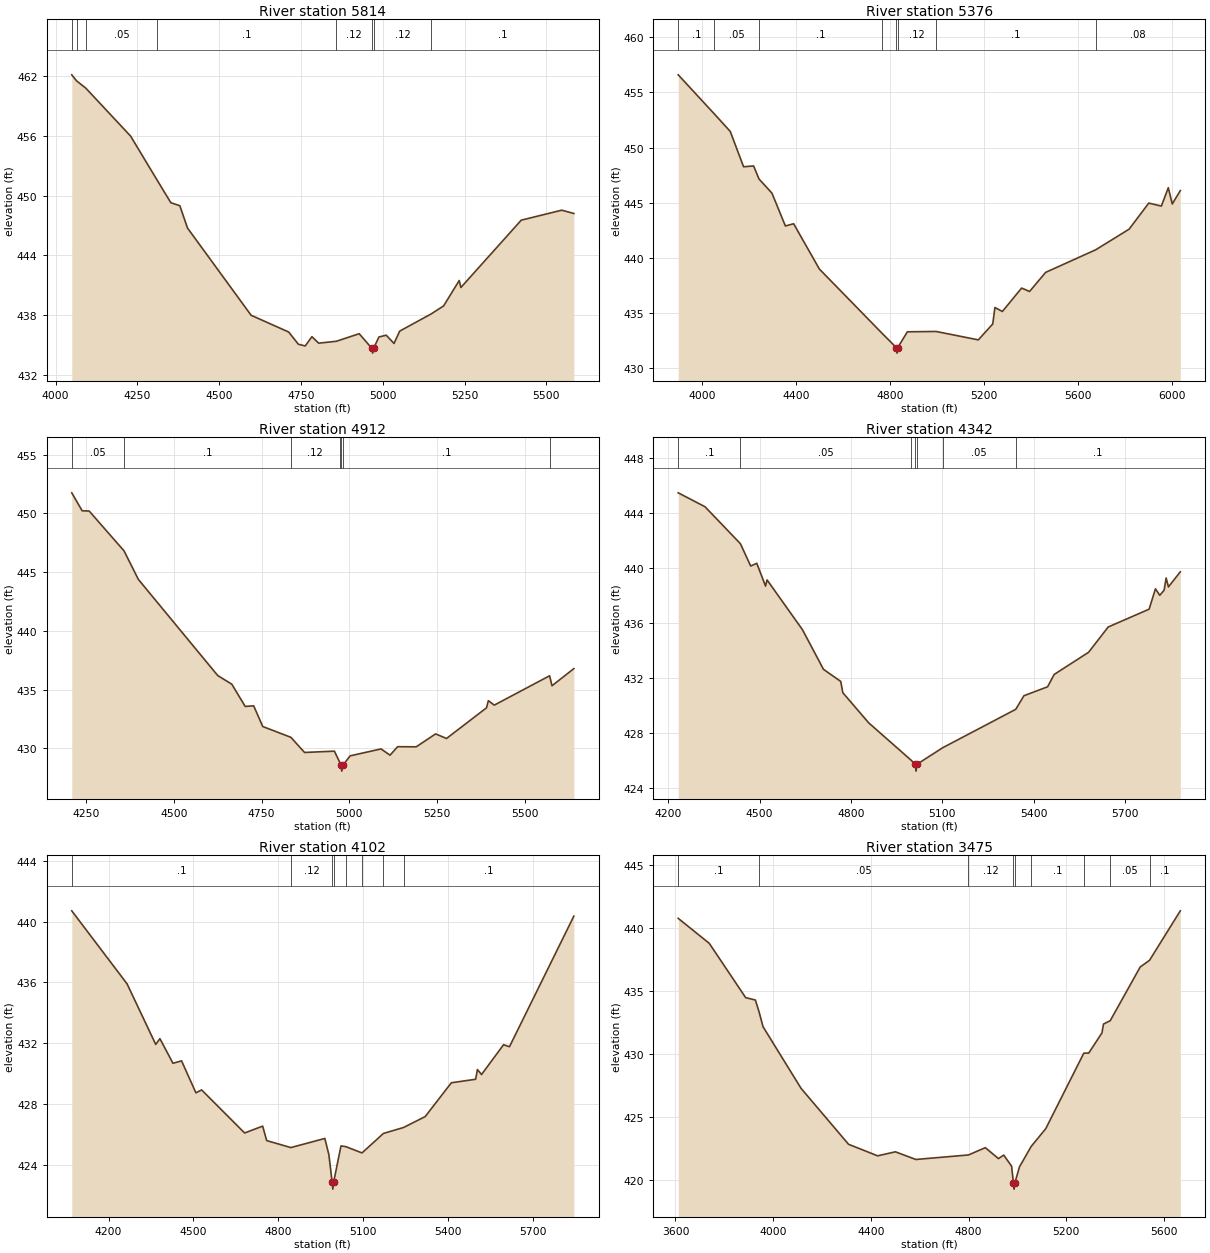
Type RM Length L Ch R = 1,5814,438,438,438
BEGIN DESCRIPTION:
UNT 023 IN LACR 10.0
END DESCRIPTION:
XS GIS Cut Line= 3
      2177372.18     13206860.85      2177601.34     13206520.59
      2177878.91     13205431.13
#Sta/Elev= 30
  4049.3  462.12  4064.2  461.51  4092.3  460.78  4229.1  455.97  4310.2  451.55
  4352.1  449.28  4379.6  448.98  4403.0  446.74  4597.5  437.98  4712.2  436.30
  4742.0  435.07  4762.7  434.90  4783.3  435.83  4803.9  435.18  4858.0  435.37
  4927.8  436.13  4966.0  434.68  4968.8  434.18  4972.0  434.68  4988.1  435.80
  5010.3  435.98  5034.2  435.15  5051.6  436.39  5148.0  438.12  5185.8  438.92
  5233.5  441.47  5238.6  440.77  5423.1  447.53  5546.9  448.53  5583.8  448.20
#Mann=8,-1,0
  4049.3    0.05       0  4064.2     0.1       0  4092.3    0.05       0
  4310.2     0.1       0  4858.0    0.12       0  4966.0    0.07       0
  4972.0    0.12       0  5148.0     0.1       0
Bank Sta=4966,4972
Exp/Cntr=0.3,0.1

Type RM Length L Ch R = 1,5376,464,464,464
BEGIN DESCRIPTION:
UNT 023 IN LACR 9.0
END DESCRIPTION:
XS GIS Cut Line= 4
      2177594.40     13207145.58      2177983.28     13206687.25
      2178191.61     13205728.92      2177983.28     13205215.03
#Sta/Elev= 30
  3898.9  456.58  4053.0  453.03  4120.2  451.46  4176.9  448.26  4219.7  448.33
  4242.6  447.15  4297.7  445.87  4354.8  442.90  4390.0  443.10  4499.5  439.00
  4767.4  433.16  4826.9  431.89  4829.7  431.39  4832.9  431.89  4873.9  433.32
  4996.1  433.35  5175.8  432.59  5237.2  434.03  5246.4  435.52  5278.1  435.16
  5360.0  437.28  5393.8  436.97  5462.3  438.70  5675.8  440.75  5817.4  442.61
  5901.0  444.97  5954.6  444.70  5984.1  446.36  6000.9  444.89  6035.2  446.10
#Mann=8,-1,0
  3898.9     0.1       0  4053.0    0.05       0  4242.6     0.1       0
  4767.4    0.12       0  4826.9    0.07       0  4832.9    0.12       0
  4996.1     0.1       0  5675.8    0.08       0
Bank Sta=4826.9,4832.9
Exp/Cntr=0.3,0.1

Type RM Length L Ch R = 1,4912,570,570,570
BEGIN DESCRIPTION:
UNT 023 IN LACR 8.0
END DESCRIPTION:
XS GIS Cut Line= 3
      2178608.28     13206916.46      2178615.22     13206499.75
      2178282.39     13205542.85
#Sta/Elev= 30
  4209.6  451.75  4239.2  450.22  4259.2  450.20  4358.4  446.81  4399.2  444.38
  4625.3  436.19  4665.5  435.45  4703.5  433.56  4727.7  433.61  4753.5  431.85
  4833.6  430.93  4872.6  429.64  4957.6  429.75  4972.8  428.80  4975.8  428.55
  4978.6  428.05  4981.8  428.55  5002.3  429.35  5090.3  429.94  5116.1  429.41
  5137.6  430.13  5190.6  430.12  5245.8  431.22  5276.9  430.83  5390.7  433.44
  5396.0  434.05  5412.9  433.67  5570.5  436.17  5577.3  435.32  5639.5  436.78
#Mann=7,-1,0
  4209.6    0.05       0  4358.4     0.1       0  4833.6    0.12       0
  4972.8     0.1       0  4975.8    0.07       0  4981.8     0.1       0
  5570.5    0.08       0
Bank Sta=4975.8,4981.8
Exp/Cntr=0.3,0.1

Type RM Length L Ch R = 1,4342,240,240,240
BEGIN DESCRIPTION:
UNT 023 IN LACR 7.0
END DESCRIPTION:
XS GIS Cut Line= 3
      2179087.45     13206534.50      2179115.22     13206006.70
      2178282.31     13205257.08
#Sta/Elev= 30
  4232.6  445.47  4320.4  444.46  4436.7  441.77  4470.6  440.14  4490.6  440.34
  4519.4  438.68  4524.4  439.13  4640.8  435.50  4709.7  432.62  4766.4  431.74
  4773.2  430.92  4858.4  428.72  4996.3  426.03  5010.8  425.71  5013.6  425.21
  5016.8  425.71  5101.0  426.91  5341.2  429.71  5368.1  430.70  5445.8  431.35
  5467.5  432.25  5580.4  433.86  5644.7  435.70  5779.2  437.00  5800.1  438.48
  5814.3  438.01  5828.5  438.38  5835.2  439.27  5842.7  438.62  5881.7  439.72
#Mann=7,-1,0
  4232.6     0.1       0  4436.7    0.05       0  4996.3    0.08       0
  5010.8    0.07       0  5016.8    0.08       0  5101.0    0.05       0
  5341.2     0.1       0
Bank Sta=5010.8,5016.8
Exp/Cntr=0.3,0.1

Type RM Length L Ch R = 1,4102,627,627,627
BEGIN DESCRIPTION:
UNT 023 IN LACR 6.0
END DESCRIPTION:
XS GIS Cut Line= 3
      2179443.86     13206509.65      2179353.57     13205967.94
      2178562.89     13205031.61
#Sta/Elev= 30
  4069.8  440.71  4265.3  435.91  4366.6  431.93  4381.4  432.31  4427.5  430.69
  4457.9  430.85  4508.6  428.75  4528.8  428.94  4680.8  426.11  4744.5  426.56
  4758.8  425.61  4844.2  425.15  4964.3  425.75  4978.6  424.69  4989.9  422.92
  4992.6  422.42  4995.9  422.92  5021.4  425.26  5038.8  425.21  5095.7  424.80
  5171.5  426.08  5242.6  426.47  5319.2  427.19  5411.5  429.41  5497.3  429.64
  5503.8  430.28  5518.1  429.95  5596.1  431.91  5617.0  431.78  5844.5  440.36
#Mann=8,-1,0
  4069.8     0.1       0  4844.2    0.12       0  4989.9    0.07       0
  4995.9    0.12       0  5038.8    0.05       0  5095.7    0.08       0
  5171.5    0.05       0  5242.6     0.1       0
Bank Sta=4989.9,4995.9
Exp/Cntr=0.3,0.1

Type RM Length L Ch R = 1,3475,667,667,667
BEGIN DESCRIPTION:
UNT 023 IN LACR 5.0
END DESCRIPTION:
XS GIS Cut Line= 3
      2179700.79     13206558.24      2179853.57     13206072.11
      2179284.11     13204634.56
#Sta/Elev= 30
  3611.3  440.79  3738.5  438.80  3887.5  434.48  3927.2  434.29  3942.1  433.36
  3958.7  432.16  4114.3  427.26  4308.6  422.81  4427.7  421.89  4500.5  422.21
  4584.2  421.60  4799.7  421.96  4868.7  422.54  4922.5  421.67  4944.0  421.95
  4976.3  421.07  4983.8  419.74  4986.6  419.24  4989.8  419.74  5008.5  421.01
  5056.6  422.64  5116.1  424.05  5271.9  430.06  5292.2  430.07  5346.2  431.67
  5352.7  432.38  5380.3  432.65  5502.9  436.92  5541.0  437.45  5667.1  441.39
#Mann=9,-1,0
  3611.3     0.1       0  3942.1    0.05       0  4799.7    0.12       0
  4983.8    0.07       0  4989.8    0.12       0  5056.6     0.1       0
  5271.9    0.08       0  5380.3    0.05       0  5541.0     0.1       0
Bank Sta=4983.8,4989.8
Exp/Cntr=0.3,0.1

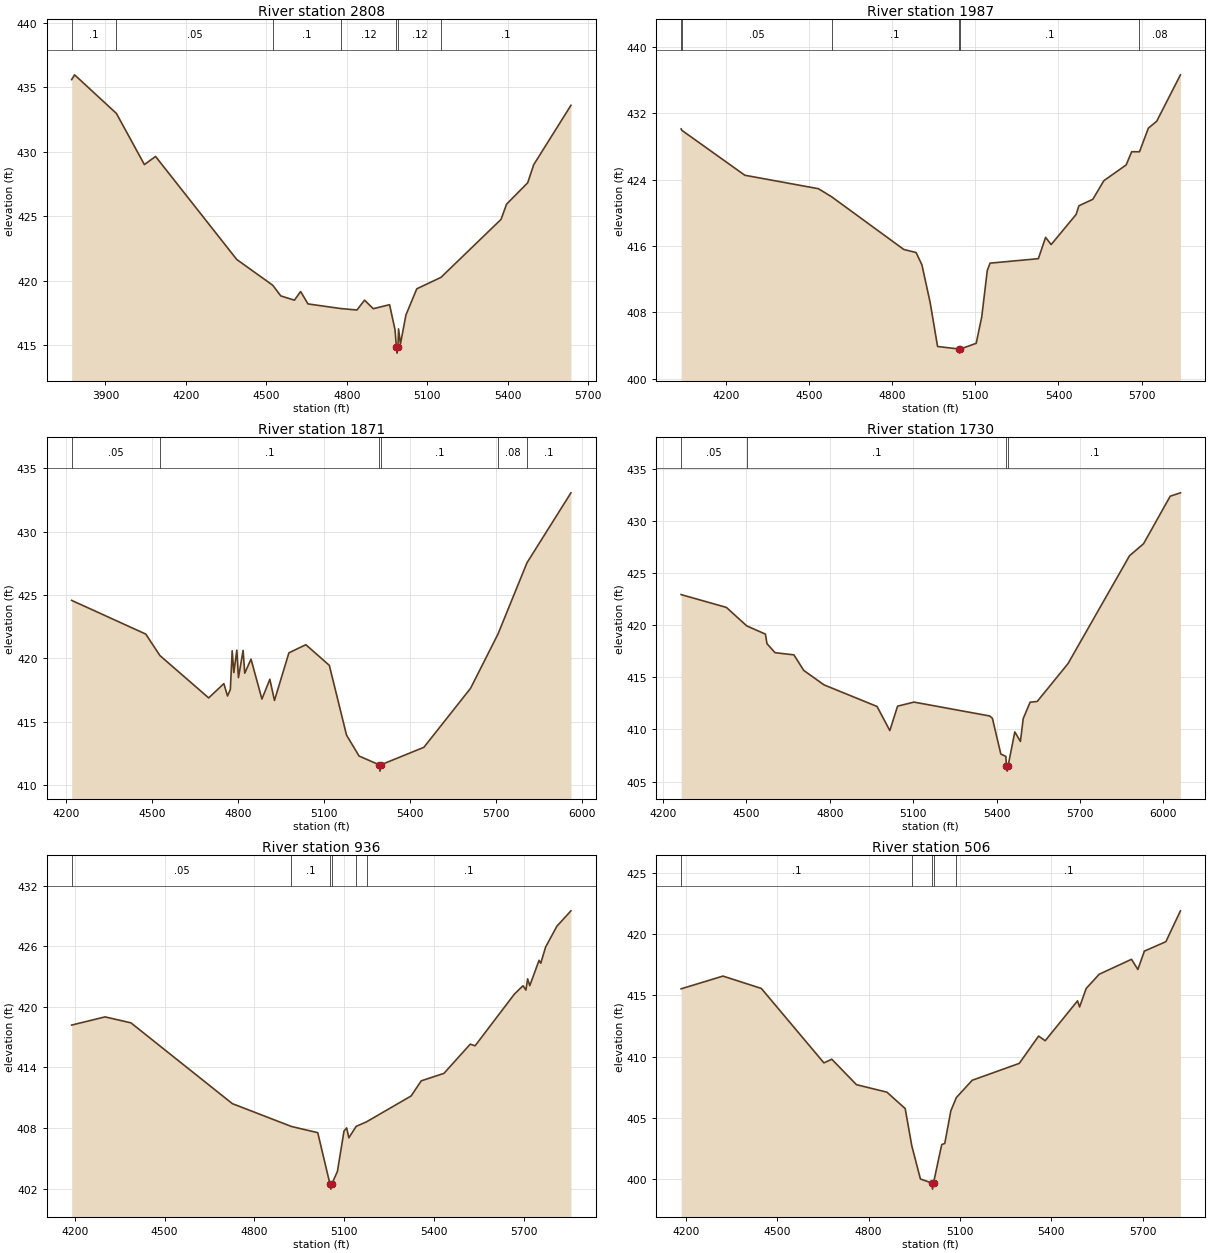
Type RM Length L Ch R = 1,2808,821,821,821
BEGIN DESCRIPTION:
Mapping XS 1ec5e18b
END DESCRIPTION:
XS GIS Cut Line= 3
      2179992.46     13206537.40      2180193.85     13205842.94
      2180006.68     13204719.90
#Sta/Elev= 30
  3774.0  435.58  3785.0  435.95  3941.0  432.96  4045.3  429.00  4086.9  429.63
  4389.7  421.65  4523.6  419.66  4553.9  418.83  4604.6  418.50  4627.8  419.17
  4655.3  418.21  4778.2  417.85  4837.8  417.74  4866.0  418.50  4898.6  417.84
  4959.4  418.15  4979.7  416.21  4984.7  414.90  4987.4  414.40  4990.7  414.90
  4992.8  416.28  5000.0  415.11  5020.3  417.35  5060.8  419.38  5151.3  420.27
  5375.1  424.76  5395.4  425.93  5474.3  427.59  5496.8  428.99  5635.6  433.59
#Mann=7,-1,0
  3774.0     0.1       0  3941.0    0.05       0  4523.6     0.1       0
  4778.2    0.12       0  4984.7    0.07       0  4990.7    0.12       0
  5151.3     0.1       0
Bank Sta=4984.7,4990.7
Exp/Cntr=0.3,0.1

Type RM Length L Ch R = 1,1987,116,116,116
BEGIN DESCRIPTION:
UNT 023 IN LACR 4.0
END DESCRIPTION:
XS GIS Cut Line= 3
      2180230.71     13206480.48      2180796.25     13205683.31
      2180840.04     13204861.28
#Sta/Elev= 30
  4039.2  430.12  4041.3  429.96  4268.9  424.53  4534.1  422.91  4581.7  421.94
  4842.2  415.58  4886.5  415.21  4907.4  413.74  4937.0  409.22  4964.0  403.88
  5040.1  403.58  5042.8  403.08  5046.1  403.58  5103.2  404.26  5123.2  407.44
  5143.2  413.04  5153.3  413.93  5327.4  414.47  5353.5  417.04  5373.6  416.17
  5463.7  419.81  5473.7  420.85  5523.8  421.63  5563.8  423.88  5643.9  425.77
  5664.0  427.37  5692.1  427.36  5724.1  430.21  5754.1  431.04  5839.8  436.64
#Mann=6,-1,0
  4039.2     0.1       0  4041.3    0.05       0  4581.7     0.1       0
  5040.1    0.07       0  5046.1     0.1       0  5692.1    0.08       0
Bank Sta=5040.1,5046.1
Exp/Cntr=0.3,0.1

Type RM Length L Ch R = 1,1871,141,141,141
BEGIN DESCRIPTION:
UNT 023 IN LACR 3.0
END DESCRIPTION:
XS GIS Cut Line= 3
      2180506.72     13206454.50      2181064.76     13205418.40
      2180958.24     13204862.84
#Sta/Elev= 30
  4219.2  424.57  4477.8  421.91  4527.5  420.21  4697.5  416.87  4750.4  418.00
  4763.2  417.02  4773.1  417.54  4779.5  420.59  4785.1  418.87  4795.7  420.64
  4801.4  418.47  4817.6  420.62  4823.3  418.82  4845.2  419.93  4883.3  416.78
  4910.9  418.34  4927.1  416.67  4977.5  420.43  5036.6  421.07  5118.5  419.44
  5178.6  413.93  5222.4  412.28  5292.6  411.59  5295.3  411.09  5298.6  411.59
  5448.5  412.97  5611.4  417.63  5707.1  421.91  5808.3  427.54  5961.7  433.06
#Mann=6,-1,0
  4219.2    0.05       0  4527.5     0.1       0  5292.6    0.07       0
  5298.6     0.1       0  5707.1    0.08       0  5808.3     0.1       0
Bank Sta=5292.6,5298.6
Exp/Cntr=0.3,0.1

Type RM Length L Ch R = 1,1730,794,794,794
BEGIN DESCRIPTION:
UNT 023 IN LACR 2.0
END DESCRIPTION:
XS GIS Cut Line= 3
      2180621.32     13206501.34      2181136.94     13205584.68
      2181048.40     13204845.09
#Sta/Elev= 30
  4265.0  422.93  4428.0  421.70  4501.0  419.93  4568.3  419.14  4574.0  418.22
  4602.9  417.36  4670.9  417.15  4706.1  415.66  4779.3  414.27  4970.0  412.20
  5015.9  409.89  5043.8  412.23  5103.1  412.62  5375.0  411.29  5385.0  411.07
  5415.3  407.64  5433.4  407.41  5435.4  406.50  5438.2  406.00  5441.4  406.50
  5465.6  409.76  5485.8  408.85  5495.8  411.03  5520.7  412.61  5546.2  412.68
  5657.0  416.31  5878.5  426.66  5928.9  427.81  6024.9  432.37  6061.6  432.69
#Mann=4,-1,0
  4265.0    0.05       0  4501.0     0.1       0  5435.4    0.07       0
  5441.4     0.1       0
Bank Sta=5435.4,5441.4
Exp/Cntr=0.3,0.1

Type RM Length L Ch R = 1,936,430,430,430
BEGIN DESCRIPTION:
Mapping XS e8269866
END DESCRIPTION:
XS GIS Cut Line= 3
      2181277.56     13206319.06      2181631.73     13205694.05
      2181183.80     13204855.47
#Sta/Elev= 30
  4189.0  418.19  4300.8  419.00  4387.3  418.41  4726.4  410.41  4923.9  408.15
  5011.7  407.54  5052.6  402.45  5055.3  401.95  5058.6  402.45  5077.5  403.71
  5099.5  407.70  5108.3  408.01  5115.7  407.03  5140.0  408.16  5175.2  408.62
  5323.7  411.17  5357.7  412.67  5433.6  413.41  5521.4  416.30  5537.7  416.14
  5669.4  421.27  5697.8  422.08  5707.6  421.66  5713.3  422.76  5720.5  422.09
  5751.5  424.60  5757.2  424.31  5773.5  425.92  5811.2  427.98  5858.1  429.50
#Mann=6,-1,0
  4189.0    0.05       0  4923.9     0.1       0  5052.6    0.07       0
  5058.6     0.1       0  5140.0    0.12       0  5175.2     0.1       0
Bank Sta=5052.6,5058.6
Exp/Cntr=0.3,0.1

Type RM Length L Ch R = 1,506,374,374,374
BEGIN DESCRIPTION:
Mapping XS cdf6d64b
END DESCRIPTION:
XS GIS Cut Line= 4
      2181768.00     13206277.53      2181927.72     13205784.48
      2181927.72     13205277.53      2181469.39     13204867.81
#Sta/Elev= 30
  4184.1  415.54  4321.5  416.58  4447.6  415.57  4653.1  409.49  4678.9  409.79
  4760.0  407.71  4860.0  407.10  4920.0  405.76  4941.7  402.72  4970.0  400.01
  5007.0  399.68  5009.8  399.18  5013.0  399.68  5040.0  402.82  5050.0  402.91
  5070.0  405.58  5088.1  406.66  5140.0  408.07  5294.7  409.45  5358.2  411.68
  5379.9  411.30  5486.1  414.56  5492.8  414.06  5514.5  415.57  5557.2  416.73
  5663.3  417.95  5684.2  417.12  5705.6  418.62  5776.2  419.39  5824.1  421.91
#Mann=5,-1,0
  4184.1     0.1       0  4941.7    0.12       0  5007.0    0.07       0
  5013.0    0.12       0  5088.1     0.1       0
Bank Sta=5007,5013
Exp/Cntr=0.3,0.1

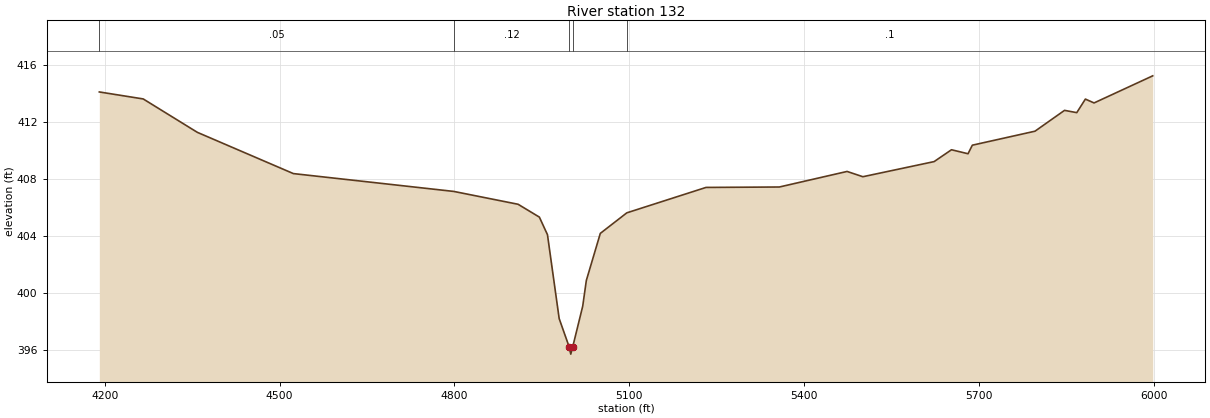
Type RM Length L Ch R = 1,132,0,0,0
BEGIN DESCRIPTION:
UNT 023 IN LACR 1.0
END DESCRIPTION:
XS GIS Cut Line= 4
      2181969.41     13206152.50      2182302.72     13205659.48
      2182240.22     13205159.48      2181656.88     13204756.69
#Sta/Elev= 30
  4190.6  414.08  4265.9  413.59  4358.8  411.25  4523.6  408.36  4798.9  407.11
  4909.3  406.21  4945.8  405.31  4959.7  404.08  4979.8  398.20  4997.0  396.21
  4999.7  395.71  5003.0  396.21  5020.2  399.07  5026.4  400.87  5050.4  404.17
  5095.9  405.61  5231.8  407.39  5357.7  407.42  5473.9  408.51  5501.0  408.14
  5623.3  409.20  5653.1  410.03  5681.5  409.75  5688.9  410.35  5796.4  411.33
  5847.1  412.79  5868.1  412.63  5882.9  413.58  5897.8  413.31  5998.5  415.21
#Mann=5,-1,0
  4190.6    0.05       0  4798.9    0.12       0  4997.0    0.07       0
  5003.0    0.12       0  5095.9     0.1       0
Bank Sta=4997,5003
Exp/Cntr=0.3,0.1

Chan Stop Cuts=-1