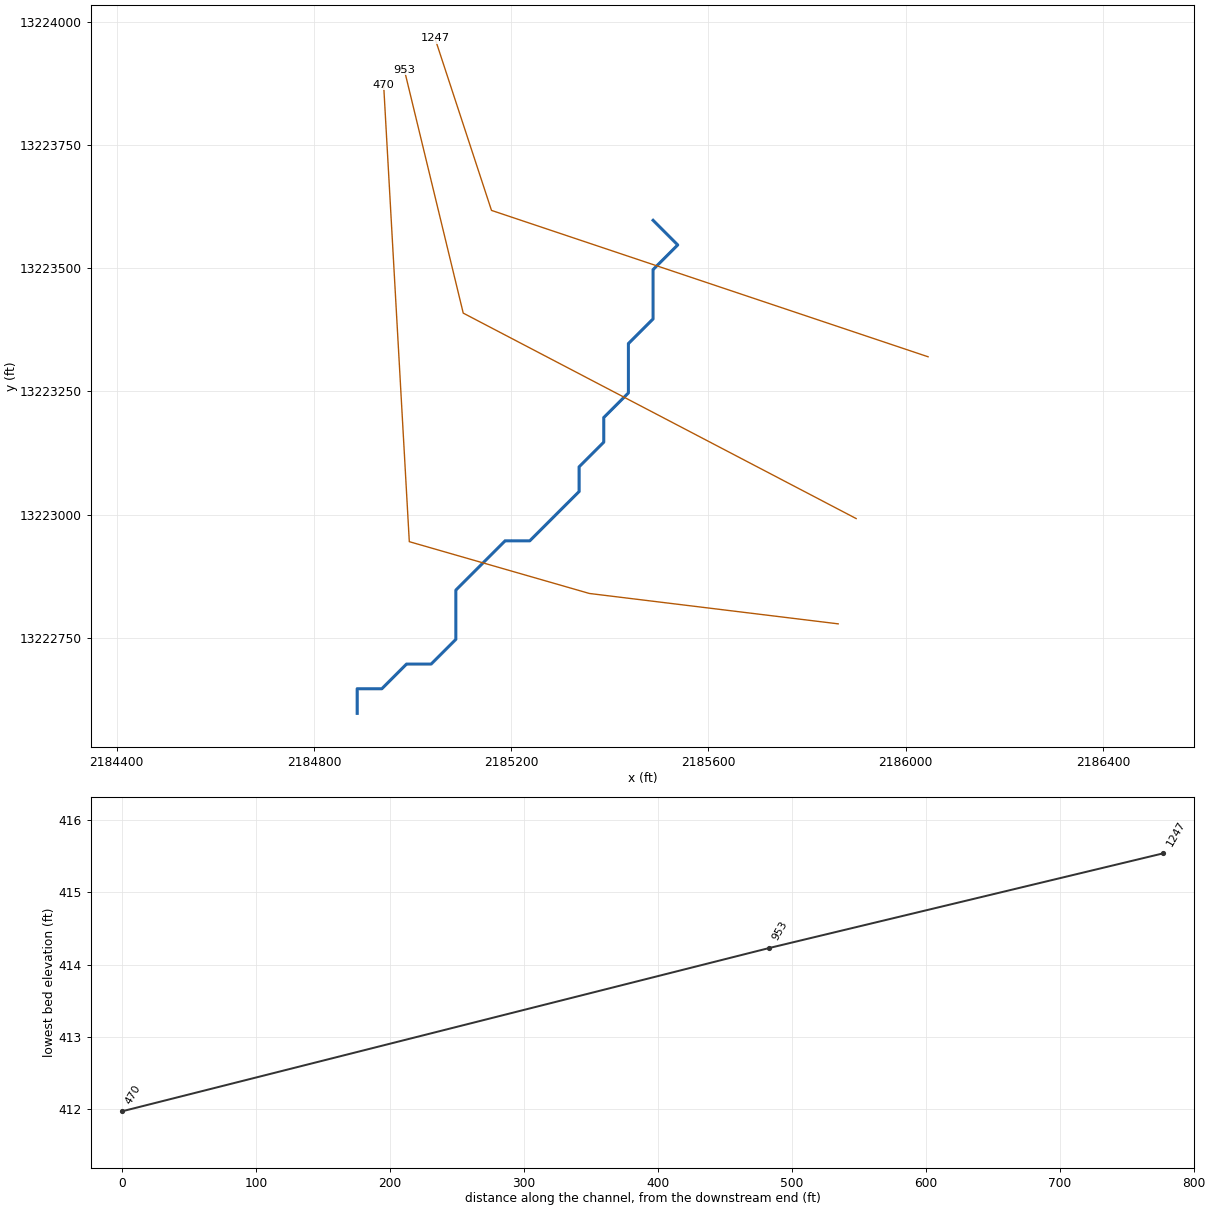
--- UNT 025 IN LACR.prj (project) ---

Proj Title=UNT 025 IN LACR Base Level Engineering
Current Plan=p01
Default Exp/Contr=0.3,0.1
English Units
Geom File=g01
Flow File=f01
Plan File=p01
Y Axis Title=Elevation
X Axis Title(PF)=Main Channel Distance
X Axis Title(XS)=Station
BEGIN DESCRIPTION:
UNT 025 IN LACR
END DESCRIPTION:
DSS Export Rating Curves= 0
DSS Export Rating Curve Sorted= 0
DSS Export Volume Flow Curves= 0
DXF OffsetX= 0
DXF OffsetY= 0
DXF ScaleX= 1
DXF ScaleY= 10

--- UNT 025 IN LACR.p01 (plan) ---

Plan Title=Multiple Run
Short Identifier=Multiple
Geom File=g01
Flow File=f01
Subcritical Flow
K Sum by GR= 0
Std Step Tol= 0.01
Critical Tol= 0.01
Num of Std Step Trials= 20
Max Error Tol= 0.3
Flow Tol Ratio= 0.001
Split Flow NTrial= 30
Split Flow Tol= 0.02
Split Flow Ratio= 0.02
Log Output Level= 0
Friction Slope Method= 1
Unsteady Friction Slope Method= 2
Unsteady Bridges Friction Slope Method= 1
Parabolic Critical Depth
Global Vel Dist=  1 , 1 , 1
Global Log Level= 0
CheckData=True
Encroach Param= -1, 0, 0, 0
BEGIN DESCRIPTION:
Multiple Run
END DESCRIPTION:

--- UNT 025 IN LACR.f01 (steady flow) ---

Flow Title=Multiple
Number of Profiles=7
Profile Names=10-year,25-year,50-year,1pct_min,100-year,1pct_plu,500-year
River Rch & RM= UNT 025 IN LACR,Reach-1,1247
     182     251     308     278     376     508     569
Boundary for River Rch & Prof#=UNT 025 IN LACR,Reach-1,1
Up Type=0
Dn Type=3
Dn Slope=0.005
Boundary for River Rch & Prof#=UNT 025 IN LACR,Reach-1,2
Up Type=0
Dn Type=3
Dn Slope=0.005
Boundary for River Rch & Prof#=UNT 025 IN LACR,Reach-1,3
Up Type=0
Dn Type=3
Dn Slope=0.005
Boundary for River Rch & Prof#=UNT 025 IN LACR,Reach-1,4
Up Type=0
Dn Type=3
Dn Slope=0.005
Boundary for River Rch & Prof#=UNT 025 IN LACR,Reach-1,5
Up Type=0
Dn Type=3
Dn Slope=0.005
Boundary for River Rch & Prof#=UNT 025 IN LACR,Reach-1,6
Up Type=0
Dn Type=3
Dn Slope=0.005
Boundary for River Rch & Prof#=UNT 025 IN LACR,Reach-1,7
Up Type=0
Dn Type=3
Dn Slope=0.005

--- UNT 025 IN LACR.g01 (geometry) ---

Geom Title=Existing Conditions
Program Version=4.10

River Reach=UNT 025 IN LACR ,Reach-1
Reach XY= 24
      2185487.72     13223596.85      2185537.72     13223546.85
      2185487.72     13223496.86      2185487.72     13223446.85
      2185487.72     13223396.85      2185437.72     13223346.85
      2185437.72     13223296.85      2185437.72     13223246.85
      2185387.72     13223196.85      2185387.72     13223146.86
      2185337.72     13223096.85      2185337.72     13223046.85
      2185287.72     13222996.86      2185237.72     13222946.85
      2185187.72     13222946.85      2185137.72     13222896.85
      2185087.72     13222846.86      2185087.72     13222796.85
      2185087.72     13222746.85      2185037.72     13222696.85
      2184987.72     13222696.85      2184937.72     13222646.86
      2184887.72     13222646.86      2184887.72     13222596.85

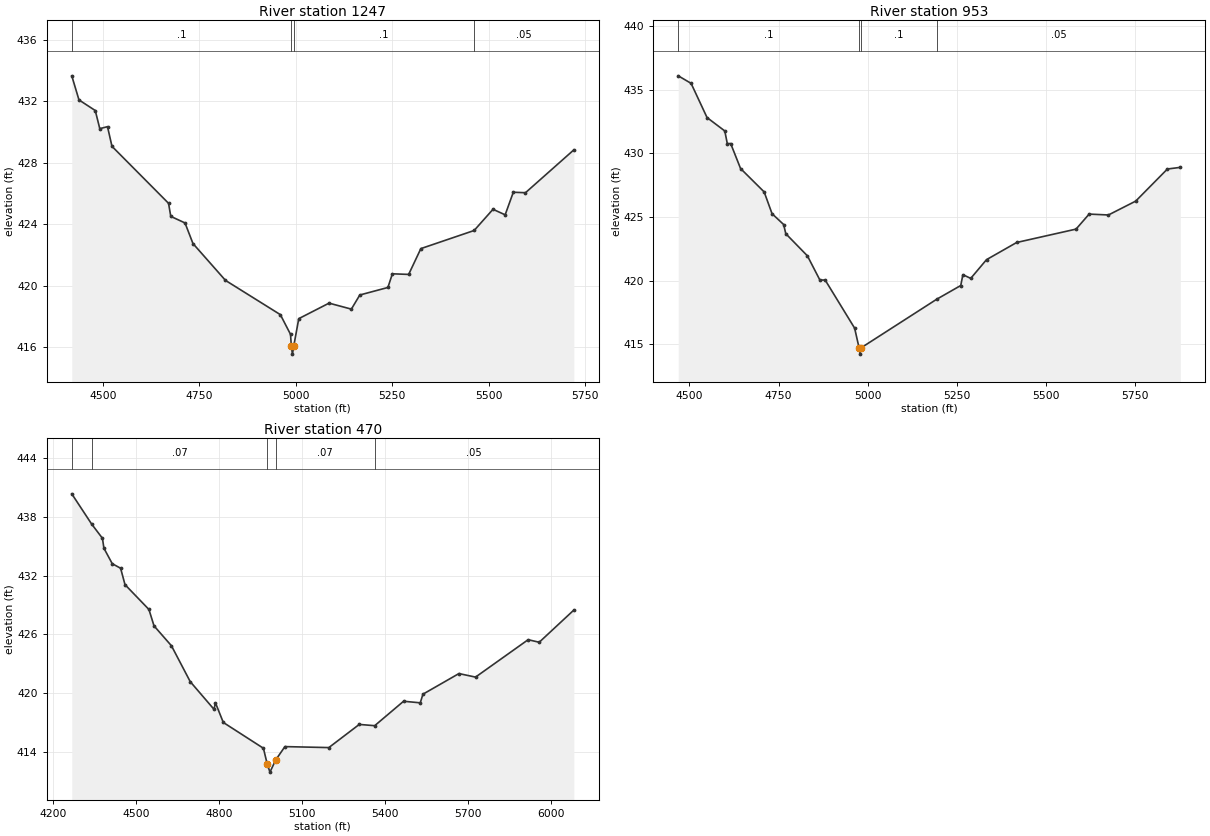
Type RM Length L Ch R = 1 ,1247    ,294,294,294
BEGIN DESCRIPTION:
UNT 025 IN LACR 2.0
END DESCRIPTION:
XS GIS Cut Line= 3
      2186045.49     13223320.08      2185160.03     13223616.97
      2185045.45     13223965.93
#Sta/Elev= 30
  4419.8  433.66  4438.5  432.09  4480.7   431.4  4492.4  430.22  4512.4  430.35
    4524  429.07  4670.6  425.36  4676.4  424.51  4713.3  424.08  4733.9  422.74
  4818.2  420.34  4960.4  418.11  4986.7  416.83  4988.9  416.04  4991.7  415.54
  4994.9  416.04  5008.1  417.85  5086.6  418.86  5144.4  418.47  5166.3  419.39
  5239.1  419.88  5250.7  420.77  5292.9  420.73  5324.5  422.41  5462.6  423.59
  5511.5  424.97    5543  424.61  5564.1  426.08  5595.7  426.05    5721  428.84
#Mann= 4 ,-1 , 0
  4419.8      .1       0  4988.9     .07       0  4994.9      .1       0
  5462.6     .05       0
Bank Sta=4988.9,4994.9
XS Rating Curve= 0 ,0
Exp/Cntr=0.3,0.1

Type RM Length L Ch R = 1 ,953     ,483,483,483
BEGIN DESCRIPTION:
Mapping XS 1cd707f1
END DESCRIPTION:
XS GIS Cut Line= 3
      2185899.58     13222991.98      2185102.74     13223408.63
      2184983.13     13223902.66
#Sta/Elev= 30
  4468.9  436.09  4504.9   435.5  4549.7  432.81  4599.4  431.76  4606.4  430.77
  4615.9  430.77  4643.6  428.81  4709.8  426.97  4731.9  425.26  4764.4  424.41
  4770.4  423.69    4831  421.95    4866  420.05  4880.8  420.05  4963.4  416.27
  4975.8  414.73  4978.6  414.23  4981.8  414.73  5193.4  418.54  5260.9  419.62
  5266.9  420.47  5288.9  420.18  5333.1  421.65  5417.7     423  5584.1  424.05
  5620.8  425.23  5674.9  425.16  5751.4  426.25  5840.2  428.77  5876.4   428.9
#Mann= 4 ,-1 , 0
  4468.9      .1       0  4975.8     .07       0  4981.8      .1       0
  5193.4     .05       0
Bank Sta=4975.8,4981.8
XS Rating Curve= 0 ,0
Exp/Cntr=0.3,0.1

Type RM Length L Ch R = 1 ,470     ,0,0,0
BEGIN DESCRIPTION:
UNT 025 IN LACR 1.0
END DESCRIPTION:
XS GIS Cut Line= 4
      2185863.14     13222778.43      2185358.68     13222840.01
      2184993.36     13222945.09      2184941.29       13223872.
#Sta/Elev= 30
  4267.3  440.32  4339.2  437.24  4378.3  435.79  4383.6  434.78  4413.8   433.2
    4444  432.74  4459.9  431.07  4546.5  428.54  4564.9  426.87    4628  424.84
  4695.9  421.19  4781.9  418.37  4787.2  419.03  4815.6  417.03  4960.8   414.4
  4974.2  412.83  4984.4  411.97  5005.4  413.22  5038.6  414.57  5197.5  414.47
  5307.6  416.83  5363.4   416.7  5467.9  419.19  5528.3  419.03    5538  419.91
  5668.2  422.01  5728.3  421.65  5918.6  425.46  5958.7   425.2    6084  428.48
#Mann= 5 ,-1 , 0
  4267.3     .08       0  4339.2     .07       0  4974.2    .035       0
  5005.4     .07       0  5363.4     .05       0
Bank Sta=4974.2,5005.4
XS Rating Curve= 0 ,0
Exp/Cntr=0.3,0.1

Chan Stop Cuts=-1
Use User Specified Reach Order=0
Composite Channel Slope=5