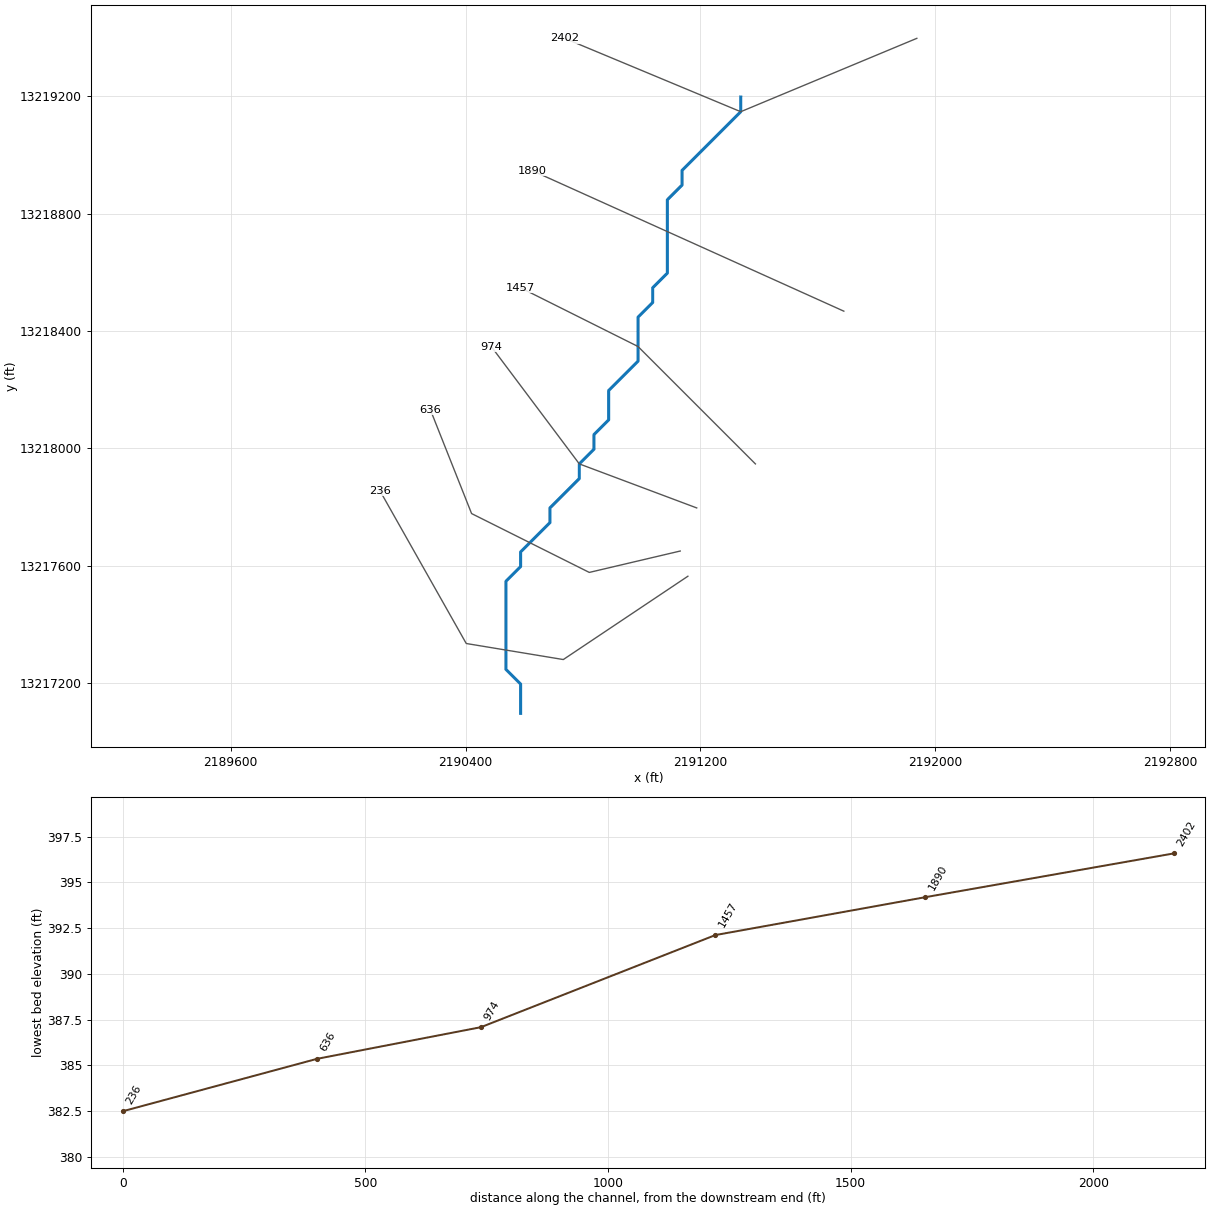
--- UNT 026 IN LACR.prj (project) ---

Proj Title=UNT 026 IN LACR Base Level Engineering
Current Plan=p01
Default Exp/Contr=0.3,0.1
English Units
Geom File=g01
Flow File=f01
Plan File=p01
BEGIN DESCRIPTION:
UNT 026 IN LACR
END DESCRIPTION:

--- UNT 026 IN LACR.p01 (plan) ---

Plan Title=Multiple Run
Short Identifier=Multiple
Geom File=g01
Flow File=f01
Subcritical Flow
K Sum by GR= 0
Std Step Tol= 0.01
Critical Tol= 0.01
Num of Std Step Trials= 20
Max Error Tol= 0.3
Flow Tol Ratio= 0.001
Split Flow NTrial= 30
Split Flow Tol= 0.02
Split Flow Ratio= 0.02
Log Output Level= 0
Friction Slope Method= 1
Unsteady Friction Slope Method= 2
Unsteady Bridges Friction Slope Method= 1
Parabolic Critical Depth
Global Vel Dist=  1 , 1 , 1
Global Log Level= 0
CheckData=True
Encroach Param= -1, 0, 0, 0
BEGIN DESCRIPTION:
Multiple Run
END DESCRIPTION:

--- UNT 026 IN LACR.f01 (steady flow) ---

Flow Title=Multiple
Number of Profiles=7
Profile Names=10-year,25-year,50-year,1pct_min,100-year,1pct_plu,500-year
River Rch & RM= UNT 026 IN LACR,Reach-1,2402
     234     330     410     375     508     687     791
Boundary for River Rch & Prof#=UNT 026 IN LACR,Reach-1,1
Up Type=0
Dn Type=3
Dn Slope=0.005
Boundary for River Rch & Prof#=UNT 026 IN LACR,Reach-1,2
Up Type=0
Dn Type=3
Dn Slope=0.005
Boundary for River Rch & Prof#=UNT 026 IN LACR,Reach-1,3
Up Type=0
Dn Type=3
Dn Slope=0.005
Boundary for River Rch & Prof#=UNT 026 IN LACR,Reach-1,4
Up Type=0
Dn Type=3
Dn Slope=0.005
Boundary for River Rch & Prof#=UNT 026 IN LACR,Reach-1,5
Up Type=0
Dn Type=3
Dn Slope=0.005
Boundary for River Rch & Prof#=UNT 026 IN LACR,Reach-1,6
Up Type=0
Dn Type=3
Dn Slope=0.005
Boundary for River Rch & Prof#=UNT 026 IN LACR,Reach-1,7
Up Type=0
Dn Type=3
Dn Slope=0.005

--- UNT 026 IN LACR.g01 (geometry) ---

Geom Title=Existing Conditions

River Reach=UNT 026 IN LACR,Reach-1
Reach XY= 30
      2191337.72     13219196.85      2191337.72     13219146.85
      2191287.72     13219096.85      2191237.72     13219046.86
      2191187.72     13218996.85      2191137.72     13218946.85
      2191137.72     13218896.86      2191087.72     13218846.85
      2191087.72     13218596.85      2191037.72     13218546.86
      2191037.72     13218496.85      2190987.72     13218446.85
      2190987.72     13218296.85      2190937.72     13218246.86
      2190887.72     13218196.85      2190887.72     13218096.85
      2190837.72     13218046.85      2190837.72     13217996.85
      2190787.72     13217946.85      2190787.72     13217896.86
      2190737.72     13217846.85      2190687.72     13217796.85
      2190687.72     13217746.86      2190637.72     13217696.85
      2190587.72     13217646.85      2190587.72     13217596.86
      2190537.72     13217546.85      2190537.72     13217246.86
      2190587.72     13217196.85      2190587.72     13217096.86

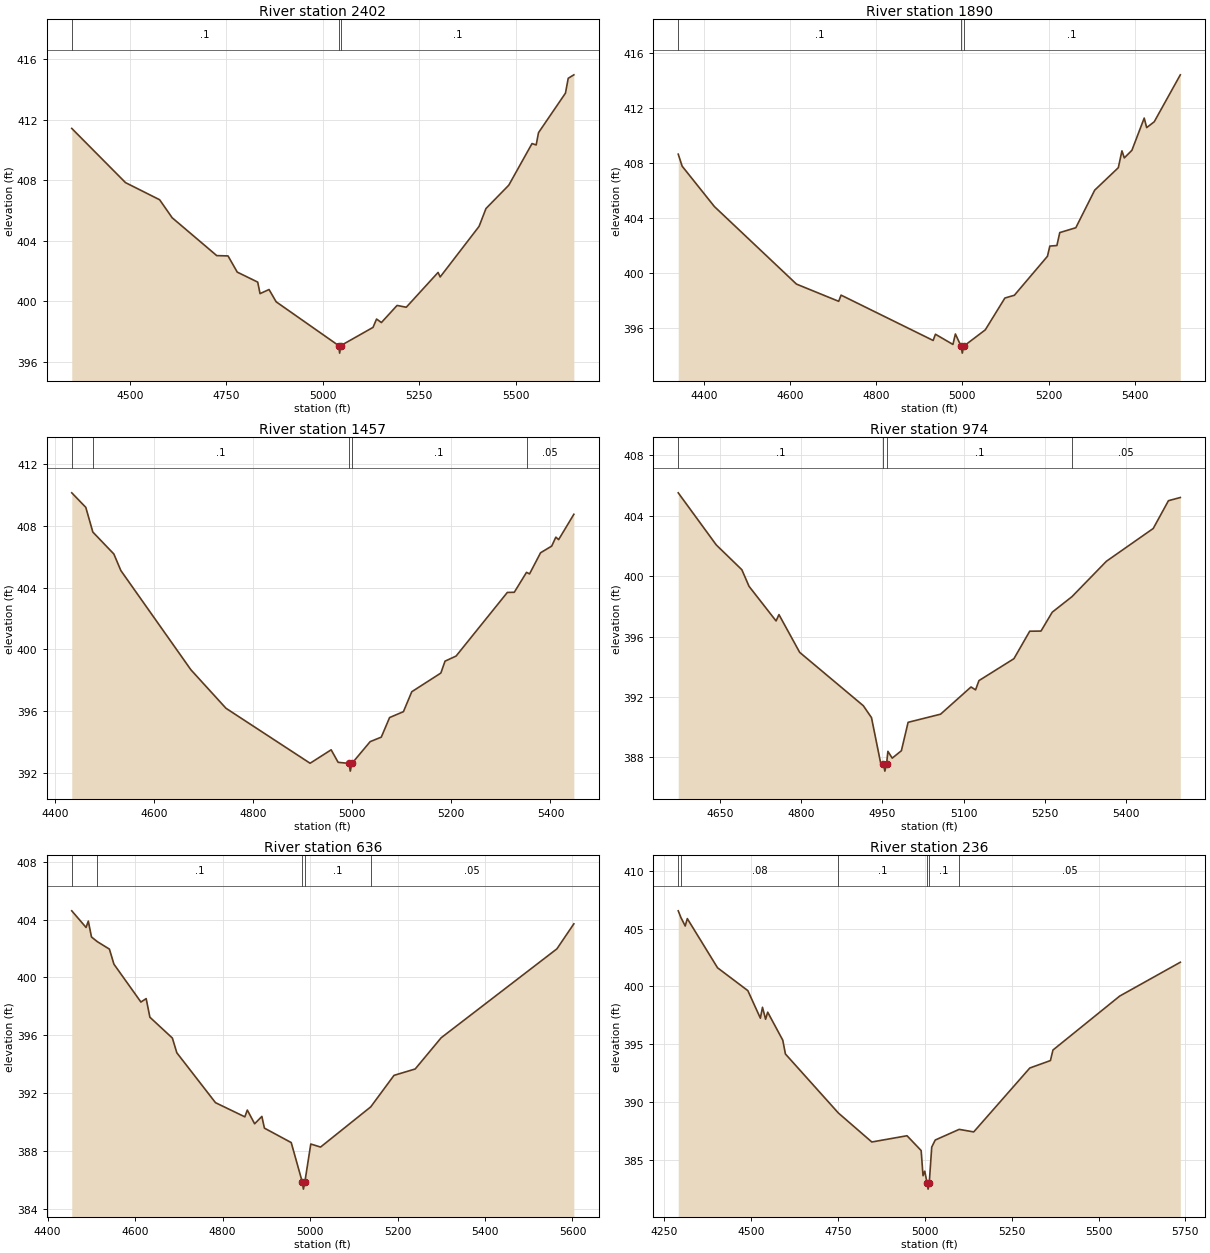
Type RM Length L Ch R = 1,2402,512,512,512
BEGIN DESCRIPTION:
UNT 026 IN LACR 5.0
END DESCRIPTION:
XS GIS Cut Line= 3
      2191937.72     13219396.85      2191337.72     13219146.85
      2190737.72     13219396.85
#Sta/Elev= 30
  4350.0  411.42  4489.2  407.84  4577.5  406.71  4610.0  405.52  4725.4  403.02
  4754.6  403.00  4778.5  401.93  4831.5  401.27  4837.5  400.51  4860.8  400.78
  4879.2  399.97  5040.9  397.08  5043.6  396.58  5046.9  397.08  5130.0  398.28
  5139.2  398.83  5151.7  398.60  5192.3  399.73  5216.1  399.61  5298.5  401.91
  5303.9  401.61  5404.6  404.95  5422.5  406.13  5481.5  407.67  5541.7  410.42
  5552.5  410.33  5558.5  411.14  5628.3  413.75  5635.4  414.73  5650.0  414.96
#Mann=3,-1,0
  4350.0     0.1       0  5040.9    0.07       0  5046.9     0.1       0
Bank Sta=5040.9,5046.9
Exp/Cntr=0.3,0.1

Type RM Length L Ch R = 1,1890,433,433,433
BEGIN DESCRIPTION:
UNT 026 IN LACR 4.0
END DESCRIPTION:
XS GIS Cut Line= 2
      2191689.00     13218467.24      2190626.55     13218946.39
#Sta/Elev= 30
  4340.4  408.63  4349.5  407.76  4424.3  404.83  4614.9  399.20  4712.9  397.95
  4718.4  398.40  4932.1  395.11  4937.5  395.56  4978.1  394.82  4983.8  395.58
  4997.0  394.69  4999.8  394.19  5003.0  394.69  5053.2  395.88  5098.7  398.19
  5120.7  398.39  5197.5  401.22  5203.0  401.96  5219.4  402.00  5226.1  402.94
  5263.3  403.29  5307.2  406.02  5362.0  407.65  5370.4  408.87  5375.9  408.36
  5393.5  408.91  5422.1  411.25  5427.8  410.56  5445.3  410.98  5505.9  414.39
#Mann=3,-1,0
  4340.4     0.1       0  4997.0    0.07       0  5003.0     0.1       0
Bank Sta=4997,5003
Exp/Cntr=0.3,0.1

Type RM Length L Ch R = 1,1457,483,483,483
BEGIN DESCRIPTION:
UNT 026 IN LACR 3.0
END DESCRIPTION:
XS GIS Cut Line= 3
      2191387.73     13217946.84      2190987.72     13218346.85
      2190587.73     13218546.85
#Sta/Elev= 30
  4434.3  410.14  4462.6  409.20  4476.8  407.60  4519.2  406.18  4533.3  405.11
  4674.7  398.68  4745.4  396.19  4915.1  392.63  4957.6  393.50  4971.7  392.69
  4993.5  392.62  4996.2  392.12  4999.5  392.62  5036.3  394.03  5058.7  394.32
  5075.5  395.59  5103.4  395.97  5120.2  397.26  5178.9  398.47  5187.3  399.24
  5209.6  399.57  5313.0  403.69  5327.0  403.70  5351.7  404.99  5357.8  404.89
  5380.1  406.26  5402.5  406.69  5410.9  407.27  5416.5  407.11  5447.2  408.75
#Mann=5,-1,0
  4434.3    0.05       0  4476.8     0.1       0  4993.5    0.07       0
  4999.5     0.1       0  5351.7    0.05       0
Bank Sta=4993.5,4999.5
Exp/Cntr=0.3,0.1

Type RM Length L Ch R = 1,974,338,338,338
BEGIN DESCRIPTION:
UNT 026 IN LACR 2.0
END DESCRIPTION:
XS GIS Cut Line= 3
      2191187.72     13217796.85      2190787.72     13217946.85
      2190487.72     13218346.85
#Sta/Elev= 30
  4572.8  405.51  4643.1  402.06  4690.3  400.42  4703.6  399.32  4753.5  397.03
  4758.8  397.45  4797.1  394.95  4914.6  391.42  4929.7  390.63  4946.6  387.63
  4951.6  387.59  4954.4  387.09  4957.6  387.59  4960.0  388.40  4968.0  387.95
  4984.9  388.44  4997.3  390.32  5057.3  390.86  5113.5  392.66  5121.9  392.47
  5128.1  393.08  5192.7  394.53  5221.9  396.35  5242.7  396.36  5263.5  397.61
  5300.0  398.64  5363.5  400.98  5450.0  403.15  5478.1  404.99  5500.0  405.20
#Mann=4,-1,0
  4572.8     0.1       0  4951.6    0.07       0  4957.6     0.1       0
  5300.0    0.05       0
Bank Sta=4951.6,4957.6
Exp/Cntr=0.3,0.1

Type RM Length L Ch R = 1,636,400,400,400
BEGIN DESCRIPTION:
Mapping XS c8299516
END DESCRIPTION:
XS GIS Cut Line= 4
      2191131.58     13217650.04      2190821.72     13217577.13
      2190420.68     13217777.65      2190280.04     13218131.85
#Sta/Elev= 30
  4455.3  404.61  4488.0  403.46  4493.1  403.90  4500.4  402.80  4514.1  402.47
  4541.4  401.96  4551.7  400.92  4613.4  398.30  4625.4  398.54  4633.9  397.25
  4685.3  395.81  4695.5  394.79  4783.9  391.34  4851.0  390.36  4856.6  390.83
  4873.4  389.88  4889.9  390.39  4895.7  389.58  4957.0  388.58  4982.2  385.86
  4984.9  385.36  4988.2  385.86  5001.7  388.48  5024.1  388.27  5138.8  391.05
  5192.0  393.23  5240.4  393.67  5299.8  395.83  5564.4  401.98  5603.1  403.71
#Mann=5,-1,0
  4455.3    0.08       0  4514.1     0.1       0  4982.2    0.07       0
  4988.2     0.1       0  5138.8    0.05       0
Bank Sta=4982.2,4988.2
Exp/Cntr=0.3,0.1

Type RM Length L Ch R = 1,236,0,0,0
BEGIN DESCRIPTION:
UNT 026 IN LACR 1.0
END DESCRIPTION:
XS GIS Cut Line= 4
      2191157.69     13217564.14      2190733.18     13217280.26
      2190402.45     13217334.95      2190108.19     13217855.75
#Sta/Elev= 30
  4291.2  406.53  4299.1  405.94  4311.3  405.22  4317.3  405.86  4404.3  401.61
  4491.4  399.64  4527.5  397.26  4533.5  398.20  4542.5  397.17  4548.5  397.78
  4591.9  395.36  4599.5  394.17  4751.9  389.07  4848.0  386.57  4949.3  387.11
  4989.9  385.83  4995.3  383.66  5000.3  384.05  5007.1  383.00  5009.9  382.50
  5013.1  383.00  5020.3  386.13  5030.4  386.74  5099.3  387.66  5141.1  387.44
  5302.5  392.96  5361.7  393.60  5369.0  394.51  5561.0  399.17  5735.3  402.09
#Mann=6,-1,0
  4291.2    0.05       0  4299.1    0.08       0  4751.9     0.1       0
  5007.1    0.07       0  5013.1     0.1       0  5099.3    0.05       0
Bank Sta=5007.1,5013.1
Exp/Cntr=0.3,0.1

Chan Stop Cuts=-1