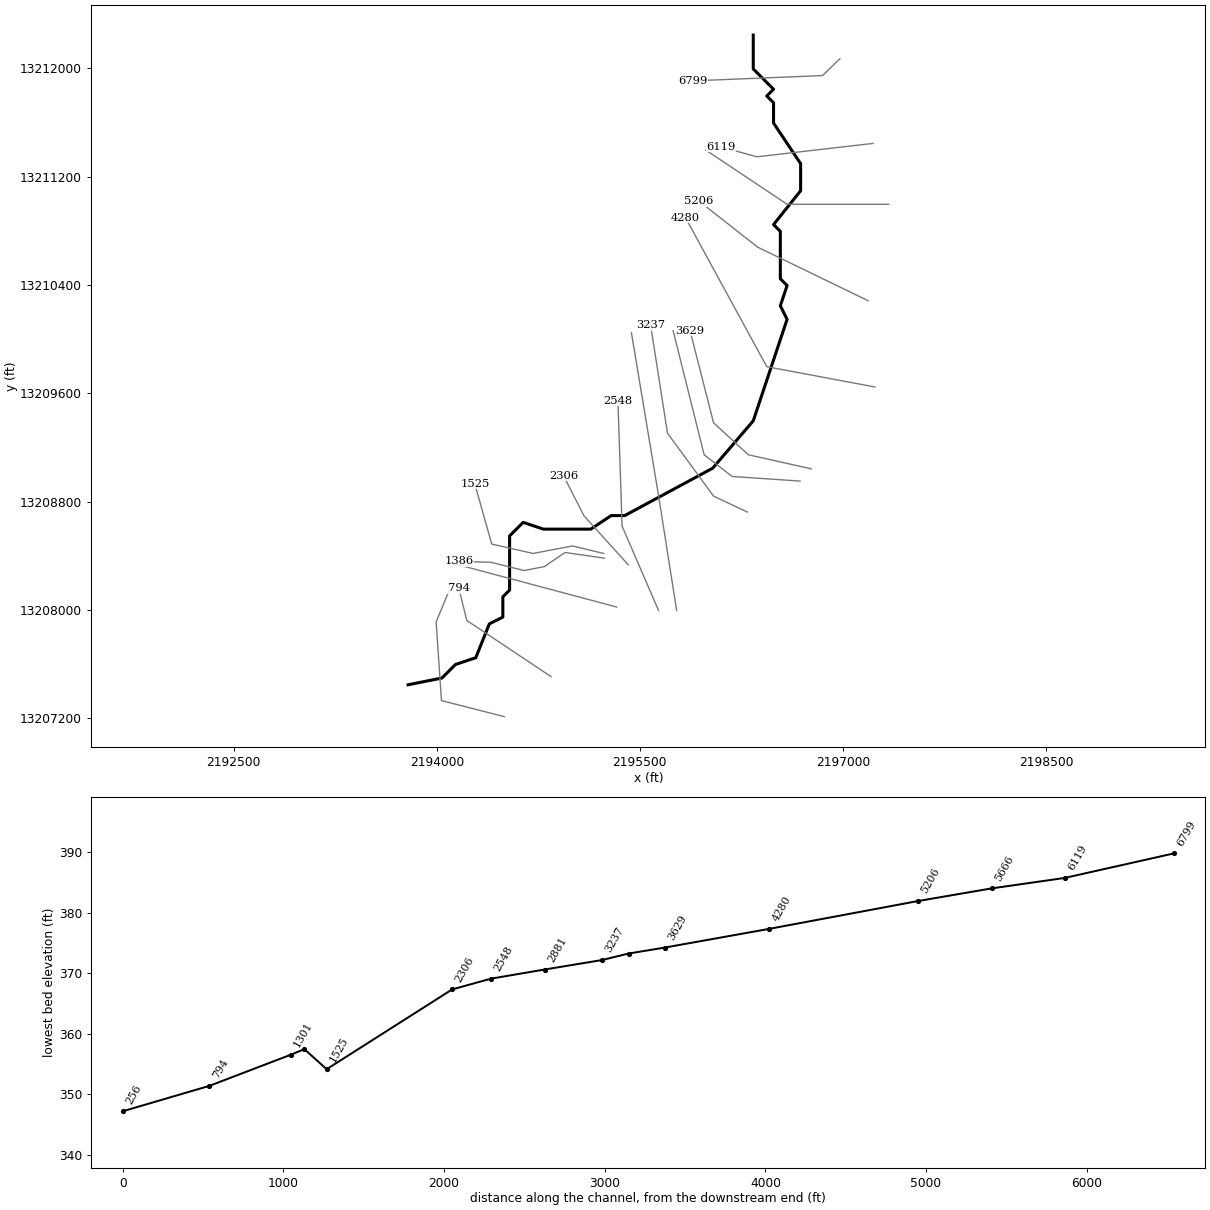
--- UNT 027 IN LACR.prj (project) ---

Proj Title=UNT 027 IN LACR Base Level Engineering
Current Plan=p01
Default Exp/Contr=0.3,0.1
English Units
Geom File=g01
Flow File=f01
Plan File=p01
BEGIN DESCRIPTION:
UNT 027 IN LACR
END DESCRIPTION:

--- UNT 027 IN LACR.p01 (plan) ---

Plan Title=Multiple Run
Short Identifier=Multiple
Geom File=g01
Flow File=f01
Subcritical Flow
K Sum by GR= 0
Std Step Tol= 0.01
Critical Tol= 0.01
Num of Std Step Trials= 20
Max Error Tol= 0.3
Flow Tol Ratio= 0.001
Split Flow NTrial= 30
Split Flow Tol= 0.02
Split Flow Ratio= 0.02
Log Output Level= 0
Friction Slope Method= 1
Unsteady Friction Slope Method= 2
Unsteady Bridges Friction Slope Method= 1
Parabolic Critical Depth
Global Vel Dist=  1 , 1 , 1
Global Log Level= 0
CheckData=True
Encroach Param= -1, 0, 0, 0
BEGIN DESCRIPTION:
Multiple Run
END DESCRIPTION:

--- UNT 027 IN LACR.f01 (steady flow) ---

Flow Title=Multiple
Number of Profiles=7
Profile Names=10-year,25-year,50-year,1pct_min,100-year,1pct_plu,500-year
River Rch & RM= UNT 027 IN LACR,Reach-1,6799
     188     258     315     283     383     517     574
River Rch & RM= UNT 027 IN LACR,Reach-1,5666
     235     326     400     362     490     662     745
Boundary for River Rch & Prof#=UNT 027 IN LACR,Reach-1,1
Up Type=0
Dn Type=3
Dn Slope=0.005
Boundary for River Rch & Prof#=UNT 027 IN LACR,Reach-1,2
Up Type=0
Dn Type=3
Dn Slope=0.005
Boundary for River Rch & Prof#=UNT 027 IN LACR,Reach-1,3
Up Type=0
Dn Type=3
Dn Slope=0.005
Boundary for River Rch & Prof#=UNT 027 IN LACR,Reach-1,4
Up Type=0
Dn Type=3
Dn Slope=0.005
Boundary for River Rch & Prof#=UNT 027 IN LACR,Reach-1,5
Up Type=0
Dn Type=3
Dn Slope=0.005
Boundary for River Rch & Prof#=UNT 027 IN LACR,Reach-1,6
Up Type=0
Dn Type=3
Dn Slope=0.005
Boundary for River Rch & Prof#=UNT 027 IN LACR,Reach-1,7
Up Type=0
Dn Type=3
Dn Slope=0.005

--- UNT 027 IN LACR.g01 (geometry) ---

Geom Title=Existing Conditions

River Reach=UNT 027 IN LACR,Reach-1
Reach XY= 30
      2196337.72     13212246.85      2196337.72     13211996.86
      2196487.72     13211846.86      2196437.72     13211796.85
      2196487.72     13211746.85      2196487.72     13211596.85
      2196687.72     13211296.85      2196687.72     13211096.85
      2196487.72     13210846.86      2196537.72     13210796.85
      2196537.72     13210446.85      2196587.72     13210396.85
      2196537.72     13210246.85      2196587.72     13210146.85
      2196337.72     13209396.86      2196037.72     13209046.86
      2195387.72     13208696.85      2195287.72     13208696.85
      2195137.72     13208596.85      2194787.72     13208596.85
      2194637.72     13208646.85      2194537.72     13208546.86
      2194537.72     13208146.85      2194487.72     13208096.85
      2194487.72     13207946.85      2194387.72     13207896.86
      2194287.72     13207646.85      2194137.72     13207596.85
      2194037.72     13207496.85      2193787.72     13207446.85

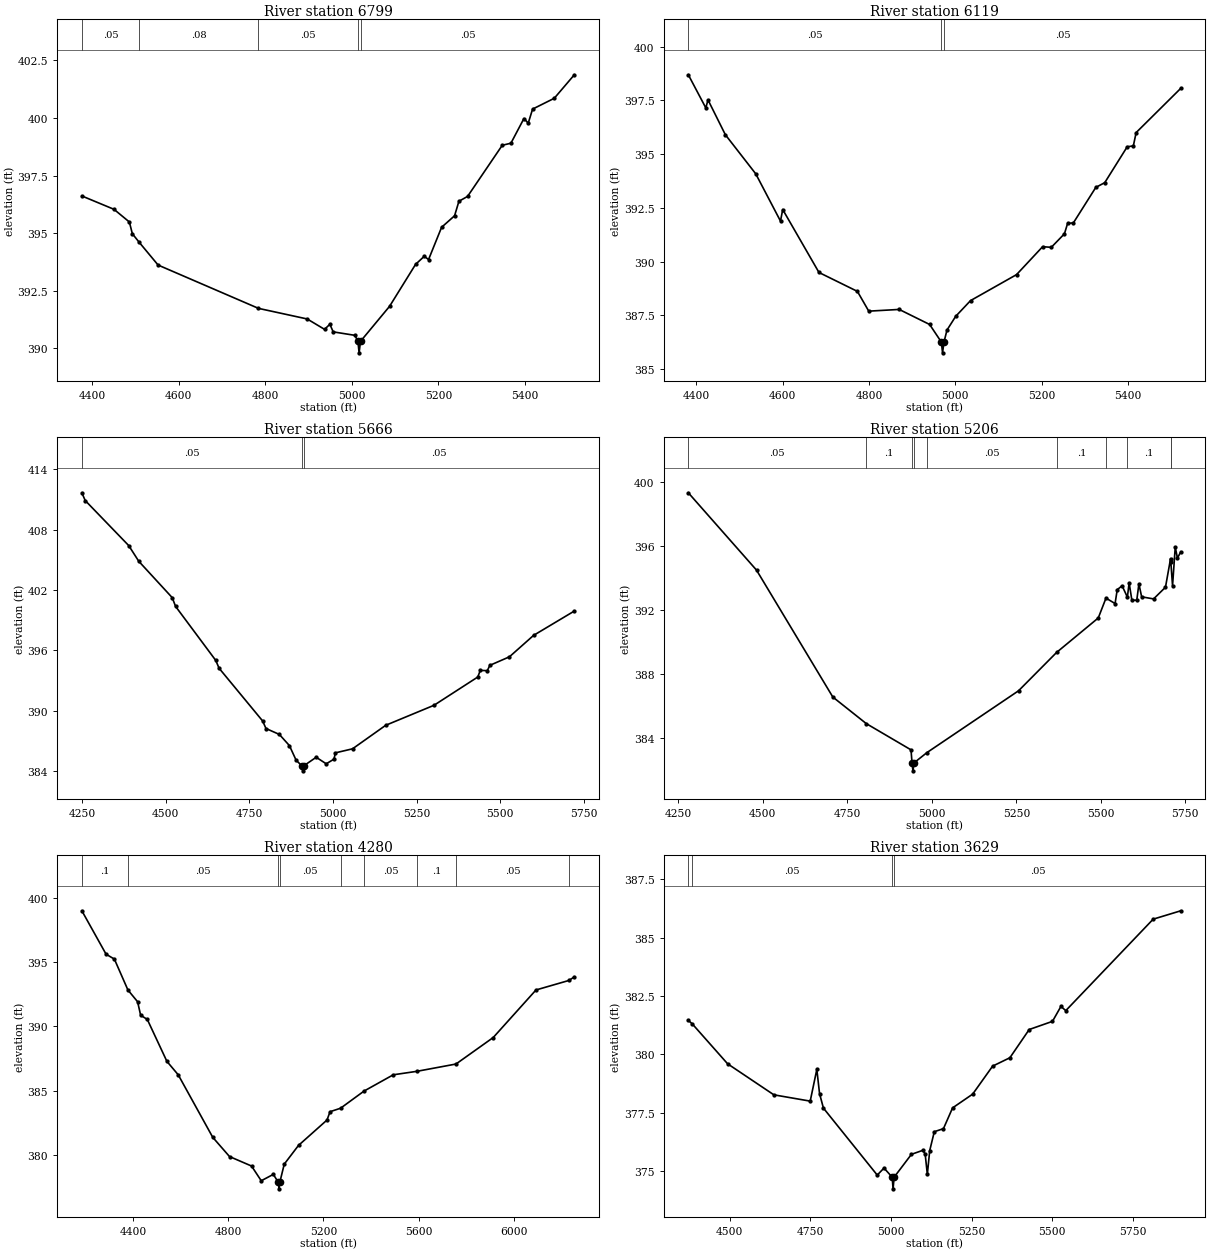
Type RM Length L Ch R = 1,6799,680,680,680
BEGIN DESCRIPTION:
UNT 027 IN LACR 12.0
END DESCRIPTION:
XS GIS Cut Line= 3
      2196977.73     13212071.79      2196849.41     13211947.82
      2195891.43     13211908.72
#Sta/Elev= 30
  4376.7  396.62  4450.9  396.04  4486.4  395.49  4493.3  394.98  4508.6  394.62
  4552.8  393.62  4784.6  391.74  4897.1  391.28  4937.1  390.83  4949.4  391.05
  4957.1  390.72  5007.2  390.57  5014.2  390.31  5016.9  389.81  5020.2  390.31
  5087.3  391.83  5147.3  393.65  5167.3  394.00  5177.3  393.86  5207.4  395.26
  5237.4  395.76  5247.4  396.39  5267.4  396.60  5347.5  398.82  5367.5  398.91
  5397.5  399.98  5407.5  399.78  5417.5  400.39  5467.6  400.86  5513.9  401.88
#Mann=5,-1,0
  4376.7    0.05       0  4508.6    0.08       0  4784.6    0.05       0
  5014.2    0.03       0  5020.2    0.05       0
Bank Sta=5014.2,5020.2
Exp/Cntr=0.3,0.1

Type RM Length L Ch R = 1,6119,453,453,453
BEGIN DESCRIPTION:
UNT 027 IN LACR 10.0
END DESCRIPTION:
XS GIS Cut Line= 3
      2197222.92     13211446.49      2196363.86     13211347.61
      2196098.14     13211421.77
#Sta/Elev= 30
  4381.8  398.69  4422.3  397.15  4427.4  397.52  4467.6  395.90  4538.0  394.08
  4595.3  391.88  4600.4  392.42  4684.4  389.49  4773.4  388.61  4799.7  387.69
  4870.2  387.77  4940.7  387.07  4967.9  386.25  4970.6  385.75  4973.9  386.25
  4980.9  386.81  5001.1  387.45  5035.4  388.18  5142.0  389.39  5202.4  390.69
  5222.5  390.66  5252.9  391.29  5260.2  391.77  5273.7  391.80  5325.6  393.45
  5346.3  393.67  5398.3  395.34  5412.5  395.38  5419.0  396.00  5522.4  398.06
#Mann=3,-1,0
  4381.8    0.05       0  4967.9    0.03       0  4973.9    0.05       0
Bank Sta=4967.9,4973.9
Exp/Cntr=0.3,0.1

Type RM Length L Ch R = 1,5666,460,460,460
BEGIN DESCRIPTION:
UNT 027 IN LACR 9.0
END DESCRIPTION:
XS GIS Cut Line= 3
      2197337.72     13210996.85      2196587.72     13210996.86
      2195987.73     13211396.85
#Sta/Elev= 30
  4250.0  411.68  4260.0  410.91  4390.0  406.43  4420.0  404.87  4520.0  401.25
  4530.0  400.38  4650.0  395.01  4660.0  394.23  4790.0  388.99  4800.0  388.24
  4840.0  387.65  4870.0  386.54  4890.0  385.09  4907.0  384.53  4909.8  384.03
  4913.0  384.53  4950.0  385.38  4980.0  384.73  5003.0  385.19  5007.5  385.82
  5058.6  386.22  5157.7  388.56  5302.0  390.55  5432.7  393.36  5440.2  394.02
  5461.2  393.99  5468.7  394.52  5527.3  395.37  5599.4  397.50  5721.1  399.92
#Mann=3,-1,0
  4250.0    0.05       0  4907.0    0.03       0  4913.0    0.05       0
Bank Sta=4907,4913
Exp/Cntr=0.3,0.1

Type RM Length L Ch R = 1,5206,926,926,926
BEGIN DESCRIPTION:
UNT 027 IN LACR 8.0
END DESCRIPTION:
XS GIS Cut Line= 3
      2197185.86     13210284.62      2196370.04     13210680.16
      2195937.45     13211020.06
#Sta/Elev= 30
  4279.7  399.30  4481.4  394.47  4707.2  386.54  4806.2  384.88  4938.5  383.24
  4941.4  382.43  4944.2  381.93  4947.4  382.43  4985.6  383.07  5256.5  386.93
  5369.3  389.33  5492.4  391.48  5515.2  392.72  5542.1  392.38  5548.5  393.25
  5562.9  393.49  5578.5  392.78  5583.7  393.67  5591.8  392.59  5606.3  392.59
  5612.6  393.61  5620.7  392.80  5656.0  392.67  5691.2  393.40  5706.3  395.19
  5707.1  394.96  5712.1  393.49  5720.1  395.91  5726.5  395.22  5736.5  395.61
#Mann=10,-1,0
  4279.7    0.05       0  4806.2     0.1       0  4941.4    0.03       0
  4947.4     0.1       0  4985.6    0.05       0  5369.3     0.1       0
  5515.2    0.05       0  5578.5     0.1       0  5706.3    0.05       0
  5707.1     0.1       0
Bank Sta=4941.4,4947.4
Exp/Cntr=0.3,0.1

Type RM Length L Ch R = 1,4280,651,651,651
BEGIN DESCRIPTION:
UNT 027 IN LACR 7.0
END DESCRIPTION:
XS GIS Cut Line= 3
      2197237.68     13209646.86      2196437.72     13209796.85
      2195837.72     13210896.86
#Sta/Elev= 30
  4186.1  399.03  4287.8  395.64  4322.6  395.26  4379.4  392.85  4420.1  391.93
  4432.8  390.88  4460.8  390.55  4543.0  387.28  4590.5  386.23  4735.5  381.35
  4805.8  379.85  4898.3  379.11  4939.0  377.96  4989.8  378.46  5010.8  377.83
  5013.5  377.33  5016.8  377.83  5035.6  379.26  5095.4  380.72  5215.0  382.70
  5227.8  383.35  5271.8  383.62  5370.5  384.96  5493.1  386.23  5591.9  386.50
  5756.3  387.07  5912.7  389.14  6092.1  392.85  6229.9  393.59  6253.0  393.87
#Mann=9,-1,0
  4186.1     0.1       0  4379.4    0.05       0  5010.8    0.03       0
  5016.8    0.05       0  5271.8     0.1       0  5370.5    0.05       0
  5591.9     0.1       0  5756.3    0.05       0  6229.9     0.1       0
Bank Sta=5010.8,5016.8
Exp/Cntr=0.3,0.1

Type RM Length L Ch R = 1,3629,224,224,224
BEGIN DESCRIPTION:
Mapping XS b57c71cf
END DESCRIPTION:
XS GIS Cut Line= 4
      2196766.66     13209042.15      2196301.34     13209146.33
      2196044.39     13209382.44      2195870.92     13210062.46
#Sta/Elev= 30
  4371.6  381.45  4383.3  381.31  4493.5  379.59  4637.0  378.26  4749.7  377.99
  4770.2  379.35  4778.7  378.31  4790.7  377.69  4957.6  374.82  4978.6  375.12
  5004.0  374.73  5006.7  374.23  5010.0  374.73  5063.7  375.71  5098.8  375.88
  5106.2  375.73  5113.0  374.85  5120.4  375.87  5134.6  376.68  5163.0  376.81
  5191.3  377.70  5253.6  378.29  5315.5  379.49  5369.1  379.85  5429.0  381.06
  5501.2  381.41  5527.4  382.05  5542.5  381.87  5813.5  385.79  5899.2  386.15
#Mann=4,-1,0
  4371.6     0.1       0  4383.3    0.05       0  5004.0    0.03       0
  5010.0    0.05       0
Bank Sta=5004,5010
Exp/Cntr=0.3,0.1

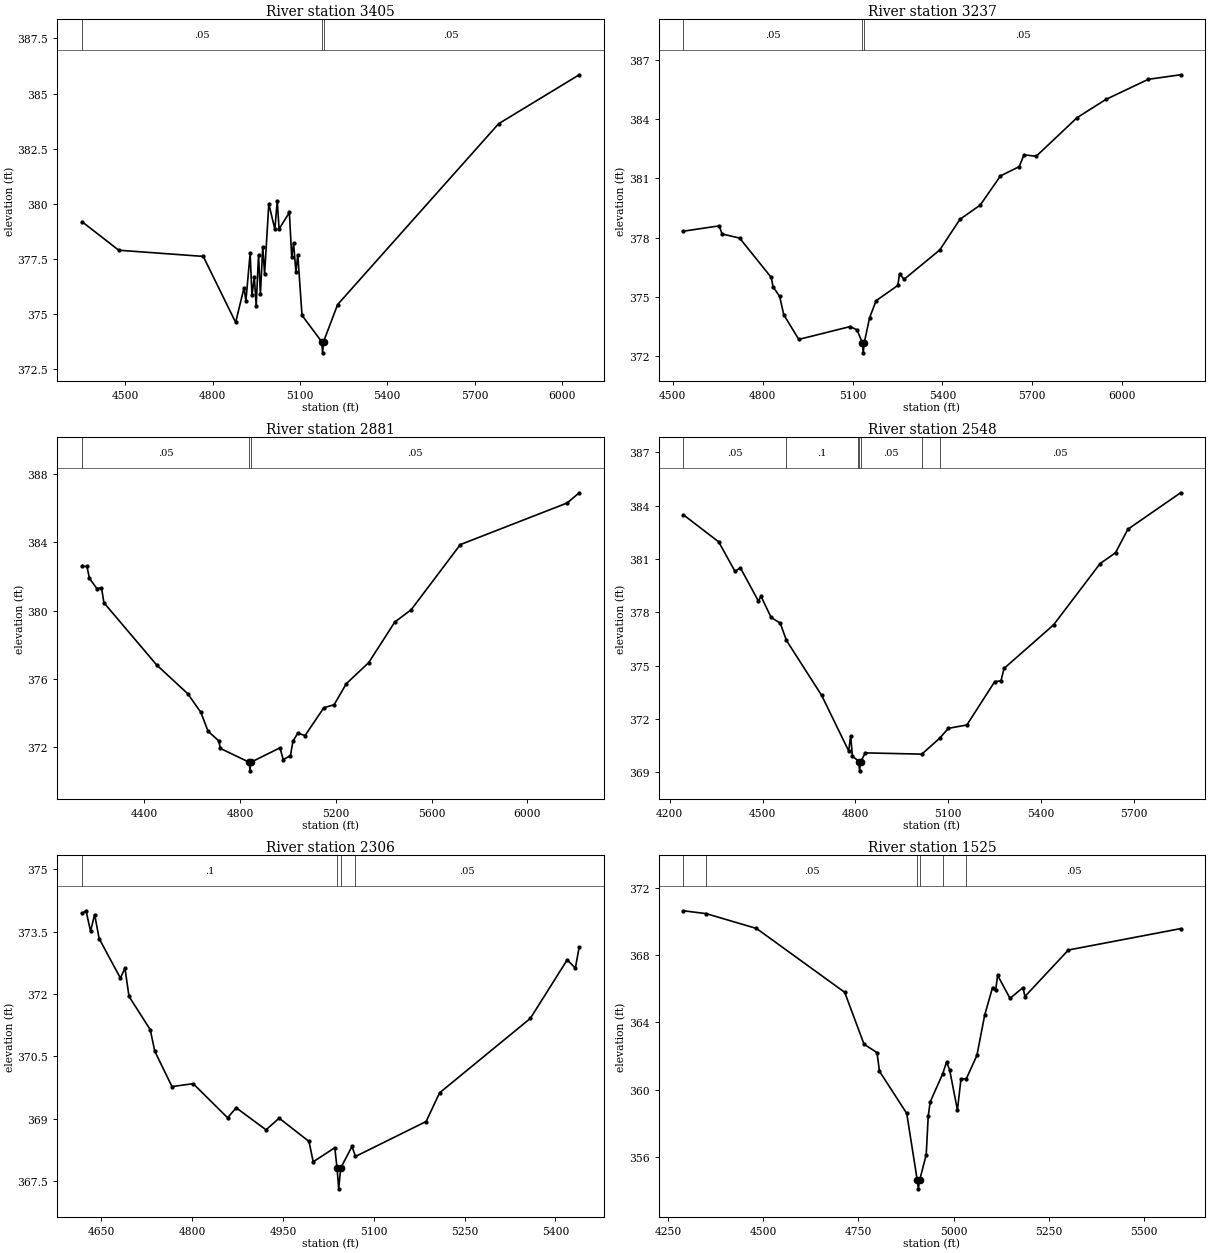
Type RM Length L Ch R = 1,3405,168,168,168
BEGIN DESCRIPTION:
UNT 027 IN LACR 6.0
END DESCRIPTION:
XS GIS Cut Line= 4
      2196683.29     13208951.89      2196181.40     13208986.02
      2195974.95     13209146.33      2195745.93     13210062.41
#Sta/Elev= 30
  4351.2  379.19  4477.1  377.90  4767.7  377.62  4879.0  374.63  4907.9  376.20
  4914.3  375.61  4928.8  377.76  4935.1  375.85  4943.2  376.68  4949.6  375.39
  4957.7  377.70  4964.1  375.90  4972.2  378.06  4978.5  376.82  4993.0  380.00
  5013.8  378.85  5022.0  380.14  5028.3  378.86  5063.6  379.61  5071.8  377.58
  5078.1  378.22  5086.2  376.91  5092.6  377.70  5107.1  374.95  5175.0  373.75
  5177.8  373.25  5181.0  373.75  5229.6  375.44  5782.8  383.63  6059.9  385.85
#Mann=3,-1,0
  4351.2    0.05       0  5175.0    0.03       0  5181.0    0.05       0
Bank Sta=5175,5181
Exp/Cntr=0.3,0.1

Type RM Length L Ch R = 1,3237,356,356,356
BEGIN DESCRIPTION:
Mapping XS 317d68bb
END DESCRIPTION:
XS GIS Cut Line= 4
      2196294.40     13208722.71      2196044.39     13208840.77
      2195704.11     13209306.05      2195579.34     13210103.23
#Sta/Elev= 30
  4535.5  378.32  4654.8  378.59  4664.5  378.18  4723.1  377.97  4828.7  375.98
  4834.9  375.50  4856.7  375.02  4870.5  374.09  4920.6  372.84  5092.1  373.49
  5115.2  373.32  5133.1  372.66  5135.8  372.16  5139.1  372.66  5156.9  373.93
  5178.8  374.80  5251.1  375.57  5257.3  376.17  5272.0  375.88  5391.4  377.37
  5458.6  378.92  5526.3  379.64  5594.1  381.12  5656.8  381.59  5672.6  382.19
  5713.1  382.11  5849.9  384.07  5945.9  384.99  6087.6  386.01  6195.3  386.24
#Mann=3,-1,0
  4535.5    0.05       0  5133.1    0.03       0  5139.1    0.05       0
Bank Sta=5133.1,5139.1
Exp/Cntr=0.3,0.1

Type RM Length L Ch R = 1,2881,333,333,333
BEGIN DESCRIPTION:
UNT 027 IN LACR 5.0
END DESCRIPTION:
XS GIS Cut Line= 3
      2195771.67     13207996.74      2195637.72     13208846.85
      2195437.71     13210046.90
#Sta/Elev= 30
  4139.4  382.60  4159.8  382.59  4169.9  381.90  4201.1  381.29  4220.5  381.34
  4230.6  380.46  4451.1  376.81  4581.1  375.12  4635.6  374.03  4665.9  372.92
  4711.2  372.35  4716.5  371.92  4838.2  371.10  4841.0  370.60  4844.2  371.10
  4966.2  371.95  4979.8  371.26  5010.1  371.49  5020.3  372.33  5040.6  372.81
  5071.0  372.67  5149.5  374.30  5192.6  374.48  5243.3  375.71  5337.1  376.95
  5446.1  379.33  5514.5  380.05  5719.8  383.87  6165.9  386.31  6216.6  386.91
#Mann=3,-1,0
  4139.4    0.05       0  4838.2    0.03       0  4844.2    0.05       0
Bank Sta=4838.2,4844.2
Exp/Cntr=0.3,0.1

Type RM Length L Ch R = 1,2548,242,242,242
BEGIN DESCRIPTION:
UNT 027 IN LACR 4.1
END DESCRIPTION:
XS GIS Cut Line= 3
      2195637.72     13207996.85      2195368.89     13208618.29
      2195337.72     13209546.88
#Sta/Elev= 30
  4244.3  383.49  4358.2  381.97  4410.6  380.32  4428.6  380.50  4486.5  378.64
  4494.9  378.91  4527.6  377.72  4557.0  377.40  4577.0  376.43  4691.0  373.33
  4778.2  370.21  4784.7  371.05  4790.2  369.91  4808.9  369.66  4810.7  369.59
  4813.4  369.09  4816.7  369.59  4831.7  370.10  5014.7  370.03  5073.1  370.94
  5100.1  371.48  5160.1  371.67  5250.1  374.11  5270.2  374.15  5280.2  374.85
  5440.2  377.30  5590.3  380.74  5640.4  381.36  5680.4  382.68  5850.5  384.73
#Mann=7,-1,0
  4244.3    0.05       0  4577.0     0.1       0  4808.9    0.05       0
  4810.7    0.03       0  4816.7    0.05       0  5014.7     0.1       0
  5073.1    0.05       0
Bank Sta=4810.7,4816.7
Exp/Cntr=0.3,0.1

Type RM Length L Ch R = 1,2306,781,781,781
BEGIN DESCRIPTION:
UNT 027 IN LACR 4.0
END DESCRIPTION:
XS GIS Cut Line= 3
      2195414.00     13208333.60      2195087.64     13208694.67
      2194935.25     13208992.54
#Sta/Elev= 30
  4618.0  373.94  4624.5  374.00  4632.0  373.51  4638.7  373.91  4646.2  373.33
  4681.3  372.38  4688.8  372.62  4695.5  371.94  4730.6  371.14  4738.1  370.62
  4766.5  369.77  4801.6  369.84  4858.4  369.02  4872.6  369.26  4921.9  368.73
  4943.6  369.01  4992.9  368.45  4999.8  367.96  5035.5  368.30  5039.2  367.81
  5042.0  367.31  5045.2  367.81  5063.9  368.33  5069.7  368.09  5186.4  368.93
  5208.6  369.62  5358.5  371.41  5419.5  372.82  5432.9  372.62  5439.3  373.13
#Mann=4,-1,0
  4618.0     0.1       0  5039.2    0.07       0  5045.2     0.1       0
  5069.7    0.05       0
Bank Sta=5039.2,5045.2
Exp/Cntr=0.3,0.1

Type RM Length L Ch R = 1,1525,139,139,139
BEGIN DESCRIPTION:
UNT 027 IN LACR 3.0
END DESCRIPTION:
XS GIS Cut Line= 5
      2195231.92     13208417.16      2195002.72     13208472.72
      2194711.06     13208417.16      2194405.50     13208486.61
      2194280.50     13208931.07
#Sta/Elev= 30
  4289.5  370.62  4349.5  370.45  4481.7  369.57  4713.7  365.78  4764.6  362.70
  4798.7  362.20  4805.3  361.09  4876.9  358.59  4904.7  354.61  4907.5  354.11
  4910.7  354.61  4928.2  356.13  4933.5  358.43  4938.6  359.27  4971.4  360.93
  4981.7  361.63  4989.7  361.19  5010.3  358.79  5019.6  360.63  5033.8  360.65
  5061.5  362.03  5082.0  364.42  5102.6  366.06  5110.9  365.90  5116.0  366.79
  5148.6  365.42  5182.7  366.06  5187.9  365.53  5302.1  368.29  5597.3  369.56
#Mann=6,-1,0
  4289.5     0.1       0  4349.5    0.05       0  4904.7    0.07       0
  4910.7    0.05       0  4971.4     0.1       0  5033.8    0.05       0
Bank Sta=4904.7,4910.7
Exp/Cntr=0.3,0.1

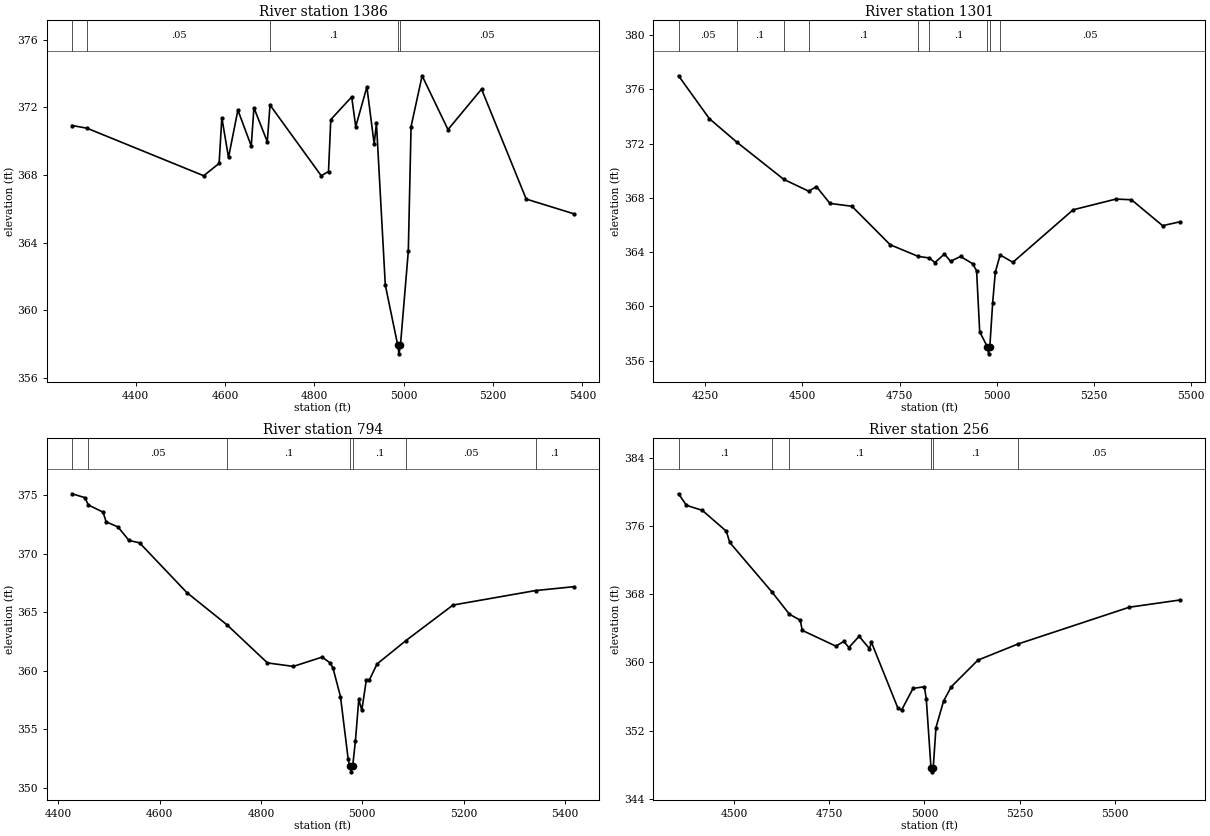
Type RM Length L Ch R = 1,1386,85,85,85
BEGIN DESCRIPTION:
UNT 027 IN LACR 2.0
END DESCRIPTION:
XS GIS Cut Line= 6
      2195238.80     13208382.45      2194947.17     13208424.11
      2194794.39     13208319.94      2194644.50     13208291.03
      2194400.58     13208351.79      2194161.20     13208358.26
#Sta/Elev= 30
  4257.8  370.93  4291.3  370.77  4552.4  367.96  4586.9  368.69  4593.0  371.39
  4607.9  369.04  4628.9  371.84  4658.8  369.72  4664.8  371.98  4694.7  369.97
  4700.8  372.14  4815.4  367.96  4831.7  368.21  4836.8  371.28  4883.6  372.62
  4892.6  370.86  4917.6  373.21  4933.9  369.84  4939.0  371.06  4958.8  361.50
  4986.7  357.93  4989.4  357.43  4992.7  357.93  5010.3  363.50  5016.5  370.87
  5041.2  373.87  5099.1  370.69  5174.2  373.08  5274.2  366.58  5380.8  365.71
#Mann=5,-1,0
  4257.8     0.1       0  4291.3    0.05       0  4700.8     0.1       0
  4986.7    0.03       0  4992.7    0.05       0
Bank Sta=4986.7,4992.7
Exp/Cntr=0.3,0.1

Type RM Length L Ch R = 1,1301,507,507,507
BEGIN DESCRIPTION:
Mapping XS 31318f78
END DESCRIPTION:
XS GIS Cut Line= 2
      2195329.07     13208021.34      2194080.88     13208354.19
#Sta/Elev= 30
  4181.0  377.00  4260.3  373.84  4330.9  372.11  4452.1  369.36  4516.2  368.49
  4535.9  368.83  4570.8  367.59  4627.4  367.38  4726.0  364.54  4798.4  363.68
  4826.5  363.57  4841.2  363.23  4865.5  363.86  4881.3  363.32  4906.9  363.68
  4937.9  363.15  4948.3  362.63  4956.3  358.13  4976.3  357.00  4979.1  356.50
  4982.3  357.00  4989.7  360.26  4996.4  362.50  5008.9  363.79  5041.7  363.25
  5196.9  367.12  5306.9  367.91  5347.0  367.86  5427.2  365.95  5472.8  366.24
#Mann=9,-1,0
  4181.0    0.05       0  4330.9     0.1       0  4452.1    0.05       0
  4516.2     0.1       0  4798.4    0.05       0  4826.5     0.1       0
  4976.3    0.07       0  4982.3     0.1       0  5008.9    0.05       0
Bank Sta=4976.3,4982.3
Exp/Cntr=0.3,0.1

Type RM Length L Ch R = 1,794,538,538,538
BEGIN DESCRIPTION:
Mapping XS 23ac8b40
END DESCRIPTION:
XS GIS Cut Line= 3
      2194843.20     13207507.59      2194221.74     13207921.89
      2194162.64     13208158.32
#Sta/Elev= 30
  4426.9  375.14  4452.1  374.81  4459.1  374.18  4488.1  373.57  4494.1  372.74
  4517.6  372.30  4539.2  371.15  4560.2  370.94  4653.4  366.69  4732.7  363.93
  4812.6  360.67  4863.7  360.37  4920.8  361.17  4935.8  360.68  4941.8  360.26
  4956.8  357.78  4971.9  352.46  4974.9  351.85  4977.6  351.35  4980.9  351.85
  4986.3  354.01  4992.9  357.54  4998.9  356.62  5007.9  359.24  5013.9  359.22
  5029.0  360.58  5086.0  362.58  5178.9  365.62  5341.9  366.86  5417.5  367.19
#Mann=7,-1,0
  4426.9     0.1       0  4459.1    0.05       0  4732.7     0.1       0
  4974.9    0.07       0  4980.9     0.1       0  5086.0    0.05       0
  5341.9     0.1       0
Bank Sta=4974.9,4980.9
Exp/Cntr=0.3,0.1

Type RM Length L Ch R = 1,256,0,0,0
BEGIN DESCRIPTION:
UNT 027 IN LACR 1.0
END DESCRIPTION:
XS GIS Cut Line= 4
      2194497.95     13207211.66      2194034.32     13207330.04
      2193994.87     13207912.03      2194093.12     13208147.85
#Sta/Elev= 30
  4354.3  379.79  4375.2  378.43  4416.5  377.85  4479.9  375.39  4488.7  374.08
  4599.3  368.28  4645.3  365.66  4673.9  364.95  4679.0  363.76  4767.4  361.91
  4788.0  362.46  4801.6  361.75  4828.5  363.07  4855.6  361.60  4860.6  362.37
  4929.8  354.68  4939.9  354.41  4969.9  356.95  4999.7  357.15  5004.7  355.70
  5017.0  347.66  5019.8  347.16  5023.0  347.66  5030.1  352.35  5050.1  355.47
  5070.2  357.14  5140.3  360.27  5245.4  362.16  5537.8  366.48  5671.6  367.33
#Mann=6,-1,0
  4354.3     0.1       0  4599.3    0.05       0  4645.3     0.1       0
  5017.0    0.07       0  5023.0     0.1       0  5245.4    0.05       0
Bank Sta=5017,5023
Exp/Cntr=0.3,0.1

Chan Stop Cuts=-1