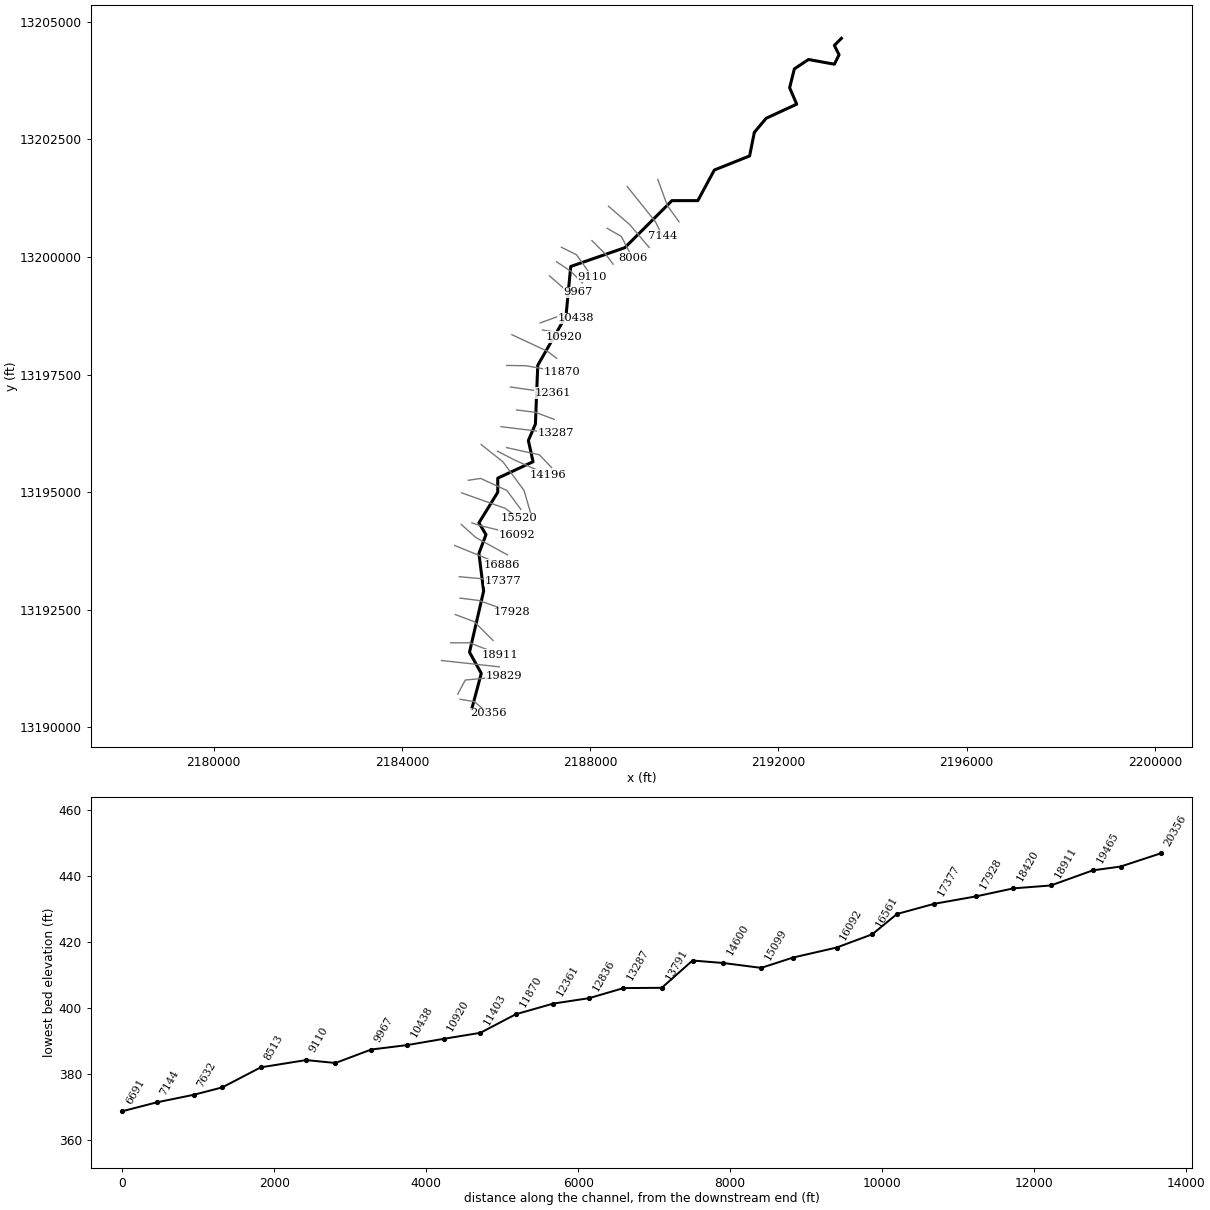
--- UNT 028 IN LACR.prj (project) ---

Proj Title=UNT 028 IN LACR Base Level Engineering
Current Plan=p01
Default Exp/Contr=0.3,0.1
English Units
Geom File=g01
Flow File=f01
Plan File=p01
Y Axis Title=Elevation
X Axis Title(PF)=Main Channel Distance
X Axis Title(XS)=Station
BEGIN DESCRIPTION:
UNT 028 IN LACR
END DESCRIPTION:
DSS Export Rating Curves= 0
DSS Export Rating Curve Sorted= 0
DSS Export Volume Flow Curves= 0
DXF OffsetX= 0
DXF OffsetY= 0
DXF ScaleX= 1
DXF ScaleY= 10

--- UNT 028 IN LACR.p01 (plan) ---

Plan Title=Multiple Run
Short Identifier=Multiple
Geom File=g01
Flow File=f01
Subcritical Flow
K Sum by GR= 0
Std Step Tol= 0.01
Critical Tol= 0.01
Num of Std Step Trials= 20
Max Error Tol= 0.3
Flow Tol Ratio= 0.001
Split Flow NTrial= 30
Split Flow Tol= 0.02
Split Flow Ratio= 0.02
Log Output Level= 0
Friction Slope Method= 1
Unsteady Friction Slope Method= 2
Unsteady Bridges Friction Slope Method= 1
Parabolic Critical Depth
Global Vel Dist=  1 , 1 , 1
Global Log Level= 0
CheckData=True
Encroach Param= -1, 0, 0, 0
BEGIN DESCRIPTION:
Multiple Run
END DESCRIPTION:

--- UNT 028 IN LACR.f01 (steady flow) ---

Flow Title=Multiple
Program Version=4.10
Number of Profiles= 7
Profile Names=10-year,25-year,50-year,1pct_min,100-year,1pct_plu,500-year
River Rch & RM=UNT 028 IN LACR,Reach-1         ,20356
     187     259     319     289     391     529     598
River Rch & RM=UNT 028 IN LACR,Reach-1         ,19829
     312     444     556     512     692     936    1090
River Rch & RM=UNT 028 IN LACR,Reach-1         ,14600
     358     515     649     601     813    1099    1297
River Rch & RM=UNT 028 IN LACR,Reach-1         ,14196
     401     577     728     675     913    1235    1461
River Rch & RM=UNT 028 IN LACR,Reach-1         ,11403
     496     720     913     851    1151    1556    1857
River Rch & RM=UNT 028 IN LACR,Reach-1         ,4962
     541     788    1002     935    1265    1710    2049
River Rch & RM=UNT 028 IN LACR,Reach-1         ,2553
     590     863    1100    1028    1391    1881    2262
River Rch & RM=UNT 028 IN LACR,Reach-1         ,1997
     590     863    1100    1028    1391    1881    2262
Boundary for River Rch & Prof#=UNT 028 IN LACR,Reach-1         , 1
Up Type= 0
Dn Type= 3
Dn Slope=0.005
Boundary for River Rch & Prof#=UNT 028 IN LACR,Reach-1         , 2
Up Type= 0
Dn Type= 3
Dn Slope=0.005
Boundary for River Rch & Prof#=UNT 028 IN LACR,Reach-1         , 3
Up Type= 0
Dn Type= 3
Dn Slope=0.005
Boundary for River Rch & Prof#=UNT 028 IN LACR,Reach-1         , 4
Up Type= 0
Dn Type= 3
Dn Slope=0.005
Boundary for River Rch & Prof#=UNT 028 IN LACR,Reach-1         , 5
Up Type= 0
Dn Type= 3
Dn Slope=0.005
Boundary for River Rch & Prof#=UNT 028 IN LACR,Reach-1         , 6
Up Type= 0
Dn Type= 3
Dn Slope=0.005
Boundary for River Rch & Prof#=UNT 028 IN LACR,Reach-1         , 7
Up Type= 0
Dn Type= 3
Dn Slope=0.005
DSS Import GetInterval= 0
DSS Import GetPeak= 0
DSS Import FillOption= 0

--- UNT 028 IN LACR.g01 (geometry) ---

Geom Title=Existing Conditions
Program Version=4.10

River Reach=UNT 028 IN LACR ,Reach-1
Reach XY= 30
      2185487.72     13190396.85      2185687.72     13191146.86
      2185437.72     13191596.85      2185737.72     13192896.85
      2185637.72     13193696.85      2185787.72     13194096.85
      2185637.72     13194346.85      2186037.72     13194996.85
      2186037.72     13195296.85      2186787.72     13195646.85
      2186687.72     13196096.86      2186837.72     13196446.85
      2186887.72     13197696.85      2187487.72     13198746.85
      2187587.72     13199796.85      2188737.72     13200196.86
      2189737.72     13201196.85      2190287.72     13201196.85
      2190637.72     13201846.86      2191387.72     13202146.86
      2191487.72     13202646.86      2191737.72     13202946.85
      2192387.72     13203246.85      2192237.72     13203596.85
      2192337.72     13203996.85      2192637.72     13204196.85
      2193187.72     13204096.85      2193287.72     13204296.86
      2193187.72     13204496.85      2193337.72     13204646.85

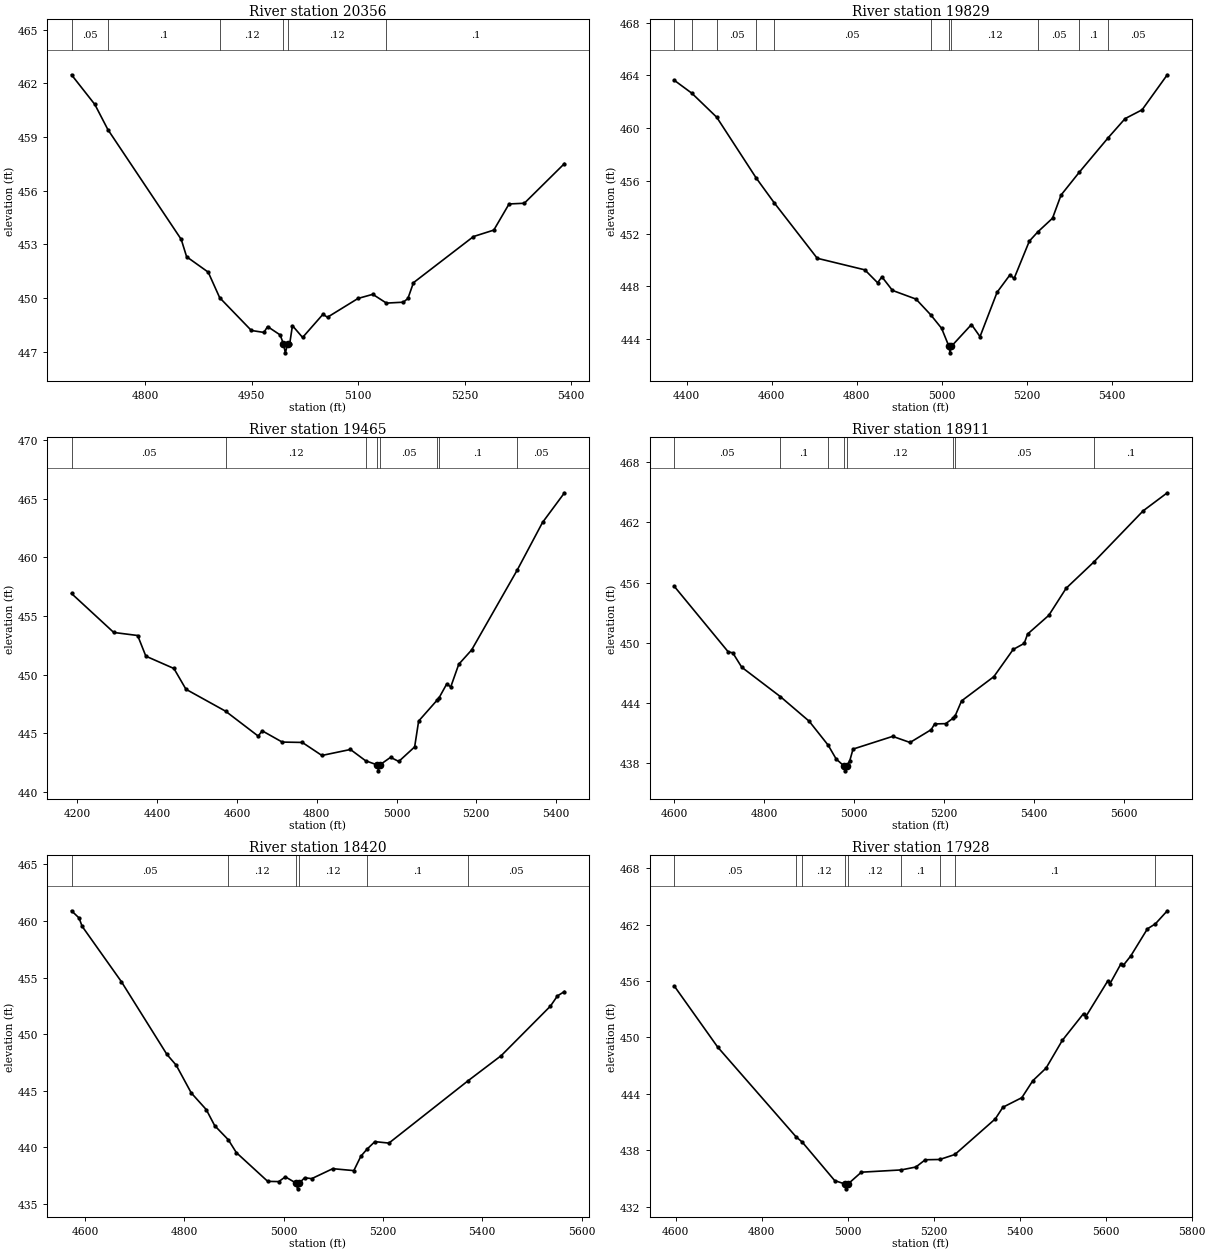
Type RM Length L Ch R = 1 ,20356   ,527,527,527
BEGIN DESCRIPTION:
UNT 028 IN LACR 41.0
END DESCRIPTION:
XS GIS Cut Line= 3
      2185237.76     13190596.85      2185537.72     13190546.85
      2185837.71     13190296.86
#Sta/Elev= 30
  4695.9  462.47  4728.8  460.81  4747.1  459.41  4850.5  453.27  4858.1   452.3
  4888.5  451.44  4904.7  450.01  4949.3  448.18  4967.1  448.07  4972.1   448.4
  4989.9  447.93  4994.5  447.43  4997.2  446.93  5000.5  447.43  5003.3  447.43
  5007.2  448.45  5021.5  447.79  5050.1  449.08  5056.6  448.92  5099.6  449.97
  5120.4   450.2  5139.6  449.71  5163.4  449.76  5169.9  449.97  5177.7  450.85
  5262.3  453.43  5290.9  453.79  5312.4  455.25  5333.9  455.29  5390.5  457.51
#Mann= 6 ,-1 , 0
  4695.9     .05       0  4747.1      .1       0  4904.7     .12       0
  4994.5     .07       0  5000.5     .12       0  5139.6      .1       0
Bank Sta=4994.5,5000.5
XS Rating Curve= 0 ,0
Exp/Cntr=0.3,0.1

Type RM Length L Ch R = 1 ,19829   ,364,364,364
BEGIN DESCRIPTION:
UNT 028 IN LACR 40.0
END DESCRIPTION:
XS GIS Cut Line= 3
      2185188.49     13190707.04      2185348.21     13191005.65
      2186166.73     13191081.95
#Sta/Elev= 30
  4370.6  463.63  4411.9  462.65  4470.4  460.83  4563.7   456.2  4605.4  454.35
  4707.1  450.12  4819.2  449.24  4849.3  448.26  4859.4  448.71  4884.2  447.68
  4939.7  447.02  4974.2  445.83    5000   444.8  5017.1  443.44  5019.8  442.94
  5023.1  443.44  5070.3  445.09  5090.4  444.17  5130.6  447.54  5160.7  448.85
  5170.7  448.59  5206.5  451.42  5226.4  452.12  5261.1  453.16  5281.2  454.92
  5324.6  456.67  5391.9  459.26  5431.9  460.72    5472  461.39  5531.3  464.05
#Mann= 11 ,-1 , 0
  4370.6     .05       0  4411.9      .1       0  4470.4     .05       0
  4563.7      .1       0  4605.4     .05       0  4974.2     .12       0
  5017.1     .07       0  5023.1     .12       0  5226.4     .05       0
  5324.6      .1       0  5391.9     .05       0
Bank Sta=5017.1,5023.1
XS Rating Curve= 0 ,0
Exp/Cntr=0.3,0.1

Type RM Length L Ch R = 1 ,19465   ,554,554,554
BEGIN DESCRIPTION:
UNT 028 IN LACR 39.0
END DESCRIPTION:
XS GIS Cut Line= 2
      2184842.42     13191420.34      2186071.23     13191286.29
#Sta/Elev= 30
    4185  456.91  4290.9  453.59  4350.9  453.33  4371.4  451.57  4441.8  450.52
    4472  448.75  4571.4  446.88  4653.1  444.76  4663.1  445.21  4713.4  444.25
  4763.7  444.22  4812.8  443.11  4884.4  443.62  4922.4  442.66  4951.8   442.3
  4954.6   441.8  4957.8   442.3    4985  442.95  5005.6   442.6  5045.4  443.84
  5055.4  446.04  5101.9  447.83  5106.4  448.01  5125.8   449.2  5135.9  448.95
    5156  450.88  5188.3   452.1    5303  458.93    5366  462.96  5421.1  465.49
#Mann= 8 ,-1 , 0
    4185     .05       0  4571.4     .12       0  4922.4     .05       0
  4951.8     .03       0  4957.8     .05       0  5101.9     .12       0
  5106.4      .1       0    5303     .05       0
Bank Sta=4951.8,4957.8
XS Rating Curve= 0 ,0
Exp/Cntr=0.3,0.1

Type RM Length L Ch R = 1 ,18911   ,491,491,491
BEGIN DESCRIPTION:
UNT 028 IN LACR 38.0
END DESCRIPTION:
XS GIS Cut Line= 3
      2185037.72     13191796.85      2185437.72     13191796.85
       2186087.7     13191546.86
#Sta/Elev= 30
    4600  455.62    4720  449.08    4730  448.99    4750  447.55  4835.8  444.62
    4900  442.16  4942.2  439.77    4960  438.39    4977  437.71  4979.7  437.21
    4983  437.71    4990  438.18  4997.5  439.38  5085.7  440.65  5124.3  440.04
  5171.4  441.32  5178.9  441.89  5203.6  441.92  5220.2  442.47  5224.1  442.64
  5238.9  444.19  5310.7  446.61  5353.6  449.32  5378.2  449.93  5385.7  450.86
  5432.9  452.73  5471.4  455.43  5532.6  458.03  5642.8  463.16  5696.4  464.96
#Mann= 8 ,-1 , 0
    4600     .05       0  4835.8      .1       0  4942.2     .12       0
    4977     .07       0    4983     .12       0  5220.2      .1       0
  5224.1     .05       0  5532.6      .1       0
Bank Sta=4977,4983
XS Rating Curve= 0 ,0
Exp/Cntr=0.3,0.1

Type RM Length L Ch R = 1 ,18420   ,492,492,492
BEGIN DESCRIPTION:
UNT 028 IN LACR 37.0
END DESCRIPTION:
XS GIS Cut Line= 3
      2185137.72     13192396.85      2185537.72     13192246.85
      2185937.73     13191846.84
#Sta/Elev= 30
  4572.8   460.9  4587.9  460.27  4594.2  459.53  4673.4  454.63    4765  448.21
  4783.7  447.26    4814  444.81  4844.2  443.34  4861.2  441.92  4888.7  440.67
  4904.8  439.54    4968     437  4990.2  436.98  5003.5   437.4  5025.3  436.84
    5028  436.34  5031.3  436.84  5042.4  437.32  5056.6  437.24    5099  438.12
  5141.4  437.95  5155.6  439.22  5167.7  439.83  5183.8  440.51  5212.1  440.38
  5371.6  445.89  5438.4  448.11  5537.4  452.48  5551.5  453.38  5565.7  453.77
#Mann= 6 ,-1 , 0
  4572.8     .05       0  4888.7     .12       0  5025.3     .07       0
  5031.3     .12       0  5167.7      .1       0  5371.6     .05       0
Bank Sta=5025.3,5031.3
XS Rating Curve= 0 ,0
Exp/Cntr=0.3,0.1

Type RM Length L Ch R = 1 ,17928   ,551,551,551
BEGIN DESCRIPTION:
UNT 028 IN LACR 36.0
END DESCRIPTION:
XS GIS Cut Line= 3
      2185237.73     13192746.85      2185637.72     13192696.85
      2186337.72     13192446.86
#Sta/Elev= 30
  4596.9  455.46  4697.7  448.98  4880.2  439.43  4894.4  438.88  4969.8  434.79
  4994.5  434.41  4997.2  433.91  5000.5  434.41  5031.9  435.68  5124.6  435.92
  5158.7  436.23  5180.5     437  5214.2  437.03  5249.4  437.56  5343.5  441.35
    5361  442.58  5405.1   443.6  5430.6   445.4  5461.4  446.74  5499.1  449.68
  5548.5  452.53  5553.8  452.21  5604.7  455.99    5610  455.71  5635.5  457.82
  5640.8  457.65  5658.4  458.66  5697.1  461.54  5715.6  462.07  5743.3  463.46
#Mann= 9 ,-1 , 0
  4596.9     .05       0  4880.2      .1       0  4894.4     .12       0
  4994.5     .07       0  5000.5     .12       0  5124.6      .1       0
  5214.2     .12       0  5249.4      .1       0  5715.6     .05       0
Bank Sta=4994.5,5000.5
XS Rating Curve= 0 ,0
Exp/Cntr=0.3,0.1

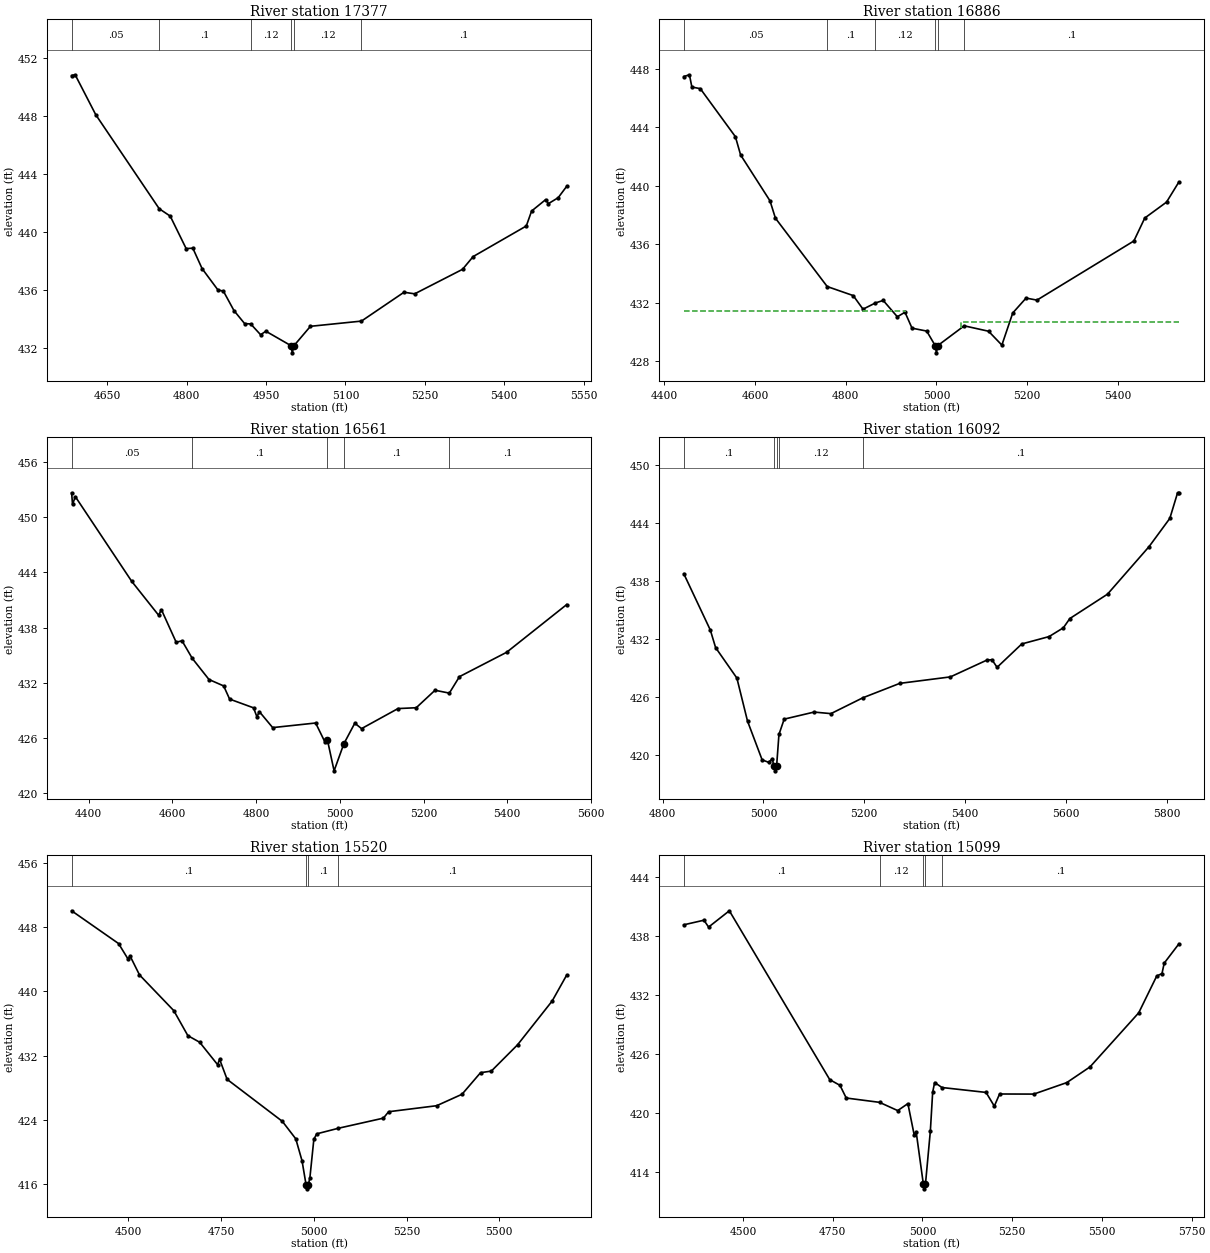
Type RM Length L Ch R = 1 ,17377   ,491,491,491
BEGIN DESCRIPTION:
UNT 028 IN LACR 35.0
END DESCRIPTION:
XS GIS Cut Line= 2
      2185222.19     13193202.12      2186153.84     13193118.44
#Sta/Elev= 30
  4582.8  450.79  4589.5  450.84  4628.5  448.08  4748.3   441.6  4769.1  441.09
  4799.2  438.85  4811.8  438.88  4829.3  437.47  4859.4  435.99  4869.5  435.92
  4889.6  434.57  4909.6  433.68  4921.2  433.65  4939.8  432.91  4949.8  433.15
    4997  432.16  4999.7  431.66    5003  432.16    5034  433.49  5130.4  433.85
  5210.8  435.84  5230.9  435.73  5321.3  437.42  5341.4   438.3  5441.8  440.41
  5451.8  441.44  5478.4  442.23  5483.5  441.95    5502  442.36  5518.2  443.15
#Mann= 6 ,-1 , 0
  4582.8     .05       0  4748.3      .1       0  4921.2     .12       0
    4997     .07       0    5003     .12       0  5130.4      .1       0
Bank Sta=4997,5003
XS Rating Curve= 0 ,0
Exp/Cntr=0.3,0.1

Type RM Length L Ch R = 1 ,16886   ,325,325,325
BEGIN DESCRIPTION:
UNT 028 IN LACR 34.0
END DESCRIPTION:
XS GIS Cut Line= 2
      2185121.68     13193866.78      2186132.65     13193453.45
#Sta/Elev= 30
  4442.5  447.48    4455   447.6  4460.4  446.76    4479  446.65  4556.4  443.36
  4567.9  442.11  4632.7  438.97  4644.7  437.78  4758.9   433.1  4816.3  432.48
  4837.9  431.55  4864.9  431.97  4882.4  432.15  4913.6  431.03  4930.5  431.34
    4946  430.25  4978.4  430.05    4997  429.06  4999.8  428.56    5003  429.06
  5061.1  430.41  5114.8  430.04  5144.2  429.09  5168.2  431.29  5197.6  432.31
  5221.6  432.17  5435.4  436.22  5459.4  437.79  5507.4  438.88  5534.7  440.26
#Mann= 6 ,-1 , 0
  4442.5     .05       0  4758.9      .1       0  4864.9     .12       0
    4997     .07       0    5003     .12       0  5061.1      .1       0
#XS Ineff= 2 , 0
         4930.45  431.41 5053.86          430.69
Permanent Ineff=
       F       F
Bank Sta=4997,5003
XS Rating Curve= 0 ,0
Exp/Cntr=0.3,0.1

Type RM Length L Ch R = 1 ,16561   ,469,469,469
BEGIN DESCRIPTION:
UNT 028 IN LACR 33.0
END DESCRIPTION:
XS GIS Cut Line= 3
      2185261.33      13194313.6      2185574.09     13194034.35
      2186243.54     13193666.15
#Sta/Elev= 30
    4359  452.65  4361.2  451.39  4367.9  452.23  4502.5  443.03  4566.9  439.34
  4573.6  439.94  4608.9   436.4  4622.9  436.56  4647.3  434.65  4687.3  432.35
  4722.4  431.65  4736.6  430.22  4793.8  429.27  4801.9  428.29  4807.6  428.86
  4839.5  427.12  4942.2  427.62  4964.8  425.52  4970.5  425.75  4986.3  422.42
  5009.6  425.36  5035.8   427.6  5051.9  427.01  5139.1  429.19  5182.6  429.28
  5227.5  431.18  5261.7  430.87  5285.9  432.66  5398.7  435.31  5542.3   440.5
#Mann= 5 ,-1 , 0
    4359     .05       0  4647.3      .1       0  4970.5     .04       0
  5009.6      .1       0  5261.7      .1       0
Bank Sta=4970.5,5009.6
XS Rating Curve= 0 ,0
Exp/Cntr=0.3,0.1

Type RM Length L Ch R = 1 ,16092   ,572,572,572
BEGIN DESCRIPTION:
UNT 028 IN LACR 32.0
END DESCRIPTION:
XS GIS Cut Line= 3
      2185487.73     13194346.85      2185637.72     13194296.86
       2186437.7     13194096.86
#Sta/Elev= 30
  4841.9   438.8  4894.6  432.97  4905.1  431.15  4947.3     428  4968.4  423.55
  4997.4  419.54  5010.3  419.28    5018  419.66  5020.2   418.9  5022.9   418.4
  5026.2   418.9  5030.8  422.16  5041.2  423.75  5100.5  424.48    5134  424.32
  5197.4  425.96  5270.6  427.45  5371.1  428.12  5443.2  429.85  5453.5   429.9
  5463.8  429.11  5512.8  431.53  5566.9  432.29  5595.3   433.2  5608.2  434.16
  5682.9  436.68  5765.4   441.6  5806.6  444.52    5822  447.17  5824.6  447.17
#Mann= 5 ,-1 , 0
  4841.9      .1       0  5020.2     .07       0  5026.2      .1       0
  5030.8     .12       0  5197.4      .1       0
Bank Sta=5020.2,5026.2
XS Rating Curve= 0 ,0
Exp/Cntr=0.3,0.1

Type RM Length L Ch R = 1 ,15520   ,421,421,421
BEGIN DESCRIPTION:
UNT 028 IN LACR 31.0
END DESCRIPTION:
XS GIS Cut Line= 3
      2185272.43      13194983.9      2186199.66     13194654.34
      2186478.91     13194442.11
#Sta/Elev= 30
    4347  450.07  4473.6  445.98  4499.1  444.05  4504.5  444.44    4530  442.07
  4622.5  437.61  4660.4  434.49  4692.2  433.67  4740.6  430.87  4745.9  431.55
  4766.2  429.04  4915.1   423.8  4951.3  421.62  4968.2  418.88  4979.1  415.88
  4981.9  415.38  4985.1  415.88  4989.4  416.77    5000  421.55  5007.7  422.24
  5066.4  422.94  5187.5   424.2  5201.6     425  5331.1  425.75  5399.5  427.18
  5449.4  429.87  5478.5  430.07  5549.2  433.35  5642.6  438.82  5681.8  442.06
#Mann= 4 ,-1 , 0
    4347      .1       0  4979.1     .07       0  4985.1      .1       0
  5066.4      .1       0
Bank Sta=4979.1,4985.1
XS Rating Curve= 0 ,0
Exp/Cntr=0.3,0.1

Type RM Length L Ch R = 1 ,15099   ,499,499,499
BEGIN DESCRIPTION:
UNT 028 IN LACR 30.0
END DESCRIPTION:
XS GIS Cut Line= 4
      2185412.09     13195251.98      2185674.62     13195291.09
      2186233.17     13195034.15       2186529.2       13194632.
#Sta/Elev= 30
  4334.9  439.13  4391.1   439.6  4404.1   438.9  4461.9  440.56  4741.7  423.36
  4770.2  422.78  4787.6  421.49  4880.3  421.05    4931  420.21  4959.4  420.92
  4976.9  417.74  4982.4  418.06  5002.4  412.74  5005.1  412.24  5008.4  412.74
    5022  418.14  5028.4  422.07  5033.9  423.07  5054.3  422.56  5177.2  422.06
  5200.2  420.66  5214.9   421.9  5310.3  421.89  5402.1  423.06  5466.9  424.66
  5602.6  430.17  5652.8  433.92  5667.4  434.17  5673.6  435.23  5714.5  437.19
#Mann= 5 ,-1 , 0
  4334.9      .1       0  4880.3     .12       0  5002.4     .07       0
  5008.4     .12       0  5054.3      .1       0
Bank Sta=5002.4,5008.4
XS Rating Curve= 0 ,0
Exp/Cntr=0.3,0.1

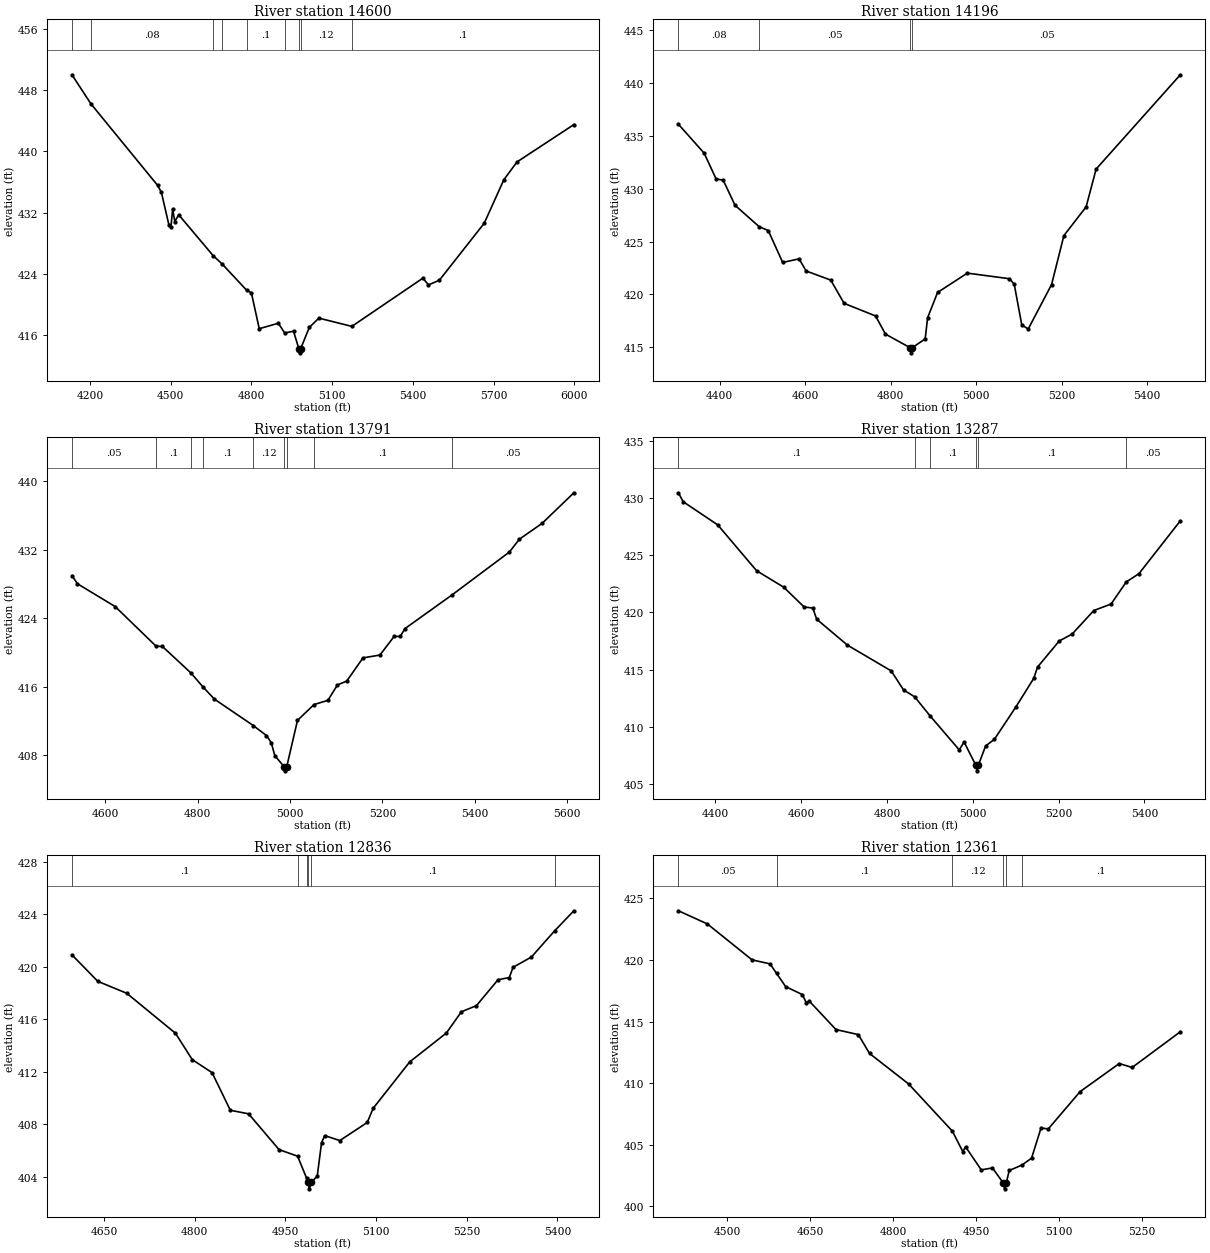
Type RM Length L Ch R = 1 ,14600   ,404,404,404
BEGIN DESCRIPTION:
UNT 028 IN LACR 29.0
END DESCRIPTION:
XS GIS Cut Line= 4
      2185685.81      13196011.6      2186149.39     13195642.97
      2186596.23     13195034.15      2186741.46       13194537.
#Sta/Elev= 30
  4132.7  449.99  4203.2   446.2  4450.9  435.57  4465.3  434.64  4492.9  430.42
  4500.5   430.1  4506.9  432.45    4515  430.85  4529.4  431.73  4657.5   426.4
  4690.9  425.31  4781.9  421.89  4799.5  421.56  4828.8  416.87  4899.8  417.58
  4923.3  416.31  4956.2  416.54  4976.3  414.22    4979  413.72  4982.3  414.22
  5014.8  417.03  5050.3  418.25  5172.9  417.17  5436.9  423.46  5457.8  422.58
  5498.2  423.19  5664.9  430.62  5737.8  436.29  5786.7  438.62  5998.1  443.49
#Mann= 9 ,-1 , 0
  4132.7     .05       0  4203.2     .08       0  4657.5      .1       0
  4690.9     .05       0  4781.9      .1       0  4923.3     .12       0
  4976.3     .07       0  4982.3     .12       0  5172.9      .1       0
Bank Sta=4976.3,4982.3
XS Rating Curve= 0 ,0
Exp/Cntr=0.3,0.1

Type RM Length L Ch R = 1 ,14196   ,405,405,405
BEGIN DESCRIPTION:
UNT 028 IN LACR 28.0
END DESCRIPTION:
XS GIS Cut Line= 3
      2186030.92      13195870.4      2186410.72     13195675.07
       2187092.8     13195371.93
#Sta/Elev= 30
  4303.8  436.09  4364.1  433.35  4391.9  430.92  4408.5   430.8  4436.3  428.42
  4492.7   426.4  4513.8  426.04  4547.6  423.02  4585.9  423.36  4602.5  422.21
    4660  421.35  4691.2  419.15  4764.7  417.96  4787.9  416.24    4845  414.97
  4847.7  414.47    4851  414.97  4880.8  415.79  4886.4  417.78  4909.7  420.18
  4979.3  422.01  5077.8  421.48  5088.9  420.97  5106.6  417.12  5121.6  416.72
  5176.3  420.93  5205.1  425.56  5257.1  428.28  5280.4  431.85  5477.3  440.77
#Mann= 4 ,-1 , 0
  4303.8     .08       0  4492.7     .05       0    4845     .03       0
    4851     .05       0
Bank Sta=4845,4851
XS Rating Curve= 0 ,0
Exp/Cntr=0.3,0.1

Type RM Length L Ch R = 1 ,13791   ,504,504,504
BEGIN DESCRIPTION:
UNT 028 IN LACR 27.0
END DESCRIPTION:
XS GIS Cut Line= 3
      2186226.23     13195946.35      2186920.71     13195794.43
       2187181.1     13195523.19
#Sta/Elev= 30
  4527.6     429  4539.4  428.05  4621.3  425.38  4709.7  420.76  4723.6  420.72
  4785.1  417.64  4810.8  416.03  4836.2  414.57  4920.3  411.49  4948.8  410.32
  4959.1   409.5    4967  407.97  4986.8   406.7  4989.5   406.2  4992.8   406.7
    5016  412.09  5051.8  413.94  5081.9  414.43  5102.4  416.22  5122.8  416.69
  5157.8  419.39  5194.5  419.72  5225.2  421.89  5238.5   421.9    5249  422.82
  5350.9  426.75  5475.1  431.76  5496.5  433.25  5545.8   435.1  5614.5  438.67
#Mann= 9 ,-1 , 0
  4527.6     .05       0  4709.7      .1       0  4785.1     .05       0
  4810.8      .1       0  4920.3     .12       0  4986.8     .07       0
  4992.8     .12       0  5051.8      .1       0  5350.9     .05       0
Bank Sta=4986.8,4992.8
XS Rating Curve= 0 ,0
Exp/Cntr=0.3,0.1

Type RM Length L Ch R = 1 ,13287   ,451,451,451
BEGIN DESCRIPTION:
UNT 028 IN LACR 26.0
END DESCRIPTION:
XS GIS Cut Line= 2
      2186106.93     13196391.22      2187267.89     13196250.17
#Sta/Elev= 30
  4314.2  430.49  4325.1  429.71  4405.7  427.68  4496.3  423.66  4559.7  422.21
  4607.1  420.48  4627.3  420.39  4636.4  419.41  4707.9  417.14    4810  414.88
  4838.8  413.21  4864.6  412.61    4901  410.92  4968.5  407.96  4979.9  408.64
  5007.1  406.62  5009.8  406.12  5013.1  406.62  5030.2  408.31  5050.2  408.87
  5100.7  411.73  5142.1  414.22  5151.1  415.22  5201.5   417.5  5231.7  418.11
  5282.1  420.17  5322.4  420.74  5357.6  422.67  5387.3   423.4  5483.7  428.03
#Mann= 6 ,-1 , 0
  4314.2      .1       0  4864.6     .12       0    4901      .1       0
  5007.1     .07       0  5013.1      .1       0  5357.6     .05       0
Bank Sta=5007.1,5013.1
XS Rating Curve= 0 ,0
Exp/Cntr=0.3,0.1

Type RM Length L Ch R = 1 ,12836   ,475,475,475
BEGIN DESCRIPTION:
UNT 028 IN LACR 25.0
END DESCRIPTION:
XS GIS Cut Line= 3
      2186437.73     13196746.85      2186837.72     13196696.85
      2187237.72     13196546.85
#Sta/Elev= 30
  4596.9  420.91  4639.7  418.89  4687.6  417.98  4768.2  414.93  4795.9  412.92
  4828.7  411.93  4858.9  409.06  4889.1  408.79  4939.5  406.06  4970.2  405.56
  4985.1  403.88  4986.9  403.57  4989.7  403.07  4992.9  403.57  5002.7  404.04
  5009.8  406.59  5015.1  407.13    5040  406.75  5085.4  408.13  5095.2  409.21
  5155.7  412.75  5216.3  414.95  5241.2  416.57  5266.1  417.04  5301.7  419.01
  5320.4  419.18  5326.6  419.96  5356.9  420.74  5395.4  422.74  5427.2  424.27
#Mann= 6 ,-1 , 0
  4596.9      .1       0  4970.2     .12       0  4985.1      .1       0
  4986.9     .07       0  4992.9      .1       0  5395.4     .05       0
Bank Sta=4986.9,4992.9
XS Rating Curve= 0 ,0
Exp/Cntr=0.3,0.1

Type RM Length L Ch R = 1 ,12361   ,491,491,491
BEGIN DESCRIPTION:
UNT 028 IN LACR 24.0
END DESCRIPTION:
XS GIS Cut Line= 2
      2186305.83     13197234.83      2187203.91     13197106.53
#Sta/Elev= 30
  4412.2     424  4464.6  422.93  4545.4  420.01  4577.7  419.69  4589.7  418.91
    4606  417.84  4636.3  417.19  4643.4  416.51  4648.4  416.68    4697  414.35
  4737.4  413.94  4757.6  412.41  4828.3  409.93  4907.3   406.1  4926.2  404.44
  4931.3  404.82  4959.6  402.95  4979.8  403.11    4999  401.91  5001.7  401.41
    5005  401.91  5010.1   402.9    5033  403.34  5050.5   403.9  5067.6  406.35
  5080.8  406.28  5138.3  409.31  5209.1  411.59  5232.3  411.27  5319.4  414.17
#Mann= 6 ,-1 , 0
  4412.2     .05       0  4589.7      .1       0  4907.3     .12       0
    4999     .07       0    5005     .12       0    5033      .1       0
Bank Sta=4999,5005
XS Rating Curve= 0 ,0
Exp/Cntr=0.3,0.1

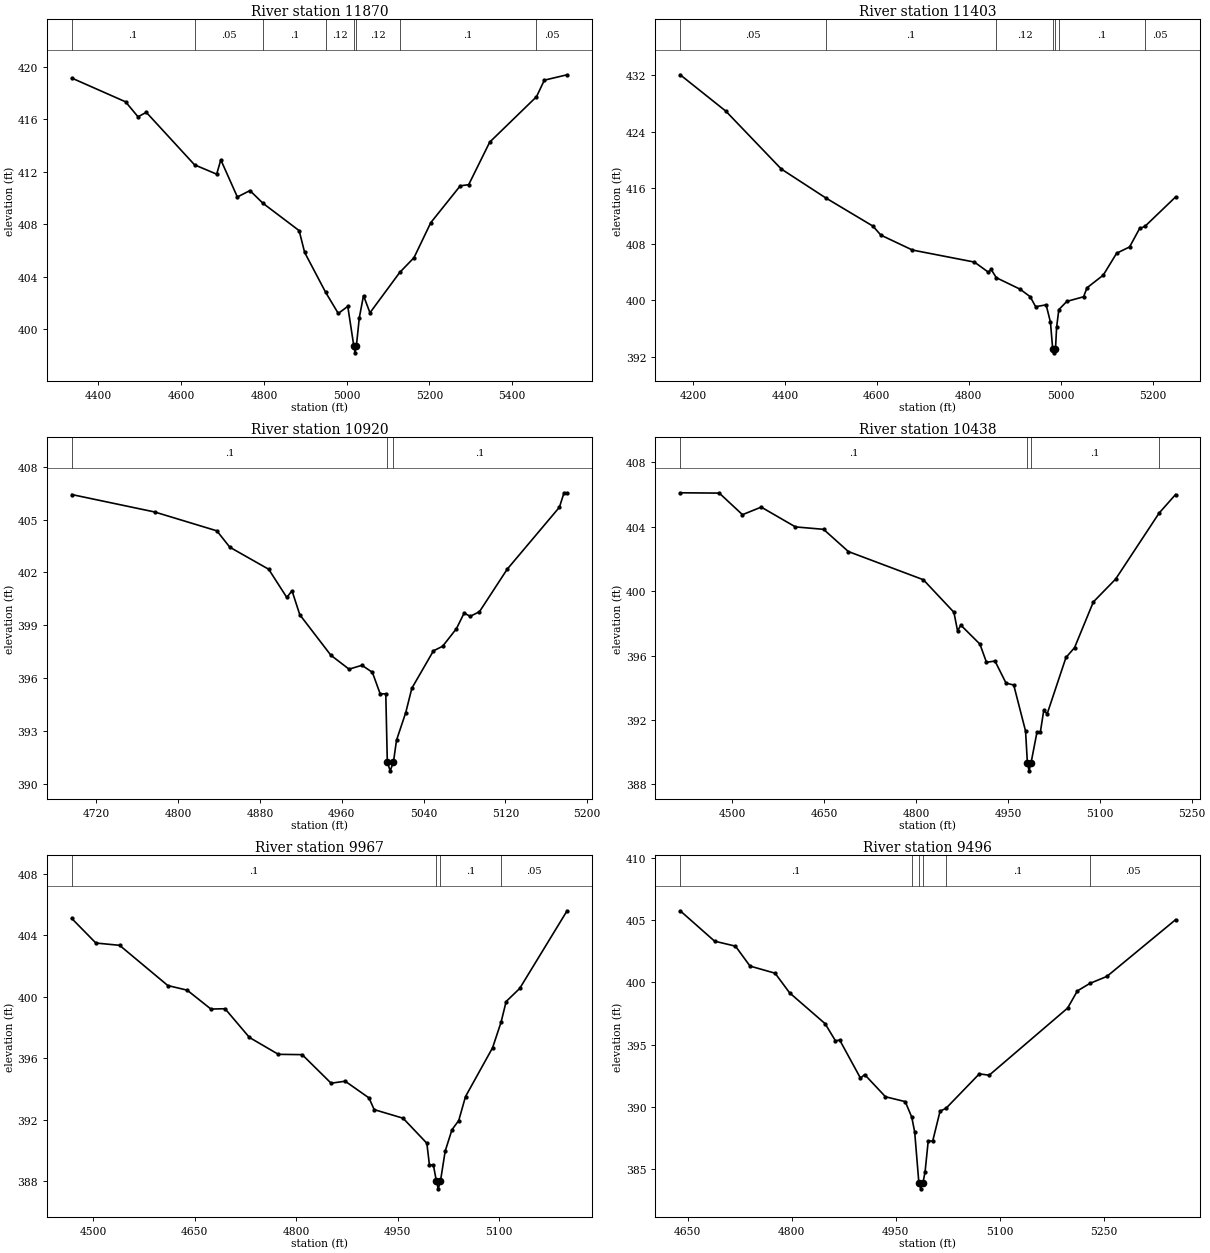
Type RM Length L Ch R = 1 ,11870   ,467,467,467
BEGIN DESCRIPTION:
UNT 028 IN LACR 23.0
END DESCRIPTION:
XS GIS Cut Line= 3
      2186227.61     13197692.84      2186635.33     13197687.26
      2187411.71     13197547.62
#Sta/Elev= 30
  4335.8  419.12  4465.9  417.31  4495.9  416.17  4515.9  416.51  4632.5  412.51
  4685.9   411.8  4695.9  412.89  4735.9  410.06  4766.3  410.55  4797.8  409.58
  4885.1   407.5  4898.4  405.84  4949.3  402.79  4979.7  401.19  5002.6  401.73
  5017.3  398.69  5020.1  398.19  5023.3  398.69  5030.5  400.87  5040.6  402.55
  5056.2  401.24    5128  404.31  5162.6  405.44  5203.2  408.11  5274.3  410.91
  5294.7     411  5345.5  414.24  5458.5   417.7  5477.5  418.96  5532.4  419.37
#Mann= 8 ,-1 , 0
  4335.8      .1       0  4632.5     .05       0  4797.8      .1       0
  4949.3     .12       0  5017.3     .07       0  5023.3     .12       0
    5128      .1       0  5458.5     .05       0
Bank Sta=5017.3,5023.3
XS Rating Curve= 0 ,0
Exp/Cntr=0.3,0.1

Type RM Length L Ch R = 1 ,11403   ,483,483,483
BEGIN DESCRIPTION:
UNT 028 IN LACR 22.0
END DESCRIPTION:
XS GIS Cut Line= 3
      2186337.76     13198346.83      2187087.72     13197996.85
      2187287.72     13197846.85
#Sta/Elev= 30
  4172.4  432.08  4271.7  426.91  4392.3  418.69    4489  414.58  4591.7  410.57
    4609  409.29  4677.6  407.17  4812.4  405.46  4843.1  404.01  4848.7  404.43
  4860.1  403.24  4911.7  401.61  4933.8  400.54  4945.6  399.12  4968.5  399.38
  4977.9  396.91  4982.8  393.06  4985.6  392.56  4988.8  393.06  4991.3  396.21
  4996.1   398.7  5013.5  399.87    5050  400.53  5057.3   401.8  5092.7   403.6
  5121.9  406.72    5150  407.61  5171.9  410.24  5183.2  410.52    5250  414.71
#Mann= 7 ,-1 , 0
  4172.4     .05       0    4489      .1       0  4860.1     .12       0
  4982.8     .07       0  4988.8     .12       0  4996.1      .1       0
  5183.2     .05       0
Bank Sta=4982.8,4988.8
XS Rating Curve= 0 ,0
Exp/Cntr=0.3,0.1

Type RM Length L Ch R = 1 ,10920   ,482,482,482
BEGIN DESCRIPTION:
UNT 028 IN LACR 21.0
END DESCRIPTION:
XS GIS Cut Line= 3
      2186987.76     13198446.85      2187287.72     13198396.86
      2187437.74     13198296.84
#Sta/Elev= 30
  4695.9  406.42    4777  405.43  4837.8  404.36  4850.5  403.43  4888.5  402.18
  4906.2  400.58  4911.3  400.96  4918.9   399.6  4949.3   397.3  4967.1  396.51
  4979.7  396.73  4989.9  396.33  4997.5  395.11    5003  395.11  5004.5  391.24
  5007.3  390.74  5010.5  391.24  5013.5  392.48  5022.5  394.04  5028.5  395.43
  5049.6  397.55  5058.6  397.81  5072.1  398.81  5079.6  399.69  5085.6  399.51
  5094.6  399.77  5121.7  402.18  5172.8   405.7  5177.3  406.52  5180.3  406.52
#Mann= 3 ,-1 , 0
  4695.9      .1       0  5004.5     .07       0  5010.5      .1       0
Bank Sta=5004.5,5010.5
XS Rating Curve= 0 ,0
Exp/Cntr=0.3,0.1

Type RM Length L Ch R = 1 ,10438   ,471,471,471
BEGIN DESCRIPTION:
UNT 028 IN LACR 20.0
END DESCRIPTION:
XS GIS Cut Line= 3
      2186937.75     13198596.87      2187487.72     13198796.85
      2187687.71     13198696.86
#Sta/Elev= 30
  4414.8  406.11  4478.6  406.09  4516.5  404.75  4547.1  405.22    4603  403.99
  4648.9  403.84  4689.4  402.46  4811.8  400.71  4861.7  398.69  4867.7  397.53
    4873  397.89  4904.2  396.71  4914.9  395.58  4928.8  395.66  4946.8  394.29
  4959.4  394.17  4978.7  391.31  4981.7  389.34  4984.5  388.84  4987.7  389.34
  4997.3  391.23  5002.8  391.23  5008.4  392.59    5014  392.38  5044.7  395.88
  5058.7  396.49  5089.4  399.33  5125.8  400.75  5196.8  404.85  5223.6     406
#Mann= 4 ,-1 , 0
  4414.8      .1       0  4981.7     .07       0  4987.7      .1       0
  5196.8     .05       0
Bank Sta=4981.7,4987.7
XS Rating Curve= 0 ,0
Exp/Cntr=0.3,0.1

Type RM Length L Ch R = 1 ,9967    ,471,471,471
BEGIN DESCRIPTION:
UNT 028 IN LACR 19.0
END DESCRIPTION:
XS GIS Cut Line= 3
      2187137.73     13199596.85      2187537.72     13199246.85
      2187737.72     13199246.85
#Sta/Elev= 30
  4468.5  405.11  4504.1  403.51  4539.2  403.36  4610.4  400.74  4638.9  400.44
    4674  399.21  4694.9  399.23  4730.9  397.36  4773.6  396.26  4808.8  396.24
  4851.5  394.38  4872.3  394.51  4907.5  393.42  4915.1  392.66  4957.8   392.1
  4992.9  390.47  4996.7  389.06  5002.5  389.06    5007     388  5009.7   387.5
    5013     388    5020  389.96    5030  391.35    5040  391.95    5050  393.51
    5090  396.69  5102.6  398.37    5110   399.7    5130  400.55    5200  405.61
#Mann= 4 ,-1 , 0
  4468.5      .1       0    5007     .07       0    5013      .1       0
  5102.6     .05       0
Bank Sta=5007,5013
XS Rating Curve= 0 ,0
Exp/Cntr=0.3,0.1

Type RM Length L Ch R = 1 ,9496    ,386,386,386
BEGIN DESCRIPTION:
UNT 028 IN LACR 18.0
END DESCRIPTION:
XS GIS Cut Line= 3
      2187287.68     13199896.88      2187587.72     13199696.86
      2187837.75     13199446.82
#Sta/Elev= 30
  4639.4  405.74    4689   403.3  4719.1   402.9  4740.1   401.3  4776.2  400.73
  4797.2  399.15  4848.3  396.68  4863.3   395.3  4869.3  395.37  4899.3  392.31
  4905.4  392.59  4935.4  390.81  4963.9  390.42  4973.3  389.17  4977.5  387.98
  4983.5  383.92  4986.2  383.42  4989.5  383.92  4992.5   384.8    4997  387.26
  5003.5  387.26  5014.1  389.66  5022.6  389.88  5070.7  392.65  5084.9  392.54
    5198  397.93  5212.1  399.31  5230.1  399.91  5254.6  400.47  5353.6  405.02
#Mann= 6 ,-1 , 0
  4639.4      .1       0  4973.3     .12       0  4983.5     .07       0
  4989.5     .12       0  5022.6      .1       0  5230.1     .05       0
Bank Sta=4983.5,4989.5
XS Rating Curve= 0 ,0
Exp/Cntr=0.3,0.1

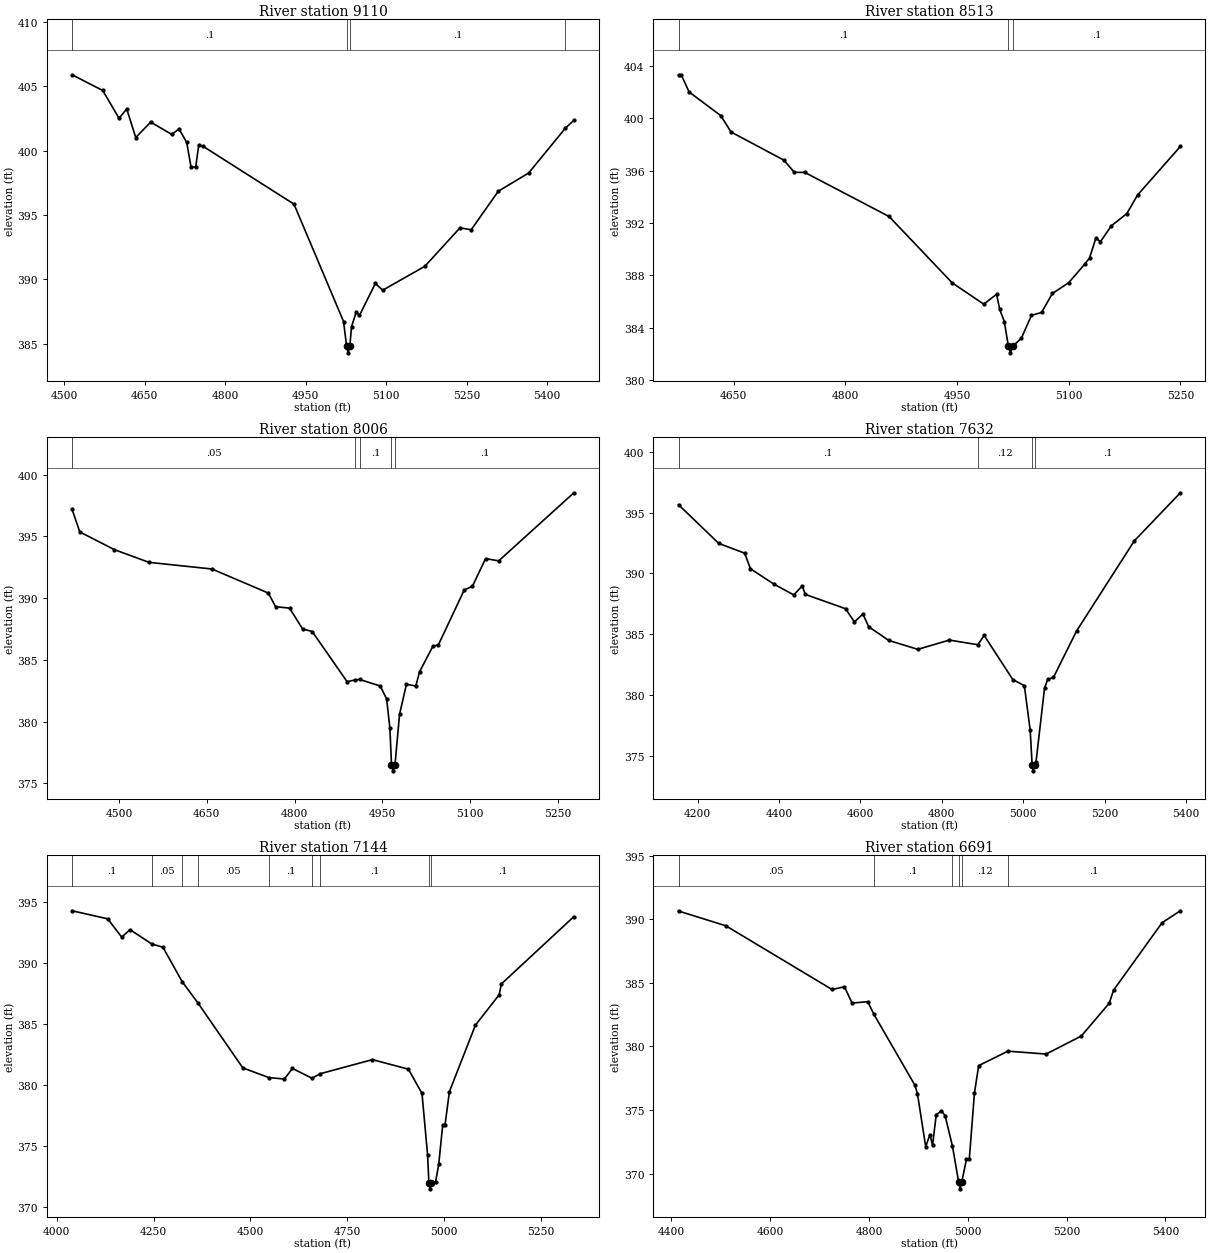
Type RM Length L Ch R = 1 ,9110    ,597,597,597
BEGIN DESCRIPTION:
UNT 028 IN LACR 17.0
END DESCRIPTION:
XS GIS Cut Line= 3
      2187389.34     13200206.32      2187713.32     13200044.33
      2188042.77     13199575.29
#Sta/Elev= 30
  4514.4  405.88  4571.6  404.66    4602   402.5  4616.3  403.23  4633.1  401.01
    4661  402.21  4700.2  401.25  4713.8  401.68  4728.1  400.63  4736.2  398.72
  4744.9  398.72  4750.5  400.42  4758.6  400.33  4928.1  395.84  5020.5  386.73
  5026.2   384.8    5029   384.3  5032.2   384.8  5035.3  386.33    5044  387.45
  5050.1   387.2  5079.8  389.69  5093.5  389.16  5172.1  391.02  5237.5     394
  5258.4  393.85  5308.9  396.84  5365.6  398.26  5433.9  401.73  5449.8  402.35
#Mann= 4 ,-1 , 0
  4514.4      .1       0  5026.2     .07       0  5032.2      .1       0
  5433.9     .05       0
Bank Sta=5026.2,5032.2
XS Rating Curve= 0 ,0
Exp/Cntr=0.3,0.1

Type RM Length L Ch R = 1 ,8513    ,507,507,507
BEGIN DESCRIPTION:
UNT 028 IN LACR 16.0
END DESCRIPTION:
XS GIS Cut Line= 3
       2188037.7     13200346.88      2188337.72     13200046.85
      2188487.72     13199846.85
#Sta/Elev= 30
  4575.7  403.31  4579.3  403.31  4589.9     402  4632.3   400.2  4646.4  398.94
  4717.2   396.8  4731.3  395.87  4745.4  395.86  4858.6   392.5  4943.4  387.44
  4985.9  385.81  5003.1  386.57  5007.3  385.41  5013.5  384.49  5018.9   382.6
  5021.6   382.1  5024.9   382.6  5036.5  383.23    5050  384.96  5063.5  385.18
  5078.1  386.63    5100  387.45  5121.9  388.89  5128.1  389.35  5136.5  390.85
  5142.7  390.58  5157.3  391.79  5178.1  392.72  5192.7  394.15    5250  397.84
#Mann= 3 ,-1 , 0
  4575.7      .1       0  5018.9     .07       0  5024.9      .1       0
Bank Sta=5018.9,5024.9
XS Rating Curve= 0 ,0
Exp/Cntr=0.3,0.1

Type RM Length L Ch R = 1 ,8006    ,374,374,374
BEGIN DESCRIPTION:
UNT 028 IN LACR 15.0
END DESCRIPTION:
XS GIS Cut Line= 3
      2188361.25     13200608.46      2188662.86     13200435.31
      2188897.44     13199982.89
#Sta/Elev= 30
  4419.8  397.19    4433  395.36    4492  393.93    4551   392.9  4658.8  392.36
  4755.2  390.41  4767.5  389.31  4791.5  389.19  4813.6  387.51  4830.1   387.3
  4889.7  383.24  4902.7  383.37    4911  383.42  4946.4  382.89  4957.3  381.83
  4962.9  379.46  4965.6  376.52  4968.4  376.02  4971.6  376.52  4979.4  380.61
  4991.1  383.02  5007.1  382.89  5013.7  384.06  5036.2  386.09  5045.8  386.23
    5090  390.67  5103.8  390.95  5126.3   393.2  5148.8  393.02  5277.2  398.53
#Mann= 5 ,-1 , 0
  4419.8     .05       0  4902.7     .12       0    4911      .1       0
  4965.6     .07       0  4971.6      .1       0
Bank Sta=4965.6,4971.6
XS Rating Curve= 0 ,0
Exp/Cntr=0.3,0.1

Type RM Length L Ch R = 1 ,7632    ,488,488,488
BEGIN DESCRIPTION:
UNT 028 IN LACR 14.0
END DESCRIPTION:
XS GIS Cut Line= 3
       2188389.2     13201077.62      2188841.59     13200686.66
      2189253.32      13200202.6
#Sta/Elev= 30
  4152.9  395.65  4251.8  392.47  4315.4  391.67  4329.7  390.39  4386.7  389.14
  4436.1  388.24  4456.9  388.98  4464.6  388.28  4563.3  387.11  4585.2  386.02
  4606.1  386.67  4620.3  385.63  4669.7   384.5    4741  383.77  4818.5  384.53
  4888.6  384.15  4904.2  384.91  4974.5  381.29    5003  380.78  5017.3  377.11
    5022  374.29  5024.8  373.79    5028  374.29  5031.6  374.52  5052.5  380.57
  5060.2   381.3  5074.4  381.46  5131.3  385.28  5273.2  392.68  5386.3  396.63
#Mann= 4 ,-1 , 0
  4152.9      .1       0  4888.6     .12       0    5022     .07       0
    5028      .1       0
Bank Sta=5022,5028
XS Rating Curve= 0 ,0
Exp/Cntr=0.3,0.1

Type RM Length L Ch R = 1 ,7144    ,453,453,453
BEGIN DESCRIPTION:
UNT 028 IN LACR 13.0
END DESCRIPTION:
XS GIS Cut Line= 3
       2188787.7     13201496.88      2189387.72     13200746.85
      2189537.72     13200446.86
#Sta/Elev= 30
  4039.5  394.28  4131.6  393.62  4167.6  392.12  4189.2  392.73  4245.8  391.55
    4274   391.3    4324  388.46    4364  386.75  4480.5   381.4  4547.7  380.61
  4587.8  380.49  4608.6  381.36  4658.8  380.56    4681  380.93  4815.1  382.08
    4908   381.3  4943.2  379.31  4957.6  374.28    4961  371.99  4963.7  371.49
    4967  371.99  4978.4  372.08  4986.4  373.49  4996.8  376.75  5002.8  376.75
    5014  379.46  5081.1   384.9  5142.5   387.4  5148.1  388.28  5335.4   393.8
#Mann= 9 ,-1 , 0
  4039.5      .1       0  4245.8     .05       0    4324      .1       0
    4364     .05       0  4547.7      .1       0  4658.8     .05       0
    4681      .1       0    4961     .07       0    4967      .1       0
Bank Sta=4961,4967
XS Rating Curve= 0 ,0
Exp/Cntr=0.3,0.1

Type RM Length L Ch R = 1 ,6691    ,568,568,568
BEGIN DESCRIPTION:
UNT 028 IN LACR 12.0
END DESCRIPTION:
XS GIS Cut Line= 3
      2189437.73     13201646.82      2189637.72     13201096.85
      2189887.71     13200746.87
#Sta/Elev= 30
  4414.8  390.65  4510.5  389.49  4725.3  384.48  4750.6  384.69  4765.9  383.41
  4797.8  383.52  4809.9  382.54  4892.9  376.96  4898.2  376.29  4914.9  372.11
  4923.5  373.07  4928.8  372.23  4936.2  374.63  4946.8  374.93  4954.1  374.56
  4969.1  372.15  4981.7   369.3  4984.5   368.8  4987.7   369.3  4997.3  371.12
  5003.1  371.12  5013.5  376.33  5022.1  378.49  5081.3  379.63  5158.5   379.4
  5229.8  380.82  5286.3   383.4  5294.9  384.42  5393.2  389.73  5430.1  390.67
#Mann= 6 ,-1 , 0
  4414.8     .05       0  4809.9      .1       0  4969.1     .12       0
  4981.7     .07       0  4987.7     .12       0  5081.3      .1       0
Bank Sta=4981.7,4987.7
XS Rating Curve= 0 ,0
Exp/Cntr=0.3,0.1