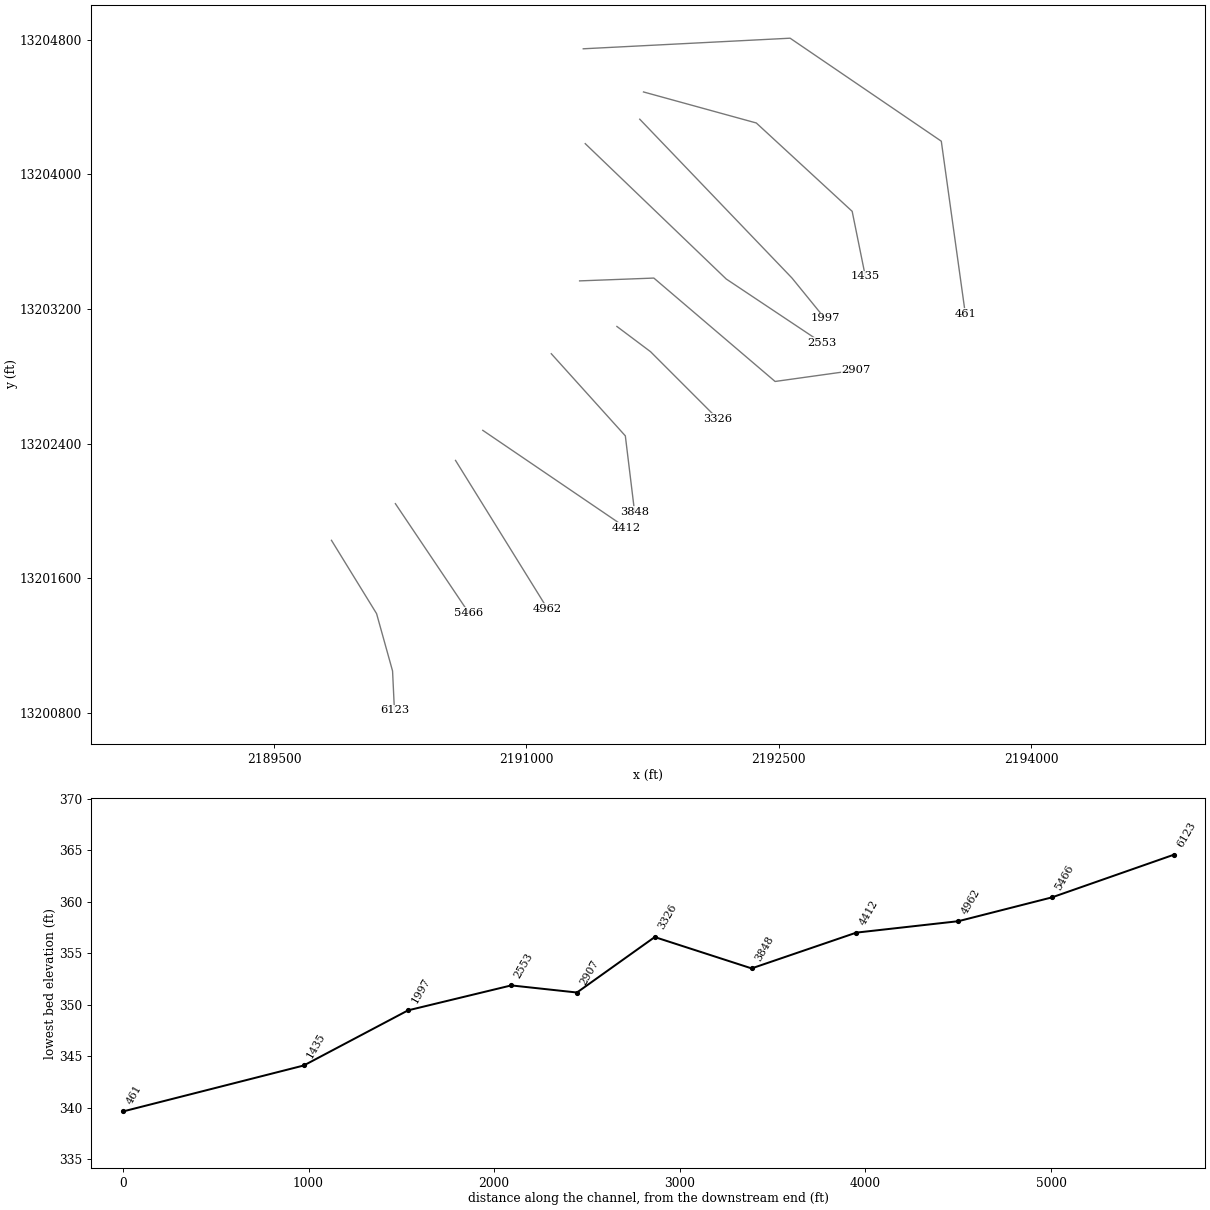
HEC-RAS study UNT 028 IN LACR.prj: UNT 028 IN LACR Base Level Engineering

--- UNT 028 IN LACR.g01 (geometry) --- (continued)

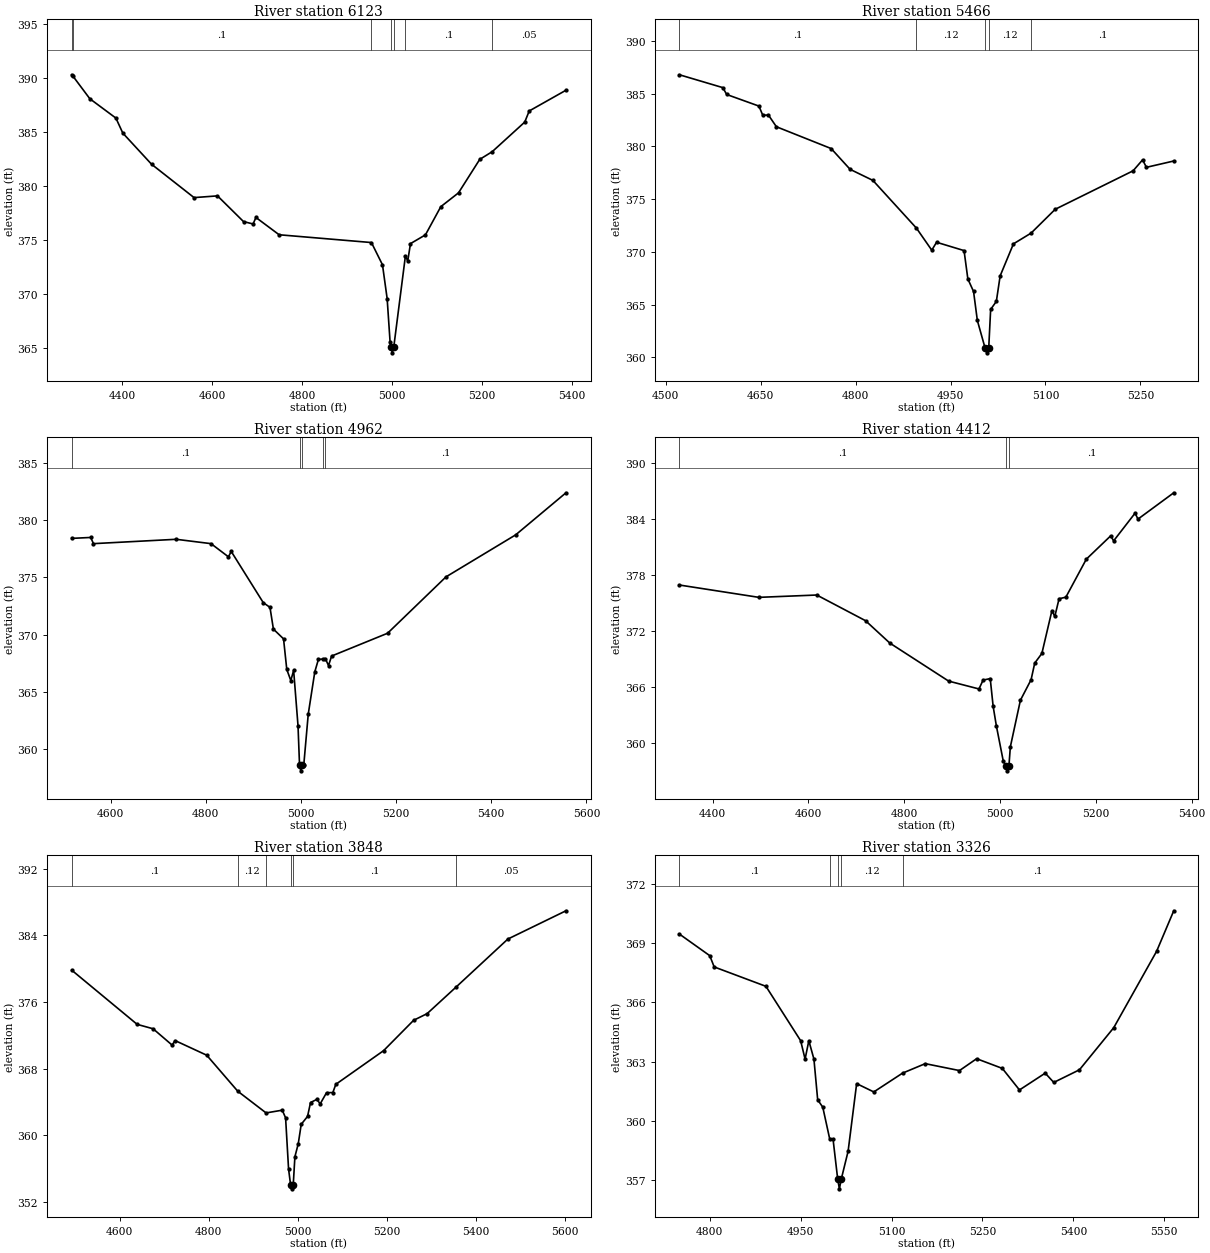
Type RM Length L Ch R = 1 ,6123    ,657,657,657
BEGIN DESCRIPTION:
UNT 028 IN LACR 10.0
END DESCRIPTION:
XS GIS Cut Line= 4
       2189841.4     13201826.09       2190109.5     13201390.43
      2190204.45     13201049.72      2190215.62     13200815.13
#Sta/Elev= 30
  4287.5   390.3  4289.8   390.2  4327.9  388.08  4385.9  386.29  4401.3   384.9
  4465.2  382.02  4559.8  378.93    4612  379.09  4669.9  376.71  4691.2  376.49
  4697.6  377.09  4749.2  375.49  4954.6  374.77  4979.2  372.71  4989.6  369.58
  4996.1  365.58  4998.2  365.06    5001  364.56  5004.2  365.06  5030.3  373.55
  5035.4  373.06  5041.5  374.67  5074.8  375.48    5109  378.09  5148.4  379.37
  5195.7  382.47  5223.4  383.18  5295.8  385.92  5305.8  386.95  5387.6  388.87
#Mann= 7 ,-1 , 0
  4287.5     .05       0  4289.8      .1       0  4954.6     .12       0
  4998.2     .07       0  5004.2     .12       0  5030.3      .1       0
  5223.4     .05       0
Bank Sta=4998.2,5004.2
XS Rating Curve= 0 ,0
Exp/Cntr=0.3,0.1

Type RM Length L Ch R = 1 ,5466    ,504,504,504
BEGIN DESCRIPTION:
UNT 028 IN LACR 9.0
END DESCRIPTION:
XS GIS Cut Line= 2
      2190221.23     13202043.89      2190656.86     13201396.04
#Sta/Elev= 30
  4521.9   386.8  4590.4  385.58  4596.5  384.93  4647.4  383.83  4653.5  382.96
  4662.4  382.98    4675  381.87  4761.5   379.8  4791.4  377.83  4827.4  376.78
  4896.2  372.25  4920.4  370.16    4928  370.91  4971.4  370.12  4977.4  367.43
  4986.4  366.24  4992.4  363.49  5004.4  360.92  5007.2  360.42  5010.4  360.92
  5013.4  364.54  5022.4   365.3  5028.4  367.72  5049.4  370.76  5077.3  371.78
  5115.4  374.04  5238.4  377.69  5253.4  378.73  5259.4  378.02  5302.6  378.62
#Mann= 5 ,-1 , 0
  4521.9      .1       0  4896.2     .12       0  5004.4     .07       0
  5010.4     .12       0  5077.3      .1       0
Bank Sta=5004.4,5010.4
XS Rating Curve= 0 ,0
Exp/Cntr=0.3,0.1

Type RM Length L Ch R = 1 ,4962    ,550,550,550
BEGIN DESCRIPTION:
UNT 028 IN LACR 8.0
END DESCRIPTION:
XS GIS Cut Line= 2
      2190578.65      13202300.9      2191126.04     13201418.38
#Sta/Elev= 30
  4518.4   378.4  4558.3  378.48  4564.2  377.94  4737.8  378.32  4811.1  377.94
  4847.7  376.79  4853.6  377.26  4920.9  372.79    4935  372.38  4942.2  370.48
  4963.5  369.63  4970.3  366.96  4978.8  365.99  4984.7  366.88  4993.9  362.05
  4997.1  358.61  4999.8  358.11  5003.1  358.61    5006  358.62  5015.4  363.06
  5029.2  366.76  5036.7  367.83  5046.4  367.87  5051.4   367.9    5058   367.3
  5064.5  368.13  5182.1  370.12  5304.8  375.04  5451.3  378.71  5556.9  382.38
#Mann= 5 ,-1 , 0
  4518.4      .1       0  4997.1     .07       0  5003.1      .1       0
  5046.4     .12       0  5051.4      .1       0
Bank Sta=4997.1,5003.1
XS Rating Curve= 0 ,0
Exp/Cntr=0.3,0.1

Type RM Length L Ch R = 1 ,4412    ,564,564,564
BEGIN DESCRIPTION:
UNT 028 IN LACR 7.0
END DESCRIPTION:
XS GIS Cut Line= 2
      2190740.67     13202479.59        2191594.     13201899.55
#Sta/Elev= 30
  4330.7   376.9  4496.4  375.58  4617.3  375.83  4719.1  373.08  4769.9  370.68
  4892.6  366.61  4955.9  365.77  4964.5  366.72  4979.4  366.88  4985.5  363.91
  4992.2  361.82  5006.5  358.08  5012.4   357.5  5015.1     357  5018.4   357.5
  5021.4  359.57  5042.4  364.56  5064.7  366.76  5072.3  368.54  5087.2  369.57
  5108.2  374.16  5114.2  373.53  5123.1  375.43  5137.3   375.6    5180  379.67
  5230.9  382.17    5237  381.63  5281.8   384.6  5287.8  383.96  5362.5  386.78
#Mann= 3 ,-1 , 0
  4330.7      .1       0  5012.4     .07       0  5018.4      .1       0
Bank Sta=5012.4,5018.4
XS Rating Curve= 0 ,0
Exp/Cntr=0.3,0.1

Type RM Length L Ch R = 1 ,3848    ,522,522,522
BEGIN DESCRIPTION:
UNT 028 IN LACR 6.0
END DESCRIPTION:
XS GIS Cut Line= 3
      2191147.72     13202934.78      2191587.72     13202446.85
      2191642.48      13201997.3
#Sta/Elev= 30
  4492.3  379.83  4639.3  373.31  4675.1  372.78  4717.7  370.82  4724.5  371.36
  4795.5   369.6  4865.2  365.27  4928.8  362.66  4965.1  362.99  4972.6  362.07
  4979.3   355.9  4983.8  354.03  4986.5  353.53  4989.8  354.03  4993.5  357.39
    5001  358.94  5007.7  361.29  5021.9  362.24  5028.6  363.91  5042.8  364.29
  5050.3  363.75  5064.5  365.09  5078.7  365.11  5085.4   366.1  5192.7  370.15
  5260.1   373.8  5290.4   374.6  5355.9  377.82  5471.7  383.57  5602.2  386.97
#Mann= 6 ,-1 , 0
  4492.3      .1       0  4865.2     .12       0  4928.8      .1       0
  4983.8     .07       0  4989.8      .1       0  5355.9     .05       0
Bank Sta=4983.8,4989.8
XS Rating Curve= 0 ,0
Exp/Cntr=0.3,0.1

Type RM Length L Ch R = 1 ,3326    ,419,419,419
BEGIN DESCRIPTION:
UNT 028 IN LACR 5.0
END DESCRIPTION:
XS GIS Cut Line= 3
      2191537.72     13203096.85      2191737.72     13202946.85
      2192137.73     13202546.84
#Sta/Elev= 30
    4750  369.45    4800  368.36  4807.3  367.79  4892.7  366.81    4950  364.06
  4957.3  363.13  4963.5  364.06  4971.9  363.13  4978.1  361.07  4986.5   360.7
  4998.1  359.07  5003.5  359.07  5011.1  357.07  5013.9  356.57  5017.1  357.07
  5028.3  358.47  5042.4  361.89  5070.7  361.47  5118.1  362.42  5155.6   362.9
  5212.1  362.55  5240.4  363.15  5282.8  362.66  5311.1  361.57  5353.6  362.42
  5367.7  361.95  5410.1  362.59  5466.7  364.72  5537.4  368.58  5565.7  370.63
#Mann= 5 ,-1 , 0
    4750      .1       0  4998.1     .12       0  5011.1     .07       0
  5017.1     .12       0  5118.1      .1       0
Bank Sta=5011.1,5017.1
XS Rating Curve= 0 ,0
Exp/Cntr=0.3,0.1

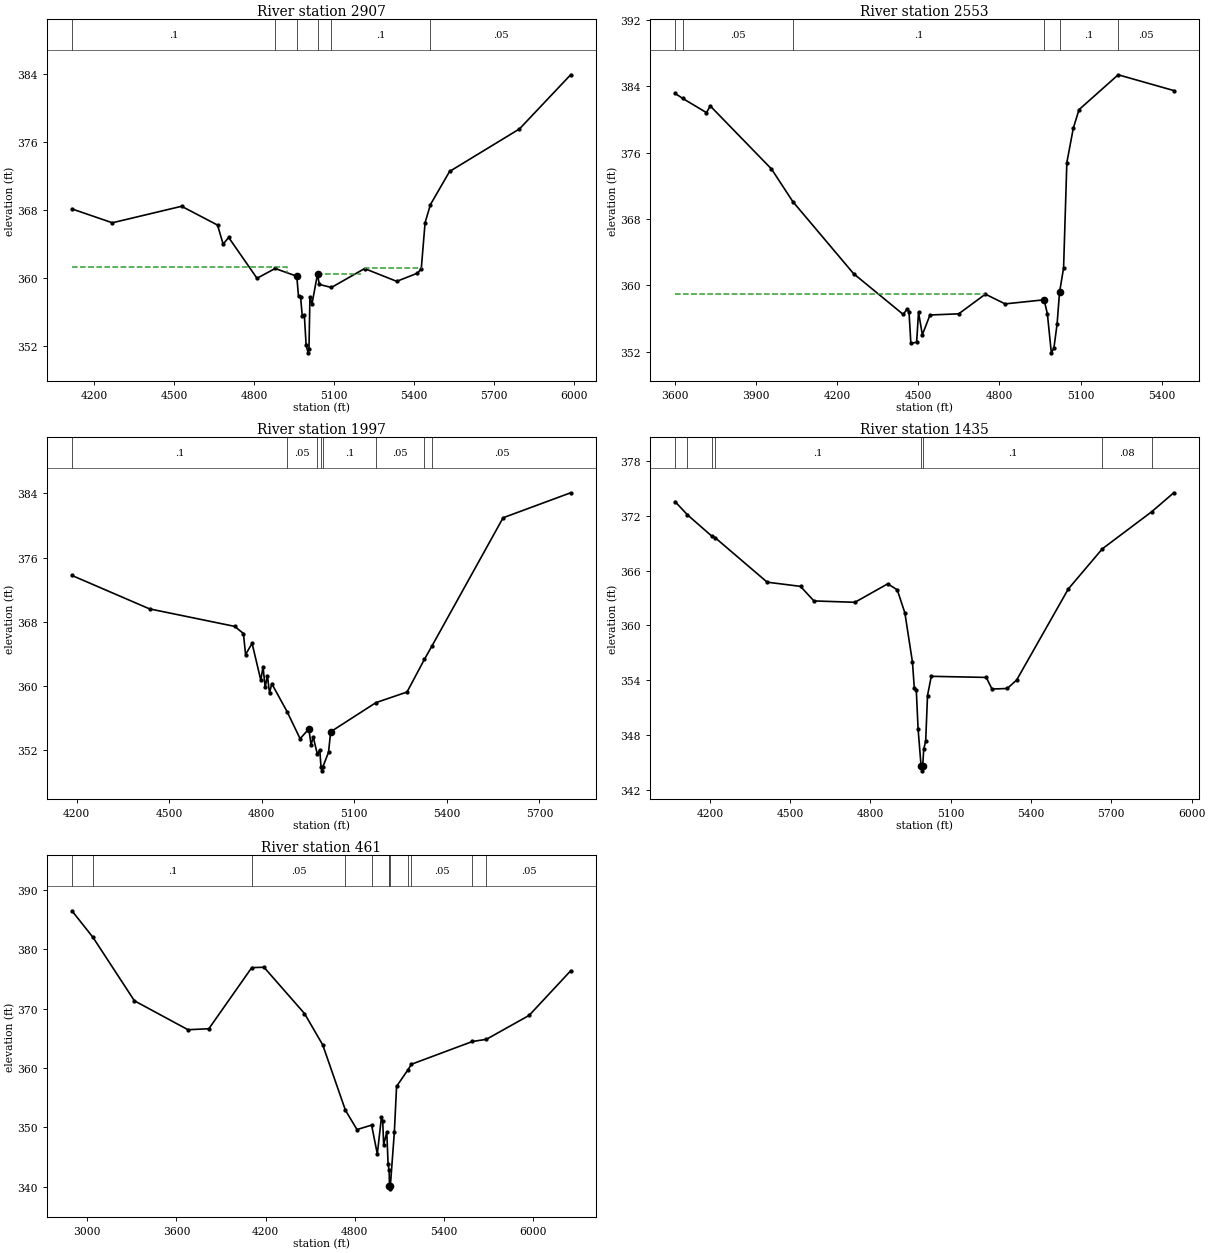
Type RM Length L Ch R = 1 ,2907    ,354,354,354
BEGIN DESCRIPTION:
UNT 028 IN LACR 4.0
END DESCRIPTION:
XS GIS Cut Line= 4
      2191315.97     13203367.69      2191757.21     13203384.45
      2192477.74     13202770.05      2192958.11     13202837.07
#Sta/Elev= 30
  4115.2   368.1  4267.1  366.47  4527.2  368.41  4662.3   366.2  4683.2  363.96
    4704  364.75  4810.5  359.95  4878.6   361.1  4959.9  360.19  4966.4  357.82
  4974.1  357.75  4980.7  355.47  4988.4  355.58    4995   352.1  5002.4  351.19
  5005.7  351.69  5009.3  357.73    5017  356.93  5037.8  360.45  5044.4  359.23
    5090  358.87  5214.6  361.09  5335.4  359.59  5413.3  360.55  5427.6  361.07
  5441.9  366.49    5462  368.61  5533.9   372.5  5796.5   377.5  5988.7  383.86
#Mann= 6 ,-1 , 0
  4115.2      .1       0  4878.6     .12       0  4959.9     .07       0
  5037.8     .12       0    5090      .1       0    5462     .05       0
#XS Ineff= 3 ,-1
  4115.2  4924.7  361.28  5038.2    5200  360.44  5214.6 5431.09   361.2
Permanent Ineff=
       T       T       T
Bank Sta=4959.9,5037.8
XS Rating Curve= 0 ,0
Exp/Cntr=0.3,0.1

Type RM Length L Ch R = 1 ,2553    ,556,556,556
BEGIN DESCRIPTION:
UNT 028 IN LACR 3.0
END DESCRIPTION:
XS GIS Cut Line= 3
      2191349.49     13204183.15       2192187.3     13203378.86
      2192757.02     13202999.05
#Sta/Elev= 30
  3598.9  383.15  3627.4  382.54  3715.3  380.83  3729.4  381.63  3955.9  374.04
  4034.9  370.11    4260  361.42  4443.6  356.51  4457.8  357.15    4465  356.85
  4471.9  353.02  4493.3  353.16  4500.2  356.78  4514.4  354.06  4542.7  356.44
    4649  356.58  4747.7  358.95  4820.9  357.78  4965.1  358.27  4977.2  356.58
  4991.9  351.88  5001.2  352.42  5013.2  355.35  5022.2  359.16  5037.2  362.11
  5049.3  374.81  5073.3  378.97  5094.4  381.19  5239.3  385.39    5445  383.49
#Mann= 6 ,-1 , 0
  3598.9      .1       0  3627.4     .05       0  4034.9      .1       0
  4965.1     .07       0  5022.2      .1       0  5239.3     .05       0
#XS Ineff= 2 , 0
       0 4747.67  358.97               0
Permanent Ineff=
       T       F
Bank Sta=4965.1,5022.2
XS Rating Curve= 0 ,0
Exp/Cntr=0.3,0.1

Type RM Length L Ch R = 1 ,1997    ,562,562,562
BEGIN DESCRIPTION:
UNT 028 IN LACR 2.0
END DESCRIPTION:
XS GIS Cut Line= 3
      2191673.47     13204328.36      2192578.28     13203384.45
      2192773.25     13203144.91
#Sta/Elev= 30
  4184.6  373.78  4436.1  369.62  4712.2  367.44  4740.5  366.55  4747.4  363.93
  4768.5  365.33  4796.8  360.75    4804  362.41  4810.9  359.87  4818.2  361.29
  4825.1  359.14  4832.3  360.31  4881.8  356.84  4924.2  353.46  4952.5  354.68
  4959.7  352.69  4966.6  353.68  4979.8  351.58    4988  352.02  4991.9  349.96
  4994.7  349.46  4997.9  349.96  5016.3  351.77  5023.2  354.32  5169.9  357.95
  5270.7  359.27  5327.1  363.34  5352.2  365.05  5582.1  380.96    5801  384.07
#Mann= 8 ,-1 , 0
  4184.6      .1       0  4881.8     .05       0  4979.8      .1       0
  4991.9     .07       0  4997.9      .1       0  5169.9     .05       0
  5327.1      .1       0  5352.2     .05       0
Bank Sta=4952.5,5023.2
XS Rating Curve= 0 ,0
Exp/Cntr=0.3,0.1

Type RM Length L Ch R = 1 ,1435    ,974,974,974
BEGIN DESCRIPTION:
Mapping XS 800acb08
END DESCRIPTION:
XS GIS Cut Line= 4
      2191695.73     13204490.39      2192366.03     13204306.05
      2192935.75     13203781.02      2193013.95     13203395.61
#Sta/Elev= 30
  4069.9  373.54  4116.4  372.09  4207.8  369.75    4219  369.61  4414.2  364.73
  4538.7  364.27  4588.8  362.68  4742.1  362.53  4864.6  364.55  4900.3  363.89
  4928.7  361.36    4957  355.98  4963.8  353.17  4971.2  352.97    4978   348.7
  4989.2  344.61  4991.9  344.11  4995.2  344.61    4999  346.48  5006.4  347.36
  5013.2  352.34  5027.3  354.44  5232.6  354.32  5254.2  353.05  5310.9  353.11
  5346.1  354.03  5539.2  363.99  5666.1  368.37  5850.8  372.43  5933.1   374.5
#Mann= 8 ,-1 , 0
  4069.9     .08       0  4116.4      .1       0  4207.8     .08       0
    4219      .1       0  4989.2     .07       0  4995.2      .1       0
  5666.1     .08       0  5850.8     .05       0
Bank Sta=4989.2,4995.2
XS Rating Curve= 0 ,0
Exp/Cntr=0.3,0.1

Type RM Length L Ch R = 1 ,461     ,0,0,0
BEGIN DESCRIPTION:
UNT 028 IN LACR 1.0
END DESCRIPTION:
XS GIS Cut Line= 4
      2191337.75     13204746.86      2192566.96     13204809.81
       2193465.4     13204197.83      2193608.44     13203170.53
#Sta/Elev= 30
  2897.1  386.47  3038.6     382  3317.6  371.31  3678.1  366.44  3818.3  366.61
  4106.9   376.9  4189.3  376.96  4461.7  369.17  4584.3  363.89    4737  352.89
  4814.8  349.63  4913.2  350.38  4951.6  345.52  4979.4   351.7  4987.9  351.02
  4994.3  347.08  5015.3  349.18  5024.2  343.76  5031.2  342.74  5033.3  340.15
    5036  339.65  5039.3  340.15  5066.1  349.14  5081.1   356.9  5155.7  359.62
  5181.4  360.63  5591.4  364.46  5684.8  364.82  5973.2  368.86  6252.2  376.36
#Mann= 12 ,-1 , 0
  2897.1     .08       0  3038.6      .1       0  4106.9     .05       0
    4737      .1       0  4913.2     .12       0  5031.2      .1       0
  5033.3     .07       0  5039.3      .1       0  5155.7     .08       0
  5181.4     .05       0  5591.4      .1       0  5684.8     .05       0
Bank Sta=5033.3,5039.3
XS Rating Curve= 0 ,0
Exp/Cntr=0.3,0.1

Chan Stop Cuts=-1
Use User Specified Reach Order=0
Composite Channel Slope=5