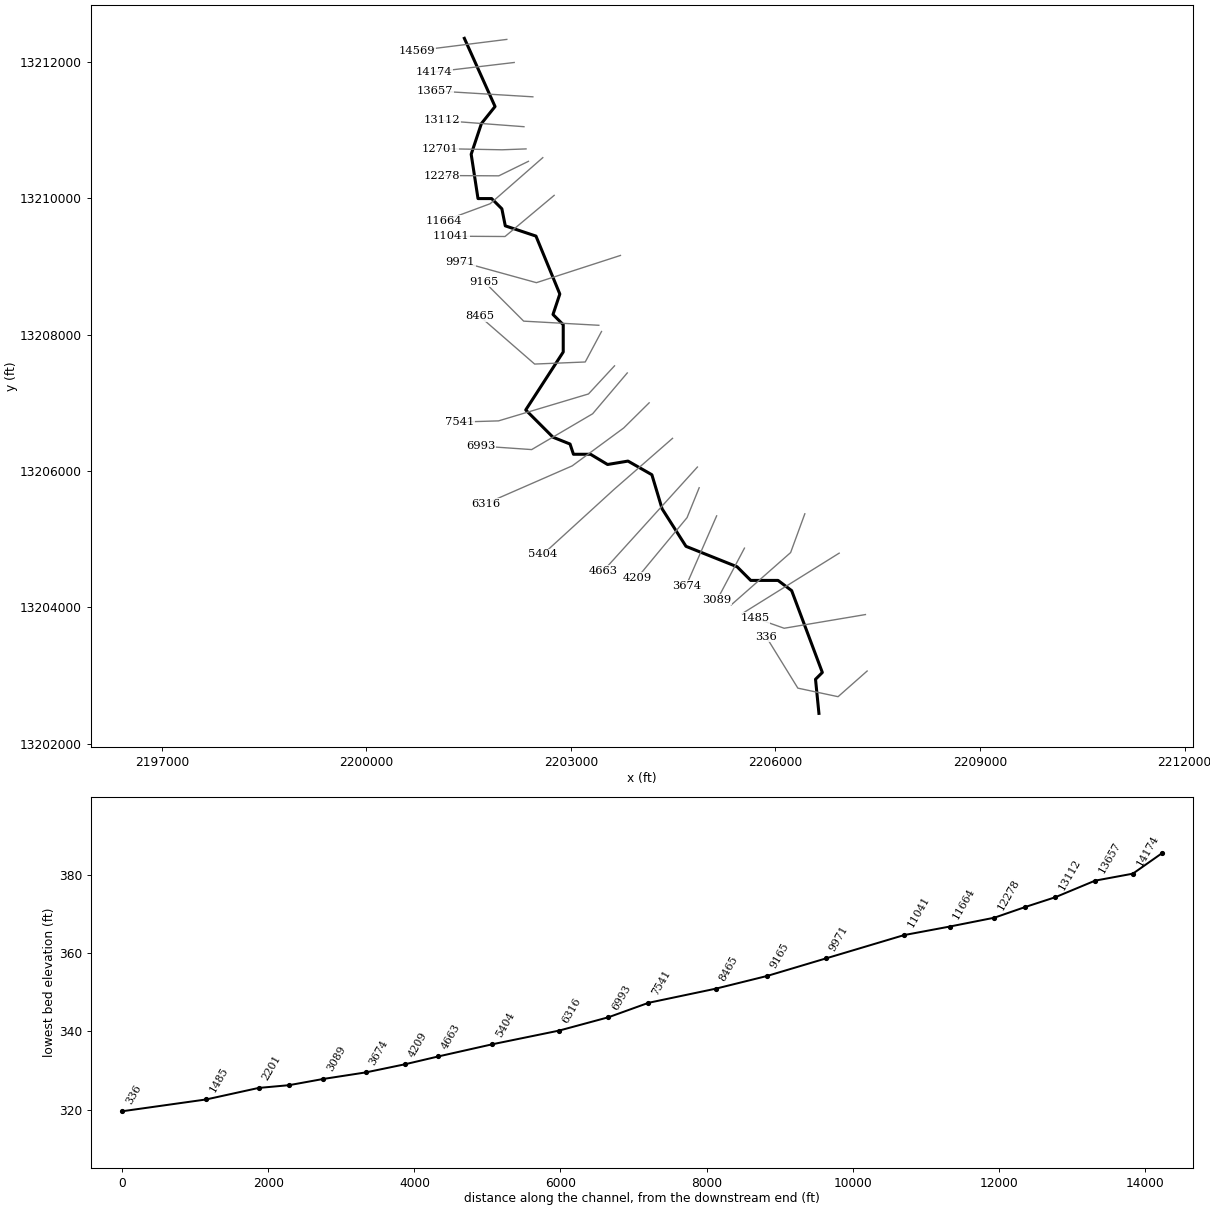
--- UNT 029 IN LACR.prj (project) ---

Proj Title=UNT 029 IN LACR Base Level Engineering
Current Plan=p01
Default Exp/Contr=0.3,0.1
English Units
Geom File=g01
Flow File=f01
Plan File=p01
Y Axis Title=Elevation
X Axis Title(PF)=Main Channel Distance
X Axis Title(XS)=Station
BEGIN DESCRIPTION:
UNT 029 IN LACR
END DESCRIPTION:
DSS Export Rating Curves= 0
DSS Export Rating Curve Sorted= 0
DSS Export Volume Flow Curves= 0
DXF OffsetX= 0
DXF OffsetY= 0
DXF ScaleX= 1
DXF ScaleY= 10

--- UNT 029 IN LACR.p01 (plan) ---

Plan Title=Multiple Run
Short Identifier=Multiple
Geom File=g01
Flow File=f01
Subcritical Flow
K Sum by GR= 0
Std Step Tol= 0.01
Critical Tol= 0.01
Num of Std Step Trials= 20
Max Error Tol= 0.3
Flow Tol Ratio= 0.001
Split Flow NTrial= 30
Split Flow Tol= 0.02
Split Flow Ratio= 0.02
Log Output Level= 0
Friction Slope Method= 1
Unsteady Friction Slope Method= 2
Unsteady Bridges Friction Slope Method= 1
Parabolic Critical Depth
Global Vel Dist=  1 , 1 , 1
Global Log Level= 0
CheckData=True
Encroach Param= -1, 0, 0, 0
BEGIN DESCRIPTION:
Multiple Run
END DESCRIPTION:

--- UNT 029 IN LACR.f01 (steady flow) ---

Flow Title=Multiple
Program Version=4.10
Number of Profiles= 7
Profile Names=10-year,25-year,50-year,1pct_min,100-year,1pct_plu,500-year
River Rch & RM=UNT 029 IN LACR,Reach-1         ,14569
     184     253     309     279     377     510     569
River Rch & RM=UNT 029 IN LACR,Reach-1         ,13657
     223     309     380     344     465     629     708
River Rch & RM=UNT 029 IN LACR,Reach-1         ,7541
     330     466     581     532     719     973    1121
River Rch & RM=UNT 029 IN LACR,Reach-1         ,5404
     416     594     745     686     928    1255    1465
River Rch & RM=UNT 029 IN LACR,Reach-1         ,3674
     416     594     745     686     928    1255    1465
River Rch & RM=UNT 029 IN LACR,Reach-1         ,2619
     558     808    1022     950    1284    1737    2061
River Rch & RM=UNT 029 IN LACR,Reach-1         ,2201
     558     808    1022     950    1284    1737    2061
Boundary for River Rch & Prof#=UNT 029 IN LACR,Reach-1         , 1
Up Type= 0
Dn Type= 3
Dn Slope=0.005
Boundary for River Rch & Prof#=UNT 029 IN LACR,Reach-1         , 2
Up Type= 0
Dn Type= 3
Dn Slope=0.005
Boundary for River Rch & Prof#=UNT 029 IN LACR,Reach-1         , 3
Up Type= 0
Dn Type= 3
Dn Slope=0.005
Boundary for River Rch & Prof#=UNT 029 IN LACR,Reach-1         , 4
Up Type= 0
Dn Type= 3
Dn Slope=0.005
Boundary for River Rch & Prof#=UNT 029 IN LACR,Reach-1         , 5
Up Type= 0
Dn Type= 3
Dn Slope=0.005
Boundary for River Rch & Prof#=UNT 029 IN LACR,Reach-1         , 6
Up Type= 0
Dn Type= 3
Dn Slope=0.005
Boundary for River Rch & Prof#=UNT 029 IN LACR,Reach-1         , 7
Up Type= 0
Dn Type= 3
Dn Slope=0.005
DSS Import GetInterval= 0
DSS Import GetPeak= 0
DSS Import FillOption= 0

--- UNT 029 IN LACR.g01 (geometry) ---

Geom Title=Existing Conditions
Program Version=4.10

River Reach=UNT 029 IN LACR ,Reach-1
Reach XY= 30
      2201437.72     13212346.86      2201887.72     13211346.86
      2201687.72     13211096.85      2201537.72     13210646.85
      2201637.72     13209996.85      2201837.72     13209996.85
      2201987.72     13209846.85      2202037.72     13209596.85
      2202487.72     13209446.85      2202837.72     13208596.85
      2202737.72     13208296.85      2202887.72     13208146.85
      2202887.72     13207746.86      2202337.72     13206896.86
      2202737.72     13206496.85      2202987.72     13206396.85
      2203037.72     13206246.86      2203287.72     13206246.86
      2203537.72     13206096.86      2203837.72     13206146.85
      2204187.72     13205946.86      2204337.72     13205446.86
      2204687.72     13204896.85      2205437.72     13204596.85
      2205637.72     13204396.85      2206037.72     13204396.85
      2206237.72     13204246.85      2206687.72     13203046.85
      2206587.72     13202946.85      2206637.72     13202446.85

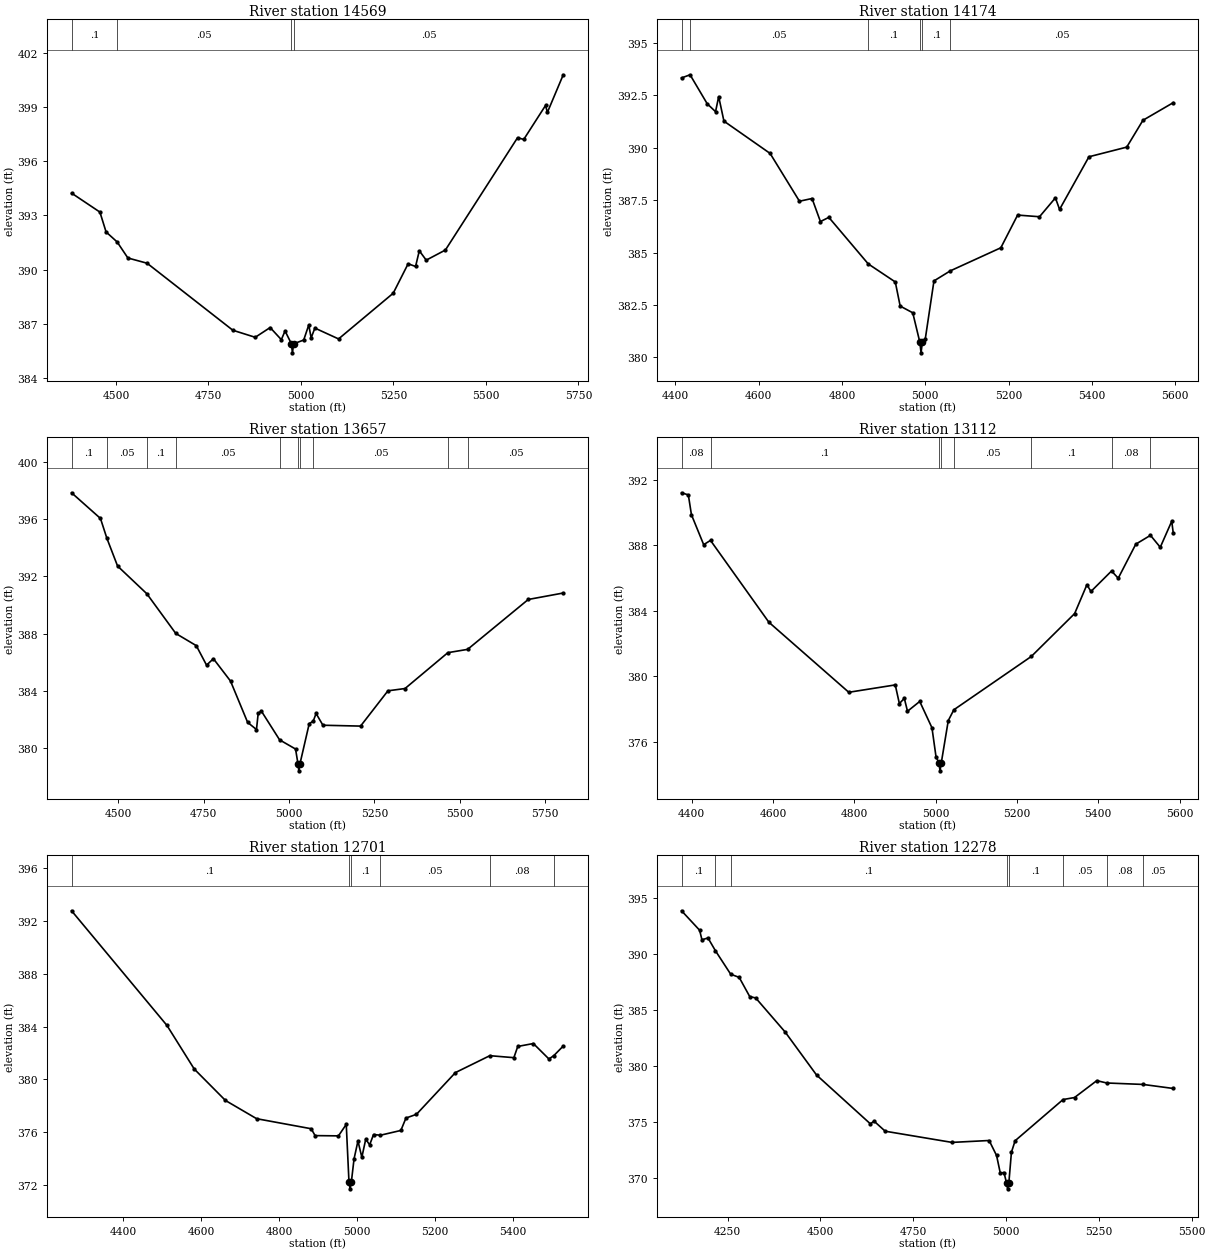
Type RM Length L Ch R = 1 ,14569   ,395,395,395
BEGIN DESCRIPTION:
UNT 029 IN LACR 12.0
END DESCRIPTION:
XS GIS Cut Line= 2
      2202060.26     13212331.17      2200741.73     13212166.36
#Sta/Elev= 30
  4380.1  394.23  4456.7  393.18  4473.4  392.08  4503.2  391.53  4532.3  390.64
  4584.2  390.35    4816  386.64  4876.5  386.25  4916.8  386.79    4947  386.12
  4957.1   386.6  4974.3  385.89    4977  385.39  4980.3  385.89  5007.5   386.1
  5021.1  386.93  5027.6  386.22  5037.7  386.76  5101.7  386.16  5249.4  388.69
  5289.7  390.32  5309.8  390.17  5319.9  391.04  5338.6  390.52  5390.4  391.08
  5585.5   397.3  5602.1   397.2    5661  399.08  5666.1   398.7  5708.9  400.78
#Mann= 4 ,-1 , 0
  4380.1      .1       0  4503.2     .05       0  4974.3     .03       0
  4980.3     .05       0
Bank Sta=4974.3,4980.3
XS Rating Curve= 0 ,0
Exp/Cntr=0.3,0.1

Type RM Length L Ch R = 1 ,14174   ,517,517,517
BEGIN DESCRIPTION:
Mapping XS c4509403
END DESCRIPTION:
XS GIS Cut Line= 2
      2202168.75     13211992.63      2200996.86     13211853.74
#Sta/Elev= 30
  4414.9  393.33  4435.3  393.48  4476.4   392.1  4496.5  391.72    4504  392.44
  4516.6  391.27  4627.4  389.73  4697.9  387.45  4728.1  387.58  4748.2  386.48
  4768.4  386.68    4863  384.46  4927.9   383.6  4939.6  382.45  4969.8  382.13
  4986.9  380.72  4989.7  380.22  4992.9  380.72    5000   380.9  5020.7  383.65
    5060  384.13  5181.2  385.23  5221.5  386.79    5274  386.71  5312.2  387.61
  5322.2  387.06  5392.7  389.57  5483.4  390.03  5522.3  391.31    5595  392.15
#Mann= 6 ,-1 , 0
  4414.9      .1       0  4435.3     .05       0    4863      .1       0
  4986.9     .07       0  4992.9      .1       0    5060     .05       0
Bank Sta=4986.9,4992.9
XS Rating Curve= 0 ,0
Exp/Cntr=0.3,0.1

Type RM Length L Ch R = 1 ,13657   ,545,545,545
BEGIN DESCRIPTION:
UNT 029 IN LACR 11.0
END DESCRIPTION:
XS GIS Cut Line= 2
      2202442.18     13211489.16       2201005.5     13211575.96
#Sta/Elev= 30
  4363.7  397.83  4448.3  396.04  4467.2  394.65  4498.4  392.72    4584  390.79
  4668.8  388.02  4728.8  387.17  4758.9  385.81  4778.9  386.26    4829   384.7
  4879.1  381.82    4905  381.32    4910  382.44  4919.2  382.61  4972.7   380.6
  5019.4  379.96  5026.4  378.94  5029.1  378.44  5032.4  378.94  5059.4  381.73
  5071.2  381.91  5079.5  382.44  5099.5  381.62  5209.7  381.56  5289.8  384.02
  5339.9  384.18  5465.2  386.68    5523  386.91  5700.6  390.39    5803  390.84
#Mann= 10 ,-1 , 0
  4363.7      .1       0  4467.2     .05       0    4584      .1       0
  4668.8     .05       0  4972.7      .1       0  5026.4     .07       0
  5032.4      .1       0  5071.2     .05       0  5465.2     .08       0
    5523     .05       0
Bank Sta=5026.4,5032.4
XS Rating Curve= 0 ,0
Exp/Cntr=0.3,0.1

Type RM Length L Ch R = 1 ,13112   ,411,411,411
BEGIN DESCRIPTION:
UNT 029 IN LACR 10.0
END DESCRIPTION:
XS GIS Cut Line= 2
      2202311.96     13211050.79      2201105.89     13211141.89
#Sta/Elev= 30
    4375   391.2  4391.7  391.07  4399.3  389.86  4429.4  388.03  4446.2  388.29
  4589.8  383.29  4786.4  379.01  4900.7  379.46  4910.8  378.32    4923  378.64
  4930.8  377.85  4960.9  378.45    4991  376.84    5001  375.06    5008  374.71
  5010.8  374.21    5014  374.71  5031.1  377.28  5044.8  377.94  5235.4   381.2
    5342  383.82  5372.1  385.58  5382.1  385.17  5432.7  386.42  5449.2  385.98
  5492.4  388.06  5528.5   388.6  5552.6  387.87  5580.8  389.46  5584.5  388.75
#Mann= 8 ,-1 , 0
    4375     .08       0  4446.2      .1       0    5008     .07       0
    5014      .1       0  5044.8     .05       0  5235.4      .1       0
  5432.7     .08       0  5528.5     .05       0
Bank Sta=5008,5014
XS Rating Curve= 0 ,0
Exp/Cntr=0.3,0.1

Type RM Length L Ch R = 1 ,12701   ,423,423,423
BEGIN DESCRIPTION:
UNT 029 IN LACR 9.0
END DESCRIPTION:
XS GIS Cut Line= 3
      2202342.35     13210725.27      2201990.79     13210712.25
      2201081.05     13210729.58
#Sta/Elev= 30
  4267.7  392.77  4512.5  384.09  4582.5  380.79  4662.6  378.41  4742.6  377.03
  4882.6  376.27  4892.6  375.75  4952.6  375.73  4972.6   376.6  4979.6  372.22
  4982.4  371.72  4985.6  372.22  4992.6  373.99  5002.6  375.34  5012.6  374.11
  5022.6  375.48  5032.6  375.05  5042.6  375.83  5060.4  375.78  5112.7  376.14
  5125.8  377.08  5152.7  377.36  5252.7  380.52    5341   381.8  5402.7  381.65
  5412.7   382.5  5452.7  382.72  5492.7  381.55  5505.4  381.81  5529.4  382.53
#Mann= 6 ,-1 , 0
  4267.7      .1       0  4979.6     .07       0  4985.6      .1       0
  5060.4     .05       0    5341     .08       0  5505.4     .05       0
Bank Sta=4979.6,4985.6
XS Rating Curve= 0 ,0
Exp/Cntr=0.3,0.1

Type RM Length L Ch R = 1 ,12278   ,614,614,614
BEGIN DESCRIPTION:
UNT 029 IN LACR 8.0
END DESCRIPTION:
XS GIS Cut Line= 3
      2202377.05     13210542.97      2201943.04      13210330.3
      2201101.86     13210334.64
#Sta/Elev= 30
  4125.9  393.84  4174.6   392.1  4180.8  391.25  4197.1  391.41  4217.3  390.26
  4258.3  388.17  4281.1  387.89  4309.6  386.17  4325.6  386.05  4405.1     383
  4489.6  379.16  4634.5   374.8  4644.5  375.04  4674.5  374.14  4854.5  373.14
  4954.5  373.31  4974.5  371.97  4984.5   370.4  4994.5  370.45  5001.5  369.49
  5004.3  368.99  5007.5  369.49  5014.5  372.26  5024.5  373.29  5153.6  376.97
  5184.5  377.15  5244.5  378.66  5271.1  378.45  5369.2  378.32  5450.4  377.96
#Mann= 8 ,-1 , 0
  4125.9      .1       0  4217.3     .05       0  4258.3      .1       0
  5001.5     .07       0  5007.5      .1       0  5153.6     .05       0
  5271.1     .08       0  5369.2     .05       0
Bank Sta=5001.5,5007.5
XS Rating Curve= 0 ,0
Exp/Cntr=0.3,0.1

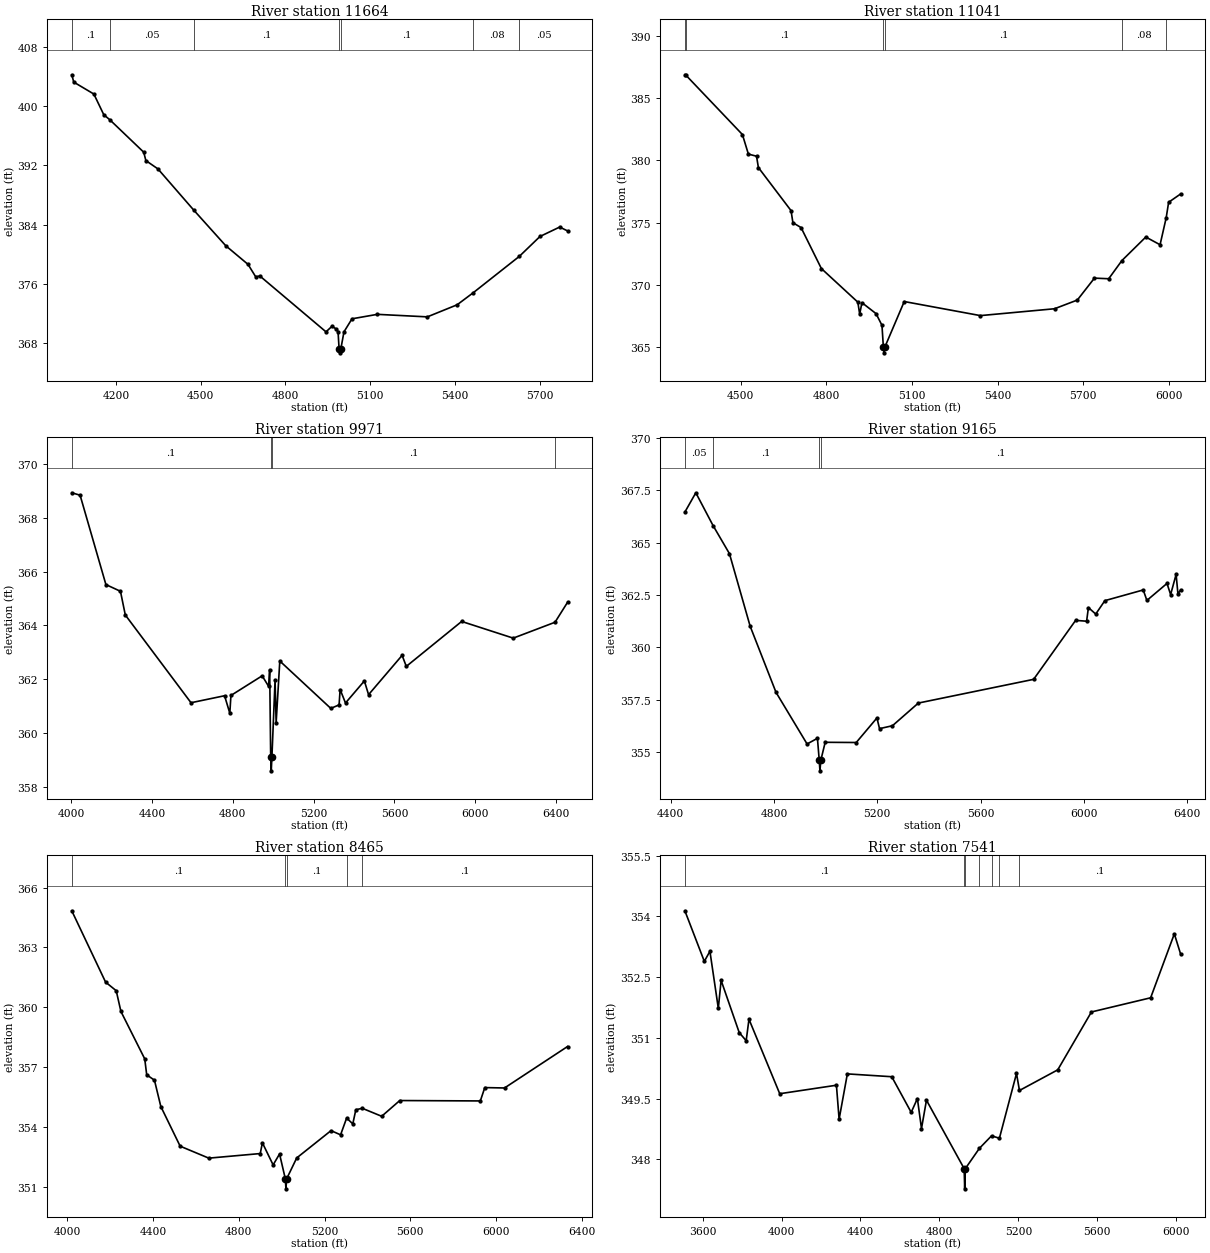
Type RM Length L Ch R = 1 ,11664   ,623,623,623
BEGIN DESCRIPTION:
UNT 029 IN LACR 7.0
END DESCRIPTION:
XS GIS Cut Line= 3
      2202587.73     13210596.87      2201816.38     13209921.29
      2201131.76     13209667.84
#Sta/Elev= 30
  4043.3  404.21  4050.4  403.22  4121.6  401.61  4156.7  398.82  4177.3  398.17
  4298.1  393.77  4305.7  392.64  4348.4  391.52  4474.6  385.99  4588.6  381.16
  4667.3  378.65  4694.8  376.96  4709.1  377.09  4943.5  369.55  4964.4  370.29
  4978.6  369.97  4986.2  369.56  4989.9  367.22  4992.6  366.72  4995.9  367.22
  5007.1  369.55  5035.6  371.31  5125.3  371.91  5302.3  371.57  5407.9   373.2
  5465.7  374.85  5628.1  379.73  5701.2  382.41    5771  383.68  5798.7  383.16
#Mann= 7 ,-1 , 0
  4043.3      .1       0  4177.3     .05       0  4474.6      .1       0
  4989.9     .07       0  4995.9      .1       0  5465.7     .08       0
  5628.1     .05       0
Bank Sta=4989.9,4995.9
XS Rating Curve= 0 ,0
Exp/Cntr=0.3,0.1

Type RM Length L Ch R = 1 ,11041   ,1070,1070,1070
BEGIN DESCRIPTION:
Mapping XS fb09e153
END DESCRIPTION:
XS GIS Cut Line= 3
      2202754.64     13210043.82      2202034.19     13209440.55
      2201235.57     13209444.89
#Sta/Elev= 30
  4303.8  386.88  4307.3  386.85  4505.6  382.08  4526.5  380.51  4555.1  380.34
  4561.6  379.43  4676.1  375.97  4682.6     375  4711.2  374.61  4782.4  371.32
  4910.3  368.62  4916.8  367.65  4924.6  368.58  4974.1   367.7  4994.9  366.76
  4999.7  365.05  5002.4  364.55  5005.7  365.05    5073  368.67  5339.9  367.54
  5599.9  368.09  5679.9  368.79  5739.9  370.55  5789.9   370.5  5836.2  371.96
    5920  373.85    5970  373.23  5991.6  375.41    6000  376.64  6042.1  377.31
#Mann= 6 ,-1 , 0
  4303.8     .05       0  4307.3      .1       0  4999.7     .07       0
  5005.7      .1       0  5836.2     .08       0  5991.6     .05       0
Bank Sta=4999.7,5005.7
XS Rating Curve= 0 ,0
Exp/Cntr=0.3,0.1

Type RM Length L Ch R = 1 ,9971    ,806,806,806
BEGIN DESCRIPTION:
UNT 029 IN LACR 6.0
END DESCRIPTION:
XS GIS Cut Line= 3
       2203726.9     13209162.77      2202494.26     13208763.46
      2201378.85     13209071.61
#Sta/Elev= 30
  4003.5  368.93  4044.7  368.84  4172.4  365.52  4244.4  365.27  4268.4  364.39
  4593.5  361.13  4759.5  361.39  4785.5  360.74    4791   361.4  4945.5  362.13
  4977.4  361.74  4982.7  362.36  4987.7   359.1  4990.5   358.6  4993.7   359.1
  5009.4  361.97  5014.7  360.39  5032.8  362.68  5285.1  360.92  5326.1  361.05
  5331.3  361.62  5357.9  361.12  5451.2  361.94    5472  361.43    5638  362.89
  5658.7  362.48  5932.6  364.15  6187.8  363.53  6394.5  364.12  6456.4  364.86
#Mann= 4 ,-1 , 0
  4003.5      .1       0  4987.7     .07       0  4993.7      .1       0
  6394.5     .08       0
Bank Sta=4987.7,4993.7
XS Rating Curve= 0 ,0
Exp/Cntr=0.3,0.1

Type RM Length L Ch R = 1 ,9165    ,700,700,700
BEGIN DESCRIPTION:
UNT 029 IN LACR 5.0
END DESCRIPTION:
XS GIS Cut Line= 3
      2203410.01     13208138.46      2202307.63     13208199.23
      2201731.51     13208775.34
#Sta/Elev= 30
  4455.3  366.45  4497.7  367.37  4564.3  365.81  4627.8  364.47    4708  361.01
  4808.1  357.86  4928.3   355.4  4968.4  355.67  4975.4  354.62  4978.1  354.12
  4981.4  354.62  4998.4  355.48  5118.6  355.47  5198.7  356.64  5208.7  356.13
  5258.8  356.27    5359  357.35  5805.1  358.48  5967.7  361.29  6010.2  361.25
  6017.2   361.9  6045.5  361.59  6080.9  362.23  6229.4  362.74  6243.5  362.24
  6321.3  363.05  6335.4  362.52  6356.6  363.48  6363.7  362.55  6374.1  362.74
#Mann= 4 ,-1 , 0
  4455.3     .05       0  4564.3      .1       0  4975.4     .07       0
  4981.4      .1       0
Bank Sta=4975.4,4981.4
XS Rating Curve= 0 ,0
Exp/Cntr=0.3,0.1

Type RM Length L Ch R = 1 ,8465    ,924,924,924
BEGIN DESCRIPTION:
Mapping XS 12f39cf6
END DESCRIPTION:
XS GIS Cut Line= 4
      2203449.13     13208047.34       2203210.4     13207600.27
      2202468.22     13207569.89      2201665.24     13208268.69
#Sta/Elev= 30
  4020.1  364.84    4178  361.26  4227.6  360.83  4249.5  359.79  4360.7  357.41
  4369.9  356.61  4406.1  356.34  4435.8  355.02    4526  353.03  4659.7  352.43
  4899.9  352.66  4909.9   353.2    4960  352.09    4990  352.64    5017  351.39
  5019.8  350.89    5023  351.39  5070.1  352.44  5230.2  353.81  5274.9   353.6
  5303.1  354.44  5331.9  354.15  5346.1  354.86  5376.4  354.93  5466.7  354.53
  5551.2  355.32  5927.2   355.3    5948  355.97  6040.1  355.95  6334.2  358.03
#Mann= 5 ,-1 , 0
  4020.1      .1       0    5017     .07       0    5023      .1       0
  5303.1     .08       0  5376.4      .1       0
Bank Sta=5017,5023
XS Rating Curve= 0 ,0
Exp/Cntr=0.3,0.1

Type RM Length L Ch R = 1 ,7541    ,548,548,548
BEGIN DESCRIPTION:
Mapping XS a5f249cf
END DESCRIPTION:
XS GIS Cut Line= 4
      2203640.09     13207543.84      2203258.15     13207131.52
       2201938.7     13206736.55       2201365.8     13206719.19
#Sta/Elev= 30
    3510  354.14  3608.6  352.89    3637  353.14  3679.5  351.73  3693.7  352.42
  3785.5  351.13  3820.7  350.93  3834.9  351.46  3990.8  349.62  4278.1  349.83
  4291.7  348.99  4333.5  350.11  4558.5  350.04    4657  349.16  4688.4   349.5
  4709.2  348.76  4734.4  349.46  4925.4  347.77  4928.2  347.27  4931.4  347.77
  5002.6  348.27  5064.3  348.58  5104.1  348.52  5190.7  350.12  5205.7   349.7
  5399.7  350.21  5570.4  351.64  5870.5  351.99  5990.6  353.57  6022.5  353.07
#Mann= 7 ,-1 , 0
    3510      .1       0  4925.4     .07       0  4931.4      .1       0
  5002.6     .08       0  5064.3      .1       0  5104.1     .08       0
  5205.7      .1       0
Bank Sta=4925.4,4931.4
XS Rating Curve= 0 ,0
Exp/Cntr=0.3,0.1

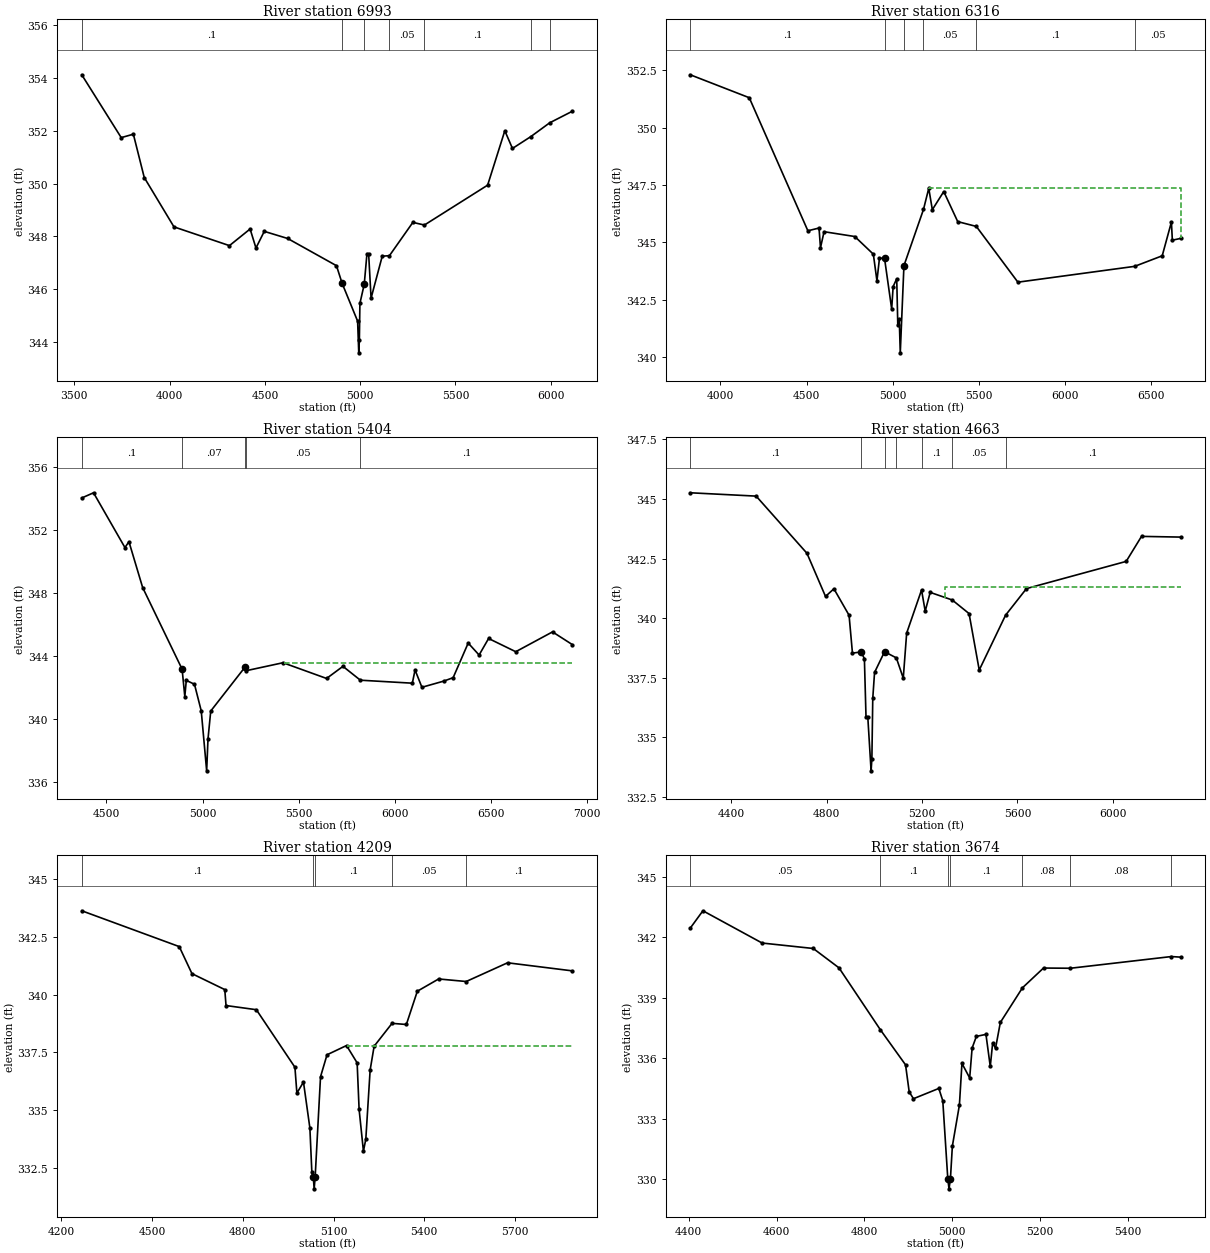
Type RM Length L Ch R = 1 ,6993    ,677,677,677
BEGIN DESCRIPTION:
UNT 029 IN LACR 4.0
END DESCRIPTION:
XS GIS Cut Line= 4
      2203826.72     13207439.67      2203318.91     13206840.72
      2202424.81     13206315.55      2201673.99     13206367.63
#Sta/Elev= 30
  3538.9  354.12    3746  351.74  3809.7  351.87  3866.8  350.23  4022.8  348.36
  4313.9  347.65  4422.4  348.28  4453.1  347.56  4496.7  348.19  4619.7  347.92
  4875.6  346.89  4905.4  346.22  4986.6  344.79  4992.6  343.59  4995.8  344.09
  4998.6  345.46  5021.4  346.19  5035.7  347.35  5044.6  347.32  5057.2  345.66
  5115.8  347.25  5153.6  347.27  5276.5  348.53  5337.2  348.43  5668.9  349.94
  5759.1     352  5799.2  351.33  5895.9  351.78  5994.4   352.3  6113.7  352.74
#Mann= 7 ,-1 , 0
  3538.9      .1       0  4905.4     .07       0  5021.4      .1       0
  5153.6     .05       0  5337.2      .1       0  5895.9     .08       0
  5994.4      .1       0
Bank Sta=4905.4,5021.4
XS Rating Curve= 0 ,0
Exp/Cntr=0.3,0.1

Type RM Length L Ch R = 1 ,6316    ,912,912,912
BEGIN DESCRIPTION:
Mapping XS 9e2d3861
END DESCRIPTION:
XS GIS Cut Line= 4
      2204147.89     13207001.29      2203774.64     13206632.39
      2203019.43     13206076.83      2201748.36     13205521.55
#Sta/Elev= 30
  3824.6   352.3  4167.3   351.3  4507.7   345.5  4572.4  345.62  4580.9  344.76
  4601.7  345.46  4780.1  345.25  4887.9  344.48  4908.8  343.32  4923.4   344.3
  4952.7  344.31  4994.4  342.09  5002.9  343.07  5023.7  343.41  5029.9  341.39
  5038.4  341.66  5044.3  340.18  5065.6  343.98  5179.1  346.43  5209.7  347.35
  5230.5  346.42  5296.8  347.21  5377.9   345.9    5486  345.69  5727.4  343.26
  6405.8  343.95  6565.6  344.41    6619  345.88  6624.4  345.09    6674  345.17
#Mann= 6 ,-1 , 0
  3824.6      .1       0  4952.7     .07       0  5065.6      .1       0
  5179.1     .05       0    5486      .1       0  6405.8     .05       0
#XS Ineff= 2 , 0
                         5210.23          347.36
Permanent Ineff=
       F       F
Bank Sta=4952.7,5065.6
XS Rating Curve= 0 ,0
Exp/Cntr=0.3,0.1

Type RM Length L Ch R = 1 ,5404    ,741,741,741
BEGIN DESCRIPTION:
Mapping XS 472be786
END DESCRIPTION:
XS GIS Cut Line= 3
      2204490.77     13206480.46      2203635.75     13205733.95
      2202589.78     13204779.12
#Sta/Elev= 30
  4371.6  354.04  4432.8  354.37  4596.1  350.89    4617  351.26  4688.2  348.35
  4893.4  343.16  4907.5  341.42  4915.1  342.45  4957.8   342.2  4992.9  340.51
  5021.1   336.7    5028  338.72  5042.3   340.5  5219.8  343.28  5225.2  343.06
  5418.2  343.57  5644.7  342.57  5729.8  343.34  5820.4  342.46  6090.6  342.27
  6104.8  343.11  6140.4  342.01  6253.4   342.4  6302.8  342.62  6381.1  344.82
  6437.8  344.06  6487.2  345.11  6628.4  344.27  6819.6  345.53  6922.9  344.72
#Mann= 5 ,-1 , 0
  4371.6      .1       0  4893.4     .07       0  5219.8      .1       0
  5225.2     .05       0  5820.4      .1       0
#XS Ineff= 2 , 0
                         5421.59          343.56
Permanent Ineff=
       F       F
Bank Sta=4893.4,5219.8
XS Rating Curve= 0 ,0
Exp/Cntr=0.3,0.1

Type RM Length L Ch R = 1 ,4663    ,454,454,454
BEGIN DESCRIPTION:
UNT 029 IN LACR 3.0
END DESCRIPTION:
XS GIS Cut Line= 2
      2204855.38     13206059.48      2203475.16     13204536.03
#Sta/Elev= 30
    4229  345.26  4505.1  345.12    4718  342.72  4795.7  340.91  4830.9  341.23
  4894.4  340.12  4908.6  338.53  4944.4  338.58  4958.6   338.3  4965.4  335.85
  4972.8  335.86  4986.7  333.59    4990  334.09  4993.7  336.63  5001.2  337.72
  5043.1  338.59  5092.5  338.33  5121.5  337.48  5135.7  339.37  5198.1  341.18
  5213.4  340.29  5234.3  341.08  5326.7  340.76  5397.2  340.19  5439.8  337.82
    5550  340.12  5637.8  341.24  6055.5  342.38  6119.7  343.43  6284.7   343.4
#Mann= 7 ,-1 , 0
    4229      .1       0  4944.4     .07       0  5043.1      .1       0
  5092.5     .05       0  5198.1      .1       0  5326.7     .05       0
    5550      .1       0
#XS Ineff= 2 , 0
                          5298.3          341.29
Permanent Ineff=
       F       F
Bank Sta=4944.4,5043.1
XS Rating Curve= 0 ,0
Exp/Cntr=0.3,0.1

Type RM Length L Ch R = 1 ,4209    ,535,535,535
BEGIN DESCRIPTION:
UNT 029 IN LACR 2.0
END DESCRIPTION:
XS GIS Cut Line= 3
      2204881.41     13205755.64      2204703.46     13205317.28
      2203969.94     13204431.85
#Sta/Elev= 30
  4267.1  343.63  4589.6  342.08  4631.6  340.91  4740.2  340.22  4744.3  339.53
  4844.6  339.35  4972.2  336.86  4978.7  335.74  5000.5  336.22  5021.7  334.23
  5028.2  332.32  5033.1   332.1  5035.8   331.6  5039.1   332.1  5056.9  336.45
  5078.4   337.4  5142.9   337.8    5178  337.05  5184.5  335.04  5198.8  333.23
  5206.7  333.75    5221  336.74  5234.2  337.77  5293.5  338.76  5340.8  338.71
  5377.1  340.15  5447.6  340.68  5538.7  340.57  5675.6  341.38    5890  341.03
#Mann= 5 ,-1 , 0
  4267.1      .1       0  5033.1     .07       0  5039.1      .1       0
  5293.5     .05       0  5538.7      .1       0
#XS Ineff= 2 , 0
                         5142.95           337.8
Permanent Ineff=
       F       F
Bank Sta=5033.1,5039.1
XS Rating Curve= 0 ,0
Exp/Cntr=0.3,0.1

Type RM Length L Ch R = 1 ,3674    ,585,585,585
BEGIN DESCRIPTION:
Mapping XS ab3833ce
END DESCRIPTION:
XS GIS Cut Line= 2
      2205137.47     13205343.28      2204691.06     13204320.45
#Sta/Elev= 30
  4403.8  342.46  4432.6  343.32  4567.3  341.72  4683.6  341.45  4742.1  340.49
  4835.9  337.43  4893.5  335.68  4901.8  334.34  4911.5     334  4969.2  334.51
  4978.2   333.9  4989.6  330.03  4992.4  329.53  4995.6  330.03    5000  331.65
    5016  333.68  5021.8  335.75  5039.4  335.03  5044.9  336.51  5054.6  337.09
  5076.4  337.19  5086.2   335.6  5091.7  336.77  5098.2   336.5  5109.1  337.78
  5159.4   339.5  5207.3  340.48  5268.6  340.47  5498.2  341.05  5519.8  341.02
#Mann= 7 ,-1 , 0
  4403.8     .05       0  4835.9      .1       0  4989.6     .07       0
  4995.6      .1       0  5159.4     .08       0  5268.6     .08       0
  5498.2     .05       0
Bank Sta=4989.6,4995.6
XS Rating Curve= 0 ,0
Exp/Cntr=0.3,0.1

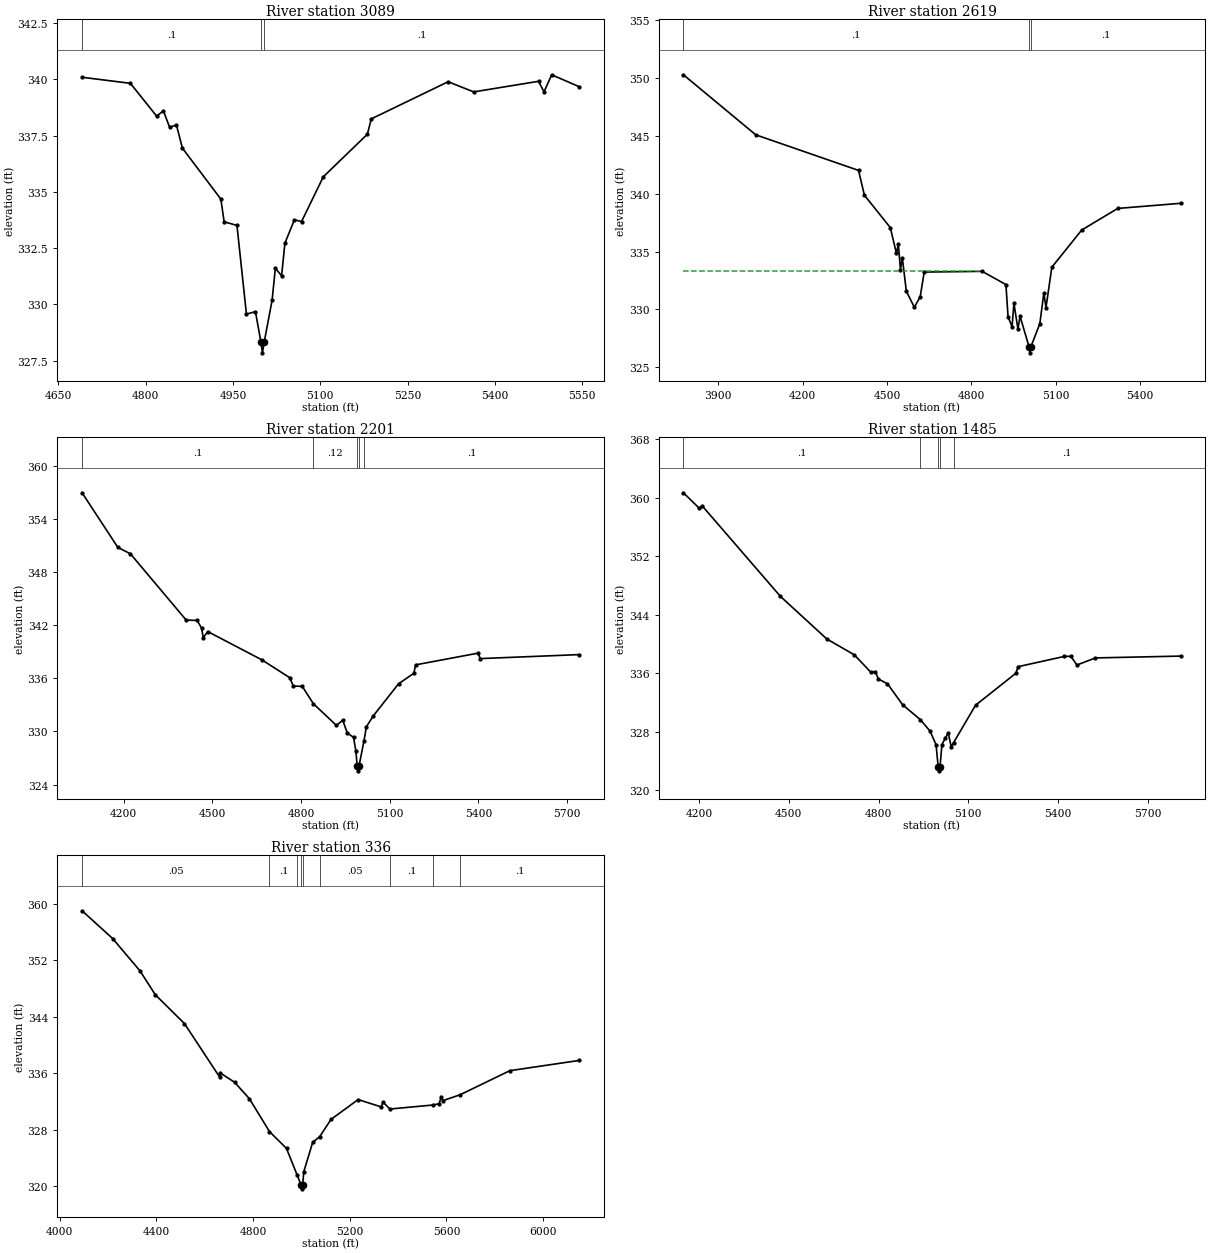
Type RM Length L Ch R = 1 ,3089    ,470,470,470
BEGIN DESCRIPTION:
Mapping XS e4cd3b1c
END DESCRIPTION:
XS GIS Cut Line= 2
      2205545.46      13204870.2      2205146.18     13204115.06
#Sta/Elev= 30
  4690.8  340.09  4773.8  339.82    4819  338.36  4830.5   338.6  4841.2  337.87
  4852.9  337.97  4863.2  336.94  4929.2  334.68  4934.9  333.67  4956.9  333.51
  4973.2  329.57  4988.7  329.68  4997.9  328.35  5000.7  327.85  5003.9  328.35
  5017.3  330.19  5022.9  331.61  5033.6  331.27  5039.3  332.72  5055.6  333.76
  5067.9  333.68  5105.3  335.67    5181  337.56  5187.7  338.24  5319.7  339.89
  5363.7  339.44  5475.1  339.91  5484.5  339.44  5497.7   340.2    5545  339.67
#Mann= 3 ,-1 , 0
  4690.8      .1       0  4997.9     .07       0  5003.9      .1       0
Bank Sta=4997.9,5003.9
XS Rating Curve= 0 ,0
Exp/Cntr=0.3,0.1

Type RM Length L Ch R = 1 ,2619    ,418,418,418
BEGIN DESCRIPTION:
Mapping XS 6589a46a
END DESCRIPTION:
XS GIS Cut Line= 3
      2206430.88     13205373.69      2206222.56     13204805.13
      2205351.41       13204038.
#Sta/Elev= 30
  3776.7  350.25  4033.6  345.07  4398.8     342  4419.7  339.86  4511.7  337.07
  4533.5  334.84  4540.2  335.64  4547.8  333.45  4554.4  334.45  4568.7  331.58
  4597.1  330.19    4618   331.1  4632.2  333.23  4838.1  333.29  4922.5  332.15
  4930.1  329.37  4944.3  328.52    4951  330.52  4965.2  328.32  4972.8  329.41
  5004.9  326.76  5007.7  326.26  5010.9  326.76    5043  328.78  5057.3  331.43
  5064.8  330.16  5085.7  333.65    5192  336.86    5320  338.72    5543  339.16
#Mann= 3 ,-1 , 0
  3776.7      .1       0  5004.9     .07       0  5010.9      .1       0
#XS Ineff= 2 , 0
         4836.65  333.34
Permanent Ineff=
       F       F
Bank Sta=5004.9,5010.9
XS Rating Curve= 0 ,0
Exp/Cntr=0.3,0.1

Type RM Length L Ch R = 1 ,2201    ,716,716,716
BEGIN DESCRIPTION:
Mapping XS 1a260f24
END DESCRIPTION:
XS GIS Cut Line= 3
      2206934.38     13204796.46      2206404.85     13204466.59
      2205506.41     13203906.69
#Sta/Elev= 30
    4059  356.96    4180  350.79  4222.5  350.07  4411.3  342.58  4447.9  342.54
  4463.2   341.7  4469.1  340.59  4484.4  341.28  4667.4  338.09  4761.8  336.07
  4773.8  335.13  4804.2  335.09  4841.8  333.13  4919.9  330.68  4941.1  331.27
  4956.5  329.83  4977.7  329.33  4985.8  327.76    4990  326.05  4992.8  325.55
    4996  326.05  5012.9  328.91  5021.2  330.53  5044.8  331.77  5129.9  335.38
  5181.8  336.57  5187.7  337.52  5398.3  338.84  5407.2  338.23  5741.5  338.68
#Mann= 5 ,-1 , 0
    4059      .1       0  4841.8     .12       0    4990     .07       0
    4996     .12       0  5012.9      .1       0
Bank Sta=4990,4996
XS Rating Curve= 0 ,0
Exp/Cntr=0.3,0.1

Type RM Length L Ch R = 1 ,1485    ,1149,1149,1149
BEGIN DESCRIPTION:
Mapping XS 53357958
END DESCRIPTION:
XS GIS Cut Line= 3
      2207319.71     13203895.96      2206127.86     13203695.23
      2205702.04     13203845.52
#Sta/Elev= 30
  4148.5  360.69  4201.2  358.58  4211.4  358.89  4472.1  346.52  4627.1  340.68
  4719.3   338.5  4774.8   336.1  4789.4  336.21  4799.5  335.19    4830  334.54
  4880.7  331.66  4939.5  329.64  4971.9  328.07  4992.2   326.2  4999.3  323.12
  5002.1  322.62  5005.3  323.12  5011.8  326.22  5022.6  327.07  5032.8  327.81
  5042.9  325.89  5050.7  326.48    5124   331.6    5259  335.99    5266  336.88
  5420.9  338.29  5442.3   338.3  5462.6  337.11  5524.5  338.08  5808.7  338.33
#Mann= 5 ,-1 , 0
  4148.5      .1       0  4939.5     .12       0  4999.3     .07       0
  5005.3     .12       0  5050.7      .1       0
Bank Sta=4999.3,5005.3
XS Rating Curve= 0 ,0
Exp/Cntr=0.3,0.1

Type RM Length L Ch R = 1 ,336     ,0,0,0
BEGIN DESCRIPTION:
UNT 029 IN LACR 1.0
END DESCRIPTION:
XS GIS Cut Line= 4
      2207344.73     13203067.94      2206918.22      13202691.6
      2206328.59     13202817.05      2205864.39      13203569.8
#Sta/Elev= 30
  4093.3  358.98  4219.7  355.05  4332.6  350.48  4396.2  347.09  4516.7  343.01
  4661.9  335.45  4665.5     336    4724   334.7  4785.3  332.37  4868.3  327.72
  4938.7  325.33  4983.1  321.53  4999.4  320.11  5002.1  319.61  5005.4  320.11
  5010.2  322.04  5046.9  326.18  5076.3  327.01  5122.7  329.44    5235  332.25
  5331.3   331.2  5337.2  331.91  5366.4  330.91  5544.5  331.48  5570.2  331.66
  5578.5  332.67  5584.4  332.08  5656.8  332.93  5862.4  336.34  6149.3  337.79
#Mann= 9 ,-1 , 0
  4093.3     .05       0  4868.3      .1       0  4983.1     .12       0
  4999.4     .07       0  5005.4     .12       0  5076.3     .05       0
  5366.4      .1       0  5544.5     .05       0  5656.8      .1       0
Bank Sta=4999.4,5005.4
XS Rating Curve= 0 ,0
Exp/Cntr=0.3,0.1

Chan Stop Cuts=-1
Use User Specified Reach Order=0
Composite Channel Slope=5