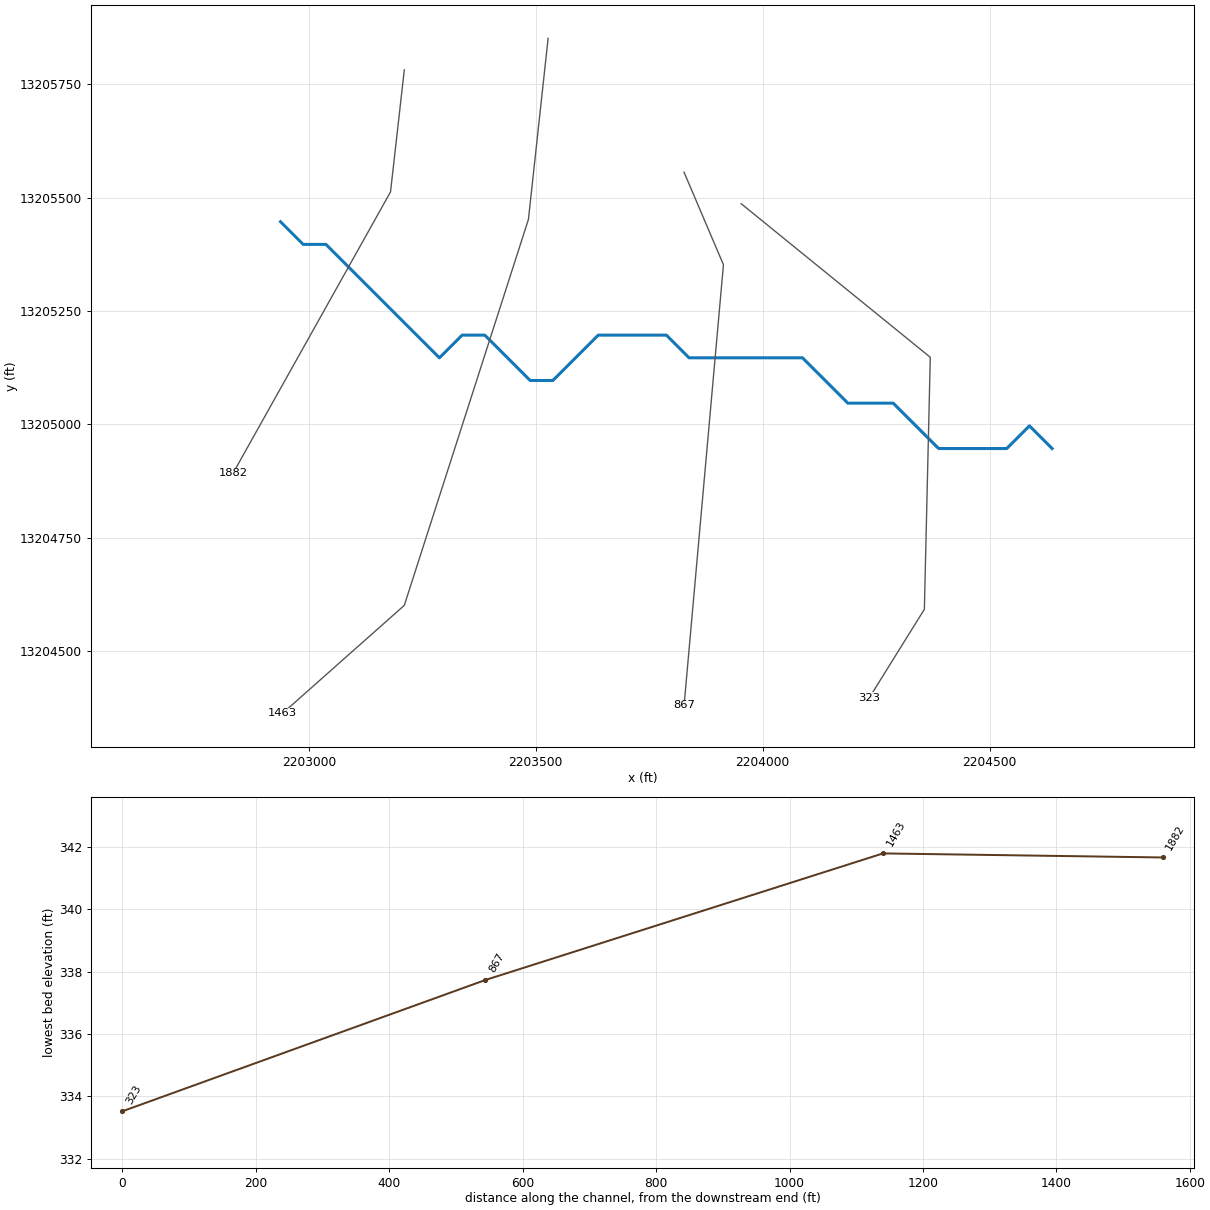
--- UNT 030 IN LACR.prj (project) ---

Proj Title=UNT 030 IN LACR Base Level Engineering
Current Plan=p01
Default Exp/Contr=0.3,0.1
English Units
Geom File=g01
Flow File=f01
Plan File=p01
Y Axis Title=Elevation
X Axis Title(PF)=Main Channel Distance
X Axis Title(XS)=Station
BEGIN DESCRIPTION:
UNT 030 IN LACR
END DESCRIPTION:
DSS Export Rating Curves= 0
DSS Export Rating Curve Sorted= 0
DSS Export Volume Flow Curves= 0
DXF OffsetX= 0
DXF OffsetY= 0
DXF ScaleX= 1
DXF ScaleY= 10

--- UNT 030 IN LACR.p01 (plan) ---

Plan Title=Multiple Run
Short Identifier=Multiple
Geom File=g01
Flow File=f01
Subcritical Flow
K Sum by GR= 0
Std Step Tol= 0.01
Critical Tol= 0.01
Num of Std Step Trials= 20
Max Error Tol= 0.3
Flow Tol Ratio= 0.001
Split Flow NTrial= 30
Split Flow Tol= 0.02
Split Flow Ratio= 0.02
Log Output Level= 0
Friction Slope Method= 1
Unsteady Friction Slope Method= 2
Unsteady Bridges Friction Slope Method= 1
Parabolic Critical Depth
Global Vel Dist=  1 , 1 , 1
Global Log Level= 0
CheckData=True
Encroach Param= -1, 0, 0, 0
BEGIN DESCRIPTION:
Multiple Run
END DESCRIPTION:

--- UNT 030 IN LACR.f01 (steady flow) ---

Flow Title=Multiple
Program Version=4.10
Number of Profiles= 7
Profile Names=10-year,25-year,50-year,1pct_min,100-year,1pct_plu,500-year
River Rch & RM=UNT 030 IN LACR,Reach-1         ,1882
     114     149     177     154     208     282     294
River Rch & RM=UNT 030 IN LACR,Reach-1         ,323
     416     594     745     686     928    1255    1465
Boundary for River Rch & Prof#=UNT 030 IN LACR,Reach-1         , 1
Up Type= 0
Dn Type= 3
Dn Slope=0.007
Boundary for River Rch & Prof#=UNT 030 IN LACR,Reach-1         , 2
Up Type= 0
Dn Type= 3
Dn Slope=0.007
Boundary for River Rch & Prof#=UNT 030 IN LACR,Reach-1         , 3
Up Type= 0
Dn Type= 3
Dn Slope=0.007
Boundary for River Rch & Prof#=UNT 030 IN LACR,Reach-1         , 4
Up Type= 0
Dn Type= 3
Dn Slope=0.007
Boundary for River Rch & Prof#=UNT 030 IN LACR,Reach-1         , 5
Up Type= 0
Dn Type= 3
Dn Slope=0.007
Boundary for River Rch & Prof#=UNT 030 IN LACR,Reach-1         , 6
Up Type= 0
Dn Type= 3
Dn Slope=0.007
Boundary for River Rch & Prof#=UNT 030 IN LACR,Reach-1         , 7
Up Type= 0
Dn Type= 3
Dn Slope=0.007
DSS Import GetInterval= 0
DSS Import GetPeak= 0
DSS Import FillOption= 0

--- UNT 030 IN LACR.g01 (geometry) ---

Geom Title=Existing Conditions
Program Version=4.10

River Reach=UNT 030 IN LACR ,Reach-1
Reach XY= 22
      2202937.72     13205446.86      2202987.72     13205396.85
      2203037.72     13205396.85      2203287.72     13205146.85
      2203337.72     13205196.85      2203387.72     13205196.85
      2203437.72     13205146.85      2203487.72     13205096.86
      2203537.72     13205096.86      2203587.72     13205146.85
      2203637.72     13205196.85      2203787.72     13205196.85
      2203837.72     13205146.85      2204087.72     13205146.85
      2204137.72     13205096.86      2204187.72     13205046.85
      2204287.72     13205046.85      2204337.72     13204996.85
      2204387.72     13204946.86      2204537.72     13204946.86
      2204587.72     13204996.85      2204637.72     13204946.86

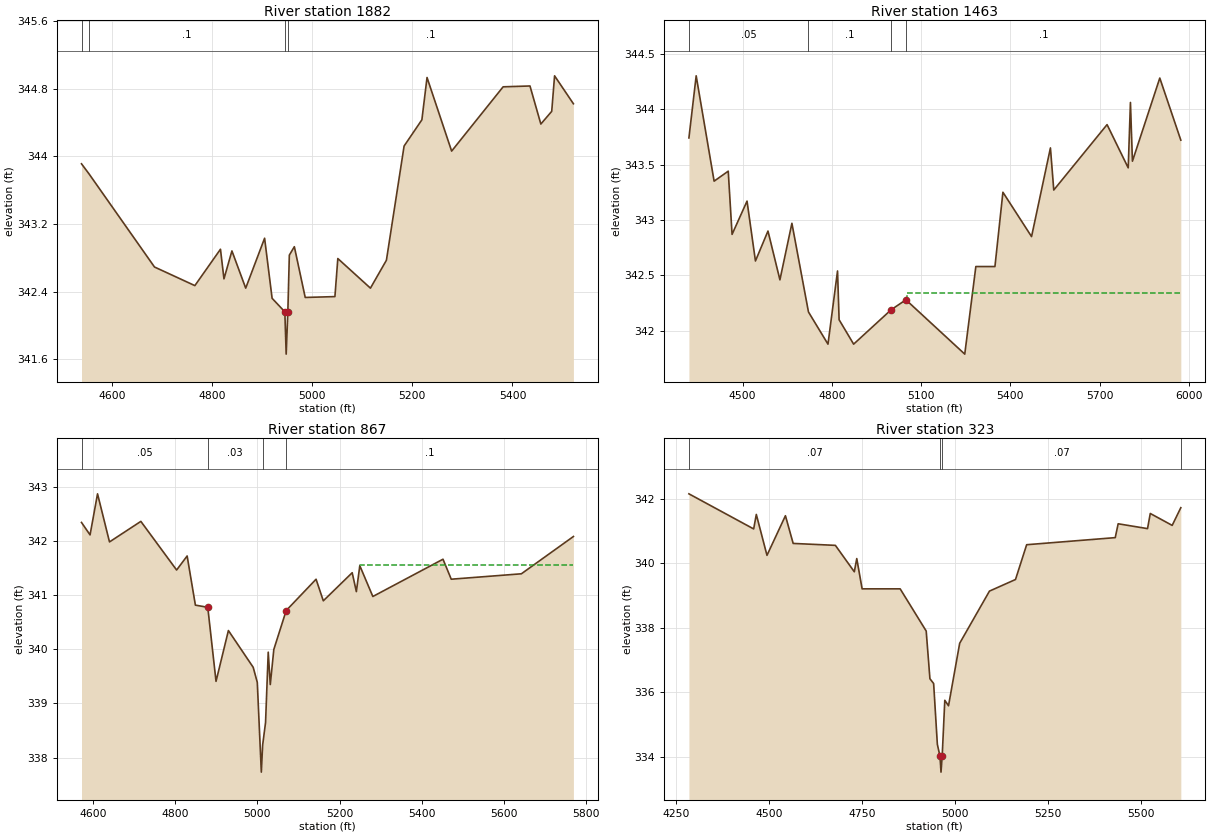
Type RM Length L Ch R = 1 ,1882    ,419,419,419
BEGIN DESCRIPTION:
UNT 030 IN LACR 2.0
END DESCRIPTION:
XS GIS Cut Line= 3
       2203210.4     13205781.68      2203180.02     13205512.59
      2202832.79     13204891.92
#Sta/Elev= 30
  4539.6  343.91  4554.7  343.79  4685.3  342.69  4765.9  342.47    4817   342.9
    4824  342.55  4839.9  342.88  4867.4  342.44  4905.1  343.03  4920.1  342.32
  4945.5  342.16  4948.2  341.66  4951.5  342.16  4954.5  342.83  4964.5  342.93
  4986.2  342.33  5045.5  342.34  5051.3  342.79  5116.4  342.44  5148.3  342.77
  5183.6  344.12  5219.1  344.43  5229.4  344.93  5278.5  344.06  5381.3  344.82
  5434.9  344.83  5456.6  344.38  5478.3  344.53    5484  344.95  5521.6  344.62
#Mann= 4 ,-1 , 0
  4539.6     .05       0  4554.7      .1       0  4945.5     .07       0
  4951.5      .1       0
Bank Sta=4945.5,4951.5
XS Rating Curve= 0 ,0
Exp/Cntr=0.3,0.1

Type RM Length L Ch R = 1 ,1463    ,596,596,596
BEGIN DESCRIPTION:
Mapping XS 743a9024
END DESCRIPTION:
XS GIS Cut Line= 4
      2203527.24      13205851.1      2203483.84     13205451.83
       2203210.4     13204601.14      2202941.98     13204363.02
#Sta/Elev= 30
  4319.3  343.74  4343.7   344.3    4404  343.35  4451.5  343.44  4464.4  342.87
  4514.7  343.17    4543  342.63  4585.1   342.9  4625.3  342.46  4665.6  342.97
  4721.3  342.17  4786.9  341.88    4819  342.54  4824.3   342.1  4873.2  341.88
  4999.2  342.19  5048.9  342.28  5246.8  341.79  5284.1  342.58  5348.3  342.58
  5375.1  343.25  5471.4  342.85  5534.9  343.65  5546.1  343.27  5725.3  343.86
  5796.4  343.47  5803.9  344.06  5810.6  343.53  5902.6  344.28  5973.3  343.72
#Mann= 4 ,-1 , 0
  4319.3     .05       0  4721.3      .1       0  4999.2     .03       0
  5048.9      .1       0
#XS Ineff= 2 , 0
       0    4819  342.54 5053.98       0  342.34
Permanent Ineff=
       T       T
Bank Sta=4999.2,5048.9
XS Rating Curve= 0 ,0
Exp/Cntr=0.3,0.1

Type RM Length L Ch R = 1 ,867     ,544,544,544
BEGIN DESCRIPTION:
UNT 030 IN LACR 3.0
END DESCRIPTION:
XS GIS Cut Line= 3
      2203826.71     13205556.03      2203913.53       13205352.
      2203826.81      13204380.8
#Sta/Elev= 30
  4572.3  342.35  4593.1  342.12  4611.3  342.88  4640.4  341.99  4716.7  342.37
  4803.7  341.47  4829.3  341.73  4849.4  340.82  4879.5  340.78  4899.6  339.41
  4929.7  340.35    4990  339.67    5000  339.39  5009.8  337.73    5013  338.23
  5020.1  338.65  5026.6  339.95  5031.6  339.35  5040.2     340  5070.3  340.72
    5143   341.3  5160.6   340.9  5230.9  341.42    5241  341.07  5249.4  341.55
  5281.1  340.98  5451.8  341.67  5471.9   341.3  5642.5   341.4  5769.1  342.09
#Mann= 4 ,-1 , 0
  4572.3     .05       0  4879.5     .03       0    5013     .05       0
  5070.3      .1       0
#XS Ineff= 2 , 0
       0                 5249.55       0  341.57
Permanent Ineff=
       F       T
Bank Sta=4879.5,5070.3
XS Rating Curve= 0 ,0
Exp/Cntr=0.3,0.1

Type RM Length L Ch R = 1 ,323     ,0,0,0
BEGIN DESCRIPTION:
UNT 030 IN LACR 1.0
END DESCRIPTION:
XS GIS Cut Line= 4
      2203952.61     13205486.54      2204369.26     13205148.01
      2204356.24     13204592.46       2204234.7     13204397.13
#Sta/Elev= 30
  4284.6  342.16  4458.7  341.07  4465.8  341.52  4494.5  340.25  4544.1  341.48
  4564.9  340.62  4678.4  340.56  4729.3  339.74  4735.9  340.15  4750.3  339.21
  4852.6  339.21  4922.6   337.9  4932.6  336.42  4942.6  336.27  4952.6  334.38
  4959.6  334.02  4962.4  333.52  4965.6  334.02  4972.6  335.75  4982.6  335.58
  5012.6  337.52  5092.7  339.14  5162.7   339.5  5192.7  340.58  5430.9   340.8
  5438.7  341.23  5517.7  341.08  5525.1  341.55    5584  341.18  5607.2  341.73
#Mann= 4 ,-1 , 0
  4284.6     .07       0  4959.6    .035       0  4965.6     .07       0
  5607.2      .1       0
Bank Sta=4959.6,4965.6
XS Rating Curve= 0 ,0
Exp/Cntr=0.3,0.1

Chan Stop Cuts=-1
Use User Specified Reach Order=0
Composite Channel Slope=5