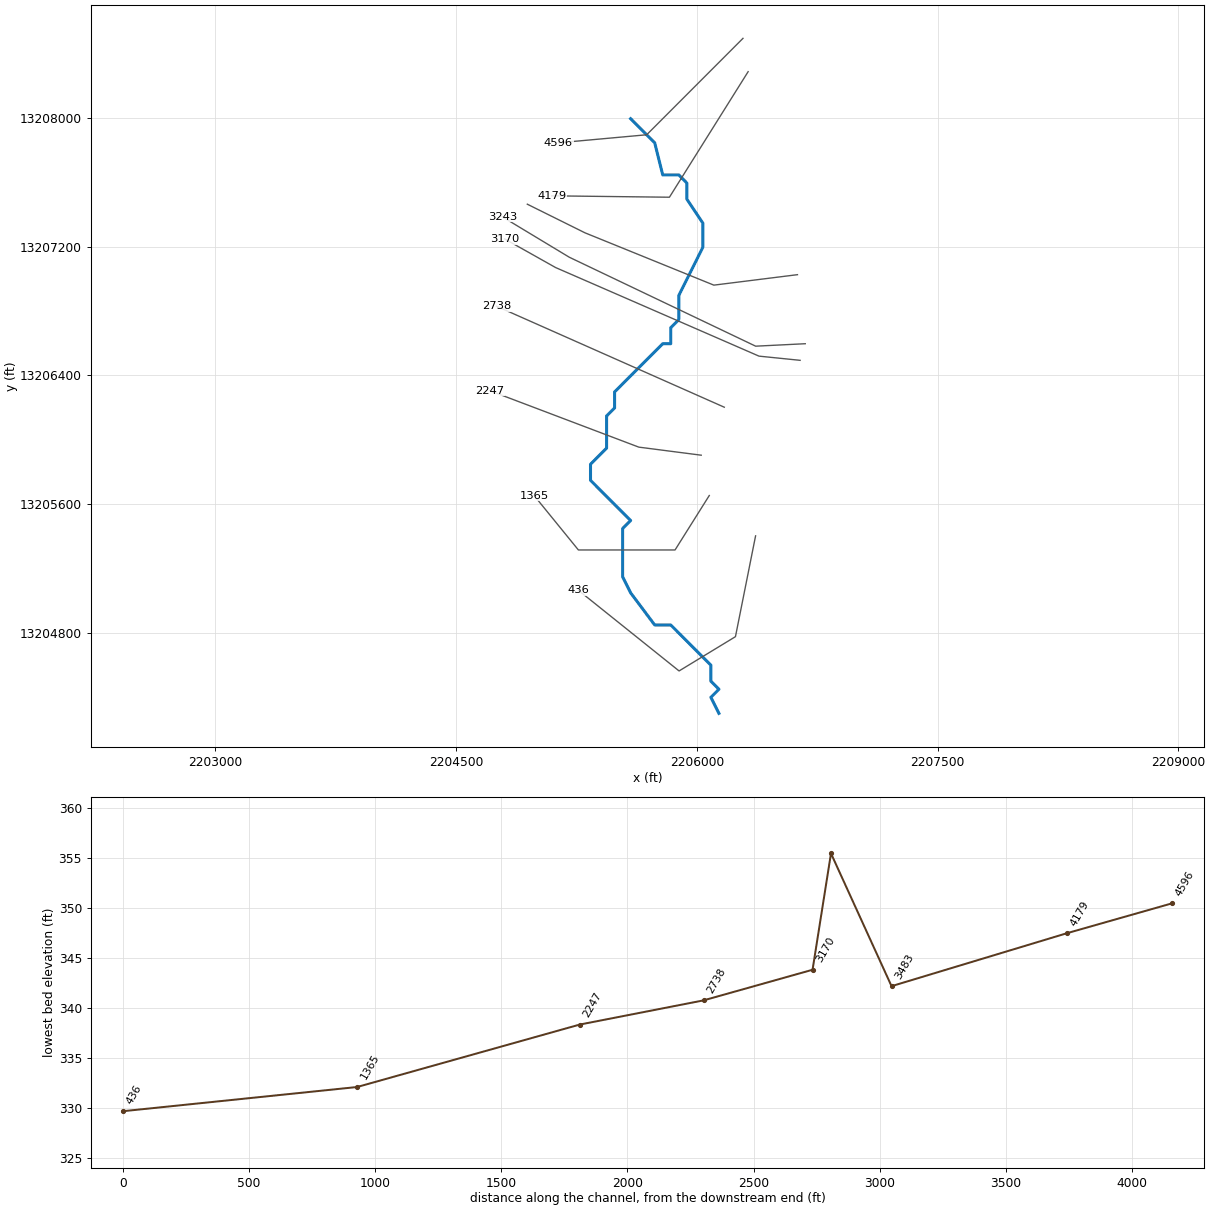
--- UNT 031 IN LACR.prj (project) ---

Proj Title=UNT 031 IN LACR Base Level Engineering
Current Plan=p01
Default Exp/Contr=0.3,0.1
English Units
Geom File=g01
Flow File=f01
Plan File=p01
BEGIN DESCRIPTION:
UNT 031 IN LACR
END DESCRIPTION:

--- UNT 031 IN LACR.p01 (plan) ---

Plan Title=Multiple Run
Short Identifier=Multiple
Geom File=g01
Flow File=f01
Subcritical Flow
K Sum by GR= 0
Std Step Tol= 0.01
Critical Tol= 0.01
Num of Std Step Trials= 20
Max Error Tol= 0.3
Flow Tol Ratio= 0.001
Split Flow NTrial= 30
Split Flow Tol= 0.02
Split Flow Ratio= 0.02
Log Output Level= 0
Friction Slope Method= 1
Unsteady Friction Slope Method= 2
Unsteady Bridges Friction Slope Method= 1
Parabolic Critical Depth
Global Vel Dist=  1 , 1 , 1
Global Log Level= 0
CheckData=True
Encroach Param= -1, 0, 0, 0
BEGIN DESCRIPTION:
Multiple Run
END DESCRIPTION:

--- UNT 031 IN LACR.f01 (steady flow) ---

Flow Title=Multiple
Number of Profiles=7
Profile Names=10-year,25-year,50-year,1pct_min,100-year,1pct_plu,500-year
River Rch & RM= UNT 031 IN LACR,Reach-1,4596
     220     308     382     349     472     639     732
River Rch & RM= UNT 031 IN LACR,Reach-1,3243
     274     388     484     445     602     815     947
Boundary for River Rch & Prof#=UNT 031 IN LACR,Reach-1,1
Up Type=0
Dn Type=3
Dn Slope=0.005
Boundary for River Rch & Prof#=UNT 031 IN LACR,Reach-1,2
Up Type=0
Dn Type=3
Dn Slope=0.005
Boundary for River Rch & Prof#=UNT 031 IN LACR,Reach-1,3
Up Type=0
Dn Type=3
Dn Slope=0.005
Boundary for River Rch & Prof#=UNT 031 IN LACR,Reach-1,4
Up Type=0
Dn Type=3
Dn Slope=0.005
Boundary for River Rch & Prof#=UNT 031 IN LACR,Reach-1,5
Up Type=0
Dn Type=3
Dn Slope=0.005
Boundary for River Rch & Prof#=UNT 031 IN LACR,Reach-1,6
Up Type=0
Dn Type=3
Dn Slope=0.005
Boundary for River Rch & Prof#=UNT 031 IN LACR,Reach-1,7
Up Type=0
Dn Type=3
Dn Slope=0.005

--- UNT 031 IN LACR.g01 (geometry) ---

Geom Title=Existing Conditions

River Reach=UNT 031 IN LACR,Reach-1
Reach XY= 30
      2205587.72     13207996.85      2205737.72     13207846.85
      2205787.72     13207646.85      2205887.72     13207646.85
      2205937.72     13207596.85      2205937.72     13207496.85
      2206037.72     13207346.85      2206037.72     13207196.85
      2205887.72     13206896.86      2205887.72     13206746.86
      2205837.72     13206696.85      2205837.72     13206596.86
      2205787.72     13206596.86      2205487.72     13206296.85
      2205487.72     13206196.85      2205437.72     13206146.85
      2205437.72     13205946.86      2205337.72     13205846.85
      2205337.72     13205746.86      2205587.72     13205496.85
      2205537.72     13205446.86      2205537.72     13205146.85
      2205587.72     13205046.85      2205737.72     13204846.85
      2205837.72     13204846.85      2206087.72     13204596.85
      2206087.72     13204496.85      2206137.72     13204446.86
      2206087.72     13204396.85      2206137.72     13204296.86

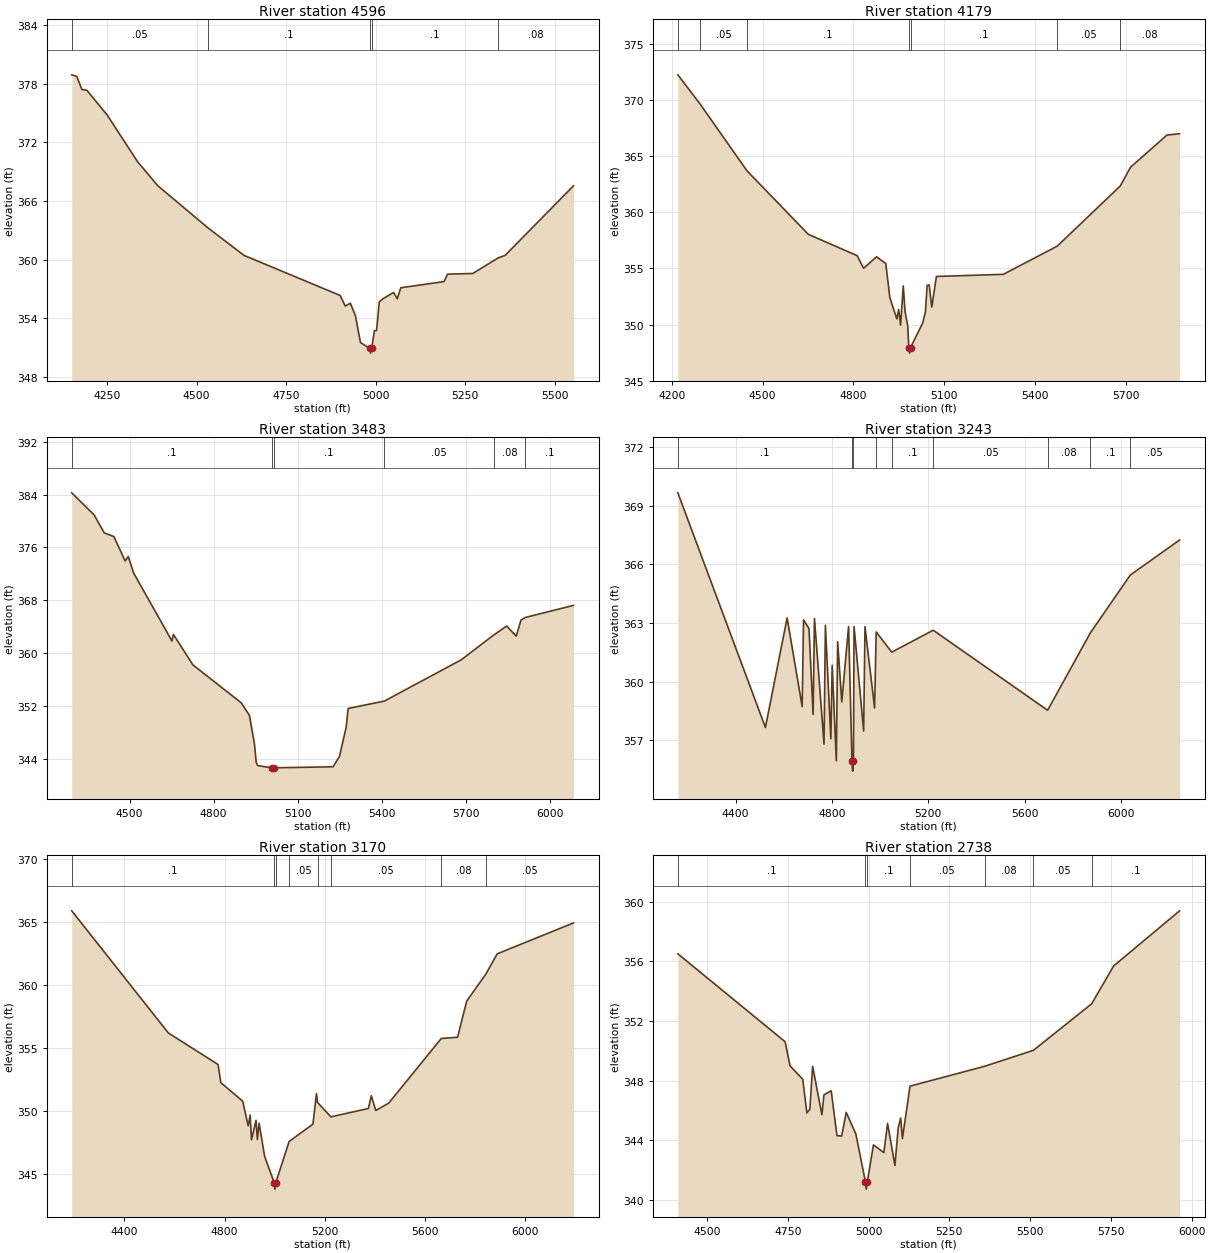
Type RM Length L Ch R = 1,4596,417,417,417
BEGIN DESCRIPTION:
UNT 031 IN LACR 4.0
END DESCRIPTION:
XS GIS Cut Line= 3
      2206287.70     13208496.84      2205687.72     13207896.86
      2205137.69     13207846.85
#Sta/Elev= 30
  4151.5  378.89  4165.6  378.73  4179.8  377.39  4193.9  377.31  4250.5  374.78
  4335.3  370.01  4391.9  367.55  4532.2  363.24  4632.3  360.44  4901.0  356.34
  4915.1  355.26  4929.3  355.55  4943.4  354.29  4957.6  351.53  4982.9  350.95
  4985.6  350.45  4988.9  350.95  4996.5  352.75  5002.5  352.75  5010.0  355.67
  5020.1  356.00  5050.2  356.65  5060.2  356.00  5070.3  357.13  5190.8  357.76
  5200.8  358.52  5271.1  358.59  5342.0  360.18  5361.5  360.44  5552.3  367.55
#Mann=5,-1,0
  4151.5    0.05       0  4532.2     0.1       0  4982.9    0.07       0
  4988.9     0.1       0  5342.0    0.08       0
Bank Sta=4982.9,4988.9
Exp/Cntr=0.3,0.1

Type RM Length L Ch R = 1,4179,696,696,696
BEGIN DESCRIPTION:
UNT 031 IN LACR 3.0
END DESCRIPTION:
XS GIS Cut Line= 3
      2206319.85     13208289.51      2205829.39     13207508.26
      2205095.89     13207516.94
#Sta/Elev= 30
  4220.4  372.22  4293.7  369.63  4448.6  363.68  4651.0  358.03  4812.4  356.13
  4833.6  355.01  4876.1  356.03  4906.7  355.43  4920.2  352.39  4943.2  350.50
  4949.1  351.34  4955.6  349.95  4964.4  353.44  4970.3  351.15  4979.2  349.90
  4982.6  347.96  4985.4  347.46  4988.6  347.96  5028.0  350.11  5037.4  351.09
  5043.3  353.48  5050.0  353.54  5058.6  351.55  5073.7  354.28  5294.5  354.47
  5472.2  356.97  5680.7  362.33  5714.6  364.00  5834.6  366.86  5876.4  366.98
#Mann=7,-1,0
  4220.4     0.1       0  4293.7    0.05       0  4448.6     0.1       0
  4982.6    0.07       0  4988.6     0.1       0  5472.2    0.05       0
  5680.7    0.08       0
Bank Sta=4982.6,4988.6
Exp/Cntr=0.3,0.1

Type RM Length L Ch R = 1,3483,240,240,240
BEGIN DESCRIPTION:
Mapping XS 4224571a
END DESCRIPTION:
XS GIS Cut Line= 4
      2206627.05     13207026.37      2206106.22     13206961.27
      2205303.27     13207286.79      2204943.98     13207464.85
#Sta/Elev= 30
  4293.3  384.27  4373.2  380.93  4409.4  378.20  4443.8  377.65  4484.1  373.96
  4495.1  374.64  4514.3  372.14  4651.3  361.85  4656.3  362.85  4726.0  358.24
  4898.5  352.51  4928.0  350.60  4946.0  346.27  4952.1  343.52  4957.5  343.00
  5008.1  342.66  5010.9  342.16  5014.1  342.66  5226.6  342.82  5249.6  344.38
  5273.7  348.82  5280.6  351.64  5410.1  352.76  5684.6  359.00  5801.3  362.78
  5847.0  364.11  5881.1  362.58  5898.0  365.00  5912.5  365.40  6085.6  367.24
#Mann=6,-1,0
  4293.3     0.1       0  5008.1    0.07       0  5014.1     0.1       0
  5410.1    0.05       0  5801.3    0.08       0  5912.5     0.1       0
Bank Sta=5008.1,5014.1
Exp/Cntr=0.3,0.1

Type RM Length L Ch R = 1,3243,73,73,73
BEGIN DESCRIPTION:
UNT 031 IN LACR 2.0
END DESCRIPTION:
XS GIS Cut Line= 4
      2206675.72     13206596.80      2206366.64     13206581.49
      2205205.61     13207134.88      2204787.76     13207386.71
#Sta/Elev= 30
  4160.0  369.65  4523.7  357.66  4613.8  363.26  4676.3  358.73  4681.9  363.16
  4704.6  362.71  4721.7  358.33  4727.3  363.23  4767.1  356.81  4772.7  362.88
  4795.4  357.08  4800.9  360.84  4818.1  355.96  4823.6  362.04  4840.8  358.97
  4869.0  362.82  4883.2  355.93  4885.9  355.43  4889.2  355.93  4891.7  362.82
  4931.6  357.48  4937.1  362.81  4977.0  358.66  4983.7  362.54  5048.4  361.51
  5220.5  362.63  5695.5  358.54  5873.3  362.50  6038.9  365.45  6243.5  367.24
#Mann=9,-1,0
  4160.0     0.1       0  4883.2    0.03       0  4889.2     0.1       0
  4983.7    0.05       0  5048.4     0.1       0  5220.5    0.05       0
  5695.5    0.08       0  5873.3     0.1       0  6038.9    0.05       0
Bank Sta=4883.2,4889.2
Exp/Cntr=0.3,0.1

Type RM Length L Ch R = 1,3170,432,432,432
BEGIN DESCRIPTION:
Mapping XS 583fa970
END DESCRIPTION:
XS GIS Cut Line= 4
      2206643.61     13206493.49      2206387.49     13206519.54
      2205120.13     13207070.75      2204803.27     13207248.71
#Sta/Elev= 30
  4190.0  365.86  4575.6  356.18  4774.0  353.68  4785.2  352.24  4872.5  350.77
  4894.3  348.82  4902.2  349.67  4907.6  347.71  4925.6  349.25  4931.0  347.73
  4937.9  349.03  4959.9  346.40  4998.4  344.30  5001.1  343.80  5004.4  344.30
  5057.8  347.58  5152.9  348.95  5166.9  351.38  5171.2  350.67  5224.5  349.53
  5374.1  350.19  5385.7  351.20  5403.7  350.03  5456.0  350.63  5665.0  355.74
  5730.2  355.84  5766.7  358.71  5842.9  360.84  5888.4  362.45  6192.9  364.90
#Mann=8,-1,0
  4190.0     0.1       0  4998.4    0.07       0  5004.4     0.1       0
  5057.8    0.05       0  5171.2     0.1       0  5224.5    0.05       0
  5665.0    0.08       0  5842.9    0.05       0
Bank Sta=4998.4,5004.4
Exp/Cntr=0.3,0.1

Type RM Length L Ch R = 1,2738,491,491,491
BEGIN DESCRIPTION:
Mapping XS 2c125b07
END DESCRIPTION:
XS GIS Cut Line= 2
      2206171.32     13206201.72      2204751.28     13206830.44
#Sta/Elev= 30
  4409.7  356.51  4741.7  350.62  4757.0  349.00  4796.4  348.10  4809.0  345.85
  4818.3  346.10  4826.9  348.97  4855.6  345.73  4862.0  347.06  4884.4  347.33
  4902.2  344.32  4916.7  344.30  4930.9  345.88  4960.5  344.45  4990.3  341.24
  4993.0  340.74  4996.3  341.24  5015.1  343.70  5047.4  343.19  5058.9  345.14
  5081.6  342.32  5091.7  344.83  5099.4  345.51  5104.9  344.13  5128.4  347.64
  5358.9  348.97  5510.2  350.04  5690.6  353.16  5758.8  355.70  5962.7  359.39
#Mann=7,-1,0
  4409.7     0.1       0  4990.3    0.07       0  4996.3     0.1       0
  5128.4    0.05       0  5358.9    0.08       0  5510.2    0.05       0
  5690.6     0.1       0
Bank Sta=4990.3,4996.3
Exp/Cntr=0.3,0.1

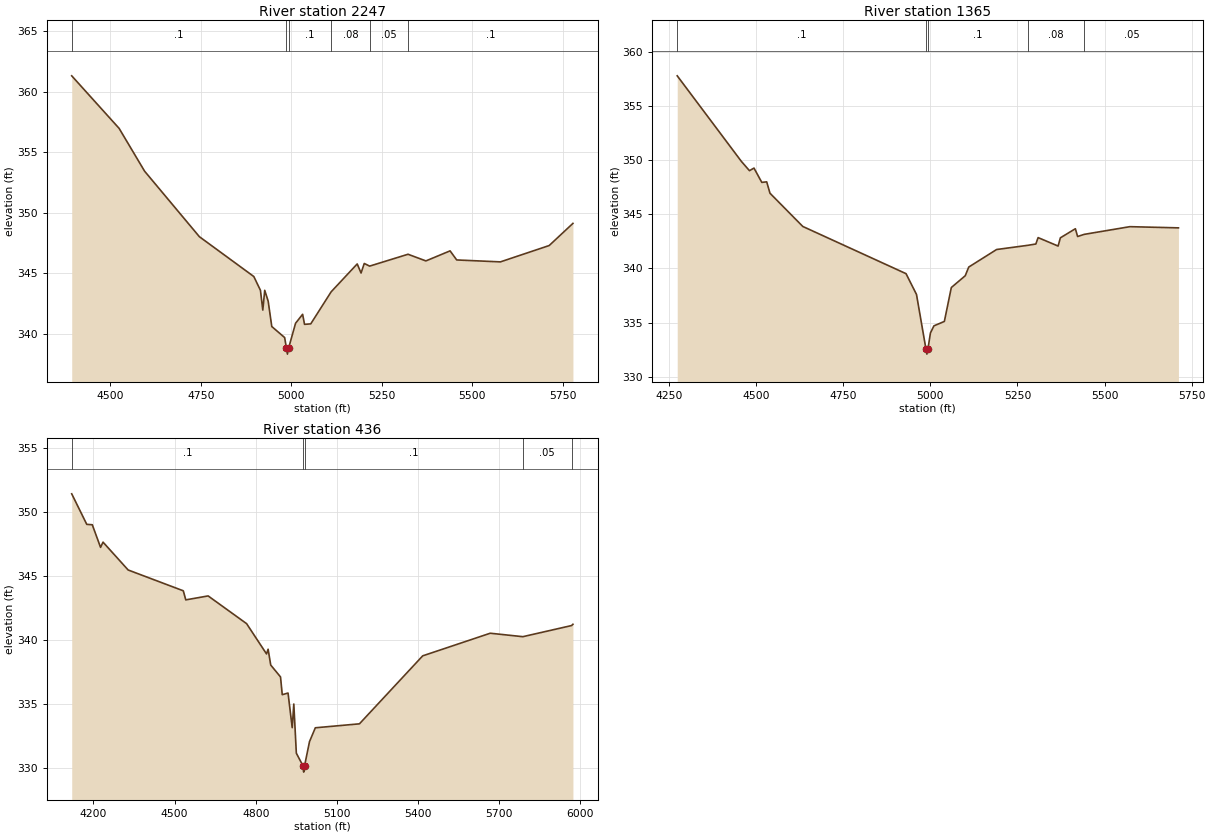
Type RM Length L Ch R = 1,2247,882,882,882
BEGIN DESCRIPTION:
Mapping XS 611c9cb6
END DESCRIPTION:
XS GIS Cut Line= 3
      2206027.50     13205903.20      2205638.59     13205953.39
      2204710.25     13206304.65
#Sta/Elev= 30
  4393.1  361.31  4524.0  356.97  4594.5  353.43  4745.8  348.02  4896.2  344.73
  4914.5  343.59  4921.0  341.96  4926.3  343.59  4935.8  342.70  4945.8  340.60
  4981.3  339.69  4986.3  338.82  4989.1  338.32  4992.3  338.82  5011.5  340.87
  5031.0  341.61  5036.3  340.78  5053.5  340.82  5109.9  343.47  5181.8  345.77
  5192.5  345.02  5201.3  345.81  5216.1  345.59  5322.2  346.57  5371.6  346.02
  5438.4  346.85  5456.7  346.10  5577.4  345.94  5712.2  347.29  5777.8  349.12
#Mann=6,-1,0
  4393.1     0.1       0  4986.3    0.07       0  4992.3     0.1       0
  5109.9    0.08       0  5216.1    0.05       0  5322.2     0.1       0
Bank Sta=4986.3,4992.3
Exp/Cntr=0.3,0.1

Type RM Length L Ch R = 1,1365,929,929,929
BEGIN DESCRIPTION:
Mapping XS 2e05ed22
END DESCRIPTION:
XS GIS Cut Line= 4
      2206077.70     13205652.33      2205864.41     13205313.57
      2205262.23     13205313.57      2204986.44     13205652.05
#Sta/Elev= 30
  4273.0  357.78  4456.9  349.89  4480.4  349.02  4493.4  349.26  4515.8  347.94
  4529.9  347.99  4539.3  346.94  4633.5  343.87  4930.0  339.51  4960.0  337.59
  4987.0  332.58  4989.8  332.08  4993.0  332.58  5000.0  334.03  5010.0  334.69
  5040.0  335.10  5060.0  338.23  5100.0  339.32  5110.0  340.12  5190.0  341.74
  5280.2  342.13  5302.7  342.25  5309.2  342.84  5366.6  342.06  5373.1  342.82
  5416.2  343.66  5422.6  342.94  5441.5  343.14  5572.7  343.85  5712.1  343.74
#Mann=5,-1,0
  4273.0     0.1       0  4987.0    0.07       0  4993.0     0.1       0
  5280.2    0.08       0  5441.5    0.05       0
Bank Sta=4987,4993
Exp/Cntr=0.3,0.1

Type RM Length L Ch R = 1,436,0,0,0
BEGIN DESCRIPTION:
UNT 031 IN LACR 1.0
END DESCRIPTION:
XS GIS Cut Line= 4
      2206366.22     13205401.36      2206240.77     13204774.13
      2205889.50     13204560.85      2205263.01     13205062.05
#Sta/Elev= 30
  4119.9  351.44  4175.5  349.05  4195.9  349.02  4226.5  347.25  4235.6  347.66
  4328.5  345.48  4532.4  343.85  4541.6  343.14  4624.2  343.45  4766.4  341.28
  4840.1  338.91  4845.9  339.28  4855.6  338.04  4891.8  337.11  4898.2  335.72
  4919.6  335.85  4935.0  333.14  4940.9  334.99  4950.3  331.14  4974.7  330.16
  4977.5  329.66  4980.7  330.16  4999.0  332.05  5020.5  333.13  5183.6  333.44
  5417.4  338.76  5667.1  340.53  5787.6  340.26  5967.7  341.13  5972.8  341.23
#Mann=5,-1,0
  4119.9     0.1       0  4974.7    0.07       0  4980.7     0.1       0
  5787.6    0.05       0  5967.7    0.08       0
Bank Sta=4974.7,4980.7
Exp/Cntr=0.3,0.1

Chan Stop Cuts=-1