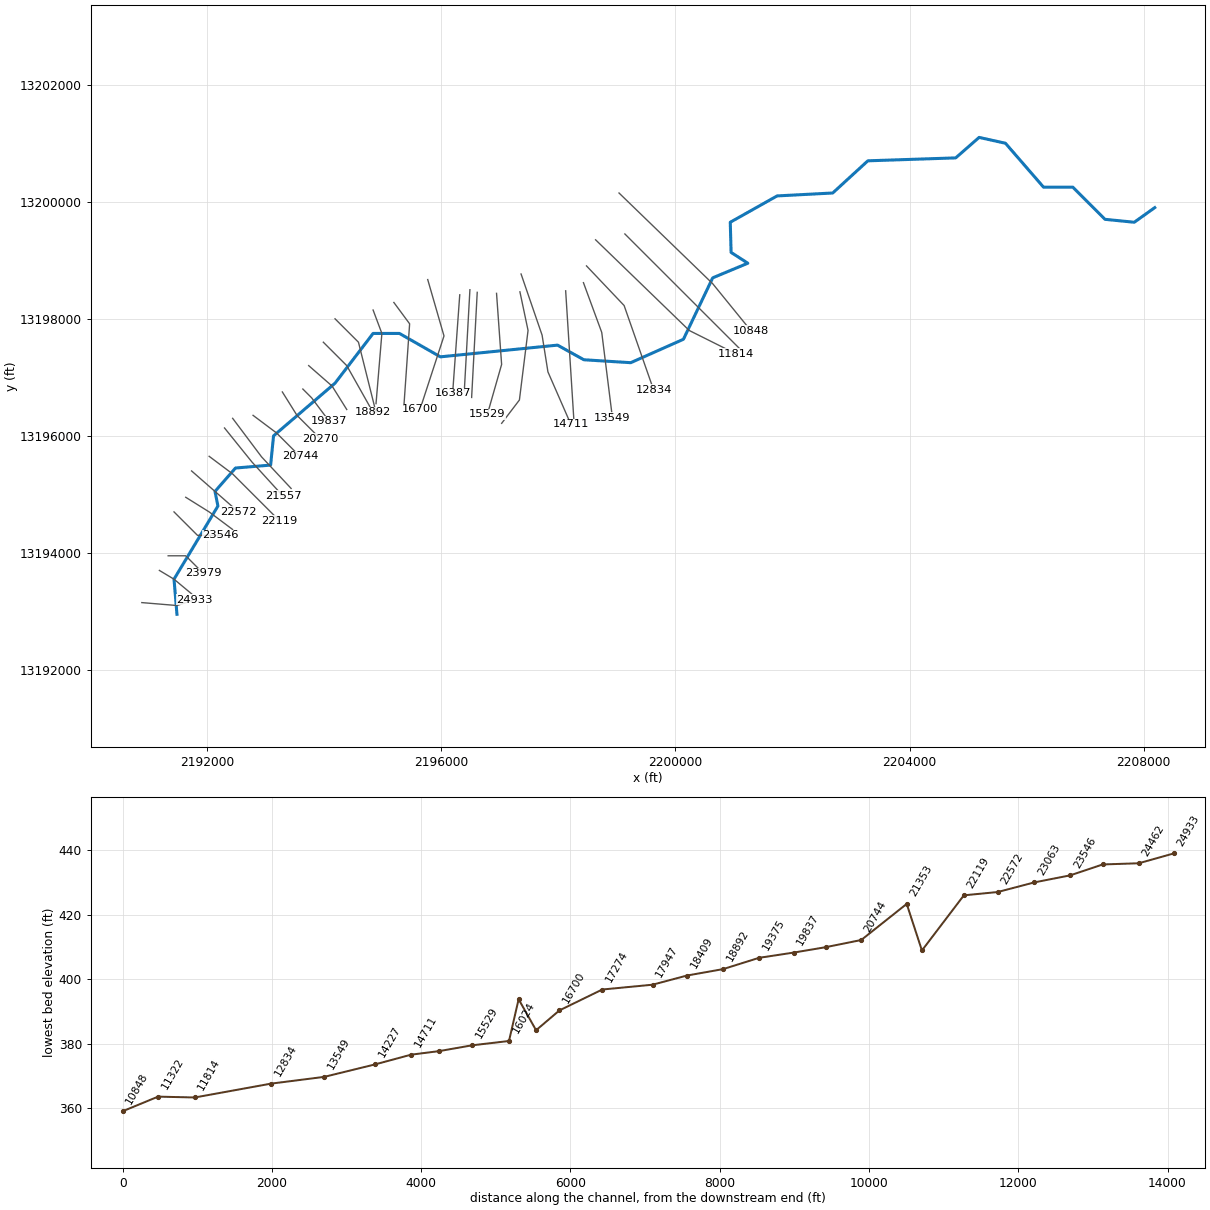
--- UNT 032 IN LACR.prj (project) ---

Proj Title=UNT 032 IN LACR Base Level Engineering
Current Plan=p01
Default Exp/Contr=0.3,0.1
English Units
Geom File=g01
Flow File=f01
Plan File=p01
Y Axis Title=Elevation
X Axis Title(PF)=Main Channel Distance
X Axis Title(XS)=Station
BEGIN DESCRIPTION:
UNT 032 IN LACR
END DESCRIPTION:
DSS Export Rating Curves= 0
DSS Export Rating Curve Sorted= 0
DSS Export Volume Flow Curves= 0
DXF OffsetX= 0
DXF OffsetY= 0
DXF ScaleX= 1
DXF ScaleY= 10

--- UNT 032 IN LACR.p01 (plan) ---

Plan Title=Multiple Run
Short Identifier=Multiple
Geom File=g01
Flow File=f01
Subcritical Flow
K Sum by GR= 0
Std Step Tol= 0.01
Critical Tol= 0.01
Num of Std Step Trials= 20
Max Error Tol= 0.3
Flow Tol Ratio= 0.001
Split Flow NTrial= 30
Split Flow Tol= 0.02
Split Flow Ratio= 0.02
Log Output Level= 0
Friction Slope Method= 1
Unsteady Friction Slope Method= 2
Unsteady Bridges Friction Slope Method= 1
Parabolic Critical Depth
Global Vel Dist=  1 , 1 , 1
Global Log Level= 0
CheckData=True
Encroach Param= -1, 0, 0, 0
BEGIN DESCRIPTION:
Multiple Run
END DESCRIPTION:

--- UNT 032 IN LACR.f01 (steady flow) ---

Flow Title=Multiple
Number of Profiles=7
Profile Names=10-year,25-year,50-year,1pct_min,100-year,1pct_plu,500-year
River Rch & RM= UNT 032 IN LACR,Reach-1,24933
     205     286     353     321     435     588     669
River Rch & RM= UNT 032 IN LACR,Reach-1,23546
     306     435     543     499     675     913    1061
River Rch & RM= UNT 032 IN LACR,Reach-1,14711
     500     724     917     852    1153    1559    1853
River Rch & RM= UNT 032 IN LACR,Reach-1,7468
     554     804    1019     948    1282    1734    2064
Boundary for River Rch & Prof#=UNT 032 IN LACR,Reach-1,1
Up Type=0
Dn Type=3
Dn Slope=0.005
Boundary for River Rch & Prof#=UNT 032 IN LACR,Reach-1,2
Up Type=0
Dn Type=3
Dn Slope=0.005
Boundary for River Rch & Prof#=UNT 032 IN LACR,Reach-1,3
Up Type=0
Dn Type=3
Dn Slope=0.005
Boundary for River Rch & Prof#=UNT 032 IN LACR,Reach-1,4
Up Type=0
Dn Type=3
Dn Slope=0.005
Boundary for River Rch & Prof#=UNT 032 IN LACR,Reach-1,5
Up Type=0
Dn Type=3
Dn Slope=0.005
Boundary for River Rch & Prof#=UNT 032 IN LACR,Reach-1,6
Up Type=0
Dn Type=3
Dn Slope=0.005
Boundary for River Rch & Prof#=UNT 032 IN LACR,Reach-1,7
Up Type=0
Dn Type=3
Dn Slope=0.005

--- UNT 032 IN LACR.g01 (geometry) ---

Geom Title=Existing Conditions
Program Version=4.10

River Reach=UNT 032 IN LACR ,Reach-1
Reach XY= 30
      2191487.72     13192946.85      2191437.72     13193546.85
      2192187.72     13194796.86      2192137.72     13195046.85
      2192487.72     13195446.86      2193087.72     13195496.85
      2193137.72     13195996.85      2194187.72     13196896.86
      2194837.72     13197746.86      2195287.72     13197746.86
      2195987.72     13197346.85      2197987.72     13197546.86
      2198437.72     13197296.85      2199237.72     13197246.86
      2200137.72     13197646.85      2200637.72     13198696.86
      2201237.72     13198946.85      2200951.92     13199131.58
      2200937.72     13199646.85      2201737.72     13200096.85
      2202687.72     13200146.85      2203287.72     13200696.86
      2204787.72     13200746.85      2205187.72     13201096.85
      2205637.72     13200996.86      2206287.72     13200246.85
      2206787.72     13200246.85      2207337.72     13199696.86
      2207837.72     13199646.85      2208187.72     13199896.85

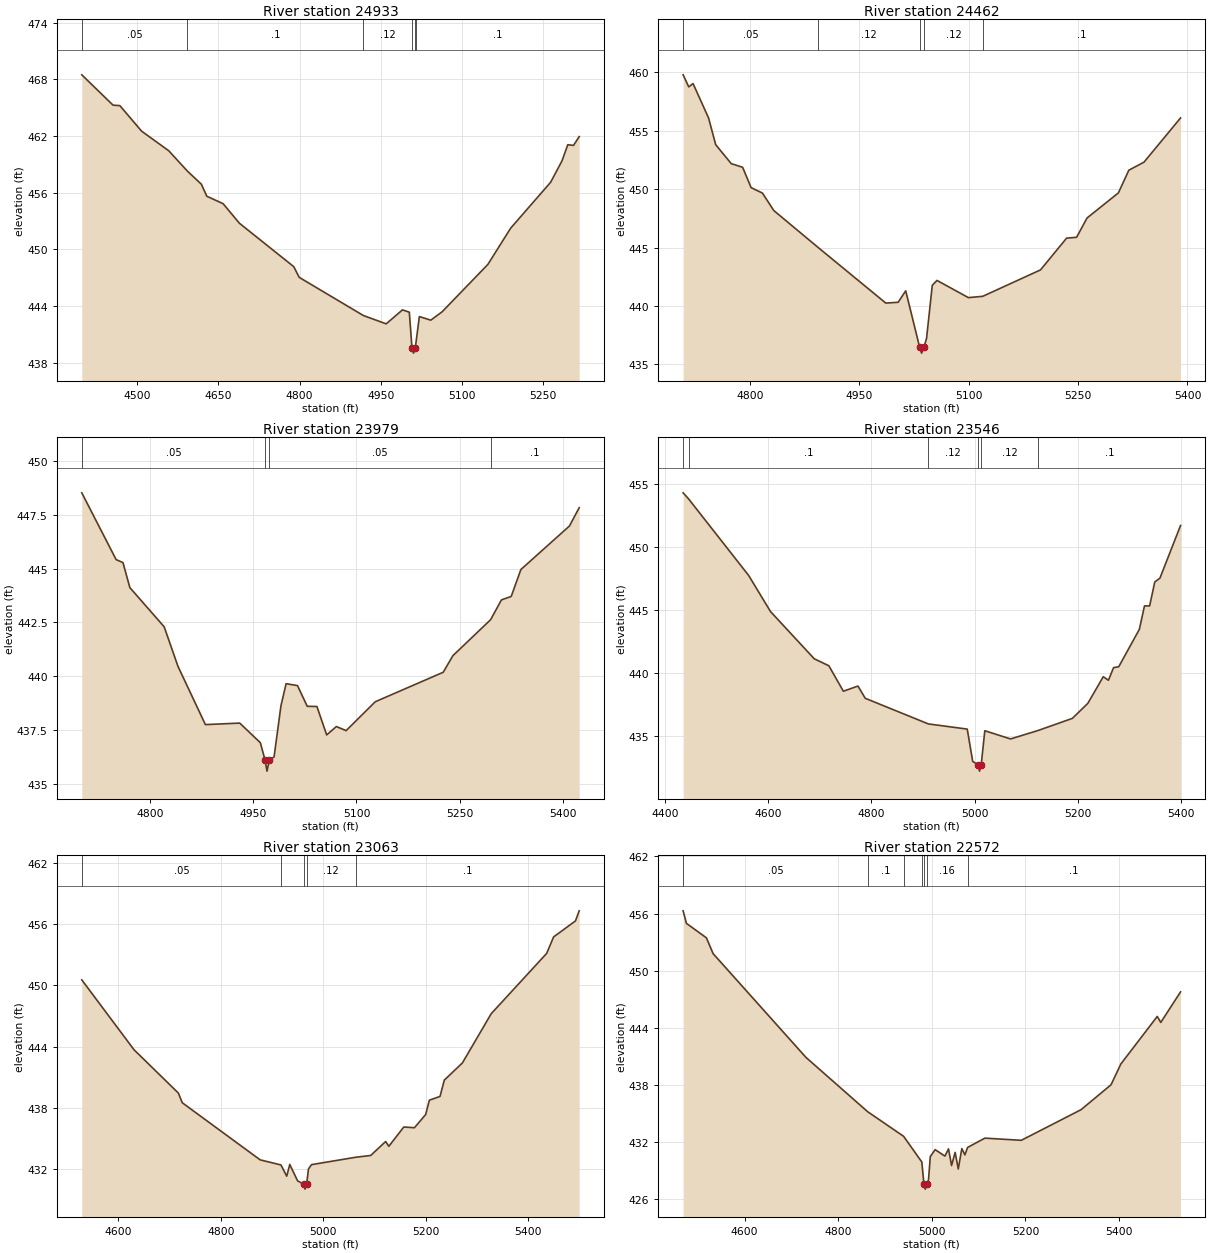
Type RM Length L Ch R = 1 ,24933   ,471,471,471
BEGIN DESCRIPTION:
UNT 032 IN LACR 40.0
END DESCRIPTION:
XS GIS Cut Line= 3
       2190887.7     13193146.86      2191487.72     13193096.85
      2191787.69     13193196.85
#Sta/Elev= 30
  4397.9  468.49  4455.6  465.28  4468.2  465.23  4508.3  462.53  4558.5  460.45
    4593  458.29  4618.7  456.91  4628.7  455.64  4658.8  454.85  4688.9  452.78
  4789.3  448.18  4799.3  447.05  4917.8  443.01  4959.9  442.13    4990  443.61
  5002.6  443.36  5007.5  439.53  5010.3  439.03  5013.5  439.53  5015.2  440.28
  5021.1   442.9  5042.2  442.52  5063.2  443.41  5147.6  448.42  5189.7  452.26
  5263.5  457.12  5284.6   459.4  5295.1  461.09  5305.7  461.02  5316.2  461.95
#Mann= 6 ,-1 , 0
  4397.9     .05       0    4593      .1       0  4917.8     .12       0
  5007.5     .07       0  5013.5     .12       0  5015.2      .1       0
Bank Sta=5007.5,5013.5
XS Rating Curve= 0 ,0
Exp/Cntr=0.3,0.1

Type RM Length L Ch R = 1 ,24462   ,483,483,483
BEGIN DESCRIPTION:
UNT 032 IN LACR 39.0
END DESCRIPTION:
XS GIS Cut Line= 3
      2191187.76     13193696.83      2191437.72     13193546.85
      2191737.71     13193296.86
#Sta/Elev= 30
  4708.5  459.78  4716.2  458.75  4722.1  459.03  4743.4  456.09  4753.2   453.8
  4774.5  452.18  4790.1  451.87  4801.7  450.13  4817.3  449.66  4832.8  448.17
  4893.8     445  4986.4  440.25  5003.3  440.32  5013.7   441.3  5032.8  436.47
  5035.5  435.97  5038.8  436.47  5042.3  437.25  5050.1  441.77  5056.6  442.19
  5099.6  440.72  5119.3  440.83  5198.5  443.09  5234.3  445.81    5248  445.88
  5262.3  447.53  5305.3  449.68  5319.6  451.62  5340.4  452.31  5390.5  456.09
#Mann= 5 ,-1 , 0
  4708.5     .05       0  4893.8     .12       0  5032.8     .07       0
  5038.8     .12       0  5119.3      .1       0
Bank Sta=5032.8,5038.8
XS Rating Curve= 0 ,0
Exp/Cntr=0.3,0.1

Type RM Length L Ch R = 1 ,23979   ,433,433,433
BEGIN DESCRIPTION:
UNT 032 IN LACR 38.0
END DESCRIPTION:
XS GIS Cut Line= 3
      2191337.72     13193946.85      2191637.72     13193946.86
      2191937.75     13193646.83
#Sta/Elev= 30
    4700  448.52    4750  445.42    4760  445.28    4770  444.12    4820   442.3
    4840  440.47    4880  437.76    4930  437.83    4960  436.92    4967   436.1
  4969.7   435.6    4973   436.1    4980  436.26    4990  438.63  4997.5  439.66
  5014.1  439.57  5028.3  438.61  5042.4   438.6  5056.6  437.28  5070.7  437.67
  5084.9  437.48  5127.3  438.82  5226.3  440.19  5240.4  440.96  5295.3  442.63
  5311.1  443.55  5325.3  443.71  5339.4  444.96  5410.1  446.98  5424.3  447.83
#Mann= 4 ,-1 , 0
    4700     .05       0    4967     .04       0    4973     .05       0
  5295.3      .1       0
Bank Sta=4967,4973
XS Rating Curve= 0 ,0
Exp/Cntr=0.3,0.1

Type RM Length L Ch R = 1 ,23546   ,483,483,483
BEGIN DESCRIPTION:
UNT 032 IN LACR 37.0
END DESCRIPTION:
XS GIS Cut Line= 3
      2191437.71     13194696.87      2191837.72     13194296.86
      2192237.72     13194296.85
#Sta/Elev= 30
  4434.3  454.28  4444.9   453.8  4561.6  447.73    4604  444.87  4688.9  441.13
  4717.2  440.58  4745.4  438.56  4773.7  438.97  4787.9     438  4910.4  435.97
  4985.9  435.56  4996.5     433    5007  432.73  5009.7  432.23    5013  432.73
    5020  435.43    5070  434.78  5123.5  435.45    5190  436.41    5220   437.6
    5250  439.71    5260  439.43    5270  440.43    5280   440.5    5320  443.46
    5330  445.32    5340  445.32    5350  447.22    5360  447.52    5400  451.69
#Mann= 6 ,-1 , 0
  4434.3     .05       0  4444.9      .1       0  4910.4     .12       0
    5007     .07       0    5013     .12       0  5123.5      .1       0
Bank Sta=5007,5013
XS Rating Curve= 0 ,0
Exp/Cntr=0.3,0.1

Type RM Length L Ch R = 1 ,23063   ,491,491,491
BEGIN DESCRIPTION:
UNT 032 IN LACR 36.0
END DESCRIPTION:
XS GIS Cut Line= 3
      2191637.72     13194946.86      2192037.72     13194696.85
      2192437.72     13194396.85
#Sta/Elev= 30
  4528.3  450.55  4630.3   443.7    4717  439.45  4724.6   438.5  4876.8   432.9
  4917.4   432.4  4928.7   431.3  4934.6  432.45  4949.9  430.84  4961.6  430.53
  4964.4  430.03  4967.6  430.53  4971.1     432    4977  432.43    5064  433.16
  5092.7  433.33  5121.9   434.7  5128.1  434.23  5157.3  436.12  5178.1  436.05
    5200  437.34  5207.3  438.75  5228.1  439.12  5236.5  440.72  5271.9  442.41
  5328.1  447.23  5436.5  453.15    5450  454.76  5492.7  456.33    5500  457.32
#Mann= 5 ,-1 , 0
  4528.3     .05       0  4917.4     .12       0  4961.6     .07       0
  4967.6     .12       0    5064      .1       0
Bank Sta=4961.6,4967.6
XS Rating Curve= 0 ,0
Exp/Cntr=0.3,0.1

Type RM Length L Ch R = 1 ,22572   ,453,453,453
BEGIN DESCRIPTION:
UNT 032 IN LACR 35.0
END DESCRIPTION:
XS GIS Cut Line= 3
      2191737.73     13195396.85      2192137.72     13195046.85
      2192537.72     13194696.86
#Sta/Elev= 30
  4468.5  456.29  4475.6  454.97  4518.3  453.45  4532.6  451.79  4730.9  440.89
  4862.8  435.18  4939.7  432.59  4978.6  429.89  4983.2  427.54    4986  427.04
  4989.2  427.54  4992.9  428.02  4996.7  430.46  5007.1  431.19    5028  430.51
  5035.6  431.27  5042.2  429.52  5049.8   430.9  5056.5  429.16  5064.1   431.3
  5070.7  430.64  5076.4  431.42  5113.4   432.4  5191.2  432.17  5318.9  435.39
    5383  438.01  5403.9  440.19  5481.7  445.19  5489.3  444.56  5531.5  447.77
#Mann= 7 ,-1 , 0
  4468.5     .05       0  4862.8      .1       0  4939.7     .05       0
  4978.6     .16       0  4983.2     .07       0  4989.2     .16       0
  5076.4      .1       0
Bank Sta=4983.2,4989.2
XS Rating Curve= 0 ,0
Exp/Cntr=0.3,0.1

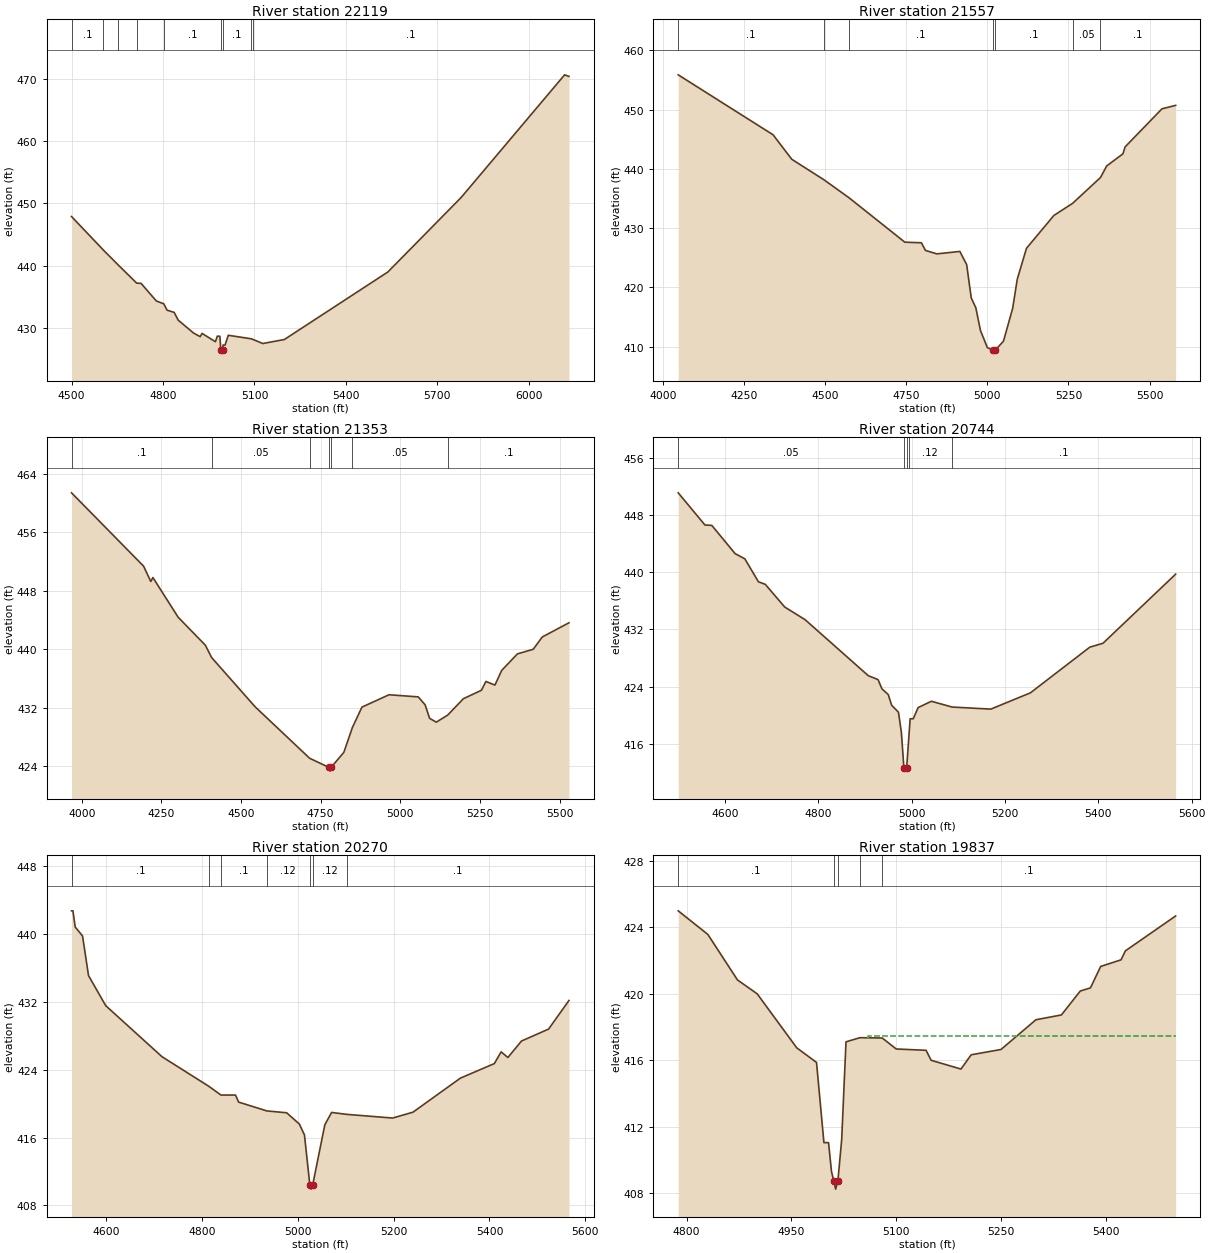
Type RM Length L Ch R = 1 ,22119   ,562,562,562
BEGIN DESCRIPTION:
UNT 032 IN LACR 34.0
END DESCRIPTION:
XS GIS Cut Line= 3
      2192037.72     13195646.85      2192437.72     13195346.85
      2193237.74     13194546.83
#Sta/Elev= 30
    4500  447.91    4604  442.56  4653.5  440.13  4713.7  437.24  4728.1   437.2
  4778.1  434.38  4802.4  433.93  4813.5   432.9  4836.5  432.55    4850   431.3
    4900  429.25  4921.9  428.66  4928.1  429.18  4971.9  427.85  4978.1  428.74
  4986.5  428.72  4989.7  426.52  4992.5  426.02  4995.7  426.52  4996.9  427.31
  5003.5  427.31  5014.1  428.88  5089.2  428.32  5094.8  428.22  5127.3  427.56
    5198   428.2  5537.4  439.02  5777.8  450.96  6117.2  470.62  6131.4  470.37
#Mann= 9 ,-1 , 0
    4500      .1       0    4604     .05       0  4653.5      .1       0
  4713.7     .05       0  4802.4      .1       0  4989.7     .07       0
  4995.7      .1       0  5089.2     .16       0  5094.8      .1       0
Bank Sta=4989.7,4995.7
XS Rating Curve= 0 ,0
Exp/Cntr=0.3,0.1

Type RM Length L Ch R = 1 ,21557   ,204,204,204
BEGIN DESCRIPTION:
UNT 032 IN LACR 33.0
END DESCRIPTION:
XS GIS Cut Line= 3
      2192300.26     13196130.94      2192768.98     13195549.38
      2193298.51     13194967.76
#Sta/Elev= 30
  4046.8  455.86  4339.3  445.74  4396.9  441.61  4495.8  438.16  4571.9  435.18
  4745.5  427.62  4796.5  427.52    4809  426.23  4844.2  425.65  4915.1  426.06
  4936.1  423.83  4950.2  418.22  4964.4  416.54  4978.6  412.72    5000  409.82
  5018.2   409.4  5020.9   408.9  5024.2   409.4  5049.6  410.92  5077.9  416.46
  5092.1  421.37  5120.5  426.59    5205  432.13  5262.6  434.17  5348.6  438.53
  5367.8  440.48  5417.8  442.53  5424.6   443.7  5538.1  450.12  5580.3  450.71
#Mann= 7 ,-1 , 0
  4046.8      .1       0  4495.8     .05       0  4571.9      .1       0
  5018.2     .07       0  5024.2      .1       0  5262.6     .05       0
  5348.6      .1       0
Bank Sta=5018.2,5024.2
XS Rating Curve= 0 ,0
Exp/Cntr=0.3,0.1

Type RM Length L Ch R = 1 ,21353   ,609,609,609
BEGIN DESCRIPTION:
UNT 032 IN LACR 32.0
END DESCRIPTION:
XS GIS Cut Line= 3
      2192439.15     13196295.87      2192933.91     13195636.18
      2193437.39     13195097.98
#Sta/Elev= 30
    3968  461.37  4194.3  451.35  4216.8  449.26  4223.5   449.8  4302.7  444.38
  4388.1  440.56  4407.9  438.87  4544.3  432.15  4715.4  425.12  4776.7  423.86
  4779.5  423.36  4782.7  423.86    4823  425.93  4849.5  429.29  4879.7   432.1
  4964.7  433.79  5056.5   433.5    5078  432.42  5092.2  430.57  5113.2  430.05
  5148.9  431.01  5198.2  433.25  5254.8   434.4    5269  435.61  5297.3  435.11
  5318.4  437.11  5367.7  439.37  5417.5     440  5445.8  441.68  5529.6  443.62
#Mann= 7 ,-1 , 0
    3968      .1       0  4407.9     .05       0  4715.4      .1       0
  4776.7     .03       0  4782.7      .1       0  4849.5     .05       0
  5148.9      .1       0
Bank Sta=4776.7,4782.7
XS Rating Curve= 0 ,0
Exp/Cntr=0.3,0.1

Type RM Length L Ch R = 1 ,20744   ,474,474,474
BEGIN DESCRIPTION:
UNT 032 IN LACR 31.0
END DESCRIPTION:
XS GIS Cut Line= 3
      2192787.72     13196346.85      2193187.72     13196046.85
      2193587.73     13195646.84
#Sta/Elev= 30
    4500  451.15  4557.3  446.64  4571.9  446.59  4621.9  442.63  4642.7   441.9
  4671.9  438.68  4686.5  438.33  4728.1  435.15  4771.9  433.37  4907.3  425.52
  4928.1  424.98  4936.5  423.68    4950  422.88  4957.3  421.38  4971.9   420.4
  4978.1   417.6  4983.5  412.65  4986.2  412.15  4989.5  412.65  4993.5  416.36
  4996.9  419.49  5003.5  419.49  5014.1  421.06  5042.4  421.94  5086.8  421.13
  5169.7  420.84  5254.6  423.12  5381.8  429.52  5410.1  430.07  5565.7  439.75
#Mann= 5 ,-1 , 0
    4500     .05       0  4983.5     .07       0  4989.5     .05       0
  4993.5     .12       0  5086.8      .1       0
Bank Sta=4983.5,4989.5
XS Rating Curve= 0 ,0
Exp/Cntr=0.3,0.1

Type RM Length L Ch R = 1 ,20270   ,433,433,433
BEGIN DESCRIPTION:
UNT 032 IN LACR 30.0
END DESCRIPTION:
XS GIS Cut Line= 3
      2193287.72     13196746.86      2193537.72     13196346.85
      2193937.73     13195946.84
#Sta/Elev= 30
  4528.3  442.74  4531.2  442.74    4536  440.83  4551.3  439.77  4563.7  435.11
  4599.6  431.56    4717  425.54    4815  422.04  4839.9  421.02  4870.3  421.02
  4876.8  420.19  4935.7  419.15    4977  418.93  5003.5   417.6  5014.1  416.32
  5025.3  410.43    5028  409.93  5031.3  410.43  5056.6  417.52  5070.7  418.97
    5103  418.74    5198  418.31  5240.4     419  5339.4  423.02  5410.1  424.73
  5424.3  426.11  5438.4  425.45  5466.7  427.39  5523.3   428.8  5565.7  432.17
#Mann= 7 ,-1 , 0
  4528.3      .1       0    4815     .05       0  4839.9      .1       0
  4935.7     .12       0  5025.3     .07       0  5031.3     .12       0
    5103      .1       0
Bank Sta=5025.3,5031.3
XS Rating Curve= 0 ,0
Exp/Cntr=0.3,0.1

Type RM Length L Ch R = 1 ,19837   ,462,462,462
BEGIN DESCRIPTION:
UNT 032 IN LACR 29.0
END DESCRIPTION:
XS GIS Cut Line= 3
      2193637.74     13196796.83      2193787.72     13196646.85
      2194087.72     13196246.85
#Sta/Elev= 30
  4787.9     425  4830.3  423.58  4872.7  420.84    4901     420  4957.6  416.75
  4985.9  415.87  4996.5  411.04  5003.1  411.04  5007.3  409.31  5010.5  408.74
  5013.3  408.24  5016.5  408.74  5021.9  411.21  5028.1  417.11    5048  417.36
    5080  417.34    5100  416.68  5142.7   416.6    5150     416  5192.7  415.47
  5207.3  416.33    5250  416.65    5300  418.44  5336.5  418.73  5363.5  420.17
  5378.1  420.36  5392.7  421.65  5421.9  422.05  5428.1  422.59    5500  424.69
#Mann= 5 ,-1 , 0
  4787.9      .1       0  5010.5     .07       0  5016.5      .1       0
    5048     .12       0    5080      .1       0
#XS Ineff= 2 , 0
                          5060.2          417.45
Permanent Ineff=
       F       F
Bank Sta=5010.5,5016.5
XS Rating Curve= 0 ,0
Exp/Cntr=0.3,0.1

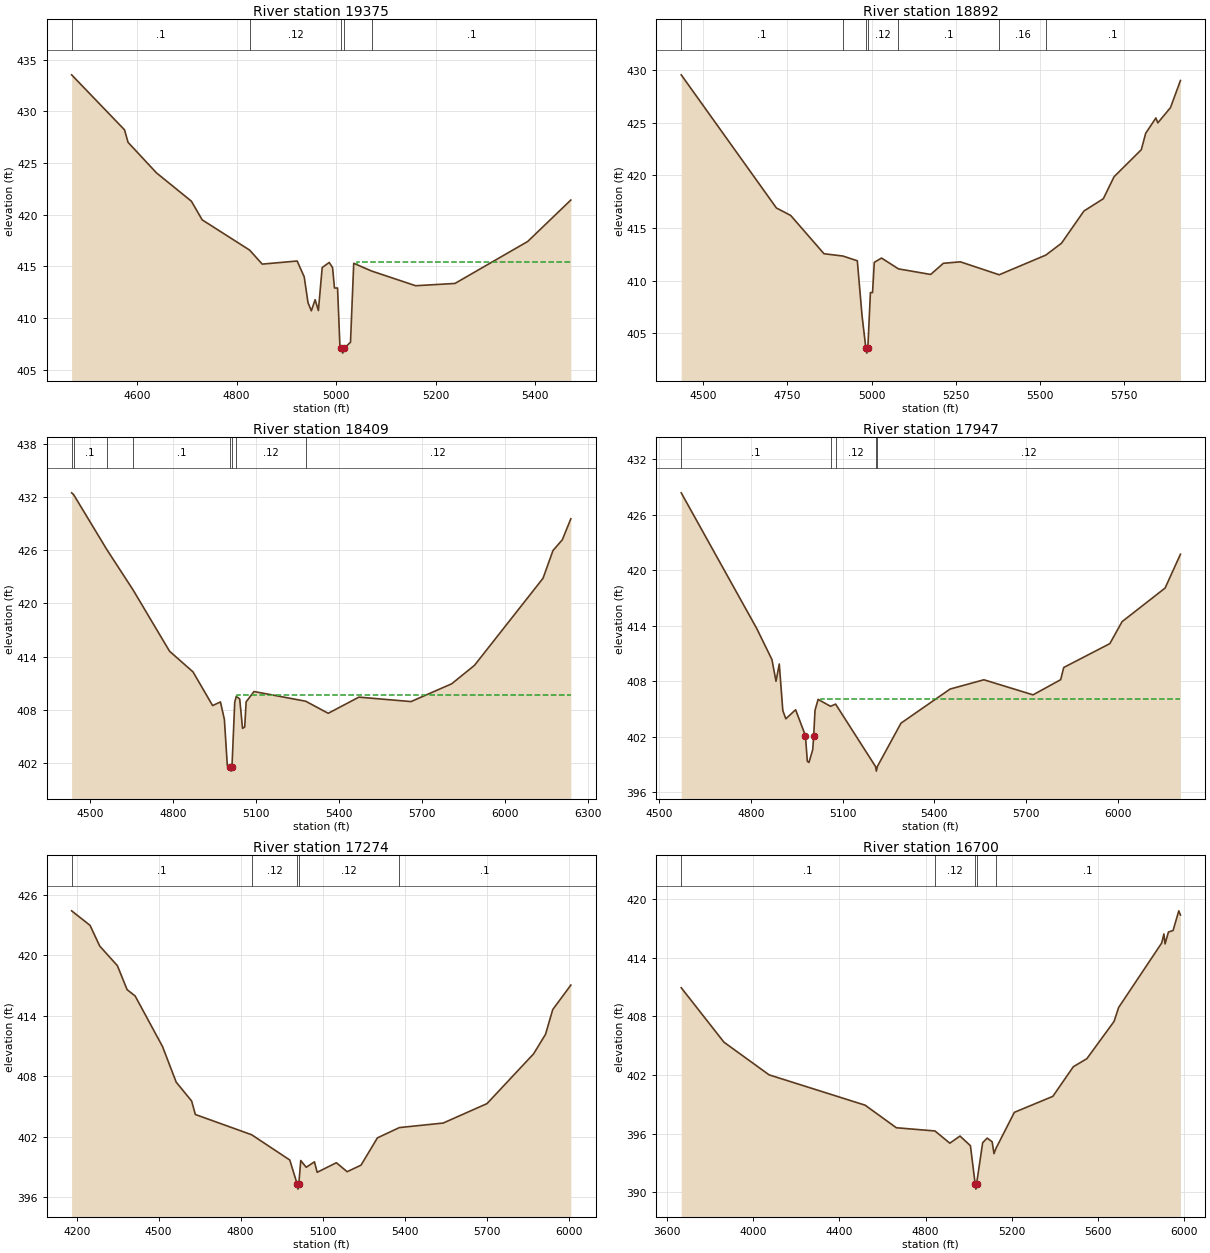
Type RM Length L Ch R = 1 ,19375   ,483,483,483
BEGIN DESCRIPTION:
UNT 032 IN LACR 28.0
END DESCRIPTION:
XS GIS Cut Line= 3
      2193737.73     13197196.85      2194137.72     13196846.85
      2194387.72     13196446.85
#Sta/Elev= 30
  4468.5  433.54  4574.8  428.22  4581.9  427.01  4638.9  424.06  4709.1  421.32
  4730.9  419.51  4826.1  416.59  4851.5  415.23  4921.7  415.53  4935.9     414
  4943.5  411.51  4950.2  410.71  4957.8  411.79  4964.4  410.74    4972   414.9
  4986.2  415.39  4992.9  414.89  4996.7  412.92  5002.9  412.92  5007.7  407.23
  5010.6  407.12  5013.3  406.62  5016.6  407.12  5028.9  407.67  5035.4  415.31
  5071.4  414.56  5159.8  413.14  5238.8  413.36    5385  417.42  5471.7  421.43
#Mann= 5 ,-1 , 0
  4468.5      .1       0  4826.1     .12       0  5010.6     .07       0
  5016.6     .12       0  5071.4      .1       0
#XS Ineff= 2 , 0
         4981.63  415.13 5042.86          415.39
Permanent Ineff=
       F       F
Bank Sta=5010.6,5016.6
XS Rating Curve= 0 ,0
Exp/Cntr=0.3,0.1

Type RM Length L Ch R = 1 ,18892   ,483,483,483
BEGIN DESCRIPTION:
UNT 032 IN LACR 27.0
END DESCRIPTION:
XS GIS Cut Line= 3
      2193987.71     13197596.87      2194387.72     13197196.85
      2194837.73     13196396.84
#Sta/Elev= 30
  4434.3  429.57  4717.2  416.91  4759.6   416.2  4858.6  412.56  4914.9  412.34
  4957.6  411.89  4971.7  406.66  4982.9  403.61  4985.6  403.11  4988.9  403.61
  4996.5  408.87  5002.9  408.87    5008  411.74  5029.6  412.15  5079.9  411.12
  5175.6  410.59  5213.2  411.65  5263.9  411.79  5379.2  410.56  5517.8  412.43
  5564.4  413.56    5631  416.62  5688.7  417.79  5720.6  419.88  5801.5  422.45
  5814.6  424.01  5844.9  425.47  5850.6     425  5888.2  426.45  5917.9  429.03
#Mann= 7 ,-1 , 0
  4434.3      .1       0  4914.9     .12       0  4982.9     .07       0
  4988.9     .12       0  5079.9      .1       0  5379.2     .16       0
  5517.8      .1       0
#XS Ineff= 2 , 0
                         5029.09          412.05
Permanent Ineff=
       F       F
Bank Sta=4982.9,4988.9
XS Rating Curve= 0 ,0
Exp/Cntr=0.3,0.1

Type RM Length L Ch R = 1 ,18409   ,462,462,462
BEGIN DESCRIPTION:
UNT 032 IN LACR 26.0
END DESCRIPTION:
XS GIS Cut Line= 3
      2194187.71     13197996.87      2194587.72     13197596.85
      2194887.71     13196396.89
#Sta/Elev= 30
  4434.3  432.45  4441.3  432.26  4561.1  426.08  4655.8  421.54  4787.9  414.62
  4872.7  412.29  4943.4   408.5  4971.7  408.91  4985.9  406.94  4996.5  401.74
  5007.3  401.62  5010.1  401.12  5013.3  401.62  5023.2  408.86    5029  409.56
  5041.2  409.24  5051.5  405.93  5059.3  406.09  5064.4  408.92  5092.8  410.08
  5279.5  408.99  5360.8  407.63  5471.6  409.45  5659.7  408.95  5806.6  410.95
    5889  413.03  6136.4  422.83  6172.5  425.96    6206  427.16  6236.9  429.53
#Mann= 8 ,-1 , 0
  4434.3     .08       0  4441.3      .1       0  4561.1     .08       0
  4655.8      .1       0  5007.3     .07       0  5013.3      .1       0
    5029     .12       0  5279.5     .12       0
#XS Ineff= 2 , 0
       0                 5031.01       0  409.72
Permanent Ineff=
       F       T
Bank Sta=5007.3,5013.3
XS Rating Curve= 0 ,0
Exp/Cntr=0.3,0.1

Type RM Length L Ch R = 1 ,17947   ,673,673,673
BEGIN DESCRIPTION:
UNT 032 IN LACR 25.0
END DESCRIPTION:
XS GIS Cut Line= 3
      2194837.72     13198146.85      2194987.72     13197746.86
      2194887.72     13196546.81
#Sta/Elev= 30
  4572.8  428.37  4819.3  413.71  4869.2  410.34  4882.5  407.99  4893.2  409.86
  4904.8  404.82  4914.6  403.93  4946.6  404.91  4978.6  402.12  4984.9  399.33
  4990.2  399.21  5002.5  400.59 5005.68  402.09    5010  404.85  5020.1  406.03
  5060.8  405.28  5077.3  405.52  5207.7  398.77  5210.5  398.27  5213.7  398.77
    5291  403.46  5451.6  407.15  5561.9  408.15  5722.5  406.52  5812.8  408.16
  5822.8  409.48  5973.4  412.06  6013.5  414.44    6154  418.07  6204.2  421.73
#Mann= 5 ,-1 , 0
  4572.8      .1       0  5060.8     .12       0  5077.3     .12       0
  5207.7     .07       0  5213.7     .12       0
#XS Ineff= 2 , 0
       0                 5028.41       0  406.05
Permanent Ineff=
       F       T
Bank Sta=4978.6,5005.68
XS Rating Curve= 0 ,0
Exp/Cntr=0.3,0.1

Type RM Length L Ch R = 1 ,17274   ,574,574,574
BEGIN DESCRIPTION:
UNT 032 IN LACR 24.0
END DESCRIPTION:
XS GIS Cut Line= 3
      2195192.49     13198275.82      2195461.59     13197911.22
      2195366.18     13196540.79
#Sta/Elev= 30
  4181.6  424.41    4249  422.97  4284.5  420.91  4349.2  418.96  4384.7  416.58
    4414  415.96  4514.2  410.94  4564.3   407.4  4620.7  405.53  4634.4  404.19
  4840.3  402.18    4980  399.67    5007  397.28  5009.8  396.78    5013  397.28
    5020  399.62  5040.1  398.95  5070.2  399.49  5080.2  398.45  5150.4   399.4
    5190  398.51  5240.6  399.16  5300.7  401.87  5380.9  402.89  5541.3  403.34
  5701.7  405.27  5872.1  410.21  5915.8  412.15  5942.3  414.61  6008.5  417.04
#Mann= 5 ,-1 , 0
  4181.6      .1       0  4840.3     .12       0    5007     .07       0
    5013     .12       0  5380.9      .1       0
Bank Sta=5007,5013
XS Rating Curve= 0 ,0
Exp/Cntr=0.3,0.1

Type RM Length L Ch R = 1 ,16700   ,313,313,313
BEGIN DESCRIPTION:
Mapping XS 5e8f80ec
END DESCRIPTION:
XS GIS Cut Line= 3
      2195770.72      13198667.4      2196048.49     13197703.89
      2195640.52     13196453.93
#Sta/Elev= 30
  3665.9  410.94  3864.2  405.36  4073.9  402.01  4519.9   398.9  4664.5  396.59
  4843.9  396.26  4912.8  395.01  4960.1  395.74  5008.5  394.75  5030.7   390.8
  5033.5   390.3  5036.7   390.8  5065.3  395.06  5086.3  395.53  5109.4  395.15
  5117.9  393.94  5127.1  394.48  5212.5  398.17  5391.2  399.81    5486  402.84
  5549.1  403.67  5675.4  407.49  5696.4  408.91  5896.3  415.52  5906.7  416.45
    5912  415.43  5927.8  416.65  5949.2   416.8  5975.8  418.82  5983.5  418.39
#Mann= 5 ,-1 , 0
  3665.9      .1       0  4843.9     .12       0  5030.7     .07       0
  5036.7     .12       0  5127.1      .1       0
Bank Sta=5030.7,5036.7
XS Rating Curve= 0 ,0
Exp/Cntr=0.3,0.1

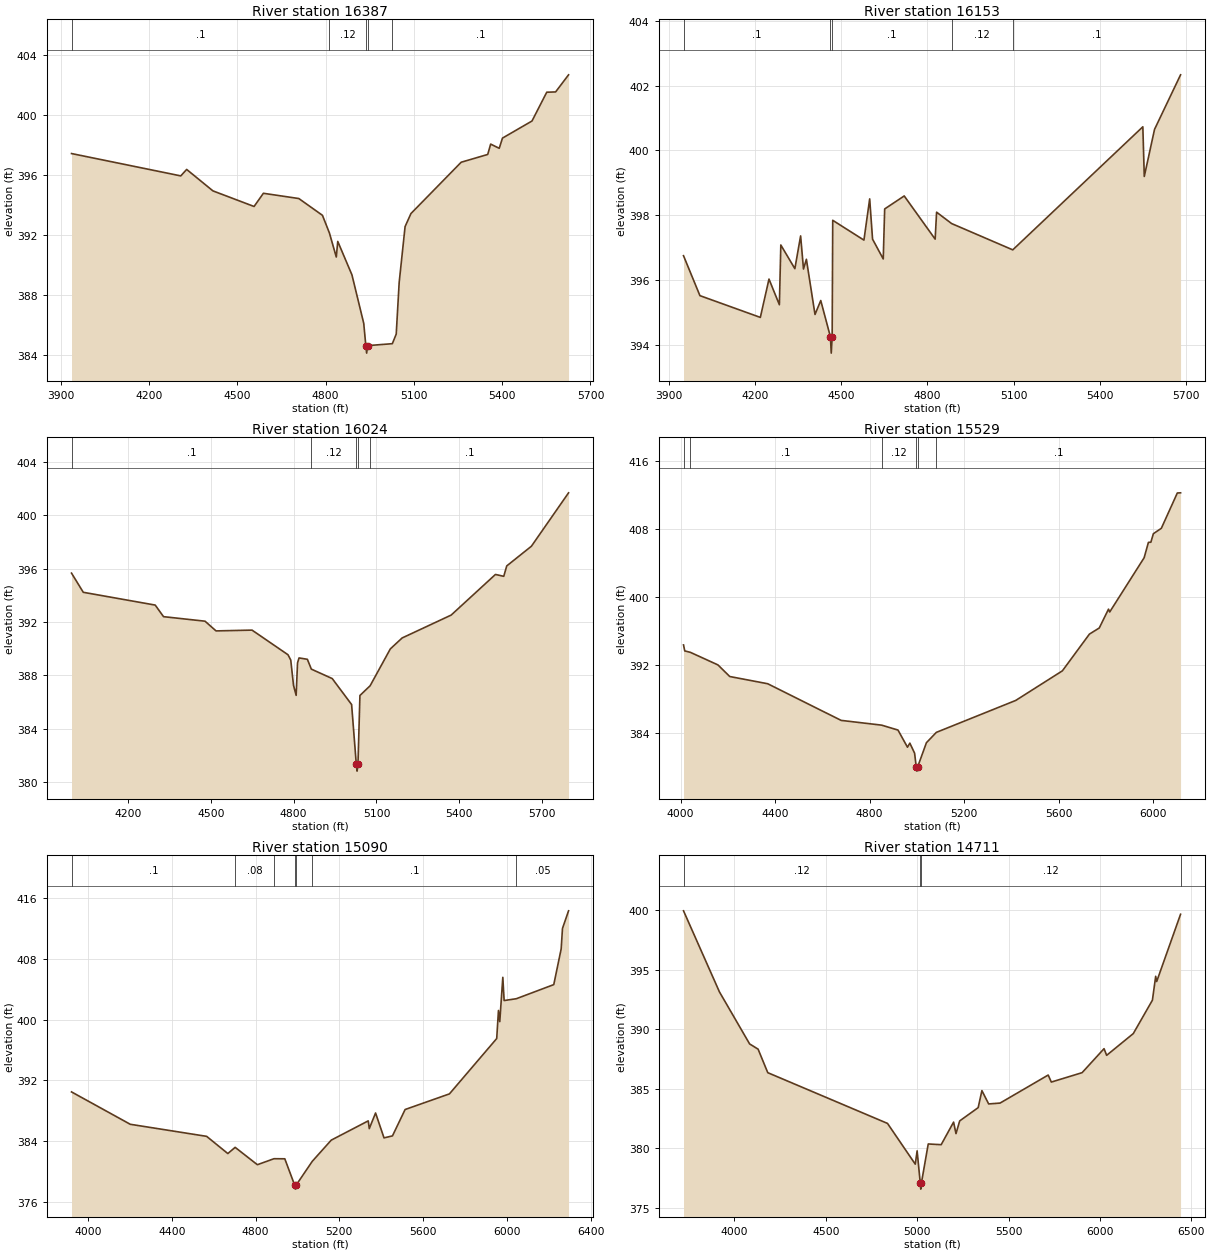
Type RM Length L Ch R = 1 ,16387   ,234,234,234
BEGIN DESCRIPTION:
UNT 032 IN LACR 23.0
END DESCRIPTION:
XS GIS Cut Line= 2
      2196317.59       13198407.      2196196.06     13196722.98
#Sta/Elev= 30
  3937.1  397.45  4308.2  395.96  4328.3  396.39  4417.5  394.96  4557.2  393.92
  4588.9   394.8  4709.2  394.45  4789.5  393.33  4813.2  392.15  4836.5  390.55
  4841.5  391.59  4889.7  389.36  4929.8  386.12  4936.8  384.64  4939.6  384.14
  4942.8  384.64  5026.9  384.77  5040.1  385.41  5050.1  388.85  5070.2  392.58
  5090.2  393.45  5260.7  396.87  5350.9  397.39  5360.9  398.08    5390   397.8
    5401  398.48  5501.3  399.62  5551.4  401.54  5581.5  401.56  5625.5   402.7
#Mann= 5 ,-1 , 0
  3937.1      .1       0  4813.2     .12       0  4936.8     .07       0
  4942.8     .12       0  5026.9      .1       0
Bank Sta=4936.8,4942.8
XS Rating Curve= 0 ,0
Exp/Cntr=0.3,0.1

Type RM Length L Ch R = 1 ,16153   ,129,129,129
BEGIN DESCRIPTION:
UNT 032 IN LACR 22.0
END DESCRIPTION:
XS GIS Cut Line= 2
       2196491.2     13198493.86      2196395.72     13196766.39
#Sta/Elev= 30
  3951.4  396.76  4008.5  395.53  4218.8  394.86  4248.9  396.04  4285.1  395.25
  4290.1  397.09    4339  396.36    4359  397.37    4369  396.35  4379.1  396.65
  4409.1  394.95  4429.1  395.38  4462.8  394.26  4465.6  393.76  4468.8  394.26
  4470.8  397.85  4579.4  397.24  4599.4  398.51  4609.4  397.27  4646.6  396.66
  4651.6   398.2  4719.6   398.6  4827.3  397.27  4832.3   398.1  4884.6  397.75
  5097.4  396.94  5550.2  400.73  5555.2   399.2  5590.9  400.65  5681.5  402.33
#Mann= 5 ,-1 , 0
  3951.4      .1       0  4462.8     .07       0  4468.8      .1       0
  4884.6     .12       0  5097.4      .1       0
Bank Sta=4462.8,4468.8
XS Rating Curve= 0 ,0
Exp/Cntr=0.3,0.1

Type RM Length L Ch R = 1 ,16024   ,495,495,495
BEGIN DESCRIPTION:
UNT 032 IN LACR 21.0
END DESCRIPTION:
XS GIS Cut Line= 2
      2196616.11     13198449.44      2196520.62     13196652.58
#Sta/Elev= 30
    3996  395.67  4038.6  394.23    4299  393.27  4329.1   392.4  4479.3  392.06
  4519.3  391.33  4649.5  391.39  4779.7  389.54  4789.7  389.14  4799.7  387.24
  4809.2  386.49  4814.2  388.93  4819.7   389.3  4849.8   389.2  4864.2  388.46
  4939.9  387.75    5010   385.8    5027   381.3  5029.8   380.8    5033   381.3
  5040.1  386.48    5077  387.21  5150.2  389.98  5192.9   390.8  5370.5  392.52
  5530.7  395.57  5560.8  395.43  5571.6  396.21  5660.9  397.69  5795.4   401.7
#Mann= 5 ,-1 , 0
    3996      .1       0  4864.2     .12       0    5027     .07       0
    5033     .12       0    5077      .1       0
Bank Sta=5027,5033
XS Rating Curve= 0 ,0
Exp/Cntr=0.3,0.1

Type RM Length L Ch R = 1 ,15529   ,439,439,439
BEGIN DESCRIPTION:
Mapping XS 98c1741f
END DESCRIPTION:
XS GIS Cut Line= 3
      2196945.97     13198432.04      2197032.77     13197216.78
      2196789.72     13196366.08
#Sta/Elev= 30
  4012.3  394.33  4017.5  393.63  4041.3  393.46  4157.9  391.98    4208  390.61
  4368.4  389.76  4679.2  385.44  4850.5  384.88  4919.8   384.3  4959.9  382.28
  4969.9  382.76    4990  381.58    4997  379.96  4999.7  379.46    5003  379.96
  5040.1  382.81  5082.2  384.03  5417.9  387.79  5615.4  391.28  5729.8  395.61
  5771.4  396.33  5810.5  398.55  5815.7  398.22  5961.3  404.61  5979.4  406.42
  5989.8  406.44  6000.3  407.44  6034.1  408.08  6101.7  412.24  6115.4  412.26
#Mann= 6 ,-1 , 0
  4012.3     .08       0  4041.3      .1       0  4850.5     .12       0
    4997     .07       0    5003     .12       0  5082.2      .1       0
Bank Sta=4997,5003
XS Rating Curve= 0 ,0
Exp/Cntr=0.3,0.1

Type RM Length L Ch R = 1 ,15090   ,379,379,379
BEGIN DESCRIPTION:
UNT 032 IN LACR 20.0
END DESCRIPTION:
XS GIS Cut Line= 4
      2197345.27     13198458.11      2197484.16     13197798.38
      2197336.59     13196609.14      2197033.56     13196210.87
#Sta/Elev= 30
  3921.2  390.49  4201.8  386.22  4566.3  384.63  4667.5  382.36  4702.4  383.18
  4808.5  380.89  4887.9  381.68  4939.5  381.67  4986.9  378.17  4989.7  377.67
  4992.9  378.17  5070.7  381.34  5161.2  384.13  5337.8  386.67  5342.8  385.65
  5372.8  387.71  5413.1  384.43  5453.5  384.69  5513.9  388.17  5725.5  390.23
  5951.2  397.53  5959.5  401.23  5965.8  399.76  5980.3   405.6  5986.6  402.54
  6044.8  402.78  6223.6  404.64  6258.9  409.35  6265.2  412.05  6294.2  414.37
#Mann= 7 ,-1 , 0
  3921.2      .1       0  4702.4     .08       0  4887.9     .12       0
  4986.9     .07       0  4992.9     .12       0  5070.7      .1       0
  6044.8     .05       0
Bank Sta=4986.9,4992.9
XS Rating Curve= 0 ,0
Exp/Cntr=0.3,0.1

Type RM Length L Ch R = 1 ,14711   ,484,484,484
BEGIN DESCRIPTION:
UNT 032 IN LACR 19.0
END DESCRIPTION:
XS GIS Cut Line= 4
      2197364.84     13198762.74      2197723.99     13197717.45
      2197823.71     13197089.75      2198215.54     13196193.28
#Sta/Elev= 30
    3722  399.97  3918.5  393.15  4083.6  388.77    4130  388.33  4182.9  386.35
    4838  382.08  4989.9  378.65    5000  379.77  5017.3  377.05    5020  376.55
  5023.3  377.05  5060.8  380.35  5131.6  380.29  5199.5  382.19  5212.6  381.22
  5232.9  382.29  5334.1  383.41  5354.4  384.84  5391.3  383.72  5453.6  383.79
    5717  386.15  5734.2  385.56  5902.5  386.35  6022.6  388.37  6036.8  387.81
  6182.6  389.64  6287.2  392.45  6305.1  394.46  6310.6  394.02  6441.2  399.68
#Mann= 4 ,-1 , 0
    3722     .12       0  5017.3     .07       0  5023.3     .12       0
  6441.2      .1       0
Bank Sta=5017.3,5023.3
XS Rating Curve= 0 ,0
Exp/Cntr=0.3,0.1

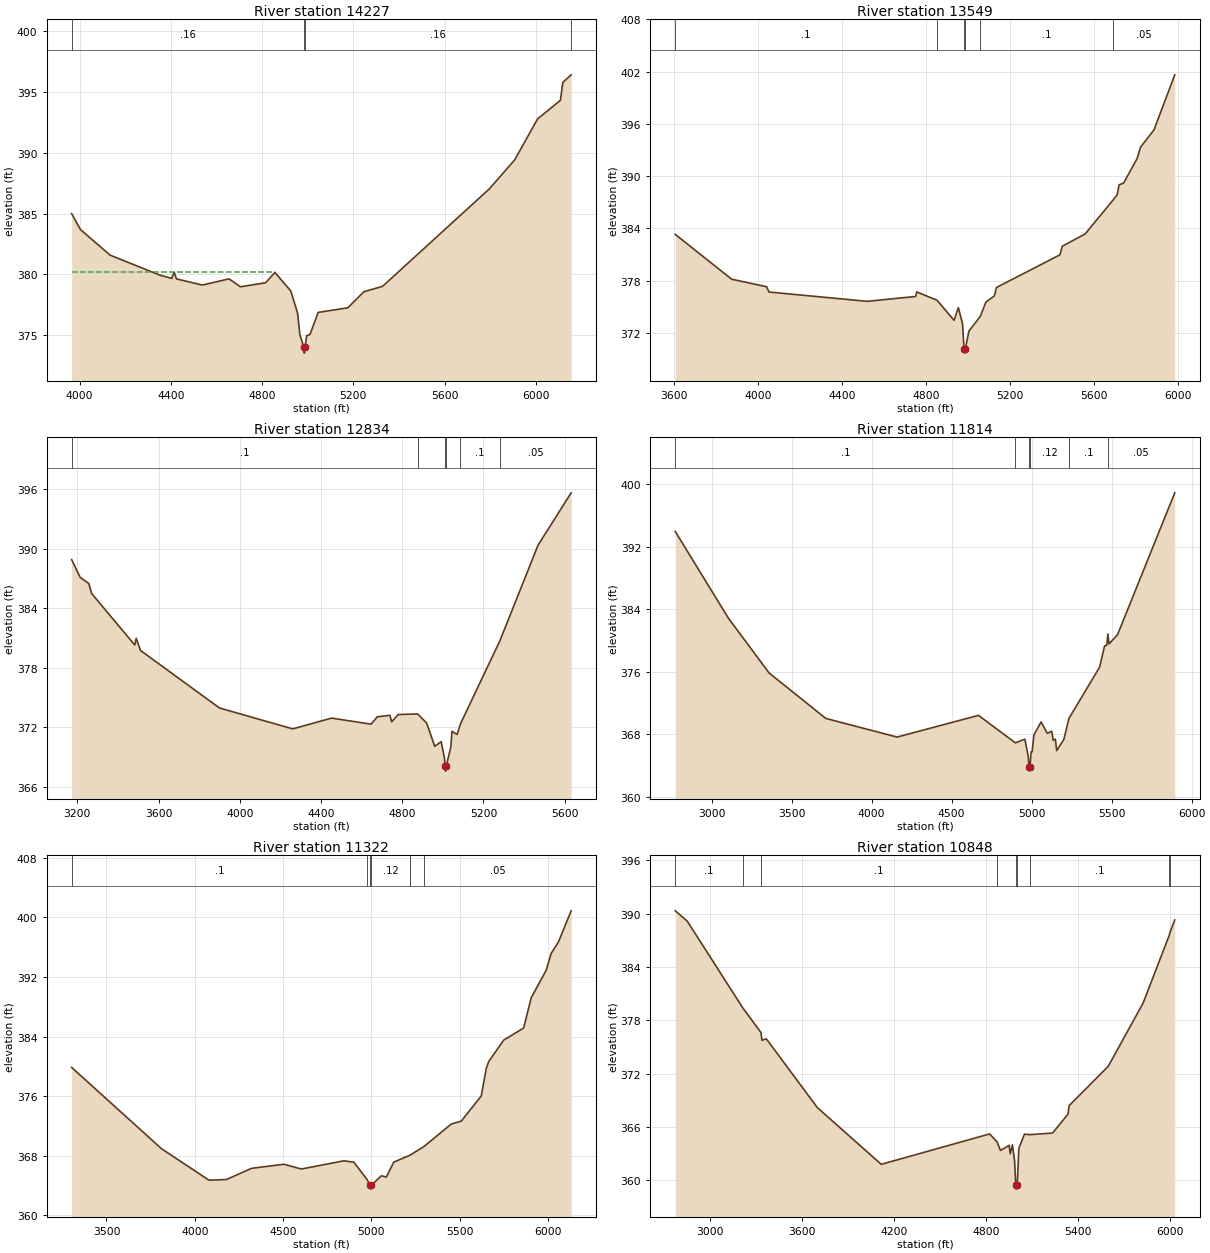
Type RM Length L Ch R = 1 ,14227   ,678,678,678
BEGIN DESCRIPTION:
UNT 032 IN LACR 18.0
END DESCRIPTION:
XS GIS Cut Line= 2
      2198126.52     13198475.49      2198265.29     13196289.89
#Sta/Elev= 30
  3964.9     385  4003.6  383.69  4133.9  381.58  4354.3  379.92  4404.4  379.67
  4414.4  380.19  4424.5  379.63  4537.9  379.12  4654.9  379.63    4705  378.98
  4815.2  379.31  4856.1  380.16  4925.5  378.64  4955.5  376.82  4965.5  375.04
  4982.6  374.02  4985.3  373.52  4988.6  374.02  4995.6  374.96  5010.1  375.06
  5045.7  376.87    5176  377.25  5246.1  378.57  5328.3  379.02  5795.5  387.02
  5907.4  389.42  6007.6  392.79  6107.8  394.32  6118.6   395.8  6154.9  396.42
#Mann= 4 ,-1 , 0
  3964.9     .16       0  4982.6     .07       0  4988.6     .16       0
  6154.9     .05       0
#XS Ineff= 2 , 0
       0 4855.92  380.16               0
Permanent Ineff=
       T       F
Bank Sta=4982.6,4988.6
XS Rating Curve= 0 ,0
Exp/Cntr=0.3,0.1

Type RM Length L Ch R = 1 ,13549   ,715,715,715
BEGIN DESCRIPTION:
UNT 032 IN LACR 17.0
END DESCRIPTION:
XS GIS Cut Line= 3
      2198430.35     13198614.33      2198742.84     13197763.65
      2198925.13     13196305.35
#Sta/Elev= 30
  3607.8  383.31  3876.2  378.16  4041.9   377.3  4053.8  376.69  4520.9  375.62
  4751.3  376.18  4756.3   376.7  4852.6  375.75  4934.1  373.44  4954.2   374.9
  4974.4  373.03  4981.5  370.17  4984.2  369.67  4987.5  370.17  5004.6   372.2
    5059   373.9  5085.3  375.53  5125.6  376.24  5135.7  377.21    5438  380.97
  5448.1  381.94  5557.5  383.36    5689  387.22  5710.1  387.87  5718.8     389
  5740.3   389.2  5804.4  392.01  5820.9  393.33  5885.1  395.32  5983.7  401.64
#Mann= 6 ,-1 , 0
  3607.8      .1       0  4852.6     .12       0  4981.5     .07       0
  4987.5     .12       0    5059      .1       0    5689     .05       0
Bank Sta=4981.5,4987.5
XS Rating Curve= 0 ,0
Exp/Cntr=0.3,0.1

Type RM Length L Ch R = 1 ,12834   ,1020,1020,1020
BEGIN DESCRIPTION:
UNT 032 IN LACR 15.0
END DESCRIPTION:
XS GIS Cut Line= 3
       2198482.4     13198900.84      2199124.79     13198223.72
      2199628.24      13196782.8
#Sta/Elev= 30
  3171.9   388.9  3213.9  387.11  3256.4  386.49  3270.5  385.48  3482.5  380.29
  3489.8  380.96  3510.8  379.74    3900  373.93  4260.8  371.82  4451.5  372.91
  4646.1   372.3  4677.1  373.04  4739.2  373.19  4748.1  372.54  4779.9  373.27
    4876  373.33  4920.2  372.41    4960  370.06  4991.7  370.54  5008.1  368.85
  5010.4  368.06  5013.1  367.56  5016.4  368.06  5039.1  369.98  5044.7  371.58
  5070.2  371.26  5086.6  372.33  5280.6   380.7  5468.5  390.35  5631.6  395.64
#Mann= 6 ,-1 , 0
  3171.9      .1       0    4876     .12       0  5010.4     .07       0
  5016.4     .12       0  5086.6      .1       0  5280.6     .05       0
Bank Sta=5010.4,5016.4
XS Rating Curve= 0 ,0
Exp/Cntr=0.3,0.1

Type RM Length L Ch R = 1 ,11814   ,492,492,492
BEGIN DESCRIPTION:
UNT 032 IN LACR 13.0
END DESCRIPTION:
XS GIS Cut Line= 3
       2198637.7     13199346.88      2200237.72     13197796.85
       2201037.7     13197396.87
#Sta/Elev= 30
  2772.3  393.95  3104.8  382.84  3359.2  375.83  3712.9  370.02  4158.4  367.63
  4667.5  370.41  4898.2  366.89  4957.7  367.36  4978.8  365.13    4983  363.77
  4985.7  363.27    4989  363.77  4996.5  365.74  5002.8  365.74    5014  367.89
  5058.7  369.57  5097.8  368.11  5125.8  368.38  5134.2  367.23  5148.1  367.36
  5156.5   365.9  5201.2  367.33  5232.8  370.01  5424.9  376.59  5455.6   379.3
  5469.6  379.39  5476.2  380.82  5483.6  379.56  5536.7  380.73  5894.4   398.9
#Mann= 6 ,-1 , 0
  2772.3      .1       0  4898.2     .12       0    4983     .07       0
    4989     .12       0  5232.8      .1       0  5476.2     .05       0
Bank Sta=4983,4989
XS Rating Curve= 0 ,0
Exp/Cntr=0.3,0.1

Type RM Length L Ch R = 1 ,11322   ,474,474,474
BEGIN DESCRIPTION:
UNT 032 IN LACR 12.0
END DESCRIPTION:
XS GIS Cut Line= 3
      2199137.69     13199446.89      2200337.72     13198246.85
      2201137.74     13197446.83
#Sta/Elev= 30
  3302.9  379.87  3812.1  368.95  4080.8  364.73  4179.8  364.82  4321.2  366.32
    4505  366.87    4604  366.23  4844.4  367.33    4901  367.15  4974.7  364.86
  4993.5  364.03  4996.2  363.53  4999.5  364.03  5056.6  365.32  5084.9  365.16
  5127.3  367.16  5217.6  368.07  5296.1  369.22  5452.5  372.26  5509.1  372.66
  5622.3  376.03  5650.5  379.71  5664.7  380.66  5749.5  383.53  5862.7  385.16
  5905.1  389.21  5989.9   392.9  6018.2  395.16  6060.7  396.77  6131.4  400.89
#Mann= 6 ,-1 , 0
  3302.9      .1       0  4974.7     .12       0  4993.5     .07       0
  4999.5     .12       0  5217.6      .1       0  5296.1     .05       0
Bank Sta=4993.5,4999.5
XS Rating Curve= 0 ,0
Exp/Cntr=0.3,0.1

Type RM Length L Ch R = 1 ,10848   ,792,792,792
BEGIN DESCRIPTION:
UNT 032 IN LACR 11.0
END DESCRIPTION:
XS GIS Cut Line= 3
       2199037.7     13200146.88      2200637.72     13198596.85
      2201287.74     13197796.84
#Sta/Elev= 30
  2772.3  390.31  2850.1  389.16  3213.2  379.38  3331.4  376.62  3338.1  375.75
  3366.4  375.91  3698.8  368.18    4116  361.79  4823.2  365.21  4871.7  364.31
  4893.9  363.35  4950.5  363.93  4957.7  362.99  4971.8  363.98    4986  362.18
  4993.5   359.5  4996.3     359  4999.5   359.5  5003.2   359.5  5013.6  363.59
  5050.3  365.18  5087.7  365.13  5234.2  365.31  5334.8  367.45  5341.2  368.38
  5596.9  372.82  5824.6  379.94  5995.2  387.57  5998.6  387.84  6030.8  389.28
#Mann= 9 ,-1 , 0
  2772.3      .1       0  3213.2     .05       0  3331.4      .1       0
  4871.7     .12       0  4993.5     .07       0  4999.5     .12       0
  5087.7      .1       0  5995.2     .05       0  5998.6      .1       0
Bank Sta=4993.5,4999.5
XS Rating Curve= 0 ,0
Exp/Cntr=0.3,0.1