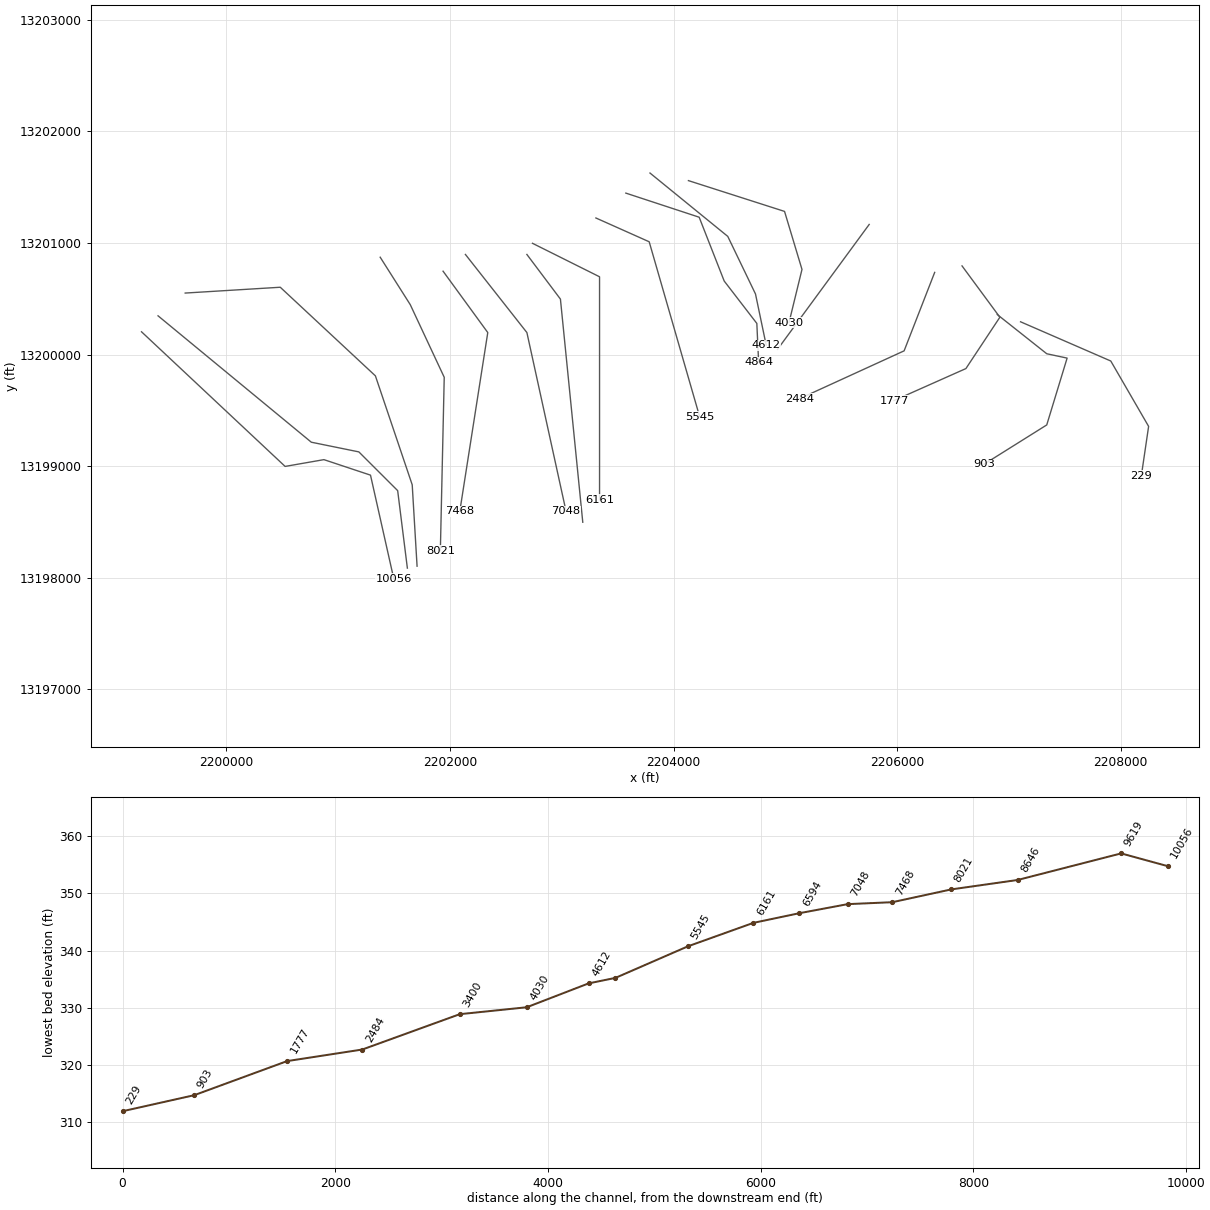
HEC-RAS study UNT 032 IN LACR.prj: UNT 032 IN LACR Base Level Engineering

--- UNT 032 IN LACR.g01 (geometry) --- (continued)

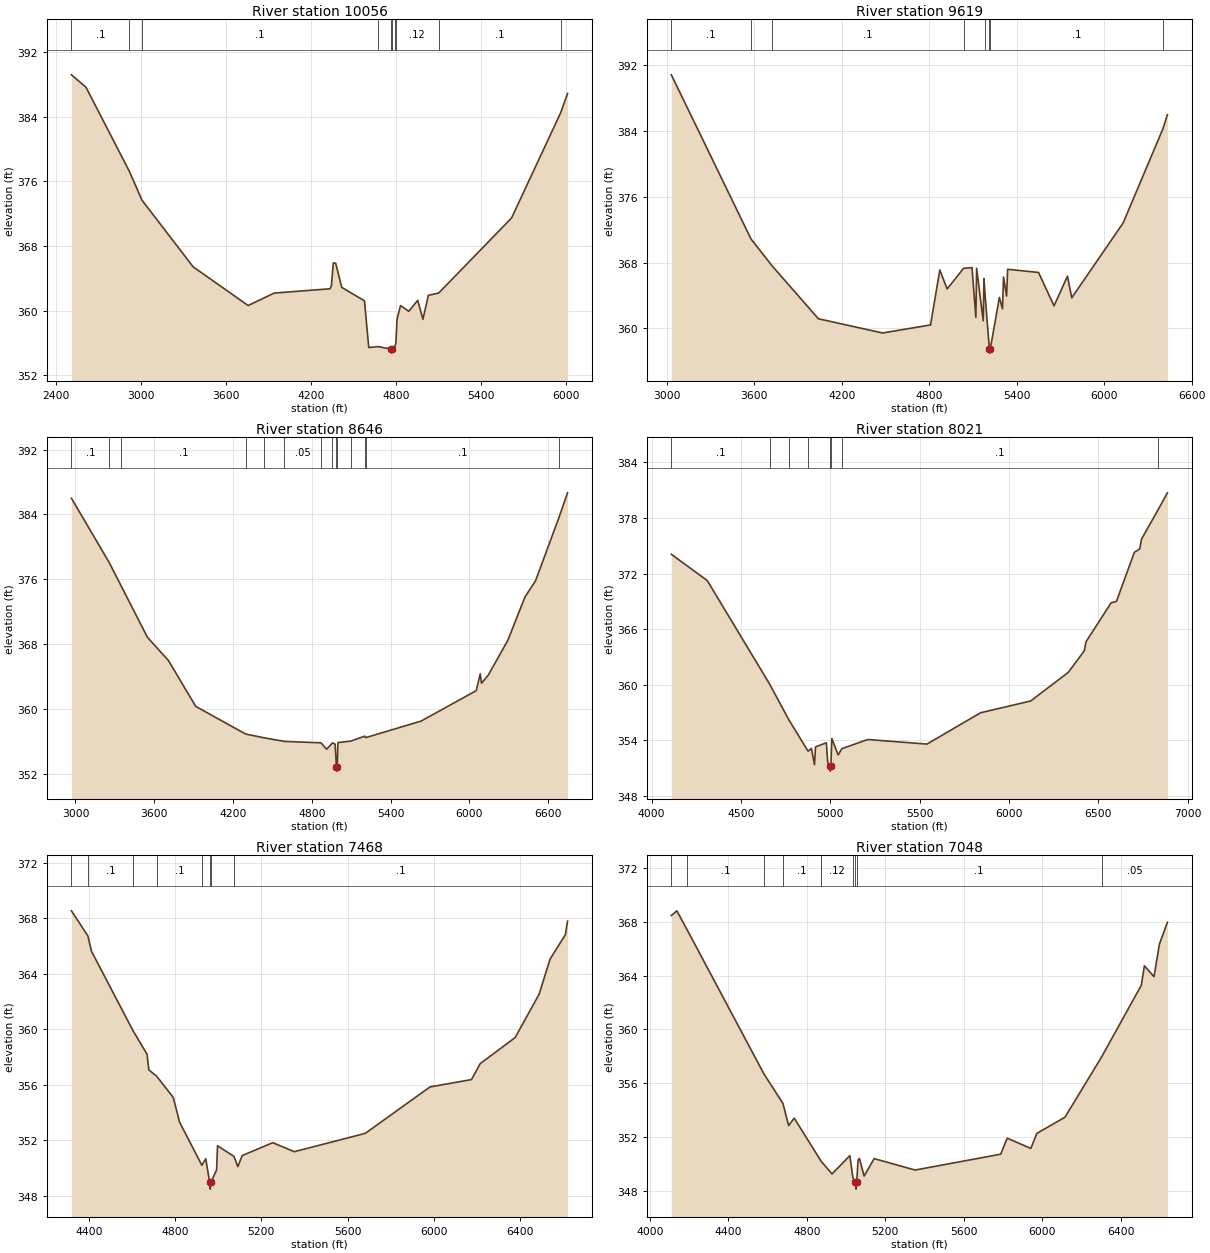
Type RM Length L Ch R = 1 ,10056   ,437,437,437
BEGIN DESCRIPTION:
Mapping XS 0ba5790f
END DESCRIPTION:
XS GIS Cut Line= 5
      2199239.82     13200203.74      2200524.56     13198997.12
      2200871.78     13199057.88      2201288.45     13198918.99
       2201496.6     13197990.98
#Sta/Elev= 30
  2507.9  389.19  2610.4  387.66  2917.4  377.23  3006.2  373.68  3367.5  365.44
  3756.3  360.65  3940.4  362.19  4334.5  362.72  4344.7  363.07  4357.9  365.92
  4375.2  365.87  4417.4   362.9  4578.2  361.23  4608.6  355.45  4673.4  355.57
    4767  355.26  4769.7  354.76    4773  355.26  4791.9  355.47  4800.2  356.01
  4808.4  358.97  4833.2  360.65  4891.2  359.93  4954.4  361.29  4991.3  358.95
  5029.7  361.91  5102.5  362.19  5617.7  371.48  5964.5  384.49  6013.2  386.88
#Mann= 10 ,-1 , 0
  2507.9      .1       0  2917.4     .05       0  3006.2      .1       0
  4673.4     .12       0    4767     .07       0    4773     .12       0
  4791.9      .1       0  4800.2     .12       0  5102.5      .1       0
  5964.5     .05       0
Bank Sta=4767,4773
XS Rating Curve= 0 ,0
Exp/Cntr=0.3,0.1

Type RM Length L Ch R = 1 ,9619    ,973,973,973
BEGIN DESCRIPTION:
UNT 032 IN LACR 10.0
END DESCRIPTION:
XS GIS Cut Line= 5
      2199387.69     13200346.88      2200758.94     13199214.13
      2201184.28     13199127.33      2201531.51      13198780.1
      2201618.31     13198085.68
#Sta/Elev= 30
    3030  390.83  3576.1  370.88  3721.6  367.59    4039  361.16  4479.4  359.43
  4808.6  360.41  4871.9  367.09  4922.4  364.79  5035.1  367.29  5093.1  367.38
  5119.4  361.32  5124.5   367.3  5169.9  360.92    5175  366.04  5183.4  363.85
  5212.3  357.48    5215  356.98  5218.3  357.48  5280.8  363.76  5302.1  362.37
  5309.1  366.23  5330.3  363.92  5337.4  367.18  5549.5  366.79  5655.6  362.73
  5747.9  366.34  5777.4  363.71  6130.1  372.82  6403.1  384.28  6433.6  385.98
#Mann= 8 ,-1 , 0
    3030      .1       0  3576.1     .05       0  3721.6      .1       0
  5035.1     .12       0  5183.4      .1       0  5212.3     .07       0
  5218.3      .1       0  6403.1     .05       0
Bank Sta=5212.3,5218.3
XS Rating Curve= 0 ,0
Exp/Cntr=0.3,0.1

Type RM Length L Ch R = 1 ,8646    ,625,625,625
BEGIN DESCRIPTION:
UNT 032 IN LACR 9.0
END DESCRIPTION:
XS GIS Cut Line= 5
       2199630.5     13200550.94      2200481.16     13200603.02
       2201332.3      13199808.8      2201661.71     13198832.19
      2201705.12     13198103.04
#Sta/Elev= 30
  2969.9     386  3256.2   378.1  3349.1  375.16  3548.2  368.85  3708.5  365.98
  3915.9  360.33  4295.6  356.92  4435.8  356.45  4591.6  356.01  4869.6  355.83
  4913.5  355.04  4957.5  355.83  4977.5  355.67  4987.6  352.84  4990.4  352.34
  4993.6  352.84  4998.9  355.86  5097.4  356.05  5203.3  356.65  5211.6  356.48
  5632.1  358.51  6052.4  362.27  6082.4  364.34  6092.4  363.19  6142.5  364.15
  6292.8  368.47    6423  373.82  6503.2   375.8  6682.2  383.63  6747.4  386.67
#Mann= 14 ,-1 , 0
  2969.9      .1       0  3256.2     .05       0  3349.1      .1       0
  4295.6     .05       0  4435.8      .1       0  4591.6     .05       0
  4869.6     .12       0  4957.5     .05       0  4987.6     .03       0
  4993.6     .05       0  5097.4      .1       0  5203.3     .05       0
  5211.6      .1       0  6682.2     .05       0
Bank Sta=4987.6,4993.6
XS Rating Curve= 0 ,0
Exp/Cntr=0.3,0.1

Type RM Length L Ch R = 1 ,8021    ,553,553,553
BEGIN DESCRIPTION:
UNT 032 IN LACR 7.0
END DESCRIPTION:
XS GIS Cut Line= 4
      2201375.24     13200872.15      2201644.35     13200446.77
      2201948.17     13199795.73      2201913.45     13198241.92
#Sta/Elev= 30
  4110.5  374.09  4311.8  371.25  4660.8  360.07  4768.3  356.22  4875.8  352.84
  4894.5  353.13  4911.7  351.39  4917.3   353.3  4977.9  353.75  4985.9  351.64
    4997  351.19  4999.7  350.69    5003  351.19  5008.8  354.21  5044.1  352.44
  5064.4  353.11  5209.7   354.1  5541.2  353.61  5841.3  356.99  6121.4  358.26
  6331.4  361.34  6421.4  363.67  6431.4  364.66  6571.5  368.85  6601.5  369.01
  6701.5   374.3  6731.5  374.66  6741.5  375.72  6831.7   378.8  6886.5  380.72
#Mann= 8 ,-1 , 0
  4110.5      .1       0  4660.8     .08       0  4768.3      .1       0
  4875.8     .12       0    4997     .07       0    5003     .12       0
  5064.4      .1       0  6831.7     .05       0
Bank Sta=4997,5003
XS Rating Curve= 0 ,0
Exp/Cntr=0.3,0.1

Type RM Length L Ch R = 1 ,7468    ,420,420,420
BEGIN DESCRIPTION:
UNT 032 IN LACR 6.0
END DESCRIPTION:
XS GIS Cut Line= 3
       2201937.7     13200746.88      2202337.72     13200196.86
      2202087.72     13198596.87
#Sta/Elev= 30
  4319.9  368.53    4396  366.72  4413.1   365.6  4604.8   359.9  4670.4  358.18
  4678.5  357.06    4715   356.6  4791.7  355.07  4821.1  353.29  4924.3  350.18
  4942.4  350.65  4960.3  348.96    4963  348.46  4966.3  348.96  4992.7  349.85
  4996.9  351.59  5073.2  350.82  5091.1  350.08  5111.3  350.88    5253  351.81
  5352.7  351.16  5681.7  352.48  5981.8  355.83  6174.1  356.36  6214.6  357.51
  6376.5  359.39  6487.8  362.52  6538.4  365.05  6609.3  366.81  6619.4  367.79
#Mann= 8 ,-1 , 0
  4319.9     .05       0    4396      .1       0  4604.8     .08       0
    4715      .1       0  4924.3     .12       0  4960.3     .07       0
  4966.3     .12       0  5073.2      .1       0
Bank Sta=4960.3,4966.3
XS Rating Curve= 0 ,0
Exp/Cntr=0.3,0.1

Type RM Length L Ch R = 1 ,7048    ,454,454,454
BEGIN DESCRIPTION:
UNT 032 IN LACR 5.0
END DESCRIPTION:
XS GIS Cut Line= 3
      2202137.74     13200896.84      2202687.72     13200196.86
      2203037.71     13198596.89
#Sta/Elev= 30
  4109.8  368.48  4137.8  368.83  4192.1  367.37  4581.1  356.71  4678.7  354.49
  4707.5  352.85  4736.1   353.4  4872.9   350.2  4928.6  349.25  5019.4  350.61
  5035.1  348.97  5048.2  348.62  5050.9  348.12  5054.2  348.62  5061.4  350.29
  5068.4   350.4  5092.1  349.09  5143.3  350.39  5352.1  349.54  5788.2  350.72
  5821.5  351.91  5941.8  351.15  5972.5  352.27  6115.8  353.47  6302.2  357.95
  6504.8  363.29  6520.5  364.74  6569.5  363.93  6596.9  366.34  6637.8  367.98
#Mann= 9 ,-1 , 0
  4109.8     .05       0  4192.1      .1       0  4581.1     .08       0
  4678.7      .1       0  4872.9     .12       0  5035.1      .1       0
  5048.2     .07       0  5054.2      .1       0  6302.2     .05       0
Bank Sta=5048.2,5054.2
XS Rating Curve= 0 ,0
Exp/Cntr=0.3,0.1

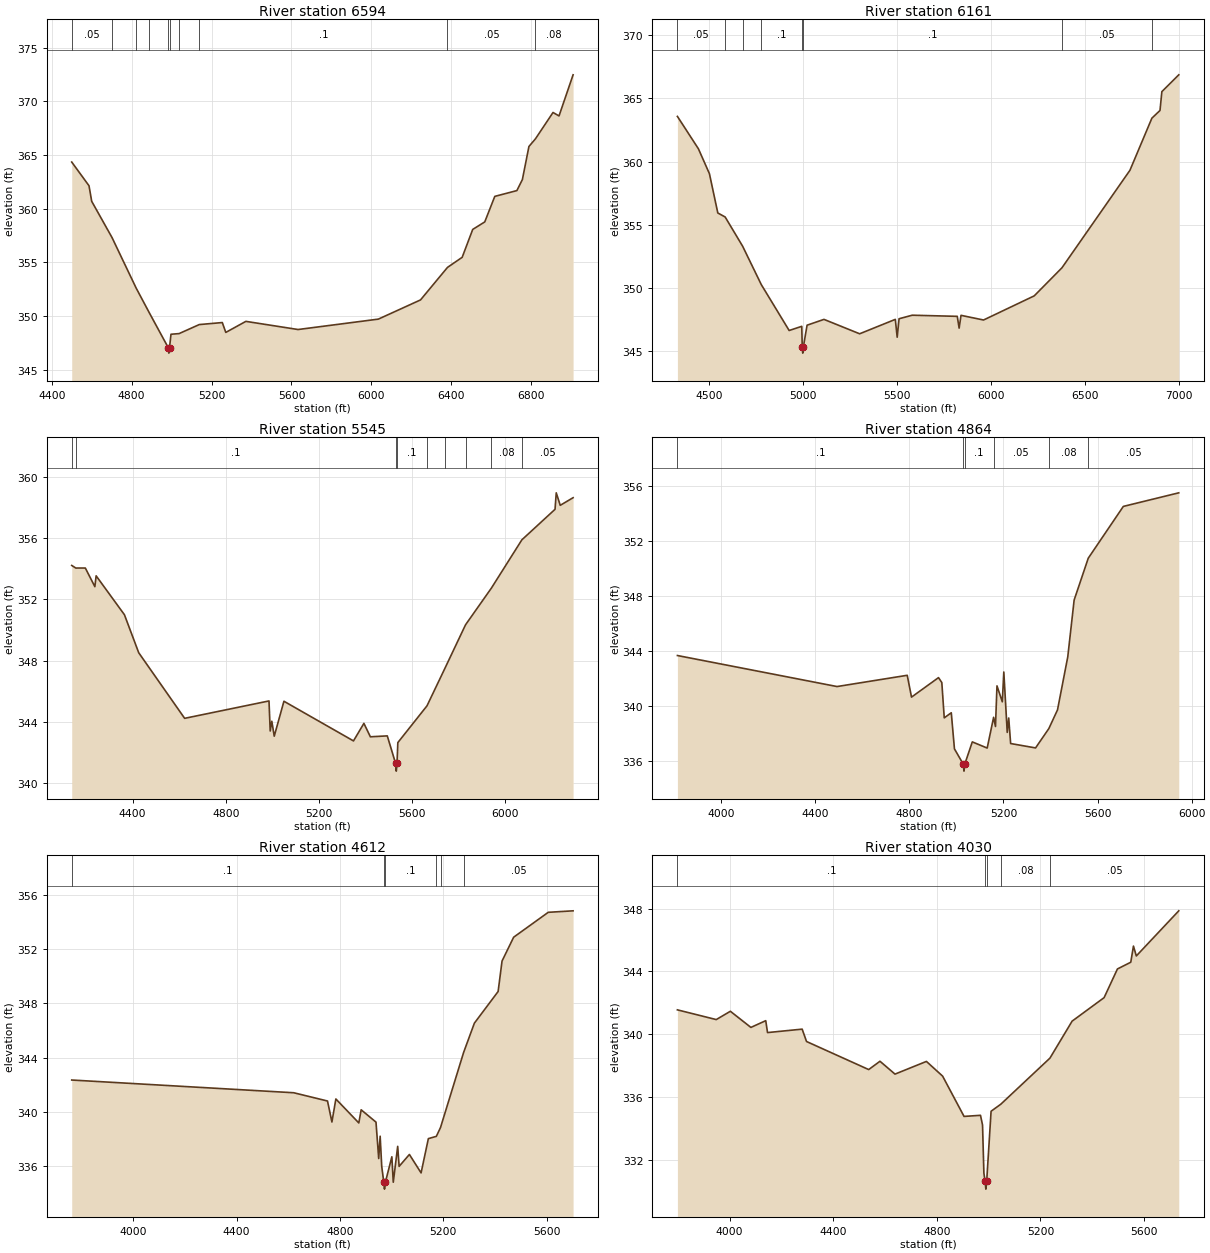
Type RM Length L Ch R = 1 ,6594    ,433,433,433
BEGIN DESCRIPTION:
UNT 032 IN LACR 4.0
END DESCRIPTION:
XS GIS Cut Line= 3
      2202687.72     13200896.85      2202987.72     13200496.85
      2203187.72     13198496.83
#Sta/Elev= 30
    4500  364.35  4586.5  362.14    4600  360.69  4701.8  357.31  4822.6   352.6
  4888.1  350.31  4983.5  347.04  4986.2  346.54  4989.5  347.04  4996.9   348.3
  5037.5  348.36  5138.2   349.2  5253.8  349.39  5271.3  348.47  5371.8   349.5
  5633.1  348.74  6035.1  349.71  6246.2   351.5  6381.2  354.53  6454.7  355.47
  6507.5  358.07  6567.8  358.77    6618  361.15  6728.6  361.69  6756.2  362.72
  6788.9   365.8  6821.4  366.51  6909.5  368.97  6939.6  368.65    7010  372.48
#Mann= 10 ,-1 , 0
    4500     .05       0  4701.8      .1       0  4822.6     .08       0
  4888.1      .1       0  4983.5     .07       0  4989.5      .1       0
  5037.5     .12       0  5138.2      .1       0  6381.2     .05       0
  6821.4     .08       0
Bank Sta=4983.5,4989.5
XS Rating Curve= 0 ,0
Exp/Cntr=0.3,0.1

Type RM Length L Ch R = 1 ,6161    ,616,616,616
BEGIN DESCRIPTION:
UNT 032 IN LACR 3.0
END DESCRIPTION:
XS GIS Cut Line= 3
      2202737.74     13200996.85      2203337.72     13200696.86
      2203337.72     13198696.86
#Sta/Elev= 30
  4329.2  363.58    4441  361.02  4499.7  359.05  4544.4  355.94  4583.6  355.62
  4676.6  353.31  4776.1  350.27  4924.5  346.64  4991.6  346.97  4994.2  345.35
    4997  344.85  5000.2  345.35    5020  347.06    5110  347.52    5300  346.38
    5490  347.52    5500  346.11    5510  347.57    5580  347.85    5820  347.76
    5830  346.83    5840  347.84    5960  347.47    6230  349.38  6377.6   351.6
    6740  359.32  6856.8  363.44    6900  364.05    6910  365.54    7000  366.87
#Mann= 8 ,-1 , 0
  4329.2     .05       0  4583.6      .1       0  4676.6     .08       0
  4776.1      .1       0  4994.2     .07       0  5000.2      .1       0
  6377.6     .05       0  6856.8     .08       0
Bank Sta=4994.2,5000.2
XS Rating Curve= 0 ,0
Exp/Cntr=0.3,0.1

Type RM Length L Ch R = 1 ,5545    ,681,681,681
BEGIN DESCRIPTION:
UNT 032 IN LACR 2.0
END DESCRIPTION:
XS GIS Cut Line= 3
      2203305.16      13201223.8      2203781.89     13201010.53
      2204233.11     13199443.77
#Sta/Elev= 30
  4138.8  354.23  4156.3  354.06  4197.2  354.06  4238.1  352.84  4243.6  353.55
  4365.1     351  4426.4  348.51  4623.6  344.21  4985.8  345.35    4991  343.38
  4997.9  344.02  5008.3  343.04  5049.9  345.33  5348.6  342.73  5393.3  343.88
  5421.1     343  5493.7  343.06  5529.5  341.25  5532.3  340.75  5535.5  341.25
    5539  342.62  5664.2  345.03  5740.3  347.46  5829.7  350.34  5940.9  352.75
  6071.6  355.91    6214  357.91  6219.2  358.99  6236.3  358.17  6291.5  358.67
#Mann= 9 ,-1 , 0
  4138.8     .08       0  4156.3      .1       0  5529.5     .07       0
  5535.5      .1       0  5664.2     .05       0  5740.3      .1       0
  5829.7     .05       0  5940.9     .08       0  6071.6     .05       0
Bank Sta=5529.5,5535.5
XS Rating Curve= 0 ,0
Exp/Cntr=0.3,0.1

Type RM Length L Ch R = 1 ,4864    ,252,252,252
BEGIN DESCRIPTION:
Mapping XS 8ef8e0bf
END DESCRIPTION:
XS GIS Cut Line= 5
      2203573.04      13201446.7      2204228.99     13201230.72
      2204452.97     13200658.77      2204744.94      13200278.8
      2204760.92     13199931.39
#Sta/Elev= 30
  3813.5  343.66  4492.2   341.4  4790.7  342.22  4808.9  340.63  4923.7  342.05
  4937.8  341.69  4948.1  339.12    4978  339.49  4991.5  336.86  5029.2  335.74
    5032  335.24  5035.2  335.74  5067.4  337.37  5130.7  336.92    5158  339.16
    5166  338.49  5172.3  341.45    5195  340.29  5201.4  342.46  5215.9  338.06
  5222.2  339.11  5230.4  337.25  5336.4  336.93  5392.9  338.34  5429.7   339.7
  5473.3  343.56  5500.4   347.7  5560.5  350.75  5709.6  354.52  5945.3  355.51
#Mann= 6 ,-1 , 0
  3813.5      .1       0  5029.2     .07       0  5035.2      .1       0
    5158     .05       0  5392.9     .08       0  5560.5     .05       0
Bank Sta=5029.2,5035.2
XS Rating Curve= 0 ,0
Exp/Cntr=0.3,0.1

Type RM Length L Ch R = 1 ,4612    ,582,582,582
BEGIN DESCRIPTION:
Mapping XS 810d15a3
END DESCRIPTION:
XS GIS Cut Line= 4
      2203789.03     13201626.68      2204484.97     13201058.74
      2204732.95     13200542.78      2204828.94     13200082.81
#Sta/Elev= 30
  3761.8  342.34    4621   341.4  4751.8  340.79  4768.9  339.24  4784.2  340.94
    4873  339.17  4882.1  340.14  4939.5  339.23    4950  336.54  4955.6  338.19
  4961.7  335.96  4969.7  334.78  4972.4  334.28  4975.7  334.78  5000.9  336.67
  5006.4  334.79  5023.5  337.44    5029  335.96  5068.8  336.84    5114  335.48
  5142.2  338.01  5173.1  338.18  5189.2  338.83  5278.7  344.38  5320.3  346.54
  5412.2  348.88  5427.4  351.13  5472.3  352.89  5606.3  354.73  5702.4  354.84
#Mann= 6 ,-1 , 0
  3761.8      .1       0  4969.7     .07       0  4975.7      .1       0
  5173.1     .05       0  5189.2     .08       0  5278.7     .05       0
Bank Sta=4969.7,4975.7
XS Rating Curve= 0 ,0
Exp/Cntr=0.3,0.1

Type RM Length L Ch R = 1 ,4030    ,630,630,630
BEGIN DESCRIPTION:
Mapping XS 7880c207
END DESCRIPTION:
XS GIS Cut Line= 4
      2204132.98      13201558.7      2204992.92     13201282.72
      2205148.91     13200762.76      2205032.92     13200286.79
#Sta/Elev= 30
  3798.4  341.55  3948.4  340.93  4002.9  341.46  4082.2  340.43  4139.5  340.86
  4146.4   340.1  4280.1  340.32    4297  339.53    4537  337.74  4580.6  338.27
  4638.6  337.45  4759.9  338.26  4822.5  337.32  4905.2  334.75  4968.7  334.82
  4976.6   334.2  4981.8  331.13  4986.6  330.61  4989.3  330.11  4992.6  330.61
  5009.6  335.08  5047.2  335.53  5236.9  338.47  5322.5  340.83    5446  342.33
  5497.5  344.16    5549  344.59  5559.3  345.62  5570.4  344.99  5734.3  347.87
#Mann= 5 ,-1 , 0
  3798.4      .1       0  4986.6     .07       0  4992.6      .1       0
  5047.2     .08       0  5236.9     .05       0
Bank Sta=4986.6,4992.6
XS Rating Curve= 0 ,0
Exp/Cntr=0.3,0.1

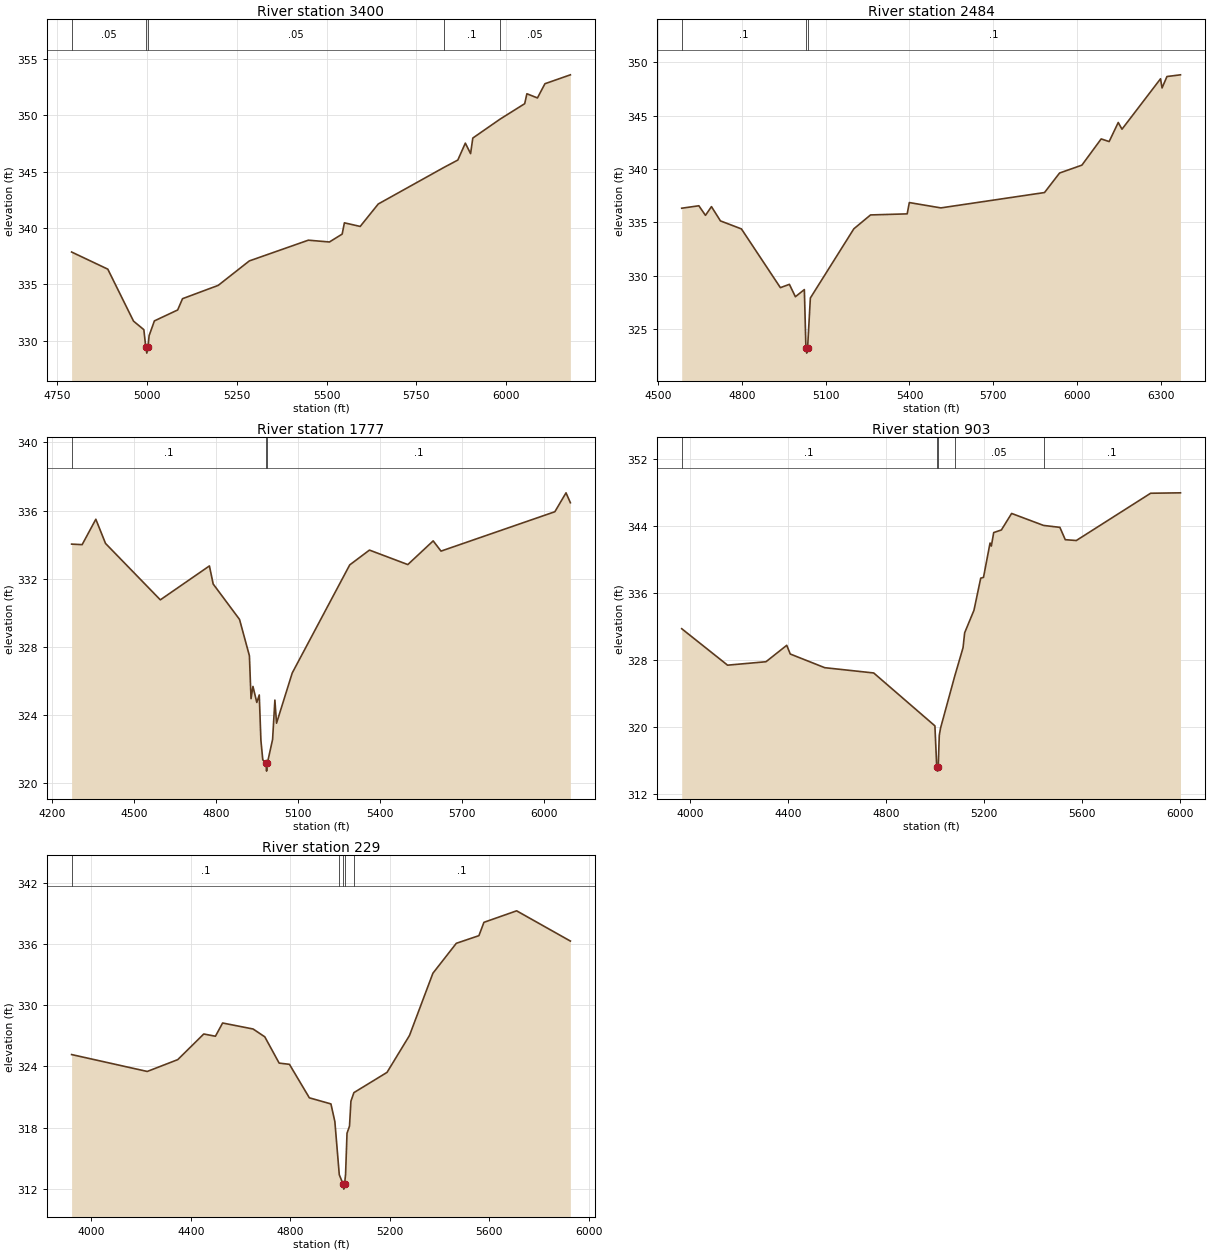
Type RM Length L Ch R = 1 ,3400    ,916,916,916
BEGIN DESCRIPTION:
Mapping XS dc185e2a
END DESCRIPTION:
XS GIS Cut Line= 2
      2205750.24     13201165.86      2204929.93     13200046.07
#Sta/Elev= 30
  4790.5  337.87  4891.2  336.35  4962.8  331.74  4991.6  330.98    4997   329.4
  4999.8   328.9    5003   329.4  5006.2  330.45  5020.9  331.76  5085.7  332.73
  5099.2  333.73  5198.5  334.91  5285.1  337.08  5449.4  338.92    5508  338.76
  5543.5  339.46  5549.7  340.46  5593.7  340.14  5643.9  342.13  5825.9  345.36
  5865.4  346.03  5886.3  347.53  5900.9   346.6  5907.1  347.98    5983  349.66
  6051.5  351.03  6057.6  351.91    6087  351.54  6107.8   352.8  6178.6  353.59
#Mann= 5 ,-1 , 0
  4790.5     .05       0    4997     .03       0    5003     .05       0
  5825.9      .1       0    5983     .05       0
Bank Sta=4997,5003
XS Rating Curve= 0 ,0
Exp/Cntr=0.3,0.1

Type RM Length L Ch R = 1 ,2484    ,707,707,707
BEGIN DESCRIPTION:
Mapping XS 6f2d5a4a
END DESCRIPTION:
XS GIS Cut Line= 3
      2206336.15     13200736.14      2206062.72     13200033.02
      2205125.21     13199603.33
#Sta/Elev= 30
  4584.6  336.32    4646  336.55  4669.7  335.65  4691.1  336.47  4723.3  335.13
  4798.4  334.38  4937.9  328.87  4970.1  329.18  4991.6  328.02  5023.7  328.69
  5029.3  323.23  5032.1  322.73  5035.3  323.23  5045.2   327.9  5200.9  334.39
  5260.7  335.69  5391.9  335.79  5399.5  336.85  5512.4  336.35  5883.5  337.79
  5937.4  339.62  6017.4  340.36  6086.4  342.82  6114.9  342.57  6147.5  344.36
  6160.9  343.73  6298.9  348.46  6304.4   347.6  6321.9  348.67  6370.3  348.83
#Mann= 3 ,-1 , 0
  4584.6      .1       0  5029.3     .07       0  5035.3      .1       0
Bank Sta=5029.3,5035.3
XS Rating Curve= 0 ,0
Exp/Cntr=0.3,0.1

Type RM Length L Ch R = 1 ,1777    ,874,874,874
BEGIN DESCRIPTION:
Mapping XS 1c7ee86c
END DESCRIPTION:
XS GIS Cut Line= 4
      2206580.84     13200794.31      2206919.38     13200334.24
      2206615.56     13199874.17      2205973.18      13199587.7
#Sta/Elev= 30
  4270.7  334.03  4309.3     334  4359.4  335.49  4394.9  334.07  4595.5  330.76
  4775.2  332.75    4789  331.69  4885.5  329.61  4921.6  327.48  4927.6  324.96
  4934.6  325.68  4948.7  324.74  4957.7  325.18  4963.7  322.52  4970.6  321.37
  4981.8  321.21  4984.5  320.71  4987.8  321.21  5006.5  322.57  5014.9  324.88
  5020.9  323.52  5078.4  326.47  5288.8  332.81  5361.1  333.68  5501.5  332.83
  5594.4  334.22  5623.1  333.62  6039.8  335.93  6080.7  337.04  6096.6  336.46
#Mann= 3 ,-1 , 0
  4270.7      .1       0  4981.8     .07       0  4987.8      .1       0
Bank Sta=4981.8,4987.8
XS Rating Curve= 0 ,0
Exp/Cntr=0.3,0.1

Type RM Length L Ch R = 1 ,903     ,674,674,674
BEGIN DESCRIPTION:
Mapping XS 425c41e1
END DESCRIPTION:
XS GIS Cut Line= 5
      2206896.04     13200358.55      2207338.76     13200006.98
      2207521.05     13199967.92      2207338.76     13199368.96
      2206778.84     13199017.38
#Sta/Elev= 30
  3964.9  331.74  4152.4  327.39  4309.4   327.8  4394.3  329.76  4408.7  328.72
  4549.6  327.09  4749.8  326.46    5000  320.15  5007.5  315.25  5010.2  314.75
  5013.5  315.25  5017.9  319.02  5023.1  319.89  5081.3  326.11    5115  329.47
  5121.6  331.25  5159.7  333.94  5187.3  337.77  5198.6  337.86  5225.4  341.96
  5230.7   341.6  5240.4  343.21  5271.8  343.52  5313.6  345.49  5444.2  344.06
  5510.9  343.83  5532.9  342.36    5578  342.26  5881.9   347.9  6003.9  347.95
#Mann= 5 ,-1 , 0
  3964.9      .1       0  5007.5     .07       0  5013.5      .1       0
  5081.3     .05       0  5444.2      .1       0
Bank Sta=5007.5,5013.5
XS Rating Curve= 0 ,0
Exp/Cntr=0.3,0.1

Type RM Length L Ch R = 1 ,229     ,0,0,0
BEGIN DESCRIPTION:
UNT 032 IN LACR 1.0
END DESCRIPTION:
XS GIS Cut Line= 4
      2207104.42     13200293.42      2207911.68     13199941.88
      2208250.22     13199355.94      2208185.11     13198913.19
#Sta/Elev= 30
  3921.1  325.17  4225.1  323.51  4347.7  324.67  4452.3  327.19  4499.2  326.97
  4528.1  328.27  4650.7  327.68  4697.6  326.91  4755.3  324.33  4796.7  324.21
  4876.7  320.92  4963.4  320.32  4979.2  318.59    4997  313.36  5012.3  312.45
    5015  311.95  5018.3  312.45  5022.3  313.42  5028.1  317.44  5038.1  318.14
  5043.8  320.59  5055.8  321.43  5188.9  323.42  5279.3  327.05  5373.3  333.16
  5467.4   336.1  5558.2  336.85  5578.4  338.16  5709.8  339.29  5925.8  336.32
#Mann= 5 ,-1 , 0
  3921.1      .1       0    4997     .12       0  5012.3     .07       0
  5018.3     .12       0  5055.8      .1       0
Bank Sta=5012.3,5018.3
XS Rating Curve= 0 ,0
Exp/Cntr=0.3,0.1

Chan Stop Cuts=-1
Use User Specified Reach Order=0
Composite Channel Slope=5