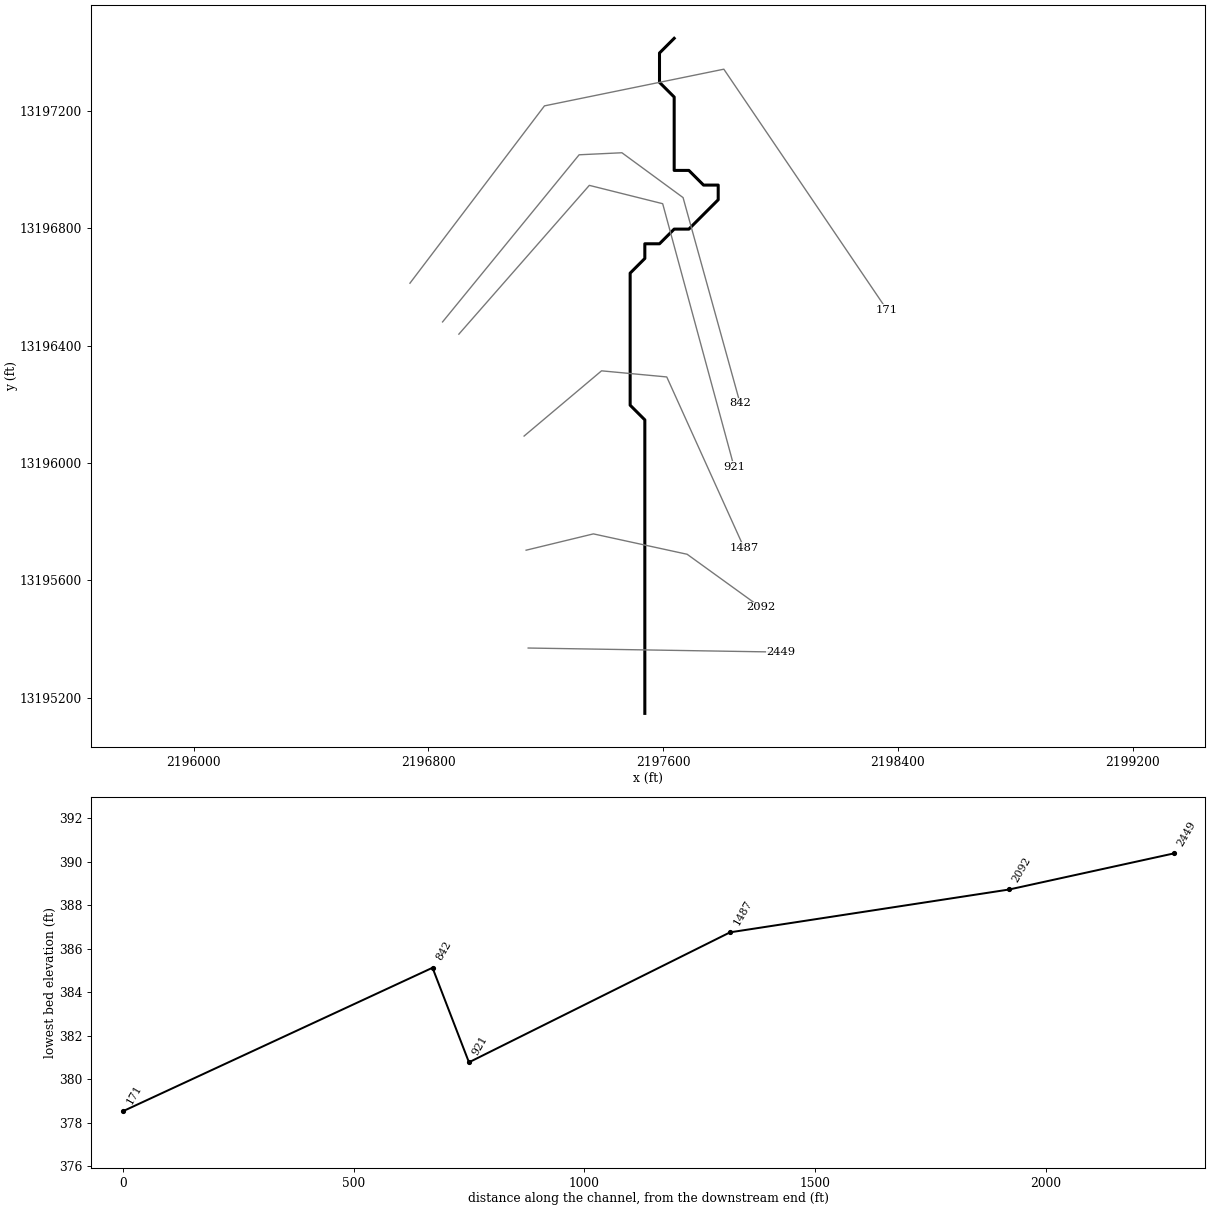
--- UNT 033 IN LACR.prj (project) ---

Proj Title=UNT 033 IN LACR Base Level Engineering
Current Plan=p01
Default Exp/Contr=0.3,0.1
English Units
Geom File=g01
Flow File=f01
Plan File=p01
Y Axis Title=Elevation
X Axis Title(PF)=Main Channel Distance
X Axis Title(XS)=Station
BEGIN DESCRIPTION:
UNT 033 IN LACR
END DESCRIPTION:
DSS Export Rating Curves= 0
DSS Export Rating Curve Sorted= 0
DSS Export Volume Flow Curves= 0
DXF OffsetX= 0
DXF OffsetY= 0
DXF ScaleX= 1
DXF ScaleY= 10

--- UNT 033 IN LACR.p01 (plan) ---

Plan Title=Multiple Run
Short Identifier=Multiple
Geom File=g01
Flow File=f01
Subcritical Flow
K Sum by GR= 0
Std Step Tol= 0.01
Critical Tol= 0.01
Num of Std Step Trials= 20
Max Error Tol= 0.3
Flow Tol Ratio= 0.001
Split Flow NTrial= 30
Split Flow Tol= 0.02
Split Flow Ratio= 0.02
Log Output Level= 0
Friction Slope Method= 1
Unsteady Friction Slope Method= 2
Unsteady Bridges Friction Slope Method= 1
Parabolic Critical Depth
Global Vel Dist=  1 , 1 , 1
Global Log Level= 0
CheckData=True
Encroach Param= -1, 0, 0, 0
BEGIN DESCRIPTION:
Multiple Run
END DESCRIPTION:

--- UNT 033 IN LACR.f01 (steady flow) ---

Flow Title=Multiple
Program Version=4.10
Number of Profiles= 7
Profile Names=10-year,25-year,50-year,1pct_min,100-year,1pct_plu,500-year
River Rch & RM=UNT 033 IN LACR,Reach-1         ,2449
     217     303     376     344     465     629     721
Boundary for River Rch & Prof#=UNT 033 IN LACR,Reach-1         , 1
Up Type= 0
Dn Type= 3
Dn Slope=0.01
Boundary for River Rch & Prof#=UNT 033 IN LACR,Reach-1         , 2
Up Type= 0
Dn Type= 3
Dn Slope=0.01
Boundary for River Rch & Prof#=UNT 033 IN LACR,Reach-1         , 3
Up Type= 0
Dn Type= 3
Dn Slope=0.01
Boundary for River Rch & Prof#=UNT 033 IN LACR,Reach-1         , 4
Up Type= 0
Dn Type= 3
Dn Slope=0.01
Boundary for River Rch & Prof#=UNT 033 IN LACR,Reach-1         , 5
Up Type= 0
Dn Type= 3
Dn Slope=0.01
Boundary for River Rch & Prof#=UNT 033 IN LACR,Reach-1         , 6
Up Type= 0
Dn Type= 3
Dn Slope=0.01
Boundary for River Rch & Prof#=UNT 033 IN LACR,Reach-1         , 7
Up Type= 0
Dn Type= 3
Dn Slope=0.01
DSS Import GetInterval= 0
DSS Import GetPeak= 0
DSS Import FillOption= 0

--- UNT 033 IN LACR.g01 (geometry) ---

Geom Title=Existing Conditions
Program Version=4.10

River Reach=UNT 033 IN LACR ,Reach-1
Reach XY= 19
      2197537.72     13195146.85      2197537.72     13196146.85
      2197487.72     13196196.85      2197487.72     13196646.85
      2197537.72     13196696.85      2197537.72     13196746.86
      2197587.72     13196746.86      2197637.72     13196796.85
      2197687.72     13196796.85      2197737.72     13196846.85
      2197787.72     13196896.86      2197787.72     13196946.85
      2197737.72     13196946.85      2197687.72     13196996.85
      2197637.72     13196996.85      2197637.72     13197246.86
      2197587.72     13197296.85      2197587.72     13197396.86
      2197637.72     13197446.85

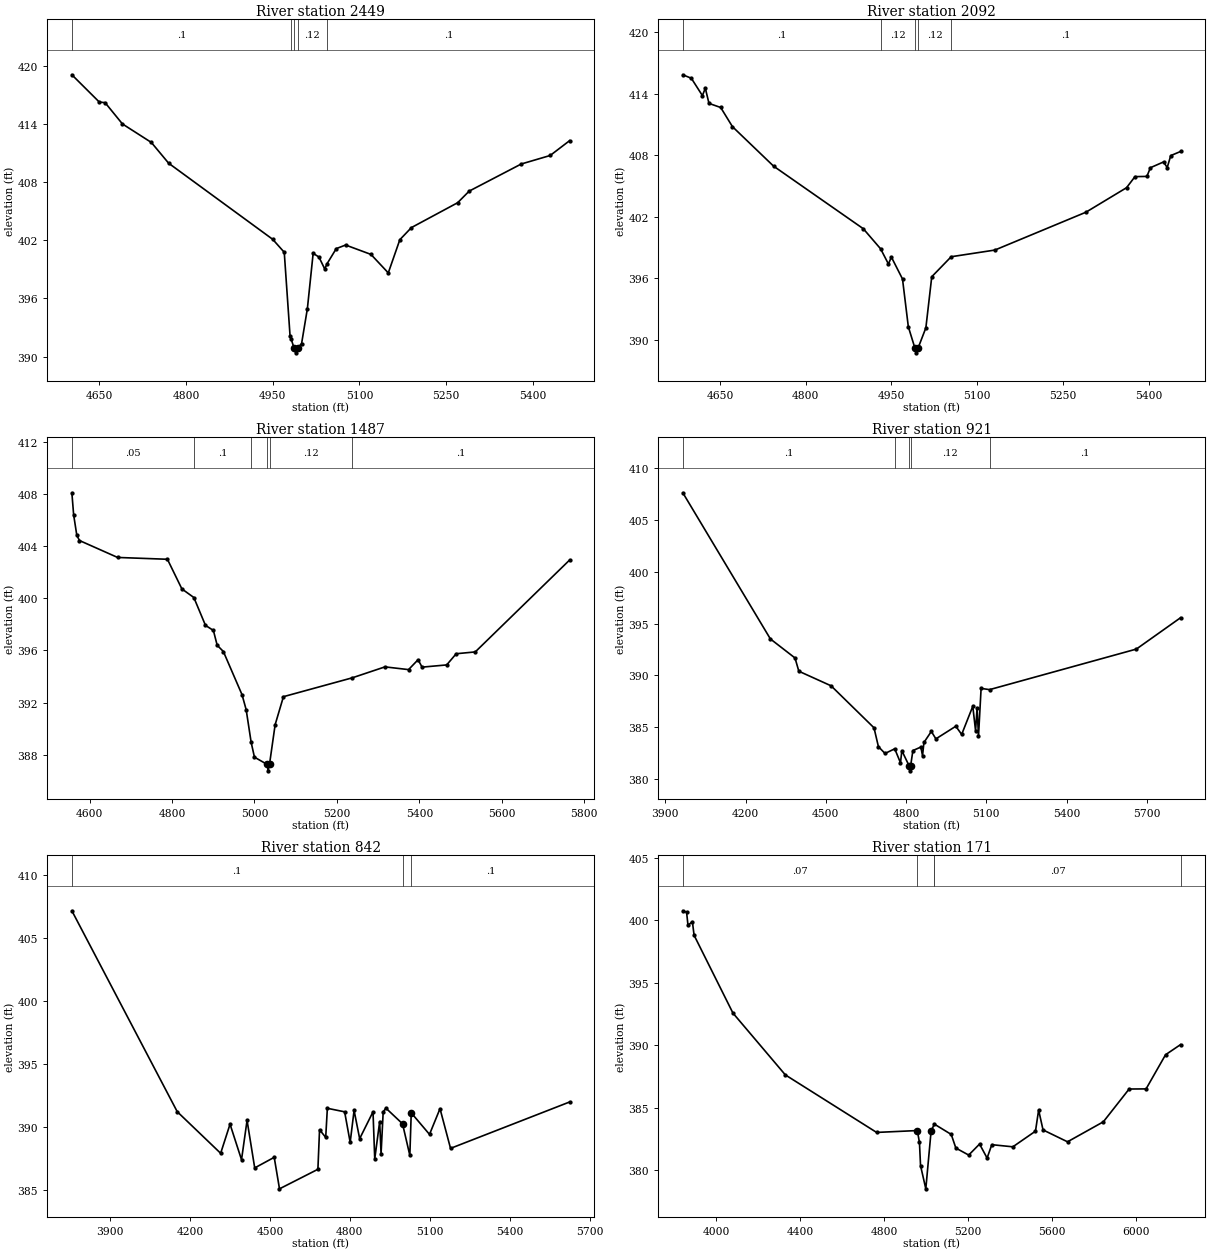
Type RM Length L Ch R = 1 ,2449    ,357,357,357
BEGIN DESCRIPTION:
UNT 033 IN LACR 3.0
END DESCRIPTION:
XS GIS Cut Line= 2
      2197140.27     13195369.51      2198001.36     13195355.63
#Sta/Elev= 30
  4602.5  419.11    4650  416.29    4660  416.23    4690  414.03    4740  412.12
    4770  409.97    4950  402.11    4970  400.77    4980  392.16    4982  391.79
    4987  390.88  4989.7  390.38    4993  390.88    5000  391.34    5010  394.94
    5020  400.66    5030  400.28    5040  399.05  5044.3  399.61    5060  401.15
  5076.2  401.52    5120  400.55    5150  398.64    5170  402.07    5190  403.32
    5270  405.89    5290  407.09    5380  409.89  5430.1  410.77  5463.7   412.3
#Mann= 5 ,-1 , 0
  4602.5      .1       0    4982     .12       0    4987     .07       0
    4993     .12       0  5044.3      .1       0
Bank Sta=4987,4993
XS Rating Curve= 0 ,0
Exp/Cntr=0.3,0.1

Type RM Length L Ch R = 1 ,2092    ,605,605,605
BEGIN DESCRIPTION:
Mapping XS d6d369b9
END DESCRIPTION:
XS GIS Cut Line= 4
      2197133.25     13195702.84      2197362.45      13195758.4
       2197681.9     13195688.96      2197931.87     13195508.42
#Sta/Elev= 30
  4584.8  415.83  4599.7  415.49  4619.1   413.8  4624.2  414.52  4630.6  413.04
  4651.1  412.64  4671.7  410.77  4743.7  406.92  4900.7  400.82    4931  398.86
  4944.7  397.38  4949.8  398.06  4969.3  395.92  4979.5  391.26  4990.8  389.22
  4993.5  388.72  4996.8  389.22  5010.2  391.16  5020.5  396.14  5054.5  398.09
  5130.9  398.74  5290.3  402.43  5361.4  404.82  5376.2   405.9    5397  405.92
  5403.2  406.77  5426.1  407.33  5432.6  406.79  5438.8  407.95  5455.9  408.35
#Mann= 5 ,-1 , 0
  4584.8      .1       0    4931     .12       0  4990.8     .07       0
  4996.8     .12       0  5054.5      .1       0
Bank Sta=4990.8,4996.8
XS Rating Curve= 0 ,0
Exp/Cntr=0.3,0.1

Type RM Length L Ch R = 1 ,1487    ,566,566,566
BEGIN DESCRIPTION:
UNT 033 IN LACR 2.0
END DESCRIPTION:
XS GIS Cut Line= 4
      2197126.35     13196091.74      2197390.23     13196313.96
      2197612.45     13196293.13      2197875.88     13195710.82
#Sta/Elev= 30
  4557.1  408.12  4561.4  406.43  4569.1  404.85  4575.6  404.45    4668  403.15
  4788.9  403.01    4824  400.73    4853  400.07  4881.2  397.93  4900.4  397.54
  4909.6   396.4  4924.6  395.92  4969.9   392.6  4979.9  391.45    4992  388.94
    5000   387.8  5030.5  387.25  5033.2  386.75  5036.5  387.25  5050.2   390.3
  5070.3  392.45  5237.4   393.9  5316.6  394.74  5373.8  394.53  5396.9  395.29
  5406.6  394.72  5466.3  394.89  5489.4  395.75  5535.6  395.89  5764.4  402.95
#Mann= 6 ,-1 , 0
  4557.1     .05       0    4853      .1       0    4992     .12       0
  5030.5     .07       0  5036.5     .12       0  5237.4      .1       0
Bank Sta=5030.5,5036.5
XS Rating Curve= 0 ,0
Exp/Cntr=0.3,0.1

Type RM Length L Ch R = 1 ,921     ,79,79,79
BEGIN DESCRIPTION:
Mapping XS 8778e5e5
END DESCRIPTION:
XS GIS Cut Line= 4
      2196904.14     13196438.98      2197348.56      13196945.9
      2197598.56      13196883.4      2197841.63     13195987.54
#Sta/Elev= 30
  3965.7  407.65    4293  393.52    4385  391.68  4399.3   390.4  4519.8  388.99
  4680.2  384.93  4696.7  383.11  4721.4  382.45  4757.7   382.9  4779.2  381.55
  4784.3  382.72  4811.2  381.27    4814  380.77  4817.2  381.27  4825.6  382.73
  4855.4  383.07  4861.6  382.23  4866.8  383.51  4894.5  384.58  4911.5  383.86
  4985.9  385.08  5007.9  384.29  5049.4  387.01  5059.8  384.65  5065.6  386.88
  5070.7  384.09  5080.5  388.74  5112.1  388.62  5660.7  392.54  5825.8  395.57
#Mann= 5 ,-1 , 0
  3965.7      .1       0  4757.7     .12       0  4811.2     .07       0
  4817.2     .12       0  5112.1      .1       0
Bank Sta=4811.2,4817.2
XS Rating Curve= 0 ,0
Exp/Cntr=0.3,0.1

Type RM Length L Ch R = 1 ,842     ,671,671,671
BEGIN DESCRIPTION:
Mapping XS 3fdd5541
END DESCRIPTION:
XS GIS Cut Line= 5
      2196848.54      13196480.6      2197313.84     13197050.07
      2197459.67     13197057.01      2197668.01     13196904.24
      2197862.46     13196202.83
#Sta/Elev= 30
    3757  407.18  4152.4  391.24  4315.3  387.94  4350.5  390.25  4393.6  387.43
  4414.4  390.55  4443.1  386.78  4516.3  387.62  4536.1  385.12  4680.2  386.67
  4686.4  389.81  4709.5   389.2  4715.7  391.51  4780.5  391.23  4801.3  388.81
    4816  391.34  4836.9   389.1    4887  391.23  4893.5  387.49    4912  390.46
  4917.2   387.9  4925.2  391.23  4935.5  391.52  4997.8  390.28  5025.2  387.77
  5030.4  391.15    5099  389.44  5138.4  391.48  5177.9  388.33  5624.6  392.01
#Mann= 3 , 0 , 0
    3757      .1       0  4997.8     .07       0  5030.4      .1       0
#XS Ineff= 2 , 0
       0 4936.08  391.48               0
Permanent Ineff=
       T       F
Bank Sta=4997.8,5030.4
XS Rating Curve= 0 ,0
Exp/Cntr=0.3,0.1

Type RM Length L Ch R = 1 ,171     ,0,0,0
BEGIN DESCRIPTION:
UNT 033 IN LACR 1.0
END DESCRIPTION:
XS GIS Cut Line= 4
      2196737.45     13196612.57      2197195.78     13197216.74
       2197806.9     13197341.74      2198362.44     13196522.32
#Sta/Elev= 30
  3841.6  400.75  3859.5  400.64  3866.3  399.59  3887.2  399.88  3895.4  398.79
  4080.6  392.57  4330.2  387.63  4765.2  383.03  4959.2  383.18  4969.4  382.23
  4974.6  380.38  4999.7  378.52  5025.1  383.17  5040.8  383.69  5120.9  382.87
  5142.9  381.78  5204.1  381.22  5255.9   382.1  5291.8  380.98  5314.2  382.05
  5414.6  381.88  5522.4  383.13  5537.4  384.82  5558.4  383.23  5675.1  382.28
  5845.9  383.88  5968.7   386.5  6049.5  386.51  6142.3  389.24  6213.7  390.05
#Mann= 5 ,-1 , 0
  3841.6     .07       0  4959.2    .035       0  5040.8     .07       0
  5040.8     .07       0  6213.7      .1       0
Bank Sta=4959.2,5025.1
XS Rating Curve= 0 ,0
Exp/Cntr=0.3,0.1

Chan Stop Cuts=-1
Use User Specified Reach Order=0
Composite Channel Slope=5