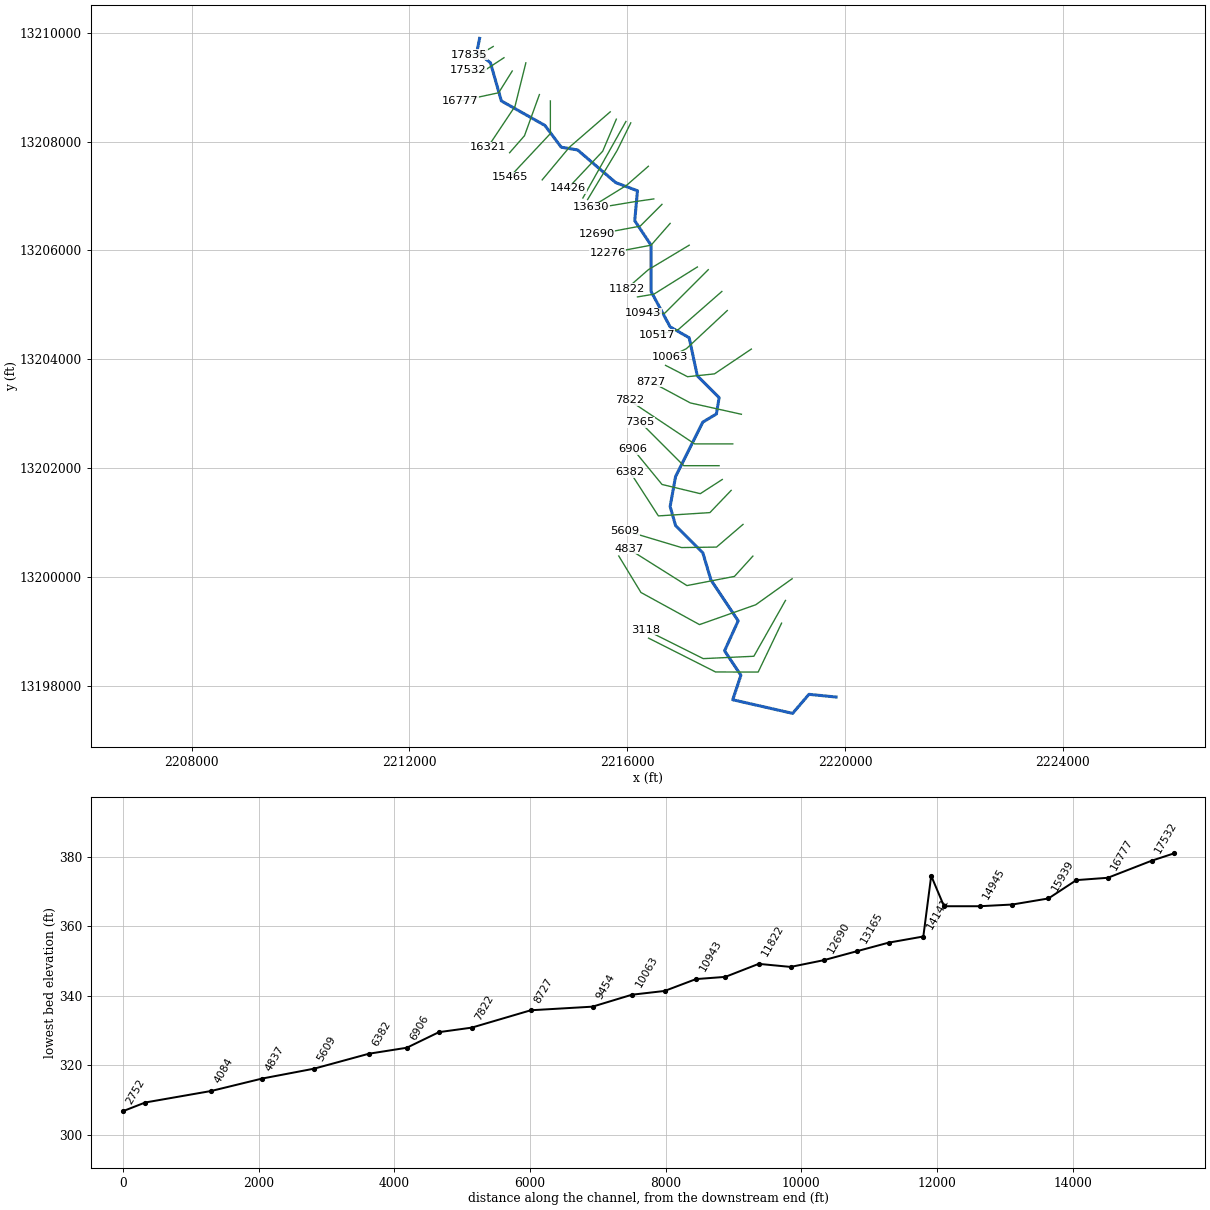
--- UNT 034 IN LACR.prj (project) ---

Proj Title=UNT 034 IN LACR Base Level Engineering
Current Plan=p01
Default Exp/Contr=0.3,0.1
English Units
Geom File=g01
Flow File=f01
Plan File=p01
Y Axis Title=Elevation
X Axis Title(PF)=Main Channel Distance
X Axis Title(XS)=Station
BEGIN DESCRIPTION:
UNT 034 IN LACR
END DESCRIPTION:
DSS Export Rating Curves= 0
DSS Export Rating Curve Sorted= 0
DSS Export Volume Flow Curves= 0
DXF OffsetX= 0
DXF OffsetY= 0
DXF ScaleX= 1
DXF ScaleY= 10

--- UNT 034 IN LACR.p01 (plan) ---

Plan Title=Multiple Run
Short Identifier=Multiple
Geom File=g01
Flow File=f01
Subcritical Flow
K Sum by GR= 0
Std Step Tol= 0.01
Critical Tol= 0.01
Num of Std Step Trials= 20
Max Error Tol= 0.3
Flow Tol Ratio= 0.001
Split Flow NTrial= 30
Split Flow Tol= 0.02
Split Flow Ratio= 0.02
Log Output Level= 0
Friction Slope Method= 1
Unsteady Friction Slope Method= 2
Unsteady Bridges Friction Slope Method= 1
Parabolic Critical Depth
Global Vel Dist=  1 , 1 , 1
Global Log Level= 0
CheckData=True
Encroach Param= -1, 0, 0, 0
BEGIN DESCRIPTION:
Multiple Run
END DESCRIPTION:

--- UNT 034 IN LACR.f01 (steady flow) ---

Flow Title=Multiple
Program Version=4.10
Number of Profiles= 7
Profile Names=10-year,25-year,50-year,1pct_min,100-year,1pct_plu,500-year
River Rch & RM=UNT 034 IN LACR,Reach-1         ,17835
     209     290     359     326     441     597     679
River Rch & RM=UNT 034 IN LACR,Reach-1         ,16777
     309     439     548     504     681     921    1069
River Rch & RM=UNT 034 IN LACR,Reach-1         ,11343
     366     522     654     602     814    1101    1284
River Rch & RM=UNT 034 IN LACR,Reach-1         ,3118
     444     638     804     744    1006    1361    1604
River Rch & RM=UNT 034 IN LACR,Reach-1         ,1563
     444     638     804     744    1006    1361    1604
Boundary for River Rch & Prof#=UNT 034 IN LACR,Reach-1         , 1
Up Type= 0
Dn Type= 3
Dn Slope=0.005
Boundary for River Rch & Prof#=UNT 034 IN LACR,Reach-1         , 2
Up Type= 0
Dn Type= 3
Dn Slope=0.005
Boundary for River Rch & Prof#=UNT 034 IN LACR,Reach-1         , 3
Up Type= 0
Dn Type= 3
Dn Slope=0.005
Boundary for River Rch & Prof#=UNT 034 IN LACR,Reach-1         , 4
Up Type= 0
Dn Type= 3
Dn Slope=0.005
Boundary for River Rch & Prof#=UNT 034 IN LACR,Reach-1         , 5
Up Type= 0
Dn Type= 3
Dn Slope=0.005
Boundary for River Rch & Prof#=UNT 034 IN LACR,Reach-1         , 6
Up Type= 0
Dn Type= 3
Dn Slope=0.005
Boundary for River Rch & Prof#=UNT 034 IN LACR,Reach-1         , 7
Up Type= 0
Dn Type= 3
Dn Slope=0.005
DSS Import GetInterval= 0
DSS Import GetPeak= 0
DSS Import FillOption= 0

--- UNT 034 IN LACR.g01 (geometry) ---

Geom Title=Existing Conditions
Program Version=4.10

River Reach=UNT 034 IN LACR ,Reach-1
Reach XY= 30
      2213287.72     13209896.85      2213237.72     13209646.85
      2213487.72     13209446.85      2213687.72     13208746.85
      2214487.72     13208296.85      2214787.72     13207896.86
      2215087.72     13207846.85      2215787.72     13207246.86
      2216187.72     13207096.86      2216137.72     13206546.85
      2216437.72     13206096.86      2216437.72     13205246.85
      2216787.72     13204596.85      2217137.72     13204396.85
      2217287.72     13203696.85      2217687.72     13203296.86
      2217637.72     13202996.86      2217387.72     13202846.85
      2216887.72     13201846.86      2216787.72     13201296.85
      2216887.72     13200946.85      2217387.72     13200446.85
      2217537.72     13199946.85      2218037.72     13199196.86
      2217787.72     13198646.85      2218087.72     13198196.85
      2217937.72     13197746.86      2219037.72     13197496.85
      2219337.72     13197846.85      2219837.72     13197796.85

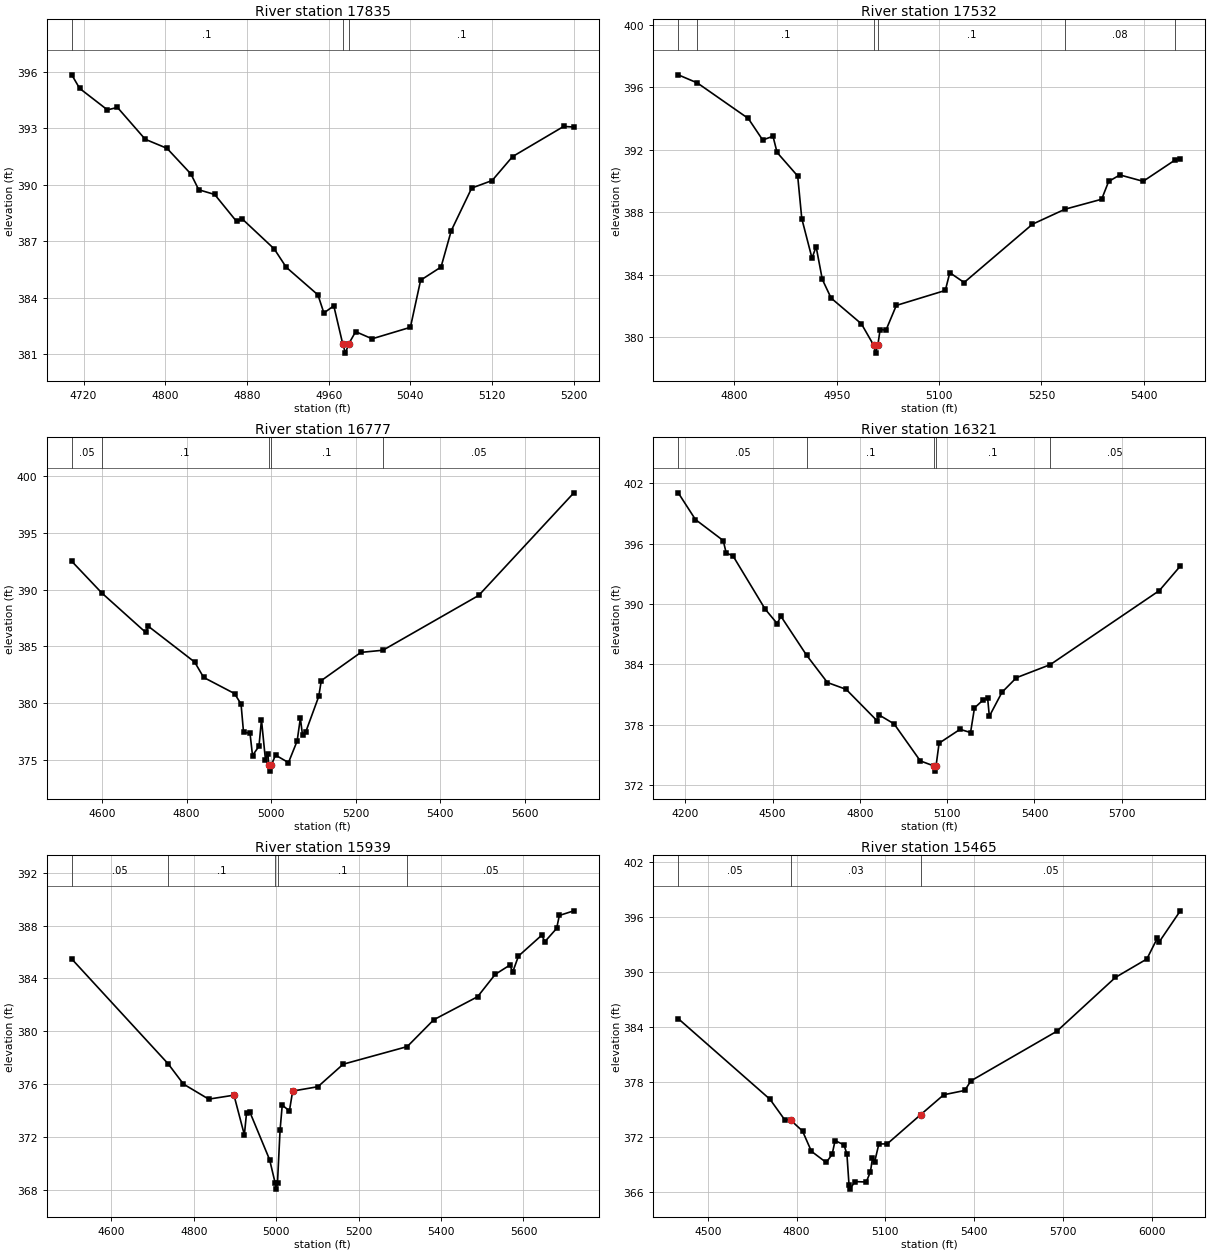
Type RM Length L Ch R = 1 ,17835   ,328,328,328
BEGIN DESCRIPTION:
UNT 034 IN LACR 23.0
END DESCRIPTION:
XS GIS Cut Line= 3
      2213537.68     13209746.83      2213287.72     13209596.85
      2213087.72     13209596.85
#Sta/Elev= 30
  4708.5  395.84  4716.2  395.12  4743.4  393.98  4753.2  394.11  4780.4  392.42
  4801.7  391.94  4825.1  390.58  4832.8  389.74  4848.4  389.49  4869.8  388.06
  4875.6  388.18  4906.7   386.6  4918.4  385.63  4949.5  384.16  4955.3   383.2
    4965  383.58  4973.7  381.57  4976.4  381.07  4979.7  381.57  4986.4  382.21
  5002.5  381.83    5040  382.44    5050  384.94    5070  385.64    5080  387.57
    5100  389.83    5120  390.23    5140   391.5    5190   393.1    5200  393.07
#Mann= 3 ,-1 , 0
  4708.5      .1       0  4973.7     .07       0  4979.7      .1       0
Bank Sta=4973.7,4979.7
XS Rating Curve= 0 ,0
Exp/Cntr=0.3,0.1

Type RM Length L Ch R = 1 ,17532   ,646,646,646
BEGIN DESCRIPTION:
UNT 034 IN LACR 22.0
END DESCRIPTION:
XS GIS Cut Line= 3
      2213735.07     13209540.55      2213318.42     13209267.12
      2213084.01     13209306.19
#Sta/Elev= 30
  4717.6  396.81  4745.6  396.29  4820.3  394.01  4841.4  392.63  4856.5  392.87
  4862.5  391.83  4892.7  390.32  4898.7  387.59  4913.7  385.05  4919.7  385.79
  4928.8  383.69  4941.7  382.49  4986.1  380.84  5004.2  379.46  5006.9  378.96
  5010.2  379.46  5013.5  380.47  5022.2  380.44  5037.3  382.02  5109.1  382.98
  5115.7  384.12  5136.7  383.49  5236.9  387.23  5284.5  388.19  5338.3  388.83
  5348.5  389.97    5365  390.39  5399.1  389.98  5446.4  391.36  5453.6  391.44
#Mann= 6 ,-1 , 0
  4717.6     .05       0  4745.6      .1       0  5004.2     .07       0
  5010.2      .1       0  5284.5     .08       0  5446.4      .1       0
Bank Sta=5004.2,5010.2
XS Rating Curve= 0 ,0
Exp/Cntr=0.3,0.1

Type RM Length L Ch R = 1 ,16777   ,463,463,463
BEGIN DESCRIPTION:
UNT 034 IN LACR 21.0
END DESCRIPTION:
XS GIS Cut Line= 3
      2213887.72     13209296.86      2213637.72     13208896.86
      2212937.71     13208746.85
#Sta/Elev= 30
  4528.3  392.49  4599.2  389.71  4703.4  386.23  4709.3  386.78    4819  383.63
  4840.2  382.28  4913.3  380.86  4928.7  379.94  4934.6  377.45  4949.9  377.38
  4955.8  375.41  4971.1  376.23    4977  378.55  4986.4  375.05  4992.3  375.58
  4994.1  374.54  4996.8  374.04  5000.1  374.54  5010.2  375.45  5040.9  374.79
  5061.4  376.69    5069   378.7  5074.1   377.2  5081.8  377.49  5112.5  380.61
  5118.5     382  5212.2  384.48  5264.3  384.67  5490.9  389.49  5715.9  398.51
#Mann= 5 ,-1 , 0
  4528.3     .05       0  4599.2      .1       0  4994.1     .07       0
  5000.1      .1       0  5264.3     .05       0
Bank Sta=4994.1,5000.1
XS Rating Curve= 0 ,0
Exp/Cntr=0.3,0.1

Type RM Length L Ch R = 1 ,16321   ,412,412,412
BEGIN DESCRIPTION:
UNT 034 IN LACR 20.0
END DESCRIPTION:
XS GIS Cut Line= 3
      2214137.72     13209446.83      2213937.72     13208646.85
      2213437.71     13207896.84
#Sta/Elev= 30
  4175.4  401.07  4234.6  398.41    4330  396.32  4340.3  395.08  4363.5   394.8
  4474.3  389.49  4515.5  388.06  4528.4  388.78  4616.8   384.9  4688.2  382.19
  4752.6  381.51  4858.3   378.4    4866  378.96  4917.5  378.07  5007.5  374.39
  5055.6  373.87  5058.3  373.37  5061.6  373.87  5072.1  376.15  5144.2  377.53
  5180.3  377.21  5193.8  379.66  5223.8  380.46  5238.9  380.66  5244.9  378.83
  5288.4  381.22    5338  382.67  5454.3  383.97  5829.3  391.34  5901.4  393.78
#Mann= 5 ,-1 , 0
  4175.4     .05       0  4616.8      .1       0  5055.6     .07       0
  5061.6      .1       0  5454.3     .05       0
Bank Sta=5055.6,5061.6
XS Rating Curve= 0 ,0
Exp/Cntr=0.3,0.1

Type RM Length L Ch R = 1 ,15939   ,533,533,533
BEGIN DESCRIPTION:
UNT 034 IN LACR 19.0
END DESCRIPTION:
XS GIS Cut Line= 3
      2214386.14     13208863.51      2214112.69     13208108.27
      2213839.22     13207795.74
#Sta/Elev= 30
  4503.7  385.47  4737.6  377.55  4774.7  376.02    4836  374.88  4897.3  375.18
  4922.6  372.18  4927.9  373.86  4936.2  373.88  4983.9   370.3    4997  368.58
  4999.7  368.08    5003  368.58  5009.2  372.53  5014.5  374.43  5031.9  373.99
  5039.8  375.49  5101.1  375.82  5162.4  377.52  5317.8  378.85  5382.3  380.88
  5488.6  382.62  5531.4  384.31  5566.5     385  5574.1  384.51  5587.8  385.69
  5644.3  387.27  5651.9  386.78  5680.4  387.78    5687  388.76  5722.2  389.11
#Mann= 5 ,-1 , 0
  4503.7     .05       0  4737.6      .1       0    4997     .07       0
    5003      .1       0  5317.8     .05       0
Bank Sta=4897.3,5039.8
XS Rating Curve= 0 ,0
Exp/Cntr=0.3,0.1

Type RM Length L Ch R = 1 ,15465   ,482,482,482
BEGIN DESCRIPTION:
UNT 034 IN LACR 18.0
END DESCRIPTION:
XS GIS Cut Line= 3
      2214587.72     13208746.85      2214587.72     13208146.85
      2213837.71     13207346.84
#Sta/Elev= 30
    4400  384.94    4710  376.14    4760  373.89    4780  373.86    4820  372.67
    4850  370.46    4900  369.24    4920  370.12    4930  371.63    4960  371.16
    4970  370.16    4977  366.83  4979.8  366.33  4997.5  367.15  5035.4  367.11
  5049.6  368.24  5056.4  369.73  5063.7   369.3  5077.9  371.26  5106.2  371.27
  5219.3  374.46  5297.2  376.63    5368   377.1  5389.1  378.15  5679.2  383.56
  5877.3  389.44  5983.5  391.45  6018.7  393.71    6026  393.35  6096.6  396.71
#Mann= 3 , 0 , 0
    4400     .05       0    4780     .03       0  5219.3     .05       0
Bank Sta=4780,5219.3
XS Rating Curve= 0 ,0
Exp/Cntr=0.3,0.1

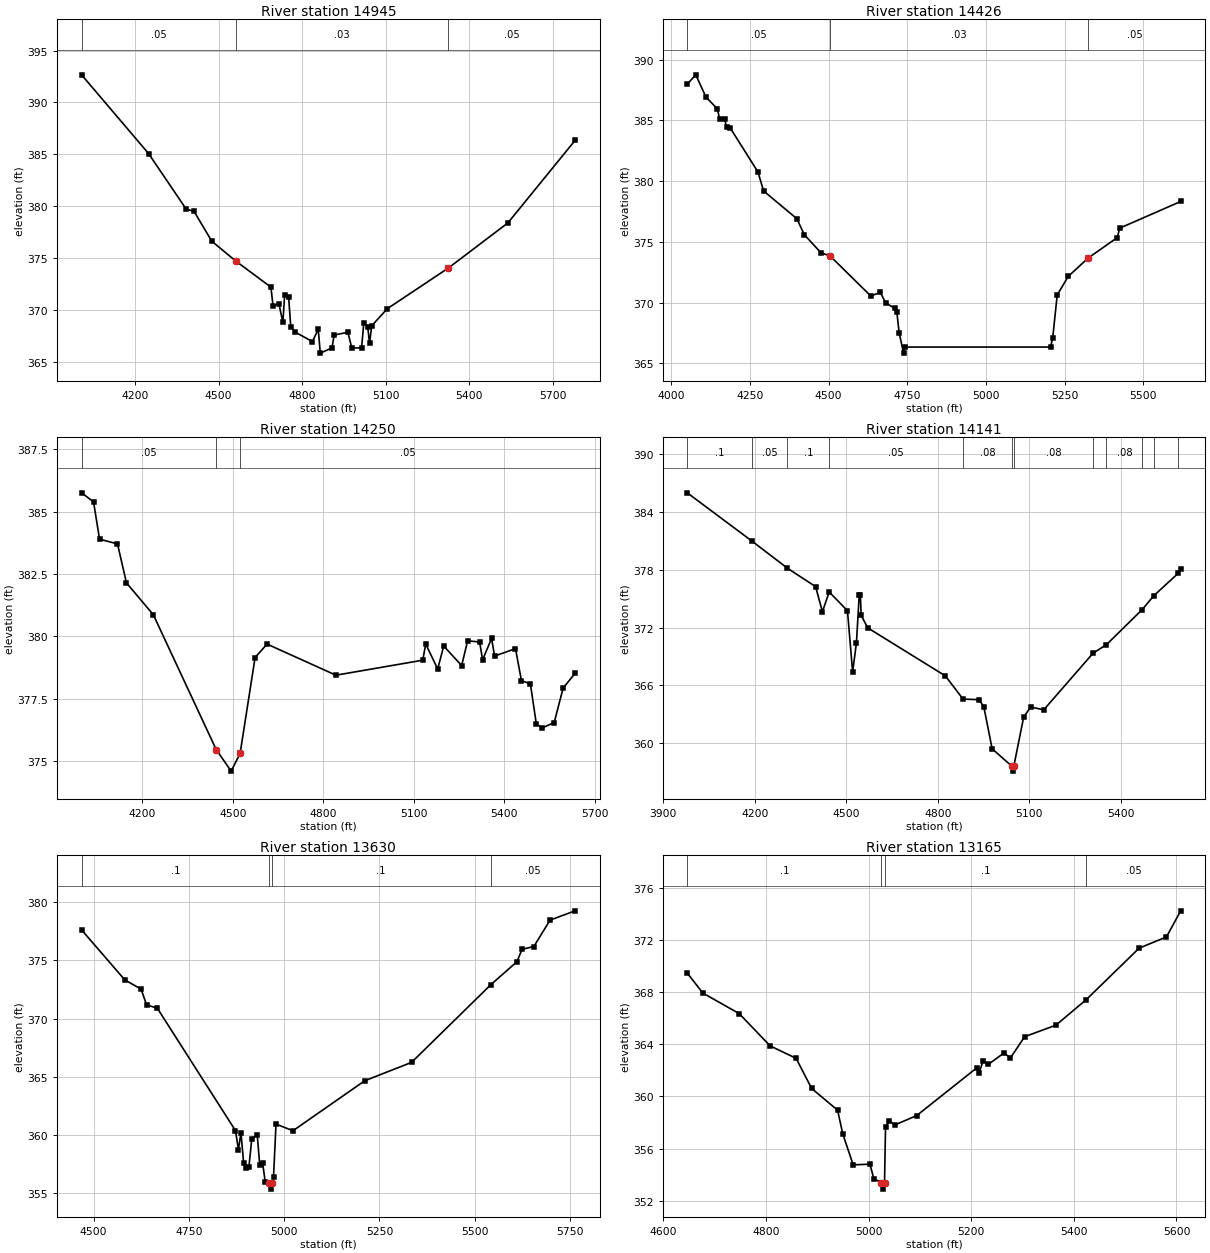
Type RM Length L Ch R = 1 ,14945   ,524,524,524
BEGIN DESCRIPTION:
UNT 034 IN LACR 17.0
END DESCRIPTION:
XS GIS Cut Line= 3
      2215687.74     13208546.87      2214937.72     13207896.86
      2214437.74     13207296.87
#Sta/Elev= 30
  4007.5  392.66  4248.3  385.07  4383.1  379.73  4411.6   379.5  4475.3  376.63
  4560.8  374.73    4688   372.2  4695.6  370.37  4716.5  370.61  4730.8  368.81
  4737.4  371.46  4751.6  371.23  4759.3  368.36  4773.5  367.89  4837.1  366.95
    4858  368.14  4865.4  365.84  4907.4  366.34    4915  367.58  4964.4  367.85
  4978.6  366.34  5013.7  366.34  5021.5   368.7  5035.8  368.39  5042.3  366.78
  5050.1  368.47  5106.1  370.12  5326.1  374.05  5539.6  378.39    5781  386.34
#Mann= 3 , 0 , 0
  4007.5     .05       0  4560.8     .03       0  5326.1     .05       0
Bank Sta=4560.8,5326.1
XS Rating Curve= 0 ,0
Exp/Cntr=0.3,0.1

Type RM Length L Ch R = 1 ,14426   ,189,189,189
BEGIN DESCRIPTION:
UNT 034 IN LACR 16.0
END DESCRIPTION:
XS GIS Cut Line= 3
      2215799.11     13208411.71      2215549.09     13207823.13
       2214913.7     13207146.06
#Sta/Elev= 30
  4050.9  387.98  4077.9  388.74  4110.5   386.9  4146.3  385.95    4154  385.08
  4169.9   385.1  4175.7  384.42  4186.6   384.4  4275.4  380.75  4293.6  379.18
  4399.1   376.9  4422.7  375.59  4475.5   374.1  4504.6  373.84  4633.7  370.55
  4664.6  370.83    4681  369.98  4710.1  369.52  4716.9   369.2  4724.2  367.51
  4738.2  365.84  4741.4  366.34  5205.3  366.34  5212.2  367.12  5226.4  370.63
  5261.6  372.16  5325.5  373.68  5417.4  375.35  5424.7  376.12  5618.9  378.32
#Mann= 3 , 0 , 0
  4050.9     .05       0  4504.6     .03       0  5325.5     .05       0
Bank Sta=4504.6,5325.5
XS Rating Curve= 0 ,0
Exp/Cntr=0.3,0.1

Type RM Length L Ch R = 1 ,14250   ,116,116,116
BEGIN DESCRIPTION:
Mapping XS 6a3fb754
END DESCRIPTION:
XS GIS Cut Line= 2
      2215976.18       13208370.       2215184.5     13206963.73
#Sta/Elev= 30
    3999385.7616 4038.67385.3972  4058.5383.9042 4118.01383.7128 4147.76382.1503
 4237.01380.8692 4445.28375.4655 4494.86 374.601 4524.62375.3138  4574.2379.1567
 4613.87 379.696 4842.16378.4478 5130.03379.0501 5139.95379.6971 5179.66378.6946
 5199.51379.6178 5259.07 378.835 5278.92379.8282 5318.63379.7791 5328.55379.0652
 5358.33 379.922 5368.26379.2135 5437.54379.5154 5457.29378.2267 5486.92378.1039
 5506.67376.4894 5526.42376.3347 5565.93376.5509 5595.55377.9337 5635.06 378.521
#Mann= 3 , 0 , 0
    3999     .05       0 4445.28     .03       0 4524.62     .05       0
Bank Sta=4445.28,4524.62
XS Rating Curve= 0 ,0
Exp/Cntr=0.3,0.1

Type RM Length L Ch R = 1 ,14141   ,511,511,511
BEGIN DESCRIPTION:
UNT 034 IN LACR 15.0
END DESCRIPTION:
XS GIS Cut Line= 3
      2216064.72     13208343.97      2215813.37     13207835.39
      2215271.81     13206935.72
#Sta/Elev= 30
  3979.2  385.97  4192.2  380.94  4307.7  378.15  4399.9  376.24  4422.2  373.64
  4444.4  375.69  4504.3  373.74  4521.2  367.38  4533.7  370.43  4542.9  375.42
  4546.5  375.42  4549.2  373.26  4570.6  371.97    4825  366.99  4883.1  364.58
  4935.7  364.52  4951.2  363.78  4978.4  359.43  5043.4  357.61  5046.1  357.11
  5049.4  357.61  5081.7   362.7  5104.6  363.77  5147.4  363.46  5309.5  369.35
    5353  370.22  5470.5  373.87    5508  375.29    5588  377.62  5596.6  378.07
#Mann= 12 ,-1 , 0
  3979.2      .1       0  4192.2     .05       0  4307.7      .1       0
  4444.4     .05       0  4883.1     .08       0  5043.4     .07       0
  5049.4     .08       0  5309.5      .1       0    5353     .08       0
  5470.5      .1       0    5508     .08       0    5588     .05       0
Bank Sta=5043.4,5049.4
XS Rating Curve= 0 ,0
Exp/Cntr=0.3,0.1

Type RM Length L Ch R = 1 ,13630   ,462,462,462
BEGIN DESCRIPTION:
UNT 034 IN LACR 14.0
END DESCRIPTION:
XS GIS Cut Line= 3
      2216387.71     13207546.85      2215987.72     13207196.85
      2215337.73     13206796.86
#Sta/Elev= 30
  4468.5  377.63  4581.9  373.33  4624.6  372.54  4638.9  371.19  4667.3  370.89
  4872.3  360.37  4879.9  358.72  4886.6  360.18  4893.7  357.57  4900.8  357.15
  4907.5  357.25  4915.1  359.69  4929.3  360.02  4935.9  357.41  4943.5  357.58
  4950.2  355.98  4961.4  355.84  4964.2  355.34  4967.4  355.84    4972  356.36
  4978.6  360.93  5023.1  360.36  5211.4  364.66  5334.3  366.24  5541.9  372.91
  5610.6  374.89  5624.1  375.96    5655   376.2  5697.5  378.47  5763.2  379.27
#Mann= 4 ,-1 , 0
  4468.5      .1       0  4961.4     .07       0  4967.4      .1       0
  5541.9     .05       0
Bank Sta=4961.4,4967.4
XS Rating Curve= 0 ,0
Exp/Cntr=0.3,0.1

Type RM Length L Ch R = 1 ,13165   ,492,492,492
BEGIN DESCRIPTION:
UNT 034 IN LACR 13.0
END DESCRIPTION:
XS GIS Cut Line= 3
      2216487.77     13206946.86      2216137.72     13206896.86
       2215537.7     13206796.85
#Sta/Elev= 30
  4646.4  369.45  4676.8  367.92  4747.5  366.35  4808.1  363.87  4858.6  362.92
  4888.9  360.61  4939.4  358.95  4949.5  357.14  4969.7  354.76  5002.5  354.81
  5010.1  353.69  5024.9   353.4  5027.6   352.9  5030.9   353.4  5032.9  357.69
  5040.6  358.13  5050.7  357.81  5093.8  358.54  5210.4  362.18  5215.4  361.83
    5223  362.73  5233.2  362.45  5263.6  363.33  5276.3  362.95  5304.1  364.58
    5365  365.46  5424.2  367.42  5527.2  371.36  5580.4  372.22  5608.3  374.22
#Mann= 4 ,-1 , 0
  4646.4      .1       0  5024.9     .07       0  5030.9      .1       0
  5424.2     .05       0
Bank Sta=5024.9,5030.9
XS Rating Curve= 0 ,0
Exp/Cntr=0.3,0.1

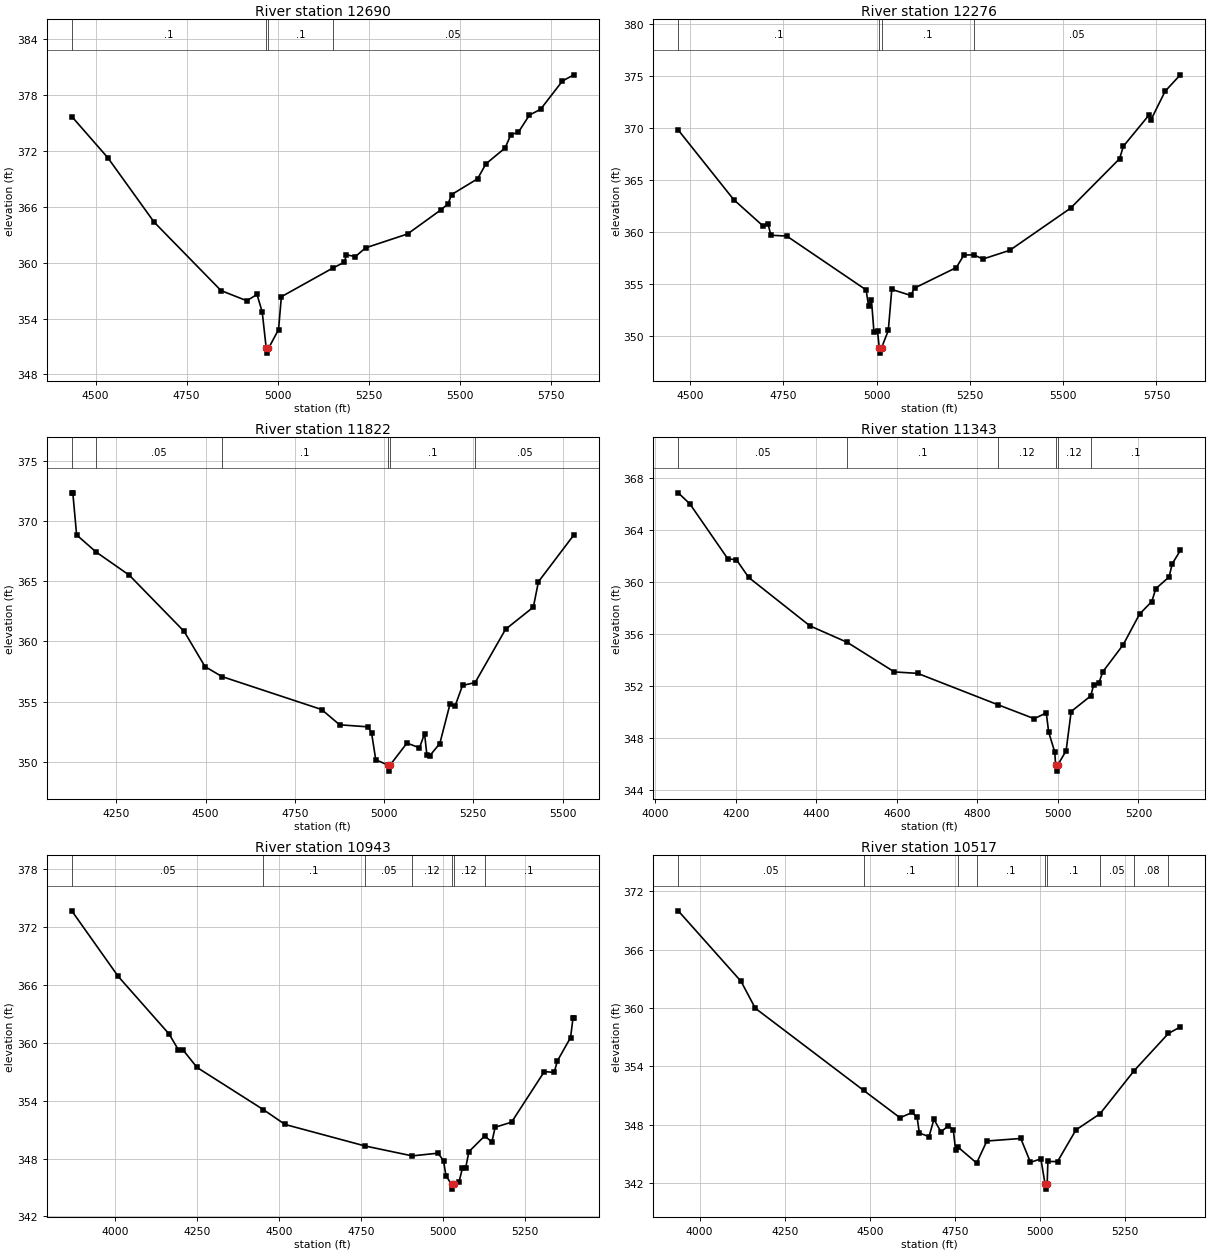
Type RM Length L Ch R = 1 ,12690   ,491,491,491
BEGIN DESCRIPTION:
UNT 034 IN LACR 12.0
END DESCRIPTION:
XS GIS Cut Line= 3
      2216637.73     13206846.87      2216237.72     13206446.85
      2215437.76     13206296.86
#Sta/Elev= 30
  4434.3  375.67  4533.3  371.25  4660.6  364.34  4844.4     357  4915.1  355.91
  4943.4  356.58  4957.6   354.7  4968.7  350.79  4971.5  350.29  4974.7  350.79
  5002.5  352.82  5010.2  356.34  5150.9   359.4  5183.1  360.04  5189.1  360.83
  5213.7  360.65  5241.6  361.58  5356.9  363.07  5447.7  365.63    5468  366.29
  5478.2   367.3  5549.4  368.99  5572.3  370.59  5624.9  372.29    5641  373.73
  5661.3  373.97  5691.8  375.82  5722.4  376.44  5782.6  379.48  5813.9  380.14
#Mann= 4 ,-1 , 0
  4434.3      .1       0  4968.7     .07       0  4974.7      .1       0
  5150.9     .05       0
Bank Sta=4968.7,4974.7
XS Rating Curve= 0 ,0
Exp/Cntr=0.3,0.1

Type RM Length L Ch R = 1 ,12276   ,471,471,471
BEGIN DESCRIPTION:
UNT 034 IN LACR 11.0
END DESCRIPTION:
XS GIS Cut Line= 3
      2216787.72     13206496.85      2216437.72     13206096.86
      2215637.76     13205946.86
#Sta/Elev= 30
  4468.5   369.8    4617  363.11  4694.9   360.6  4709.1  360.78  4716.7  359.68
  4759.4   359.6    4972  354.42  4978.6  352.85  4986.2  353.47  4992.9  350.41
  5002.5  350.48  5007.2  348.84  5009.9  348.34  5013.2  348.84  5031.4  350.52
  5040.7  354.47  5091.6  353.89  5101.7   354.6  5213.7  356.57    5234  357.78
  5260.9  357.79  5284.9  357.39  5356.9  358.23  5519.7  362.28  5651.2  367.04
  5661.3  368.24    5730  371.24  5735.1  370.77  5773.2  373.53  5813.9  375.11
#Mann= 4 ,-1 , 0
  4468.5      .1       0  5007.2     .07       0  5013.2      .1       0
  5260.9     .05       0
Bank Sta=5007.2,5013.2
XS Rating Curve= 0 ,0
Exp/Cntr=0.3,0.1

Type RM Length L Ch R = 1 ,11822   ,491,491,491
BEGIN DESCRIPTION:
UNT 034 IN LACR 10.0
END DESCRIPTION:
XS GIS Cut Line= 3
      2217137.68     13206096.83      2216387.72     13205646.85
      2215987.73     13205296.86
#Sta/Elev= 30
  4125.4  372.35  4128.3  372.35    4139  368.85  4193.6  367.43  4286.7   365.5
  4440.2  360.83  4498.5  357.91  4545.9  357.08  4825.1  354.34  4875.6  353.07
  4955.3   352.9    4965   352.4  4976.7  350.17  5010.8  349.72  5013.5  349.22
  5016.8  349.72  5064.1  351.55  5099.2  351.16  5113.4  352.33  5120.1  350.53
  5127.7  350.49  5156.1  351.51  5184.6  354.79  5198.8  354.62  5219.7  356.34
    5255  356.58  5340.3  361.01  5418.1  362.85  5432.3  364.96  5531.5  368.85
#Mann= 6 ,-1 , 0
  4125.4      .1       0  4193.6     .05       0  4545.9      .1       0
  5010.8     .07       0  5016.8      .1       0    5255     .05       0
Bank Sta=5010.8,5016.8
XS Rating Curve= 0 ,0
Exp/Cntr=0.3,0.1

Type RM Length L Ch R = 1 ,11343   ,433,433,433
BEGIN DESCRIPTION:
UNT 034 IN LACR 9.0
END DESCRIPTION:
XS GIS Cut Line= 3
      2217287.72     13205696.86      2216487.72     13205196.85
      2216187.76     13205146.86
#Sta/Elev= 30
  4056.6  366.85  4085.5     366  4179.8  361.78  4201.1  361.71  4231.7  360.35
  4383.8  356.63  4476.7  355.36  4593.7  353.09  4651.5  352.98  4850.1  350.58
    4941   349.5  4971.1  349.94    4977  348.47  4992.3  346.92  4994.1  345.97
  4996.8  345.47  5000.1  345.97  5020.3  347.03  5032.9  350.05  5081.6  351.25
  5088.7  352.09  5101.4  352.21  5111.5   353.1  5162.2  355.18  5202.8  357.53
  5233.2   358.5  5243.3  359.49  5276.3  360.39  5283.9  361.39  5304.1  362.42
#Mann= 6 ,-1 , 0
  4056.6     .05       0  4476.7      .1       0  4850.1     .12       0
  4994.1     .07       0  5000.1     .12       0  5081.6      .1       0
Bank Sta=4994.1,5000.1
XS Rating Curve= 0 ,0
Exp/Cntr=0.3,0.1

Type RM Length L Ch R = 1 ,10943   ,462,462,462
BEGIN DESCRIPTION:
UNT 034 IN LACR 8.0
END DESCRIPTION:
XS GIS Cut Line= 3
      2217487.74     13205646.88      2216687.72     13204846.85
      2216287.72     13204846.85
#Sta/Elev= 30
  3868.6  373.71  4010.1  366.91  4165.6  360.92  4193.9  359.28    4208  359.27
  4250.5  357.46  4452.5  353.09  4519.2  351.54  4762.9  349.31    4907  348.28
  4985.9  348.56  5002.5  347.77    5010  346.21    5027  345.33  5029.8  344.83
    5033  345.33    5050  345.61    5060  346.98    5070  347.04    5080  348.72
  5127.8  350.34    5150  349.73    5160  351.25    5210  351.78    5310  357.03
    5340  356.94    5350  358.15    5390  360.56  5397.5   362.6    5400   362.6
#Mann= 7 ,-1 , 0
  3868.6     .05       0  4452.5      .1       0  4762.9     .05       0
    4907     .12       0    5027     .07       0    5033     .12       0
  5127.8      .1       0
Bank Sta=5027,5033
XS Rating Curve= 0 ,0
Exp/Cntr=0.3,0.1

Type RM Length L Ch R = 1 ,10517   ,483,483,483
BEGIN DESCRIPTION:
UNT 034 IN LACR 7.0
END DESCRIPTION:
XS GIS Cut Line= 3
      2217737.71     13205246.85      2216937.72     13204546.85
      2216537.73     13204446.86
#Sta/Elev= 30
    3937  369.98  4121.6  362.74  4163.4  359.98  4481.6  351.55  4588.6  348.74
  4624.6  349.28  4638.9  348.78  4645.5  347.17    4674   346.8  4688.2  348.57
  4709.1  347.29  4730.9  347.92  4745.2   347.5  4751.8  345.44  4759.2  345.72
  4813.8  344.09  4843.9  346.35  4943.5  346.61    4972  344.16  5002.6  344.52
    5015  341.91  5017.8  341.41    5021  341.91  5023.2  344.25  5051.5  344.24
  5105.7  347.49  5176.5  349.15  5276.9  353.58  5377.3  357.39  5412.3  358.06
#Mann= 9 ,-1 , 0
    3937     .05       0  4481.6      .1       0  4759.2     .12       0
  4813.8      .1       0    5015     .07       0    5021      .1       0
  5176.5     .05       0  5276.9     .08       0  5377.3     .05       0
Bank Sta=5015,5021
XS Rating Curve= 0 ,0
Exp/Cntr=0.3,0.1

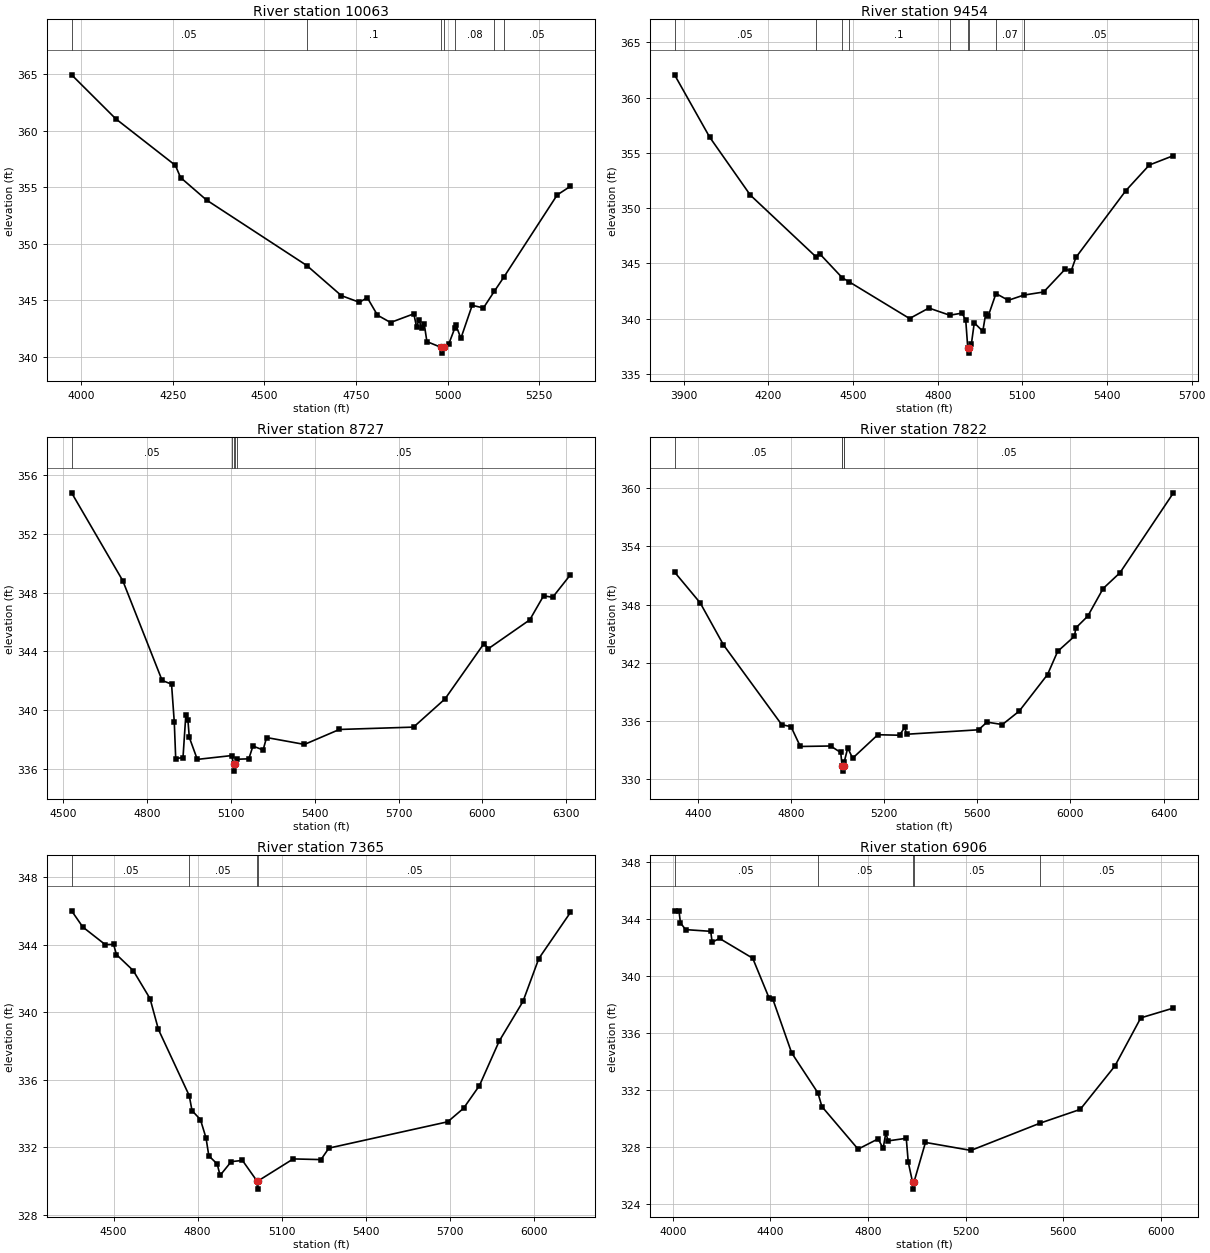
Type RM Length L Ch R = 1 ,10063   ,580,580,580
BEGIN DESCRIPTION:
UNT 034 IN LACR 6.0
END DESCRIPTION:
XS GIS Cut Line= 3
      2217837.71     13204896.85      2217087.72     13204196.85
      2216787.73     13204046.86
#Sta/Elev= 30
  3974.1  364.95  4094.5  361.06  4257.2  356.94  4271.4  355.86  4342.2  353.87
    4616  348.07  4710.1  345.41  4759.4  344.82  4780.9  345.23  4808.7  343.68
  4844.4  343.03  4907.9   343.8  4915.2  342.66  4922.1  343.23  4929.4  342.54
  4936.2  342.91  4943.6  341.34  4983.1  340.82  4985.8  340.32  4989.1  340.82
  5002.8  341.09  5019.4  342.51  5022.4  342.83  5036.3  341.63  5067.1  344.55
  5097.8  344.32  5127.5  345.79    5154  347.07  5299.1  354.32  5335.4  355.09
#Mann= 7 ,-1 , 0
  3974.1     .05       0    4616      .1       0  4983.1     .07       0
  4989.1      .1       0  5019.4     .08       0  5127.5      .1       0
    5154     .05       0
Bank Sta=4983.1,4989.1
XS Rating Curve= 0 ,0
Exp/Cntr=0.3,0.1

Type RM Length L Ch R = 1 ,9454    ,910,910,910
BEGIN DESCRIPTION:
UNT 034 IN LACR 5.0
END DESCRIPTION:
XS GIS Cut Line= 4
      2218279.39     13204189.02      2217602.27     13203733.27
      2217107.48     13203681.18      2216703.81     13203889.53
#Sta/Elev= 30
  3867.5  362.06  3991.9  356.42  4135.9  351.18  4368.4   345.6  4381.8  345.87
  4462.5  343.68  4484.4  343.36  4700.3  340.01  4768.7  340.96  4842.7  340.31
  4886.3   340.5  4899.4  339.86  4906.5  337.38  4909.3  336.88  4912.5  337.38
  4919.6  337.75  4929.6  339.62  4959.8  338.86  4969.8  340.39  4979.3  340.25
  5006.5  342.27  5050.3  341.66  5104.9  342.13  5175.4  342.41  5251.1  344.46
  5273.3  344.34  5289.8  345.54    5467  351.59    5550   353.9  5635.5  354.75
#Mann= 9 ,-1 , 0
  3867.5     .05       0  4368.4     .07       0  4462.5     .05       0
  4484.4      .1       0  4842.7     .12       0  4906.5     .07       0
  4912.5     .12       0  5006.5     .07       0  5104.9     .05       0
Bank Sta=4906.5,4912.5
XS Rating Curve= 0 ,0
Exp/Cntr=0.3,0.1

Type RM Length L Ch R = 1 ,8727    ,871,871,871
BEGIN DESCRIPTION:
UNT 034 IN LACR 4.0
END DESCRIPTION:
XS GIS Cut Line= 3
      2218097.02     13202991.09      2217159.56     13203199.41
      2216431.57     13203589.41
#Sta/Elev= 30
  4529.5  354.81  4712.7  348.82  4853.6  342.02  4887.3  341.77  4897.1  339.18
  4902.2   336.7  4928.3  336.76  4938.5  339.69  4945.8  339.34  4950.9  338.14
  4979.5  336.64  5102.4   336.9  5109.7  336.34  5112.4  335.84  5115.7  336.34
  5122.9  336.65  5163.9  336.68  5178.8  337.55  5215.1  337.28  5227.5  338.13
  5363.2  337.66  5488.2  338.68  5753.8  338.84  5866.3  340.76  6005.7  344.53
  6021.9  344.19  6169.8  346.15  6219.3  347.79  6251.8  347.69  6315.7  349.23
#Mann= 5 ,-1 , 0
  4529.5     .05       0  5102.4     .12       0  5109.7     .03       0
  5115.7     .12       0  5122.9     .05       0
Bank Sta=5109.7,5115.7
XS Rating Curve= 0 ,0
Exp/Cntr=0.3,0.1

Type RM Length L Ch R = 1 ,7822    ,483,483,483
BEGIN DESCRIPTION:
UNT 034 IN LACR 3.0
END DESCRIPTION:
XS GIS Cut Line= 3
      2217937.72     13202446.85      2217237.72     13202446.85
      2216037.74     13203246.84
#Sta/Elev= 30
    4300  351.34    4410  348.17    4510  343.84    4760  335.62    4800  335.41
    4840  333.37    4970  333.42  5013.5  332.75  5019.5  331.33  5022.3  330.83
  5025.5  331.33  5028.5  331.78  5043.6  333.22  5064.6  332.16  5172.8  334.58
  5265.9  334.53  5288.4  335.35    5296  334.63  5605.4  335.09  5641.5  335.88
  5707.6  335.63  5779.7  337.01  5901.4  340.78    5945  343.17  6017.1  344.73
  6023.1  345.59  6074.2   346.8  6140.3  349.65  6212.4  351.27  6442.2  359.51
#Mann= 5 ,-1 , 0
    4300     .05       0  5019.5     .12       0  5019.5     .07       0
  5025.5     .12       0  5028.5     .05       0
Bank Sta=5019.5,5025.5
XS Rating Curve= 0 ,0
Exp/Cntr=0.3,0.1

Type RM Length L Ch R = 1 ,7365    ,474,474,474
BEGIN DESCRIPTION:
UNT 034 IN LACR 2.0
END DESCRIPTION:
XS GIS Cut Line= 3
      2217687.72     13202046.85      2217037.72     13202046.85
       2216237.7     13202846.88
#Sta/Elev= 30
    4350  346.02    4390  345.06    4470  344.02    4500  344.03    4510  343.43
    4570  342.48    4630  340.82    4660  338.99    4770  335.07    4780  334.18
    4810  333.65    4830  332.56    4840   331.5    4870  331.02    4880  330.34
    4920  331.16    4960  331.23  5011.1  330.03  5013.9  329.53  5017.1  330.03
  5141.4  331.32  5240.4  331.28  5268.7  331.96    5693  333.52  5749.5  334.32
  5806.1  335.66  5876.8   338.3  5961.7  340.65  6018.2  343.19  6131.4  345.93
#Mann= 4 ,-1 , 0
    4350     .05       0    4770     .05       0  5011.1     .07       0
  5017.1     .05       0
Bank Sta=5011.1,5017.1
XS Rating Curve= 0 ,0
Exp/Cntr=0.3,0.1

Type RM Length L Ch R = 1 ,6906    ,558,558,558
BEGIN DESCRIPTION:
Mapping XS 632c129c
END DESCRIPTION:
XS GIS Cut Line= 4
      2217745.52     13201793.17      2217341.85     13201532.75
      2216638.73     13201702.02       2216105.4     13202352.42
#Sta/Elev= 30
  4007.1  344.56  4025.2  344.58  4031.1  343.74  4052.2  343.26  4155.2  343.14
  4161.1  342.38  4191.5  342.64  4327.4  341.25  4394.1  338.47  4409.1  338.41
    4487   334.6  4594.6  331.79  4610.9  330.83  4759.2  327.84  4841.4  328.56
    4862  327.89  4872.8  328.98  4882.6  328.42  4956.7   328.6  4964.9  326.92
  4982.4  325.53  4985.2  325.03  4988.4  325.53  5035.4  328.31  5221.8  327.75
    5506  329.67  5669.6  330.63  5811.8  333.68  5917.9  337.06  6051.8  337.75
#Mann= 5 ,-1 , 0
  4007.1     .05       0  4594.6     .05       0  4982.4     .03       0
  4988.4     .05       0    5506     .05       0
Bank Sta=4982.4,4988.4
XS Rating Curve= 0 ,0
Exp/Cntr=0.3,0.1

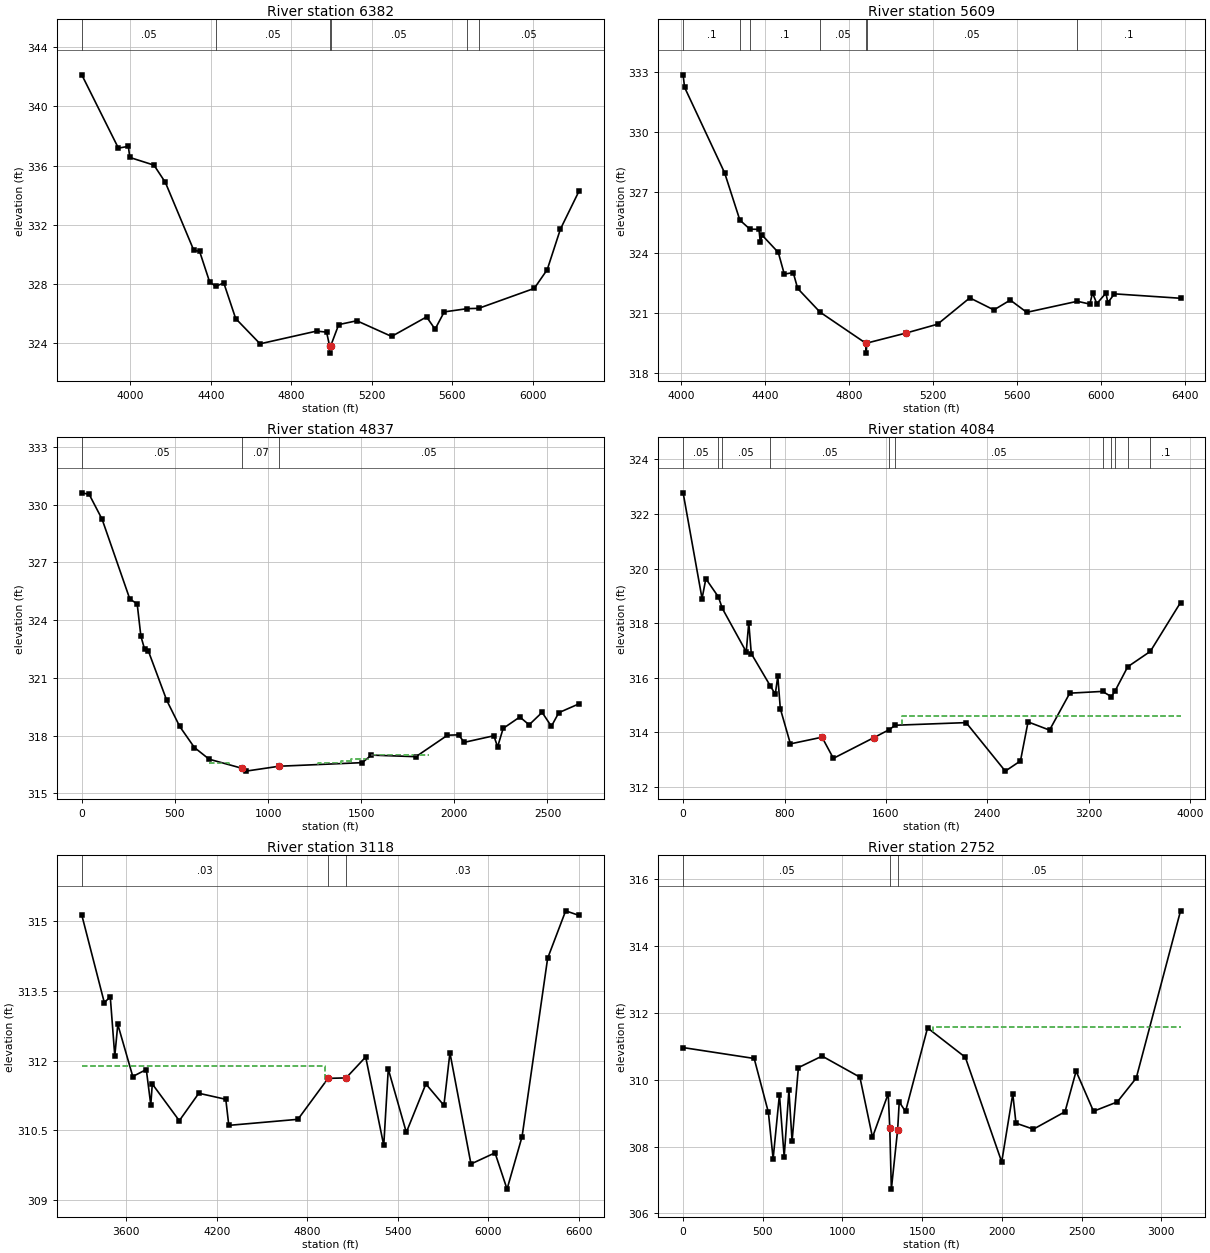
Type RM Length L Ch R = 1 ,6382    ,808,808,808
BEGIN DESCRIPTION:
Mapping XS 8f6dce19
END DESCRIPTION:
XS GIS Cut Line= 4
      2217908.99     13201592.95      2217518.34     13201184.93
      2216572.16     13201124.17      2216052.05     13201930.34
#Sta/Elev= 30
  3758.4  342.14  3940.4  337.18  3989.8   337.3  3997.1  336.55  4117.2  336.03
  4173.8  334.86  4315.3  330.26  4343.9   330.2    4394  328.12  4424.1  327.83
  4464.2  328.06  4523.3  325.65  4644.6  323.94  4925.1   324.8  4975.2  324.73
  4989.9  323.81  4992.6  323.31  4995.9  323.81  5035.4  325.24  5125.5   325.5
  5298.4  324.44  5472.1  325.76  5514.4  324.93  5559.9   326.1  5674.7  326.32
    5731  326.34  6007.4  327.69  6071.9  328.96  6137.4   331.7  6230.8   334.3
#Mann= 6 ,-1 , 0
  3758.4     .05       0  4424.1     .05       0  4989.9     .03       0
  4995.9     .05       0  5674.7      .1       0    5731     .05       0
Bank Sta=4989.9,4995.9
XS Rating Curve= 0 ,0
Exp/Cntr=0.3,0.1

Type RM Length L Ch R = 1 ,5609    ,765,765,765
BEGIN DESCRIPTION:
Mapping XS 48c2e17e
END DESCRIPTION:
XS GIS Cut Line= 4
        2218126.     13200967.94      2217639.87     13200551.25
       2216997.5     13200542.57      2215955.87     13200855.06
#Sta/Elev= 30
  4007.9  332.85  4014.7  332.23  4205.7  327.97  4278.2  325.62  4326.1  325.17
  4369.2  325.16  4375.8  324.51  4383.5  324.88  4461.4  324.01    4490  322.93
  4532.5  323.01  4553.6  322.22  4660.3  321.04  4877.3   319.5  4880.1     319
  4883.3   319.5  5070.4     320  5220.4  320.44  5373.9  321.75  5488.7  321.15
  5566.8  321.64  5645.3  321.03  5886.2  321.58  5946.1  321.44  5958.6     322
  5979.2  321.46  6022.7  321.99  6031.6  321.51    6063  321.95  6378.1  321.73
#Mann= 7 ,-1 , 0
  4007.9      .1       0  4278.2     .05       0  4326.1      .1       0
  4660.3     .05       0  4877.3     .03       0  4883.3     .05       0
  5886.2      .1       0
Bank Sta=4877.3,5070.4
XS Rating Curve= 0 ,0
Exp/Cntr=0.3,0.1

Type RM Length L Ch R = 1 ,4837    ,749,749,749
BEGIN DESCRIPTION:
Mapping XS 779f3a86
END DESCRIPTION:
XS GIS Cut Line= 4
      2218308.24     13200386.29      2217969.73     13200013.06
     2217096.541    13199844.242     2216025.353    13200518.439
#Sta/Elev= 30
       0330.6074   39.65330.5271  109.04329.2351  257.74325.0952  297.39324.8392
  317.21323.1612  337.04322.4965  356.87322.4059     456319.8303  525.36318.4796
  604.48317.3809  683.59316.7736  861.59316.2975  881.37316.1541 1059.37 316.408
 1505.13316.5943 1554.92316.9861 1793.91316.9049 1963.19318.0201 2022.94318.0385
 2052.81317.6483 2212.14317.9908 2232.05317.4113 2261.93318.3718 2351.55318.9661
 2401.34318.5594 2471.04319.2062 2520.83318.4815 2560.66319.1896  2670.2319.6534
#Mann= 3 , 0 , 0
       0     .05       0  861.59     .07       0 1059.37     .05       0
#XS Ineff= 6 ,-1
  682.74  792.13  316.59 1058.46 1242.54   316.4 1265.93 1389.66  316.59
    1390 1444.74  316.67 1444.74 1544.33  316.78  1554.5  1861.2  316.99
Permanent Ineff=
       F       F       F       F       F       F
Bank Sta=861.59,1059.37
XS Rating Curve= 0 ,0
Exp/Cntr=0.3,0.1

Type RM Length L Ch R = 1 ,4084    ,976,976,976
BEGIN DESCRIPTION:
Mapping XS 96437717
END DESCRIPTION:
XS GIS Cut Line= 5
      2219028.75     13199969.65      2218360.35     13199492.22
      2217327.37     13199127.64       2216251.8     13199717.47
     2215843.876    13200388.387
#Sta/Elev= 30
       0322.7765 149.413318.9007179.2956 319.627278.9043318.9587308.7869318.5442
498.0434316.9472517.9651318.0193537.8869316.8845687.2999315.7053727.1434315.3958
747.0651316.0535766.9869314.8658846.6974313.57561096.014313.82021185.768313.0451
1504.894313.80311624.566314.09221674.429314.25842233.059314.35472542.372312.5766
2662.105312.95042721.973314.38072891.596314.08013051.241315.43373309.875315.4985
3379.375315.3048 3409.16315.51833508.445316.40033687.158 316.9663925.442318.7565
#Mann= 11 ,-1 , 0
       0     .05       0278.9043      .1       0308.7869     .05       0
687.2999     .05       01624.566      .1       01674.429     .05       0
3309.875      .1       03379.375     .07       0 3409.16      .1       0
3508.445     .05       03687.158      .1       0
#XS Ineff= 2 , 0
       0   937.5  312.26    1725       0  314.58
Permanent Ineff=
       F       F
Bank Sta=1096.014,1504.894
XS Rating Curve= 0 ,0
Exp/Cntr=0.3,0.1

Type RM Length L Ch R = 1 ,3118    ,329,329,329
BEGIN DESCRIPTION:
Mapping XS 1e5f44bf
END DESCRIPTION:
XS GIS Cut Line= 4
     2218906.883     13199571.85      2218325.63    13198546.044
      2217396.81    13198502.641     2216337.782    13199032.155
#Sta/Elev= 30
  3306.3  315.13 3455.36  313.25  3495.1  313.37 3524.91   312.1 3544.79  312.78
 3644.16  311.66 3733.59  311.81  3763.4  311.05 3773.34   311.5 3952.21  310.71
 4081.39   311.3 4260.25  311.17 4280.13  310.61 4738.15  310.74 4937.63  311.62
 5057.31  311.63 5186.97  312.08 5306.66  310.18 5336.58  311.82  5456.2  310.46
 5585.66   311.5 5705.15  311.04 5744.99  312.17  5884.4  309.78 6043.73  310.02
 6123.39  309.24 6222.97  310.37 6392.26   314.2 6511.75  315.22 6601.37  315.12
#Mann= 3 , 0 , 0
  3306.3     .03       0 4937.63     .03       0 5057.31     .03       0
#XS Ineff= 2 , 0
       0 4915.91  311.88 5188.64       0  311.88
Permanent Ineff=
       T       T
Bank Sta=4937.63,5057.31
XS Rating Curve= 0 ,0
Exp/Cntr=0.3,0.1

Type RM Length L Ch R = 1 ,2752    ,344,344,344
BEGIN DESCRIPTION:
Mapping XS 233a85b8
END DESCRIPTION:
XS GIS Cut Line= 4
      2218835.07     13199154.44      2218405.39     13198256.02
     2217622.774    13198257.258     2216391.351    13198879.074
#Sta/Elev= 30
       0310.9578  445.88310.6323  535.06309.0207  564.78307.6312  604.42309.5542
  634.14307.6921  663.87309.6824  683.68308.1532  723.32310.3582  871.95 310.704
 1109.33310.0738 1188.31308.2767 1287.05309.5793 1296.92308.5403 1306.79306.7266
 1346.29308.5059 1356.16309.3313 1395.65309.0488 1533.88311.5458  1770.9310.6682
 1999.32307.5394 2068.84309.5744  2088.7308.6989 2197.94308.5181 2396.57  309.04
 2466.09310.2526 2575.33309.0542  2724.3309.3324 2843.48310.0466 3121.55315.0458
#Mann= 3 , 0 , 0
       0     .05       0 1296.92     .03       0 1346.29     .05       0
#XS Ineff= 2 , 0
          869.03  310.48 1567.05          311.57
Permanent Ineff=
       F       F
Bank Sta=1296.92,1346.29
XS Rating Curve= 0 ,0
Exp/Cntr=0.3,0.1