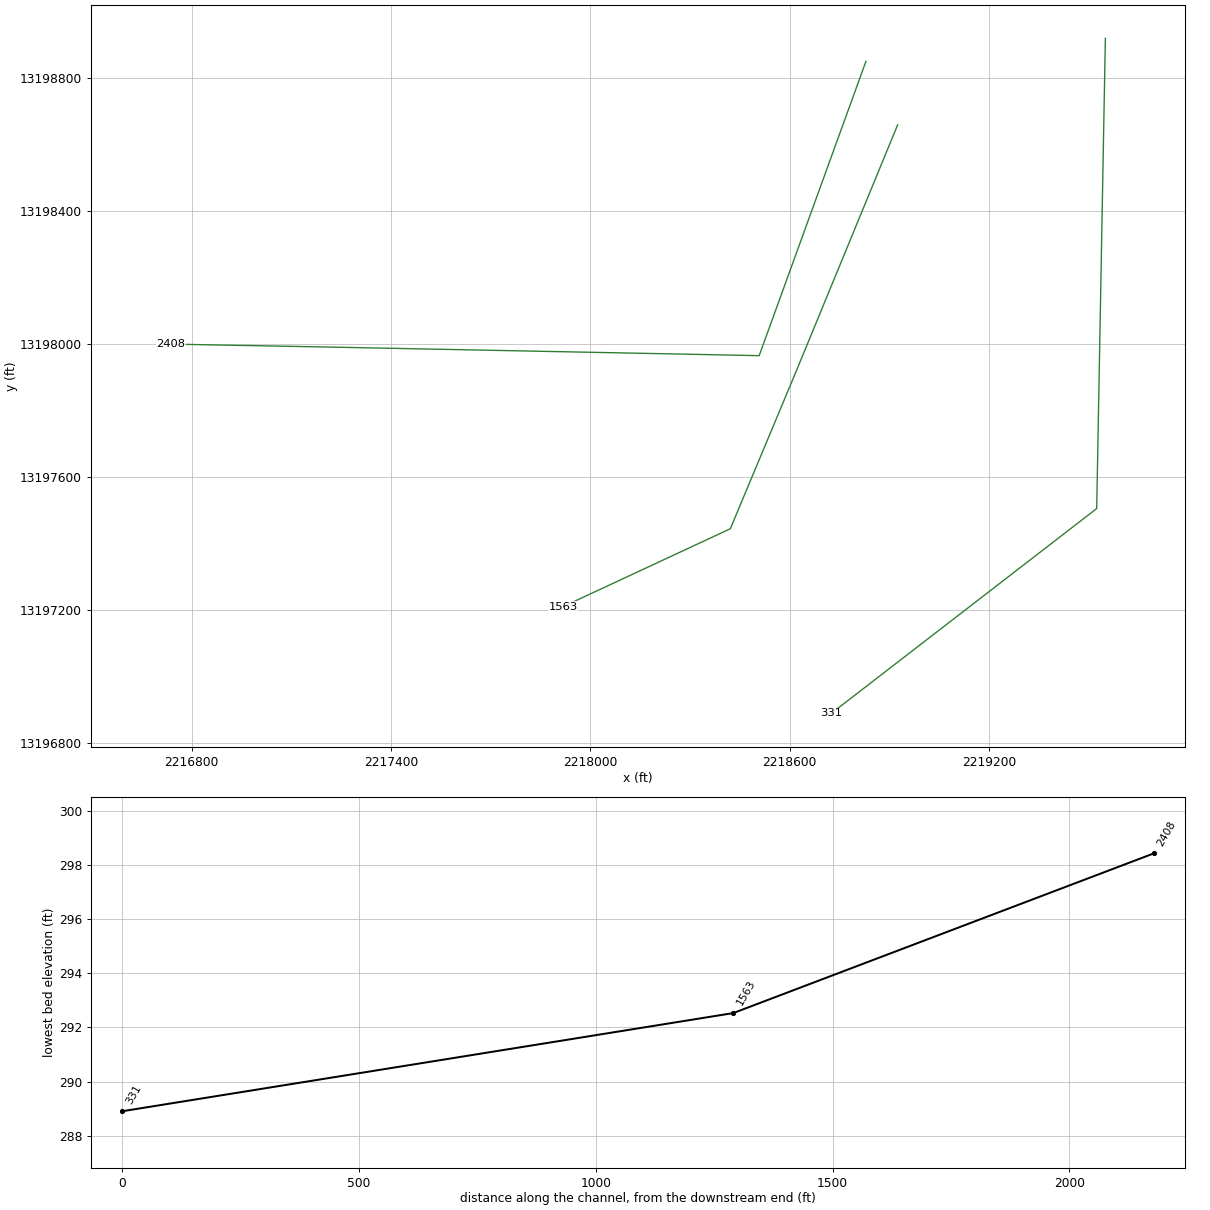
HEC-RAS study UNT 034 IN LACR.prj: UNT 034 IN LACR Base Level Engineering

--- UNT 034 IN LACR.g01 (geometry) --- (continued)

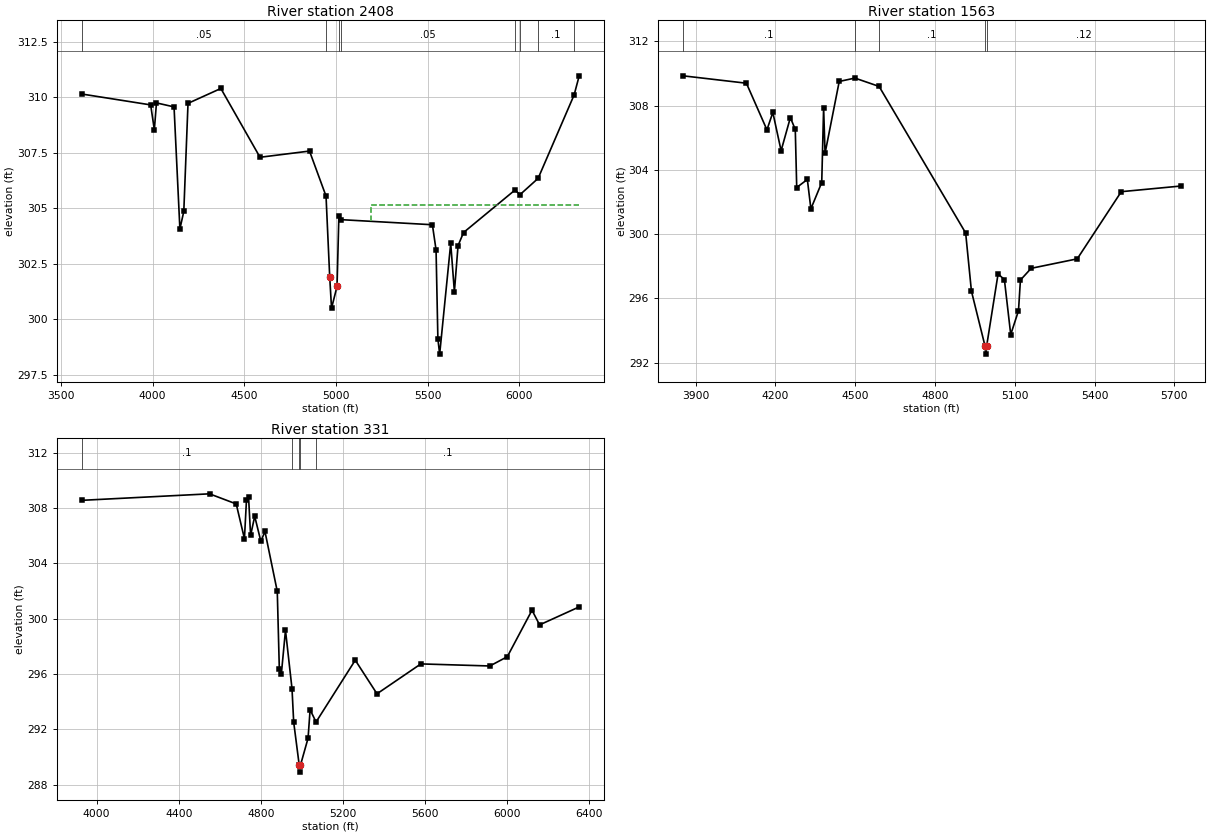
Type RM Length L Ch R = 1 ,2408    ,888,888,888
BEGIN DESCRIPTION:
Mapping XS 548e46a5
END DESCRIPTION:
XS GIS Cut Line= 4
       2218829.1     13198849.87      2218507.92     13197964.45
      2217205.84     13197990.49      2216737.04     13197999.17
#Sta/Elev= 30
  3614.3  310.14    3990  309.65    4010  308.53  4021.7  309.74  4117.5  309.56
  4149.4  304.06  4170.7  304.85  4193.7  309.72  4372.8  310.39  4586.4  307.29
  4856.4  307.57  4946.5  305.54  4966.5  301.91  4976.5  300.49  5006.5  301.47
  5016.5  304.63  5026.5  304.48  5526.6  304.25  5546.6  303.12  5556.6   299.1
  5566.3  298.42  5626.6  303.41  5646.6  301.23  5666.6  303.31  5696.6   303.9
  5976.7  305.81  6005.1  305.61  6103.3  306.34  6299.7   310.1  6327.4  310.96
#Mann= 8 ,-1 , 0
  3614.3     .05       0  4946.5     .03       0  5016.5      .1       0
  5026.5     .05       0  5976.7      .1       0  6005.1     .08       0
  6103.3      .1       0  6299.7     .08       0
#XS Ineff= 2 ,-1
 3667.05  4364.2  309.96 5192.61  6327.4  305.14
Permanent Ineff=
       T       F
Bank Sta=4966.5,5006.5
XS Rating Curve= 0 ,0
Exp/Cntr=0.3,0.1

Type RM Length L Ch R = 1 ,1563    ,1290,1290,1290
BEGIN DESCRIPTION:
Mapping XS 14817724
END DESCRIPTION:
XS GIS Cut Line= 4
      2218924.58     13198658.88      2218620.77     13197921.04
      2218421.12     13197443.61      2217917.63     13197209.23
#Sta/Elev= 30
  3852.6  309.85  4090.6  309.39  4167.8  306.49    4190  307.57  4221.1  305.19
  4255.9  307.25  4274.4  306.51  4279.8   302.9  4319.8   303.4  4333.1  301.57
  4373.9  303.21    4381  307.86  4386.4  305.03  4439.7   309.5  4498.7  309.71
  4589.7  309.19  4915.2  300.07  4936.9  296.45  4988.1  293.03  4990.8  292.53
  4994.1  293.03  5037.1  297.52  5060.9  297.17  5084.7  293.75  5113.9  295.23
  5121.2  297.14  5161.5  297.87  5334.9  298.46  5500.5  302.64  5723.4  302.99
#Mann= 5 ,-1 , 0
  3852.6      .1       0  4498.7     .05       0  4589.7      .1       0
  4988.1     .07       0  4994.1     .12       0
#XS Ineff= 1 ,-1
 3997.16 4465.91  309.16
Permanent Ineff=
       F
Bank Sta=4988.1,4994.1
XS Rating Curve= 0 ,0
Exp/Cntr=0.3,0.1

Type RM Length L Ch R = 1 ,331     ,0,0,0
BEGIN DESCRIPTION:
UNT 034 IN LACR 1.0
END DESCRIPTION:
XS GIS Cut Line= 3
      2219549.59     13198919.27      2219523.55     13197504.38
      2218724.94     13196888.07
#Sta/Elev= 30
  3927.4  308.55  4549.9  309.02  4679.9  308.29    4720  305.78    4730  308.59
    4740  308.82    4750  306.01    4770   307.4    4800  305.59    4820   306.3
    4880  301.97    4890  296.38    4900  296.03    4920  299.16  4951.8  294.94
    4960  292.52    4987  289.41  4989.7  288.91    4993  289.41    5030  291.36
    5040  293.42  5068.9  292.53    5260     297  5365.9  294.57  5579.7  296.73
  5915.8  296.58  6000.9  297.25  6121.3  300.61  6158.3  299.55  6351.3  300.85
#Mann= 5 ,-1 , 0
  3927.4      .1       0  4951.8     .12       0    4987     .07       0
    4993     .12       0  5068.9      .1       0
Bank Sta=4987,4993
XS Rating Curve= 0 ,0
Exp/Cntr=0.3,0.1
Stream Node=UNT 034 IN LACR ,Reach-1         , 0 , 0 ,Upstream end
Stream Node=UNT 034 IN LACR ,Reach-1         , 0 , 1 ,Downstream end

Chan Stop Cuts=-1
Use User Specified Reach Order=0
Composite Channel Slope=5