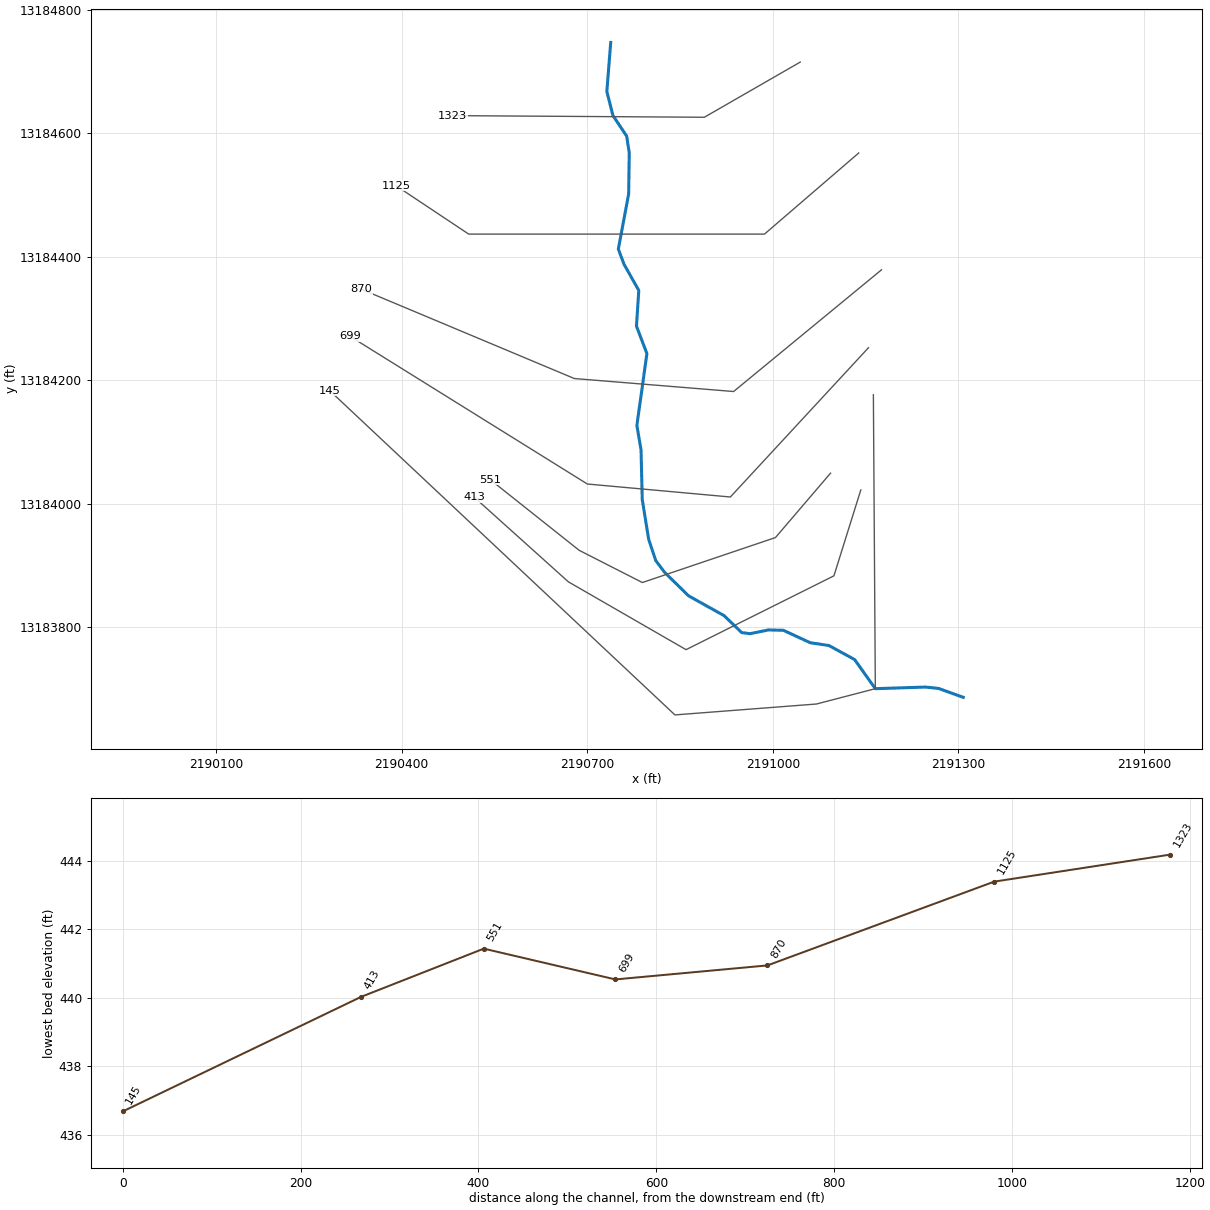
--- UNT 037 IN LACR.prj (project) ---

Proj Title=UNT 037 IN LACR Base Level Engineering
Current Plan=p01
Default Exp/Contr=0.3,0.1
English Units
Geom File=g01
Flow File=f01
Plan File=p01
Y Axis Title=Elevation
X Axis Title(PF)=Main Channel Distance
X Axis Title(XS)=Station
BEGIN DESCRIPTION:
UNT 037 IN LACR
END DESCRIPTION:
DSS Export Rating Curves= 0
DSS Export Rating Curve Sorted= 0
DSS Export Volume Flow Curves= 0
DXF OffsetX= 0
DXF OffsetY= 0
DXF ScaleX= 1
DXF ScaleY= 10

--- UNT 037 IN LACR.p01 (plan) ---

Plan Title=Multiple Run
Short Identifier=Multiple
Geom File=g01
Flow File=f01
Subcritical Flow
K Sum by GR= 0
Std Step Tol= 0.01
Critical Tol= 0.01
Num of Std Step Trials= 20
Max Error Tol= 0.3
Flow Tol Ratio= 0.001
Split Flow NTrial= 30
Split Flow Tol= 0.02
Split Flow Ratio= 0.02
Log Output Level= 0
Friction Slope Method= 1
Unsteady Friction Slope Method= 2
Unsteady Bridges Friction Slope Method= 1
Parabolic Critical Depth
Global Vel Dist=  1 , 1 , 1
Global Log Level= 0
CheckData=True
Encroach Param= -1, 0, 0, 0
BEGIN DESCRIPTION:
Multiple Run
END DESCRIPTION:

--- UNT 037 IN LACR.f01 (steady flow) ---

Flow Title=Multiple
Program Version=4.10
Number of Profiles= 7
Profile Names=10-year,25-year,50-year,1pct_min,100-year,1pct_plu,500-year
River Rch & RM=UNT 037 IN LACR,Reach-1         ,1323
      94     125     150     133     180     243     261
River Rch & RM=UNT 037 IN LACR,Reach-1         ,145
      94     125     150     133     180     243     261
Boundary for River Rch & Prof#=UNT 037 IN LACR,Reach-1         , 1
Up Type= 0
Dn Type= 3
Dn Slope=0.012
Boundary for River Rch & Prof#=UNT 037 IN LACR,Reach-1         , 2
Up Type= 0
Dn Type= 3
Dn Slope=0.012
Boundary for River Rch & Prof#=UNT 037 IN LACR,Reach-1         , 3
Up Type= 0
Dn Type= 3
Dn Slope=0.012
Boundary for River Rch & Prof#=UNT 037 IN LACR,Reach-1         , 4
Up Type= 0
Dn Type= 3
Dn Slope=0.012
Boundary for River Rch & Prof#=UNT 037 IN LACR,Reach-1         , 5
Up Type= 0
Dn Type= 3
Dn Slope=0.012
Boundary for River Rch & Prof#=UNT 037 IN LACR,Reach-1         , 6
Up Type= 0
Dn Type= 3
Dn Slope=0.012
Boundary for River Rch & Prof#=UNT 037 IN LACR,Reach-1         , 7
Up Type= 0
Dn Type= 3
Dn Slope=0.012
DSS Import GetInterval= 0
DSS Import GetPeak= 0
DSS Import FillOption= 0

--- UNT 037 IN LACR.g01 (geometry) ---

Geom Title=Existing Conditions
Program Version=4.10

River Reach=UNT 037 IN LACR ,Reach-1
Reach XY= 30
      2190737.99     13184746.85      2190731.75     13184667.44
      2190741.57     13184628.56      2190763.77     13184595.23
      2190767.98     13184568.21        2190767.     13184501.53
      2190750.31     13184412.33      2190759.54     13184387.66
      2190783.36     13184345.45      2190779.64     13184287.54
       2190796.5     13184243.17      2190780.28     13184126.88
      2190787.02     13184087.56      2190788.96     13184006.94
      2190799.38     13183942.54      2190810.87     13183908.11
      2190825.06     13183889.16      2190863.89     13183851.06
      2190921.19     13183819.05      2190949.74     13183791.56
      2190963.04      13183789.8      2190992.92      13183795.9
      2191017.06     13183795.32      2191060.59     13183775.17
      2191090.68     13183770.68      2191132.17     13183747.98
      2191165.66     13183700.83      2191246.66     13183703.44
       2191267.9     13183701.21      2191307.72     13183686.85

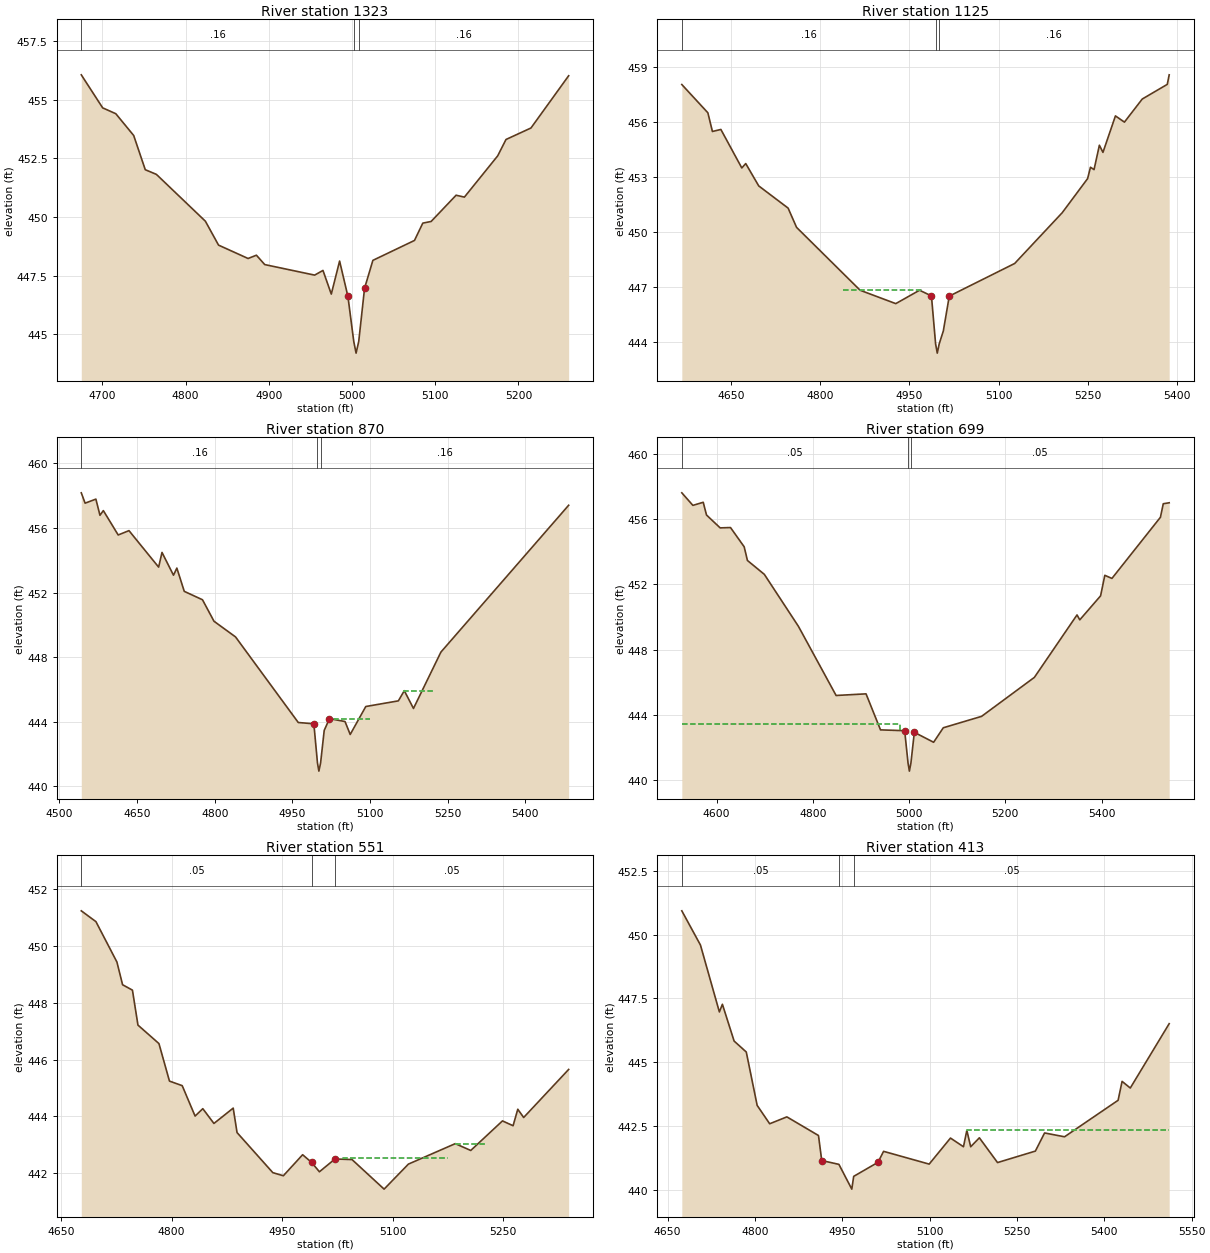
Type RM Length L Ch R = 1 ,1323    ,198,198,198
BEGIN DESCRIPTION:
UNT 037 IN LACR 1.0
END DESCRIPTION:
XS GIS Cut Line= 3
      2191044.33     13184715.03      2190889.35     13184625.72
      2190482.43     13184628.35
#Sta/Elev= 30
  4674.6  456.07  4700.3  454.66  4716.1  454.41  4737.6  453.48  4751.5  452.02
  4764.9  451.82  4823.8  449.82  4839.6   448.8  4875.1  448.23  4885.1  448.37
  4895.1  447.97  4955.1  447.52  4965.1  447.72  4975.1  446.71  4985.1  448.12
  4995.1  446.61  5002.1  444.69  5004.9  444.19  5008.1  444.69  5015.1  446.96
  5025.1  448.15  5075.1     449  5085.1  449.74  5095.1  449.81  5125.1  450.93
  5135.1  450.85  5175.1  452.61  5185.1  453.31  5215.1   453.8  5260.4  456.03
#Mann= 3 ,-1 , 0
  4674.6     .16       0  5002.1     .07       0  5008.1     .16       0
#XS Ineff= 1 ,-1
 4860.77 4985.28  448.07
Permanent Ineff=
       T
Bank Sta=4995.1,5015.1
XS Rating Curve= 0 ,0
Exp/Cntr=0.3,0.1

Type RM Length L Ch R = 1 ,1125    ,255,255,255
BEGIN DESCRIPTION:
Mapping XS e4cd7e87
END DESCRIPTION:
XS GIS Cut Line= 4
      2191138.86     13184567.92      2190986.53      13184436.6
      2190508.48      13184436.6      2190391.47      13184514.6
#Sta/Elev= 30
  4567.2  458.05    4611  456.51  4618.7  455.49  4632.9   455.6  4668.1   453.5
  4674.7  453.74  4696.6  452.52    4746  451.31  4760.2  450.26  4867.1  446.83
  4927.1   446.1  4967.1  446.83  4987.1  446.52  4994.1   443.9  4996.9   443.4
  5000.1   443.9  5007.1  444.61  5017.1  446.51  5127.1  448.29  5207.1  451.06
  5249.8  452.92  5254.6  453.54  5260.6  453.41  5269.6  454.74  5275.6  454.35
  5296.6  456.34  5311.7     456  5341.7  457.26  5383.8  458.06    5387  458.58
#Mann= 3 ,-1 , 0
  4567.2     .16       0  4994.1     .07       0  5000.1     .16       0
#XS Ineff= 1 ,-1
 4838.74 4969.17  446.83
Permanent Ineff=
       T
Bank Sta=4987.1,5017.1
XS Rating Curve= 0 ,0
Exp/Cntr=0.3,0.1

Type RM Length L Ch R = 1 ,870     ,171,171,171
BEGIN DESCRIPTION:
Mapping XS cd99cd4c
END DESCRIPTION:
XS GIS Cut Line= 4
      2191175.69     13184378.84      2190936.63     13184181.81
      2190679.21     13184202.82      2190335.07     13184347.31
#Sta/Elev= 30
  4542.2  458.18  4549.6  457.54  4570.4  457.79  4578.3  456.79  4584.8  457.08
  4613.5  455.57  4634.3  455.84  4691.6  453.58  4698.1  454.49  4720.3  453.08
  4726.8  453.52  4741.1  452.08  4776.3  451.56  4798.5  450.23  4840.1  449.26
  4961.3  443.96  4991.4  443.88  4998.4  441.45  5001.1  440.95  5004.4  441.45
  5011.4  443.47  5021.5   444.2  5051.6  444.02  5061.6  443.22  5091.7  444.95
  5154.6   445.3  5166.1  445.93  5183.8  444.83  5236.8  448.32  5483.5  457.41
#Mann= 3 ,-1 , 0
  4542.2     .16       0  4998.4     .07       0  5004.4     .16       0
#XS Ineff= 2 ,-1
 5030.83  5099.6  444.17 5164.82  5225.3  445.91
Permanent Ineff=
       T       T
Bank Sta=4991.4,5021.5
XS Rating Curve= 0 ,0
Exp/Cntr=0.3,0.1

Type RM Length L Ch R = 1 ,699     ,148,148,148
BEGIN DESCRIPTION:
Mapping XS dc02f019
END DESCRIPTION:
XS GIS Cut Line= 4
      2191154.63     13184252.72      2190931.37     13184011.08
      2190700.23     13184032.09      2190316.71     13184271.13
#Sta/Elev= 30
  4527.6  457.61  4550.6  456.84  4572.1  457.03  4578.9  456.25  4607.3  455.46
  4628.8  455.48  4657.2   454.3    4664  453.46  4699.1  452.61    4770  449.42
  4848.3  445.18  4910.5  445.28  4940.6  443.07  4990.8  443.02  4997.8  441.04
  5000.6  440.54  5003.8  441.04  5010.9  442.92    5051  442.31  5071.1   443.2
  5150.7   443.9  5260.4  446.29    5349  450.12  5354.8  449.82    5398  451.29
  5406.8  452.55  5421.6  452.36  5522.4  456.11  5528.3  456.94  5540.6     457
#Mann= 3 ,-1 , 0
  4527.6     .05       0  4997.8     .07       0  5003.8     .05       0
#XS Ineff= 2 , 0
       0 4980.73  443.43               0
Permanent Ineff=
       T       F
Bank Sta=4990.8,5010.9
XS Rating Curve= 0 ,0
Exp/Cntr=0.3,0.1

Type RM Length L Ch R = 1 ,551     ,138,138,138
BEGIN DESCRIPTION:
Mapping XS 03dc8ec6
END DESCRIPTION:
XS GIS Cut Line= 5
      2191093.31     13184049.68      2191004.25     13183945.41
      2190789.15     13183872.63      2190687.03     13183924.77
      2190543.64     13184038.84
#Sta/Elev= 30
  4677.2  451.23  4697.1  450.85  4725.6  449.43  4733.3  448.63  4746.7  448.44
  4754.2  447.21  4782.7  446.56    4797  445.24  4814.3  445.08  4831.8  444.01
  4842.3  444.27  4857.4  443.75  4883.6  444.29  4888.8  443.43  4937.4  442.02
  4951.7  441.91  4977.9  442.65  4990.1  442.38  5000.7  442.05  5021.8   442.5
    5045  442.48  5088.6  441.44  5121.6  442.32  5185.3  443.04  5206.3   442.8
  5249.4  443.84  5263.8  443.67  5270.2  444.25  5278.2  443.96  5339.3  445.65
#Mann= 3 , 0 , 0
  4677.2     .05       0  4990.1     .03       0  5021.8     .05       0
#XS Ineff= 3 ,-1
 4885.38 4977.87  442.52  5033.2 5175.49  442.52 5184.98 5228.46  443.04
Permanent Ineff=
       T       T       T
Bank Sta=4990.1,5021.8
XS Rating Curve= 0 ,0
Exp/Cntr=0.3,0.1

Type RM Length L Ch R = 1 ,413     ,268,268,268
BEGIN DESCRIPTION:
Mapping XS ec7d8f93
END DESCRIPTION:
XS GIS Cut Line= 5
      2191142.21     13184022.53      2191098.76     13183883.49
      2190859.76     13183763.99      2190669.65     13183873.71
      2190517.56     13184010.59
#Sta/Elev= 30
  4674.4  450.93  4706.4  449.59  4738.9  446.97  4744.1  447.27  4764.2  445.83
  4785.1   445.4  4803.8  443.31  4825.3  442.59  4854.8  442.86  4909.1  442.13
  4914.7  441.15  4944.2     441  4966.3  440.03  4969.6  440.53  5011.3  441.08
  5020.9  441.51  5099.2  441.01  5135.8  442.03  5158.1  441.69  5163.9  442.33
  5170.5  441.69  5185.4  442.04  5216.6  441.07  5281.6  441.52  5297.4  442.23
  5331.7  442.08  5423.7  443.51  5430.5  444.25  5444.6  443.99  5511.4  446.51
#Mann= 3 ,-1 , 0
  4674.4     .05       0  4944.2     .03       0  4969.6     .05       0
#XS Ineff= 2 ,-1
                         5164.23  5511.4  442.35
Permanent Ineff=
       F       F
Bank Sta=4914.7,5011.3
XS Rating Curve= 0 ,0
Exp/Cntr=0.3,0.1

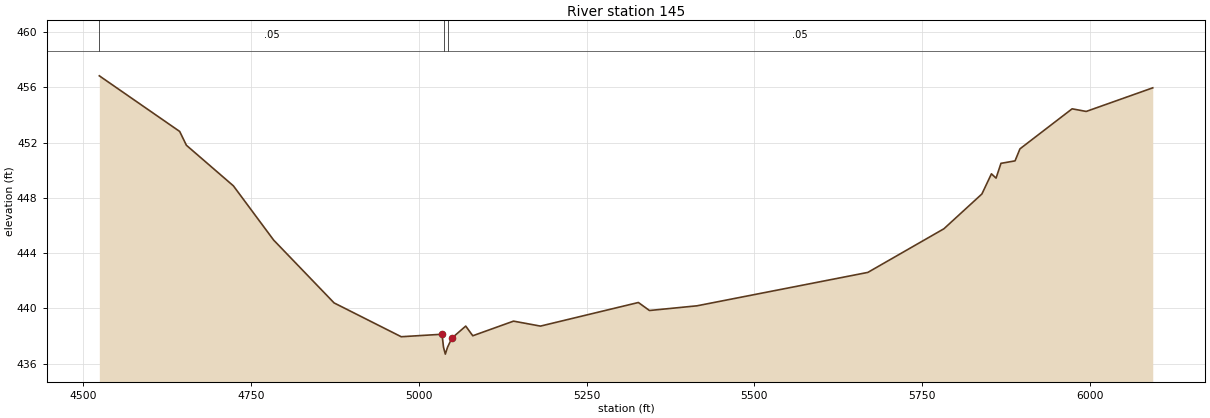
Type RM Length L Ch R = 1 ,145     ,0,0,0
BEGIN DESCRIPTION:
UNT 037 IN LACR 2.0
END DESCRIPTION:
XS GIS Cut Line= 5
      2191162.52     13184176.52      2191165.66     13183700.83
      2191070.52       13183676.      2190841.76     13183658.37
      2190284.04     13184183.06
#Sta/Elev= 30
  4524.3  456.84    4644  452.81    4654  451.81    4724  448.87    4784  444.94
    4874  440.39    4974  437.94  5034.8  438.12    5037  437.18  5039.7  436.68
    5043  437.18  5049.5  437.84  5070.1  438.71  5080.6  438.01  5141.3  439.07
  5181.4  438.71  5327.3  440.42  5343.8  439.84  5414.6  440.18  5669.1   442.6
  5782.4  445.76    5839  448.28  5853.2  449.74  5860.1  449.43  5867.4   450.5
  5888.4  450.68  5895.7  451.55  5973.4  454.45  5994.4  454.26  6093.5  455.97
#Mann= 3 ,-1 , 0
  4524.3     .05       0    5037     .03       0    5043     .05       0
#XS Ineff= 1 ,-1
 5326.68 5467.19   440.3
Permanent Ineff=
       T
Bank Sta=5034.8,5049.5
XS Rating Curve= 0 ,0
Exp/Cntr=0.3,0.1

Chan Stop Cuts=-1
Use User Specified Reach Order=0
Composite Channel Slope=5