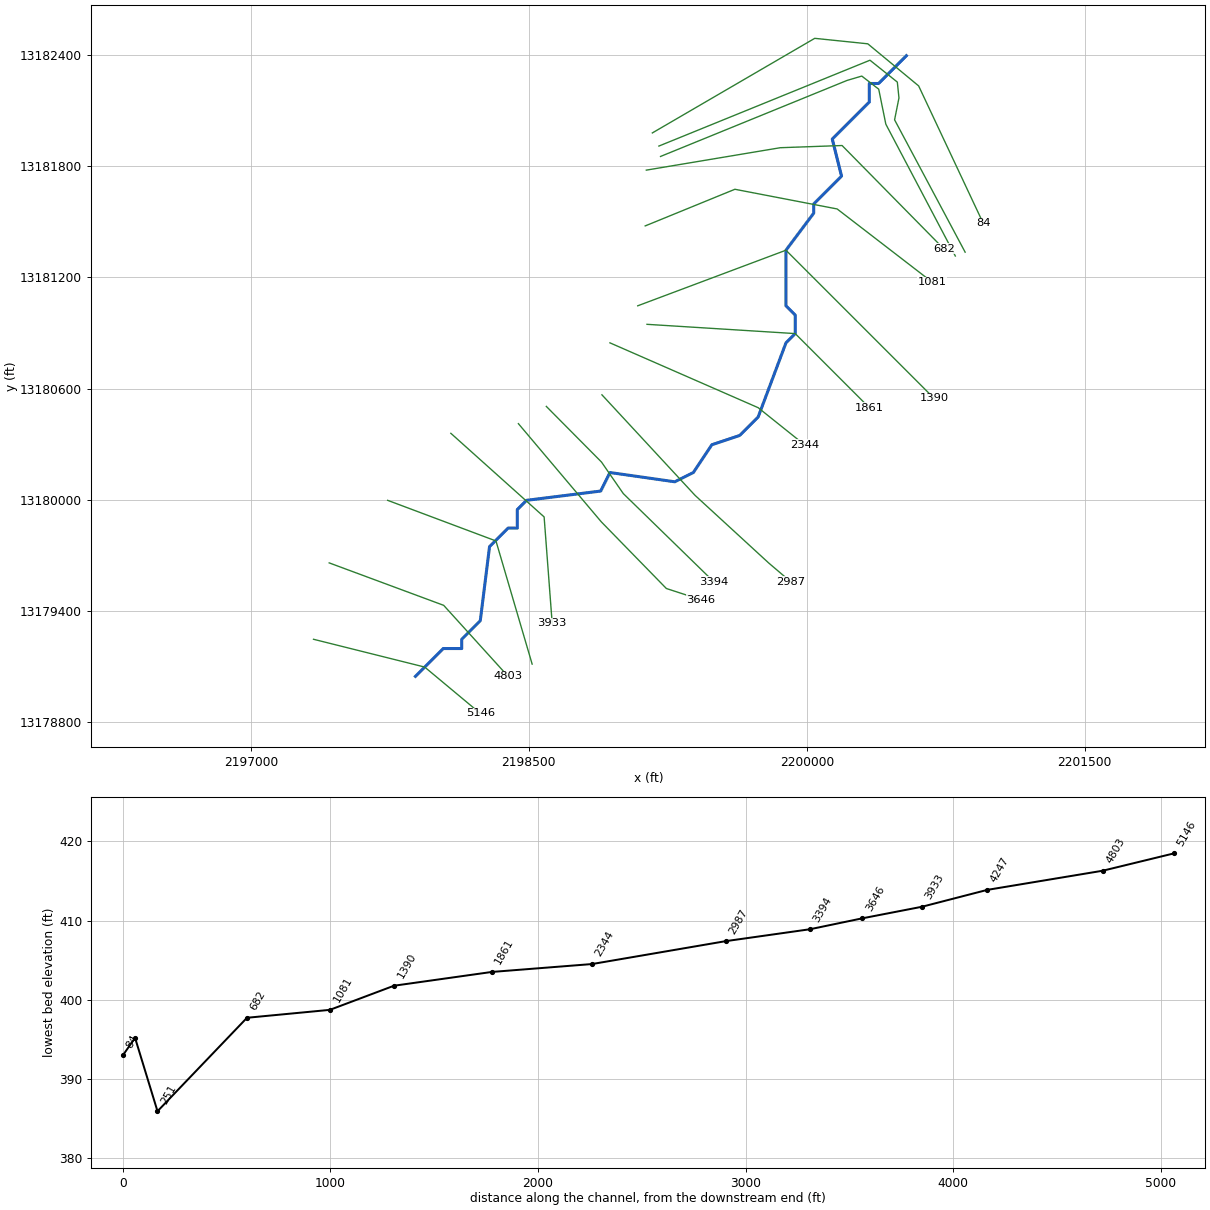
--- UNT 038 IN LACR.prj (project) ---

Proj Title=UNT 038 IN LACR Base Level Engineering
Current Plan=p01
Default Exp/Contr=0.3,0.1
English Units
Geom File=g01
Flow File=f01
Plan File=p01
Y Axis Title=Elevation
X Axis Title(PF)=Main Channel Distance
X Axis Title(XS)=Station
BEGIN DESCRIPTION:
UNT 038 IN LACR
END DESCRIPTION:
DSS Export Rating Curves= 0
DSS Export Rating Curve Sorted= 0
DSS Export Volume Flow Curves= 0
DXF OffsetX= 0
DXF OffsetY= 0
DXF ScaleX= 1
DXF ScaleY= 10

--- UNT 038 IN LACR.p01 (plan) ---

Plan Title=Multiple Run
Short Identifier=Multiple
Geom File=g01
Flow File=f01
Subcritical Flow
K Sum by GR= 0
Std Step Tol= 0.01
Critical Tol= 0.01
Num of Std Step Trials= 20
Max Error Tol= 0.3
Flow Tol Ratio= 0.001
Split Flow NTrial= 30
Split Flow Tol= 0.02
Split Flow Ratio= 0.02
Log Output Level= 0
Friction Slope Method= 1
Unsteady Friction Slope Method= 2
Unsteady Bridges Friction Slope Method= 1
Parabolic Critical Depth
Global Vel Dist=  1 , 1 , 1
Global Log Level= 0
CheckData=True
Encroach Param= -1, 0, 0, 0
BEGIN DESCRIPTION:
Multiple Run
END DESCRIPTION:

--- UNT 038 IN LACR.f01 (steady flow) ---

Flow Title=Multiple
Program Version=4.10
Number of Profiles= 7
Profile Names=10-year,25-year,50-year,1pct_min,100-year,1pct_plu,500-year
River Rch & RM=UNT 038 IN LACR,Reach-1         ,5146
     170     233     285     256     347     469     521
River Rch & RM=UNT 038 IN LACR,Reach-1         ,3646
     230     320     395     359     485     656     742
River Rch & RM=UNT 038 IN LACR,Reach-1         ,2987
     230     320     395     359     485     656     742
Boundary for River Rch & Prof#=UNT 038 IN LACR,Reach-1         , 1
Up Type= 0
Dn Type= 3
Dn Slope=0.005
Boundary for River Rch & Prof#=UNT 038 IN LACR,Reach-1         , 2
Up Type= 0
Dn Type= 3
Dn Slope=0.005
Boundary for River Rch & Prof#=UNT 038 IN LACR,Reach-1         , 3
Up Type= 0
Dn Type= 3
Dn Slope=0.005
Boundary for River Rch & Prof#=UNT 038 IN LACR,Reach-1         , 4
Up Type= 0
Dn Type= 3
Dn Slope=0.005
Boundary for River Rch & Prof#=UNT 038 IN LACR,Reach-1         , 5
Up Type= 0
Dn Type= 3
Dn Slope=0.005
Boundary for River Rch & Prof#=UNT 038 IN LACR,Reach-1         , 6
Up Type= 0
Dn Type= 3
Dn Slope=0.005
Boundary for River Rch & Prof#=UNT 038 IN LACR,Reach-1         , 7
Up Type= 0
Dn Type= 3
Dn Slope=0.005
DSS Import GetInterval= 0
DSS Import GetPeak= 0
DSS Import FillOption= 0

--- UNT 038 IN LACR.g01 (geometry) ---

Geom Title=Existing Conditions
Program Version=4.10

River Reach=UNT 038 IN LACR ,Reach-1
Reach XY= 30
      2197887.72     13179046.86      2198037.72     13179196.86
      2198137.72     13179196.86      2198137.72     13179246.85
      2198237.72     13179346.86      2198287.72     13179746.85
      2198387.72     13179846.86      2198437.72     13179846.86
      2198437.72     13179946.85      2198487.72     13179996.86
      2198887.72     13180046.85      2198937.72     13180146.85
      2199287.72     13180096.85      2199387.72     13180146.85
      2199487.72     13180296.85      2199637.72     13180346.86
      2199737.72     13180446.85      2199887.72     13180846.86
      2199937.72     13180896.85      2199937.72     13180996.86
      2199887.72     13181046.85      2199887.72     13181346.85
      2200037.72     13181546.85      2200037.72     13181596.85
      2200187.72     13181746.85      2200137.72     13181946.85
      2200337.72     13182146.86      2200337.72     13182246.85
      2200387.72     13182246.85      2200537.72     13182396.85

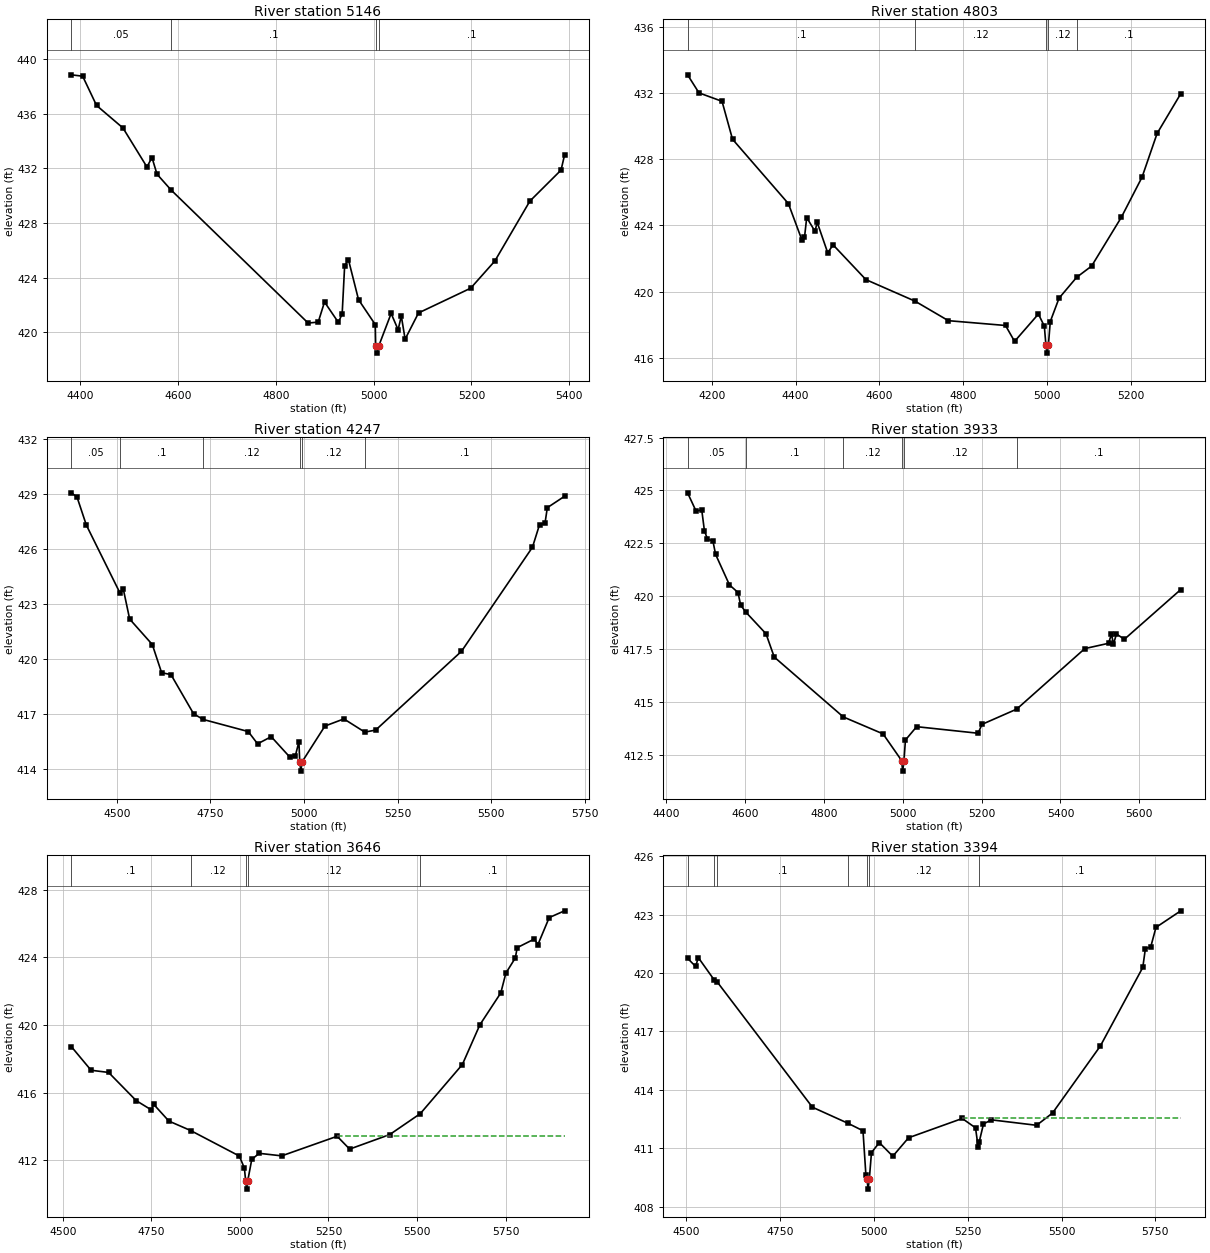
Type RM Length L Ch R = 1 ,5146    ,343,343,343
BEGIN DESCRIPTION:
UNT 038 IN LACR 11.0
END DESCRIPTION:
XS GIS Cut Line= 3
      2197337.69     13179246.86      2197937.72     13179096.85
      2198237.71     13178846.86
#Sta/Elev= 30
  4381.5  438.84  4404.7  438.74  4433.1   436.6  4487.2  434.95  4536.2   432.1
  4546.5  432.79  4556.8  431.57  4585.7  430.41    4866  420.68  4886.6  420.75
  4899.5  422.22  4927.8  420.73  4935.6  421.35  4940.7  424.88  4948.5  425.31
  4969.1  422.39  5003.3  420.57  5004.2  418.98  5006.9  418.48  5010.2  418.98
  5035.8  421.38  5050.1  420.19  5056.6   421.2  5064.4   419.5  5091.8  421.42
  5198.5  423.23    5248  425.22  5319.6   429.6  5383.4  431.87  5390.5  432.96
#Mann= 4 ,-1 , 0
  4381.5     .05       0  4585.7      .1       0  5004.2     .07       0
  5010.2      .1       0
Bank Sta=5004.2,5010.2
XS Rating Curve= 0 ,0
Exp/Cntr=0.3,0.1

Type RM Length L Ch R = 1 ,4803    ,556,556,556
BEGIN DESCRIPTION:
UNT 038 IN LACR 10.0
END DESCRIPTION:
XS GIS Cut Line= 3
      2197422.25     13179659.17      2198040.31       13179430.
      2198387.73     13179046.84
#Sta/Elev= 30
  4142.2   433.1  4169.4  432.01  4224.4   431.5  4249.4  429.21  4382.7  425.32
  4414.7  423.14  4421.1  423.28  4426.4  424.48  4446.1  423.65  4451.4  424.19
  4476.5  422.35  4489.3  422.83  4567.6  420.73  4684.7  419.43  4764.3  418.25
  4900.6  417.96  4922.2     417    4979  418.65  4993.2  417.92  4996.9  416.79
  4999.7  416.29  5002.9  416.79  5007.4   418.2  5028.3  419.61  5070.3  420.87
    5106  421.55    5177   424.5  5226.3  426.92  5262.2  429.56  5318.6  431.96
#Mann= 5 ,-1 , 0
  4142.2      .1       0  4684.7     .12       0  4996.9     .07       0
  5002.9     .12       0  5070.3      .1       0
Bank Sta=4996.9,5002.9
XS Rating Curve= 0 ,0
Exp/Cntr=0.3,0.1

Type RM Length L Ch R = 1 ,4247    ,314,314,314
BEGIN DESCRIPTION:
UNT 038 IN LACR 9.0
END DESCRIPTION:
XS GIS Cut Line= 3
       2197737.7     13179996.86      2198322.45     13179777.57
      2198517.73     13179112.78
#Sta/Elev= 30
  4378.6  429.06  4393.8  428.83  4418.7   427.3  4509.1  423.57  4517.5   423.8
  4534.4  422.17  4594.9  420.78  4619.8  419.24  4644.7  419.14  4705.2     417
  4730.9  416.69  4851.2  416.03  4876.1  415.36  4912.6  415.75  4961.6  414.65
  4976.7  414.68  4986.5  415.47  4988.8  414.37  4991.6  413.87  4994.8  414.37
    5056  416.33  5106.7  416.72  5162.5     416  5191.5  416.11  5420.8  420.41
  5610.4  426.09  5629.2  427.32  5643.8  427.39  5650.1  428.25    5696  428.87
#Mann= 6 ,-1 , 0
  4378.6     .05       0  4509.1      .1       0  4730.9     .12       0
  4988.8     .07       0  4994.8     .12       0  5162.5      .1       0
Bank Sta=4988.8,4994.8
XS Rating Curve= 0 ,0
Exp/Cntr=0.3,0.1

Type RM Length L Ch R = 1 ,3933    ,287,287,287
BEGIN DESCRIPTION:
Mapping XS ab2bd4ab
END DESCRIPTION:
XS GIS Cut Line= 3
      2198078.98     13180358.56      2198582.41      13179907.2
      2198625.82     13179334.29
#Sta/Elev= 30
  4454.4  424.89  4476.1  424.02  4490.3  424.09  4497.1   423.1  4504.6  422.72
  4518.8   422.6  4525.5  421.98  4560.6  420.54  4582.3  420.18    4589  419.58
  4602.8  419.24  4653.3  418.23  4674.2  417.13  4849.4   414.3  4950.1   413.5
  4997.2  412.24  4999.9  411.74  5003.2  412.24  5006.9  413.21  5035.3  413.84
  5191.1  413.53  5201.1  413.95  5289.1  414.67  5461.8  417.53    5522  417.78
  5529.4  418.22  5534.4  417.74  5542.1  418.22  5562.1  417.97  5705.1  420.32
#Mann= 6 ,-1 , 0
  4454.4     .05       0  4602.8      .1       0  4849.4     .12       0
  4997.2     .07       0  5003.2     .12       0  5289.1      .1       0
Bank Sta=4997.2,5003.2
XS Rating Curve= 0 ,0
Exp/Cntr=0.3,0.1

Type RM Length L Ch R = 1 ,3646    ,252,252,252
BEGIN DESCRIPTION:
UNT 038 IN LACR 8.0
END DESCRIPTION:
XS GIS Cut Line= 4
      2198443.55     13180410.64      2198890.57     13179881.16
      2199242.14     13179520.92      2199428.78     13179460.15
#Sta/Elev= 30
  4523.9  418.72  4579.6  417.32  4629.1  417.19  4707.1  415.52    4750  414.97
  4756.5   415.3  4799.4  414.31  4860.8  413.75  4998.3  412.24  5012.6  411.52
  5016.1  410.78  5018.9  410.28  5022.1  410.78  5033.4  412.04  5054.3   412.4
    5118  412.25  5274.5  413.41  5309.8  412.65  5422.9  413.51  5509.3  414.75
  5628.1  417.66  5677.5  420.01  5736.6   421.9  5750.9  423.07  5777.6  423.97
  5782.9  424.58  5831.2  425.09  5841.4  424.76  5873.3  426.36  5916.5  426.76
#Mann= 5 ,-1 , 0
  4523.9      .1       0  4860.8     .12       0  5016.1     .07       0
  5022.1     .12       0  5509.3      .1       0
#XS Ineff= 2 , 0
                         5274.33          413.41
Permanent Ineff=
       F       F
Bank Sta=5016.1,5022.1
XS Rating Curve= 0 ,0
Exp/Cntr=0.3,0.1

Type RM Length L Ch R = 1 ,3394    ,407,407,407
BEGIN DESCRIPTION:
UNT 038 IN LACR 7.0
END DESCRIPTION:
XS GIS Cut Line= 4
      2198594.29     13180503.74      2198891.95     13180203.57
      2199009.53     13180033.46      2199499.81     13179555.69
#Sta/Elev= 30
  4503.6  420.76  4525.1  420.34  4532.1   420.8  4574.9  419.64    4582  419.56
  4836.2  413.11  4930.2  412.29    4971   411.9  4978.7  409.64  4981.8   409.4
  4984.6   408.9  4987.8   409.4  4993.6  410.78  5014.6  411.29  5050.4  410.59
  5092.5  411.54  5235.5  412.53  5270.8  412.05    5278  411.05  5280.6  411.32
  5292.1  412.25  5313.2  412.46  5433.6  412.18    5476  412.81  5603.3  416.25
  5716.5  420.29  5723.5  421.26  5737.6  421.34  5751.7  422.35  5817.7   423.2
#Mann= 7 ,-1 , 0
  4503.6      .1       0  4574.9     .05       0    4582      .1       0
  4930.2     .12       0  4981.8     .07       0  4987.8     .12       0
  5280.6      .1       0
#XS Ineff= 2 , 0
                         5235.45          412.55
Permanent Ineff=
       F       F
Bank Sta=4981.8,4987.8
XS Rating Curve= 0 ,0
Exp/Cntr=0.3,0.1

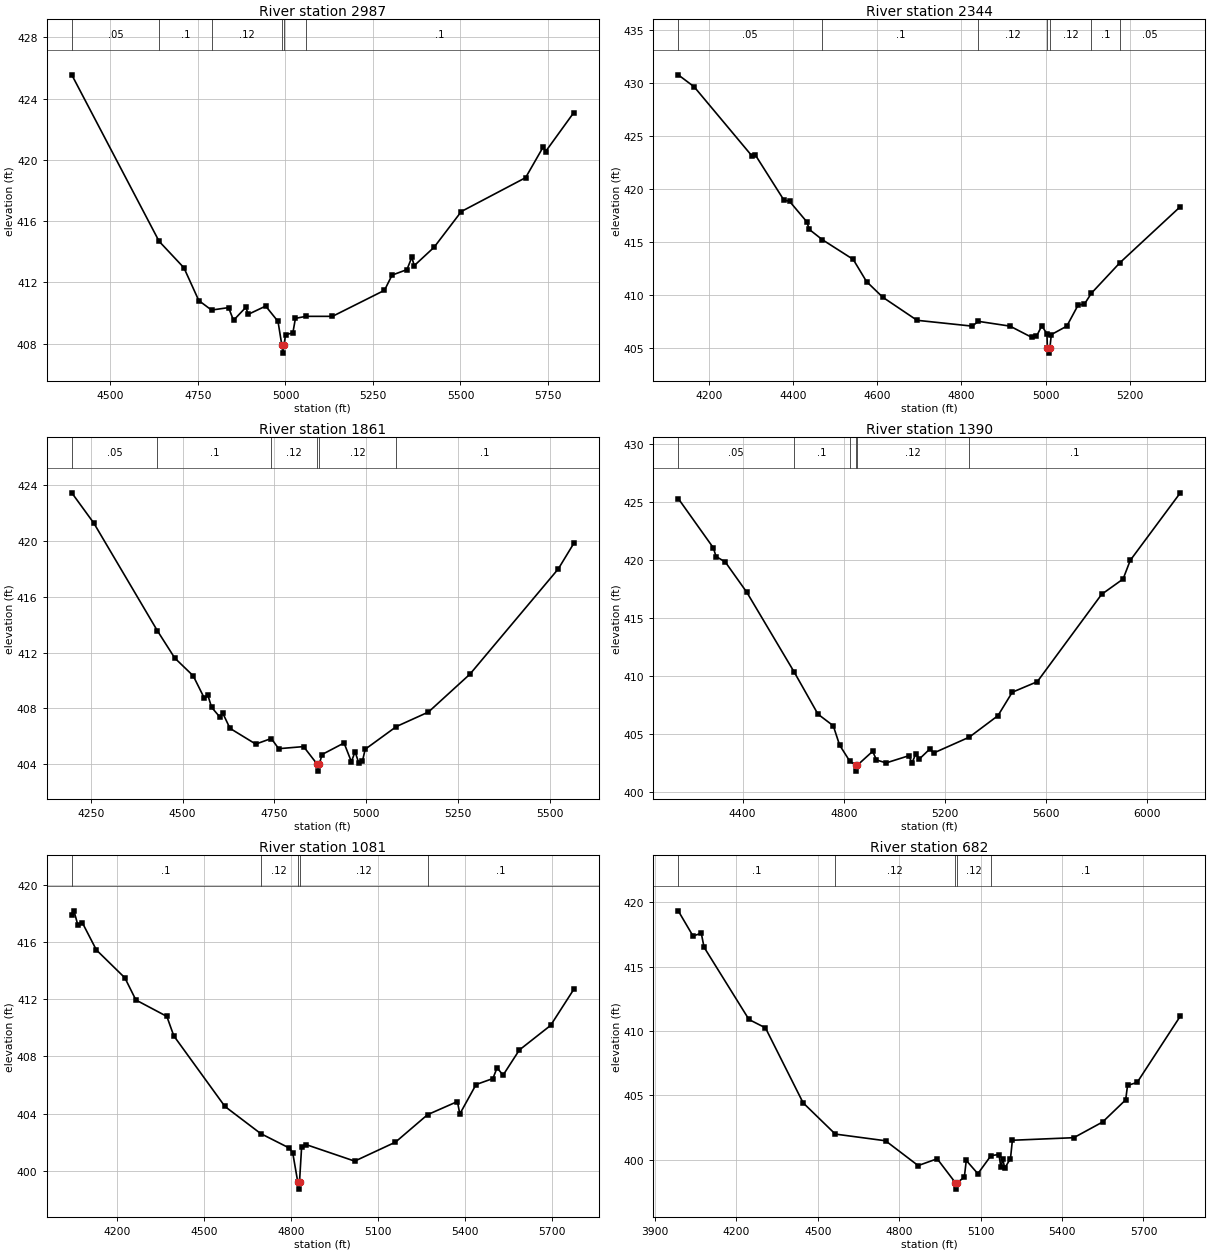
Type RM Length L Ch R = 1 ,2987    ,643,643,643
BEGIN DESCRIPTION:
UNT 038 IN LACR 6.0
END DESCRIPTION:
XS GIS Cut Line= 4
      2198894.44     13180566.32      2199397.28     13180023.46
      2199795.03     13179658.22      2199912.64     13179558.13
#Sta/Elev= 30
  4389.5  425.55  4638.9  414.69  4709.9  412.96  4752.4  410.82  4788.8   410.2
  4837.5  410.36  4851.6  409.53  4886.8  410.38  4893.6  409.92  4943.5  410.46
  4978.7  409.46  4989.8  407.89  4992.6  407.39  4995.8  407.89  5000.2  408.58
  5021.2  408.72  5028.5  409.66  5058.8  409.79  5134.3  409.79  5282.9  411.49
  5304.5  412.48  5347.1  412.84  5360.9  413.64    5368   413.1  5424.7   414.3
  5502.4  416.63  5686.1  418.84  5736.5  420.85  5743.1  420.54  5823.9  423.09
#Mann= 6 ,-1 , 0
  4389.5     .05       0  4638.9      .1       0  4788.8     .12       0
  4989.8     .07       0  4995.8     .12       0  5058.8      .1       0
Bank Sta=4989.8,4995.8
XS Rating Curve= 0 ,0
Exp/Cntr=0.3,0.1

Type RM Length L Ch R = 1 ,2344    ,483,483,483
BEGIN DESCRIPTION:
UNT 038 IN LACR 5.0
END DESCRIPTION:
XS GIS Cut Line= 3
      2198937.73     13180846.85      2199737.72     13180496.86
      2199987.75     13180296.83
#Sta/Elev= 30
  4126.8  430.78  4164.6  429.65  4301.4  423.15  4310.4  423.19  4377.8  418.96
  4391.5  418.83  4432.4   416.9  4438.3  416.18  4469.4  415.21  4542.7  413.35
  4574.3  411.26  4612.9  409.78  4694.4   407.6  4825.4  407.05  4840.3   407.5
  4915.4  407.05  4967.6  405.98  4978.2  406.08    4991  407.08  5003.2  406.32
  5004.2     405    5007   404.5  5010.2     405  5013.6  406.25  5050.4  407.05
  5077.6  409.06    5092  409.11  5108.9  410.16  5176.7  413.04  5320.2  418.33
#Mann= 7 ,-1 , 0
  4126.8     .05       0  4469.4      .1       0  4840.3     .12       0
  5004.2     .07       0  5010.2     .12       0  5108.9      .1       0
  5176.7     .05       0
Bank Sta=5004.2,5010.2
XS Rating Curve= 0 ,0
Exp/Cntr=0.3,0.1

Type RM Length L Ch R = 1 ,1861    ,471,471,471
BEGIN DESCRIPTION:
UNT 038 IN LACR 4.0
END DESCRIPTION:
XS GIS Cut Line= 3
      2199137.68     13180946.86      2199937.72     13180896.85
      2200337.73     13180496.84
#Sta/Elev= 30
  4198.4  423.47  4258.6  421.29  4431.6  413.57    4479  411.61  4529.1  410.34
  4559.1  408.75  4569.2  408.93  4579.2  408.08  4601.7  407.38  4609.2  407.68
  4629.3  406.57  4699.4  405.44  4741.7  405.84    4762  405.11  4829.7  405.26
  4866.7     404  4869.5   403.5  4872.7     404  4879.8  404.69  4939.9  405.52
  4959.9  404.17  4969.9   404.9    4980  404.08    4990  404.22  4997.5  405.07
  5082.5   406.7  5169.7  407.74  5282.8  410.46  5523.3  418.01  5565.7  419.85
#Mann= 6 ,-1 , 0
  4198.4     .05       0  4431.6      .1       0  4741.7     .12       0
  4866.7     .07       0  4872.7     .12       0  5082.5      .1       0
Bank Sta=4866.7,4872.7
XS Rating Curve= 0 ,0
Exp/Cntr=0.3,0.1

Type RM Length L Ch R = 1 ,1390    ,309,309,309
BEGIN DESCRIPTION:
UNT 038 IN LACR 3.0
END DESCRIPTION:
XS GIS Cut Line= 3
      2199087.72     13181046.86      2199887.72     13181346.85
      2200687.74     13180546.83
#Sta/Elev= 30
  4145.6  425.26  4284.4  421.01  4295.1  420.26  4331.6  419.79    4417  417.17
  4604.5  410.29  4698.3  406.67  4758.8  405.67  4783.7  404.01  4823.4  402.64
  4847.5  402.26  4850.2  401.76  4853.5  402.26  4914.6  403.47  4929.7  402.72
    4968  402.47  5056.6  403.08  5070.7  402.48  5084.9  403.25    5099   402.8
  5141.4  403.68  5155.6  403.32  5296.8  404.69  5410.1  406.54  5466.7  408.56
  5565.7  409.47  5820.2     417  5905.1  418.32  5933.4  419.93  6131.4  425.75
#Mann= 6 ,-1 , 0
  4145.6     .05       0  4604.5      .1       0  4823.4     .12       0
  4847.5     .07       0  4853.5     .12       0  5296.8      .1       0
Bank Sta=4847.5,4853.5
XS Rating Curve= 0 ,0
Exp/Cntr=0.3,0.1

Type RM Length L Ch R = 1 ,1081    ,399,399,399
BEGIN DESCRIPTION:
UNT 038 IN LACR 2.0
END DESCRIPTION:
XS GIS Cut Line= 4
      2199128.07     13181478.07      2199612.15     13181675.83
      2200164.16     13181569.56      2200677.75     13181174.04
#Sta/Elev= 30
  4043.7  417.87  4051.2  418.19  4064.9  417.18  4080.6  417.34  4128.7  415.45
    4227   413.5    4265  411.95  4371.9   410.8  4395.9  409.44  4572.3   404.5
  4695.8   402.6  4795.2  401.58  4806.5  401.25  4823.9  399.21  4826.6  398.71
  4829.9  399.21  4837.1  401.63  4852.2  401.83  5020.4  400.67  5161.3     402
  5271.9  403.92  5375.1  404.84  5383.3  403.97  5439.4  406.03  5497.5  406.45
  5511.9   407.2  5532.8  406.69  5588.9  408.45  5696.8  410.17    5777   412.7
#Mann= 5 ,-1 , 0
  4043.7      .1       0  4695.8     .12       0  4823.9     .07       0
  4829.9     .12       0  5271.9      .1       0
Bank Sta=4823.9,4829.9
XS Rating Curve= 0 ,0
Exp/Cntr=0.3,0.1

Type RM Length L Ch R = 1 ,682     ,431,431,431
BEGIN DESCRIPTION:
Mapping XS f22eedb1
END DESCRIPTION:
XS GIS Cut Line= 4
      2199133.95     13181779.15      2199857.16     13181900.17
      2200190.72     13181911.98      2200739.78     13181354.07
#Sta/Elev= 30
    3986  419.35  4040.5  417.39  4070.9  417.61  4081.1  416.52  4246.6   410.9
  4307.3  410.25  4446.1  404.42  4564.6  401.99  4749.8  401.47  4869.9  399.54
    4940  400.07    5007  398.21  5009.8  397.71    5013  398.21    5040  398.63
  5047.2  399.94  5089.9  398.91  5138.5  400.32  5167.7   400.4  5174.7   399.4
  5181.8  400.05  5188.9  399.34  5210.1  400.09  5217.1  401.51  5443.4  401.71
  5549.6  402.93  5634.4  404.65  5641.4  405.77  5676.9  406.01  5835.8  411.16
#Mann= 5 ,-1 , 0
    3986      .1       0  4564.6     .12       0    5007     .07       0
    5013     .12       0  5138.5      .1       0
Bank Sta=5007,5013
XS Rating Curve= 0 ,0
Exp/Cntr=0.3,0.1

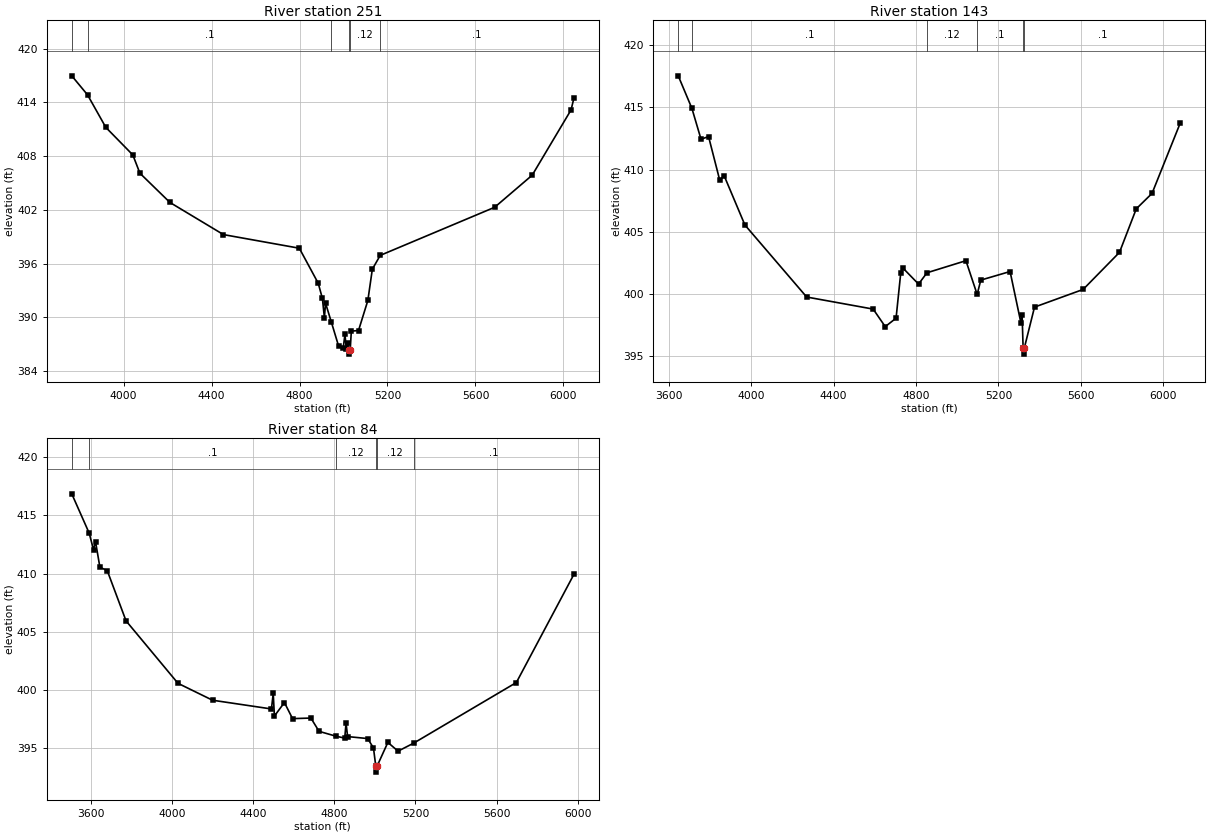
Type RM Length L Ch R = 1 ,251     ,108,108,108
BEGIN DESCRIPTION:
Mapping XS 473bc001
END DESCRIPTION:
XS GIS Cut Line= 6
       2199210.7     13181852.95      2200217.29     13182263.26
      2200296.99     13182286.87       2200388.5     13182216.03
      2200426.87     13182027.11      2200801.77     13181315.68
#Sta/Elev= 30
  3764.5  416.96  3836.1  414.84  3919.2  411.21  4042.1  408.13  4074.3  406.09
  4210.7  402.83  4454.1  399.24  4799.1  397.72  4885.1  393.81  4904.1  392.11
  4913.1  389.97  4918.4  391.58  4945.2  389.44  4977.7   386.8  4998.8  386.61
  5006.6   388.1    5013  386.43  5021.1  387.16  5024.5   386.4  5027.2   385.9
  5030.5   386.4  5035.6  388.47  5068.2  388.53  5110.7  391.89  5131.1  395.38
  5166.9  396.92  5687.3  402.29  5857.9  405.87  6034.7  413.16  6047.3  414.44
#Mann= 6 ,-1 , 0
  3764.5     .05       0  3836.1      .1       0  4945.2     .12       0
  5024.5     .07       0  5030.5     .12       0  5166.9      .1       0
Bank Sta=5024.5,5030.5
XS Rating Curve= 0 ,0
Exp/Cntr=0.3,0.1

Type RM Length L Ch R = 1 ,143     ,59,59,59
BEGIN DESCRIPTION:
Mapping XS 38d660bf
END DESCRIPTION:
XS GIS Cut Line= 6
      2199201.83     13181909.03      2200341.27     13182372.48
      2200488.86      13182254.4      2200497.72      13182168.8
       2200474.1     13182050.72      2200854.91     13181336.34
#Sta/Elev= 30
  3646.3  417.54  3712.7  414.92  3756.9  412.44  3793.4  412.66  3847.5  409.16
  3869.1  409.51  3969.8  405.55  4269.5  399.76  4592.2  398.79  4650.8  397.38
  4703.3  398.06  4726.1  401.71    4736   402.1  4812.4   400.8  4853.3  401.71
  5042.3  402.68  5096.8  399.97  5114.4  401.12  5256.6  401.81  5309.2  397.68
  5314.9  398.33  5319.8  395.67  5322.5  395.17  5325.8  395.67  5375.1  398.95
    5611  400.37  5787.4  403.35  5868.9  406.85  5945.4  408.09  6082.6  413.76
#Mann= 6 ,-1 , 0
  3646.3     .05       0  3712.7      .1       0  4853.3     .12       0
  5096.8      .1       0  5319.8     .07       0  5325.8      .1       0
Bank Sta=5319.8,5325.8
XS Rating Curve= 0 ,0
Exp/Cntr=0.3,0.1

Type RM Length L Ch R = 1 ,84      ,0,0,0
BEGIN DESCRIPTION:
UNT 038 IN LACR 1.0
END DESCRIPTION:
XS GIS Cut Line= 5
      2199166.46      13181979.9      2200043.13     13182490.55
      2200329.46     13182461.03      2200603.99     13182233.74
       2200952.3     13181492.84
#Sta/Elev= 30
  3504.1  416.84  3589.9  413.47  3611.4  412.05  3621.3  412.74  3642.9  410.54
  3679.2  410.25  3771.9  405.94  4028.3  400.58  4198.8  399.13  4489.3  398.38
  4498.2  399.71    4504  397.77  4553.4  398.93  4593.6  397.55  4684.1   397.6
  4724.3  396.46  4808.3  396.04    4851  395.88  4857.5  397.16  4865.3  396.01
  4964.3  395.84  4992.9  395.03  5004.3  393.46    5007  392.96  5010.3  393.46
  5063.9  395.51  5114.1  394.76  5190.5  395.44    5698  400.65  5981.6  409.92
#Mann= 6 ,-1 , 0
  3504.1     .05       0  3589.9      .1       0  4808.3     .12       0
  5004.3     .07       0  5010.3     .12       0  5190.5      .1       0
Bank Sta=5004.3,5010.3
XS Rating Curve= 0 ,0
Exp/Cntr=0.3,0.1

Chan Stop Cuts=-1
Use User Specified Reach Order=0
Composite Channel Slope=5