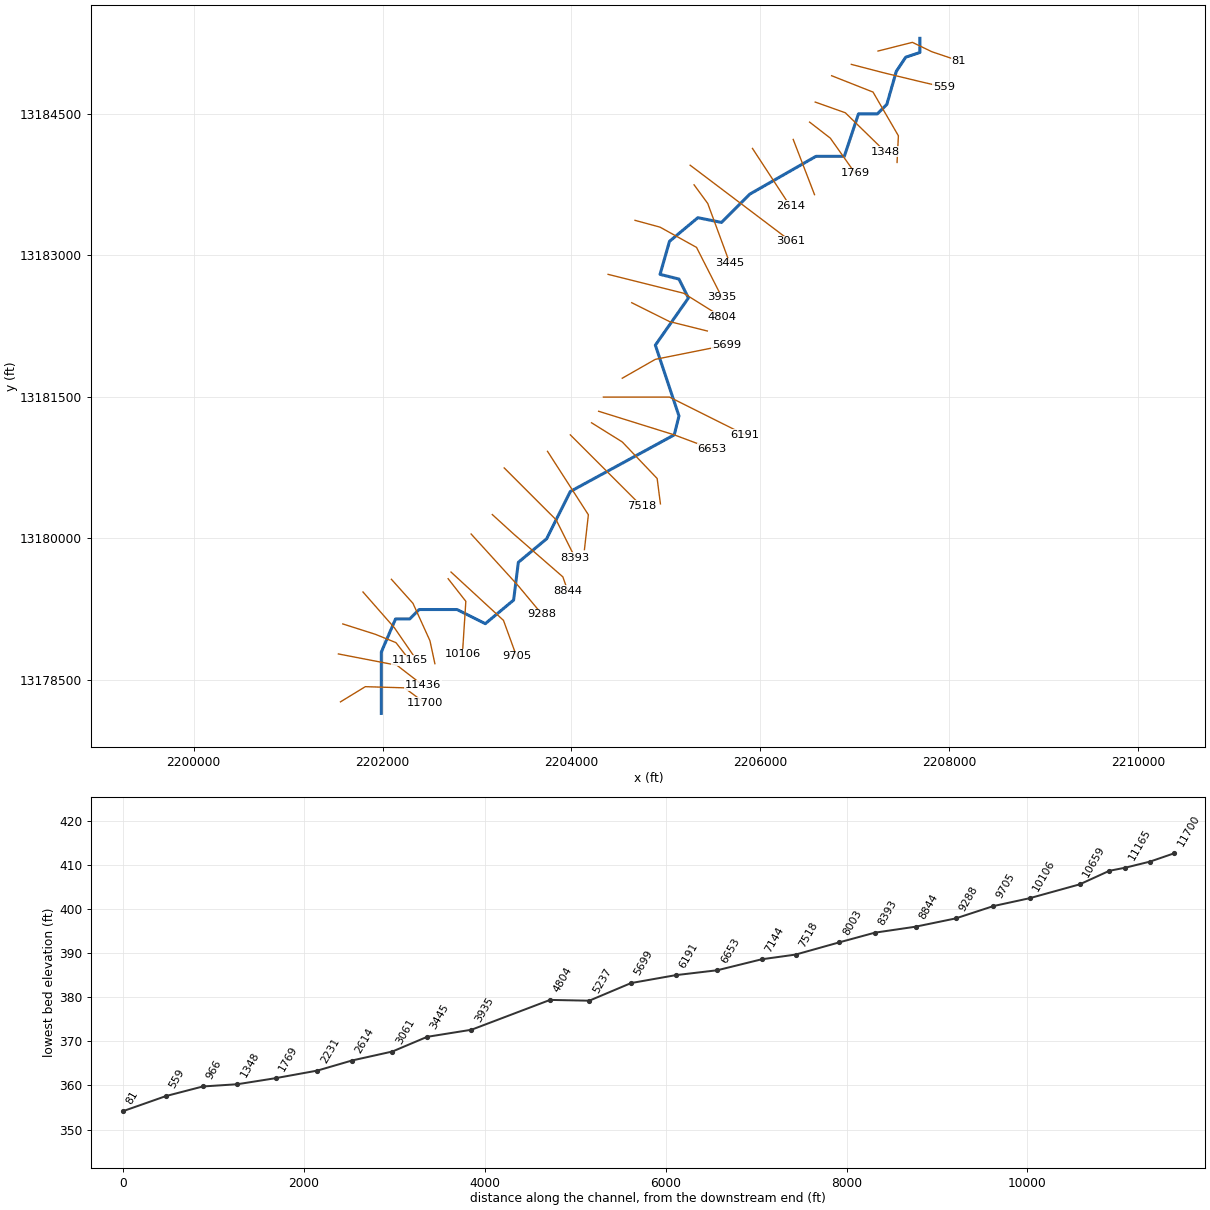
--- UNT 039 IN LACR.prj (project) ---

Proj Title=UNT 039 IN LACR Base Level Engineering
Current Plan=p01
Default Exp/Contr=0.3,0.1
English Units
Geom File=g01
Flow File=f01
Plan File=p01
BEGIN DESCRIPTION:
UNT 039 IN LACR
END DESCRIPTION:

--- UNT 039 IN LACR.p01 (plan) ---

Plan Title=Multiple Run
Short Identifier=Multiple
Geom File=g01
Flow File=f01
Subcritical Flow
K Sum by GR= 0
Std Step Tol= 0.01
Critical Tol= 0.01
Num of Std Step Trials= 20
Max Error Tol= 0.3
Flow Tol Ratio= 0.001
Split Flow NTrial= 30
Split Flow Tol= 0.02
Split Flow Ratio= 0.02
Log Output Level= 0
Friction Slope Method= 1
Unsteady Friction Slope Method= 2
Unsteady Bridges Friction Slope Method= 1
Parabolic Critical Depth
Global Vel Dist=  1 , 1 , 1
Global Log Level= 0
CheckData=True
Encroach Param= -1, 0, 0, 0
BEGIN DESCRIPTION:
Multiple Run
END DESCRIPTION:

--- UNT 039 IN LACR.f01 (steady flow) ---

Flow Title=Multiple
Number of Profiles=7
Profile Names=10-year,25-year,50-year,1pct_min,100-year,1pct_plu,500-year
River Rch & RM= UNT 039 IN LACR,Reach-1,11700
     190     260     318     286     386     522     579
River Rch & RM= UNT 039 IN LACR,Reach-1,8003
     269     375     463     421     569     769     871
Boundary for River Rch & Prof#=UNT 039 IN LACR,Reach-1,1
Up Type=0
Dn Type=3
Dn Slope=0.005
Boundary for River Rch & Prof#=UNT 039 IN LACR,Reach-1,2
Up Type=0
Dn Type=3
Dn Slope=0.005
Boundary for River Rch & Prof#=UNT 039 IN LACR,Reach-1,3
Up Type=0
Dn Type=3
Dn Slope=0.005
Boundary for River Rch & Prof#=UNT 039 IN LACR,Reach-1,4
Up Type=0
Dn Type=3
Dn Slope=0.005
Boundary for River Rch & Prof#=UNT 039 IN LACR,Reach-1,5
Up Type=0
Dn Type=3
Dn Slope=0.005
Boundary for River Rch & Prof#=UNT 039 IN LACR,Reach-1,6
Up Type=0
Dn Type=3
Dn Slope=0.005
Boundary for River Rch & Prof#=UNT 039 IN LACR,Reach-1,7
Up Type=0
Dn Type=3
Dn Slope=0.005

--- UNT 039 IN LACR.g01 (geometry) ---

Geom Title=Existing Conditions

River Reach=UNT 039 IN LACR,Reach-1
Reach XY= 30
      2201987.72     13178146.85      2201987.72     13178796.85
      2202137.72     13179146.85      2202287.72     13179146.85
      2202387.72     13179246.85      2202787.72     13179246.85
      2203087.72     13179096.85      2203387.72     13179346.86
      2203437.72     13179746.85      2203737.72     13179996.86
      2203987.72     13180496.86      2205087.72     13181096.85
      2205137.72     13181296.85      2204887.72     13182046.85
      2205237.72     13182546.85      2205137.72     13182746.85
      2204937.72     13182796.86      2205037.72     13183146.86
      2205337.72     13183396.85      2205587.72     13183346.85
      2205887.72     13183646.85      2206587.72     13184046.85
      2206887.72     13184046.85      2207037.72     13184496.85
      2207237.72     13184496.85      2207337.72     13184596.86
      2207437.72     13184946.86      2207537.72     13185096.86
      2207687.72     13185146.85      2207687.72     13185296.85

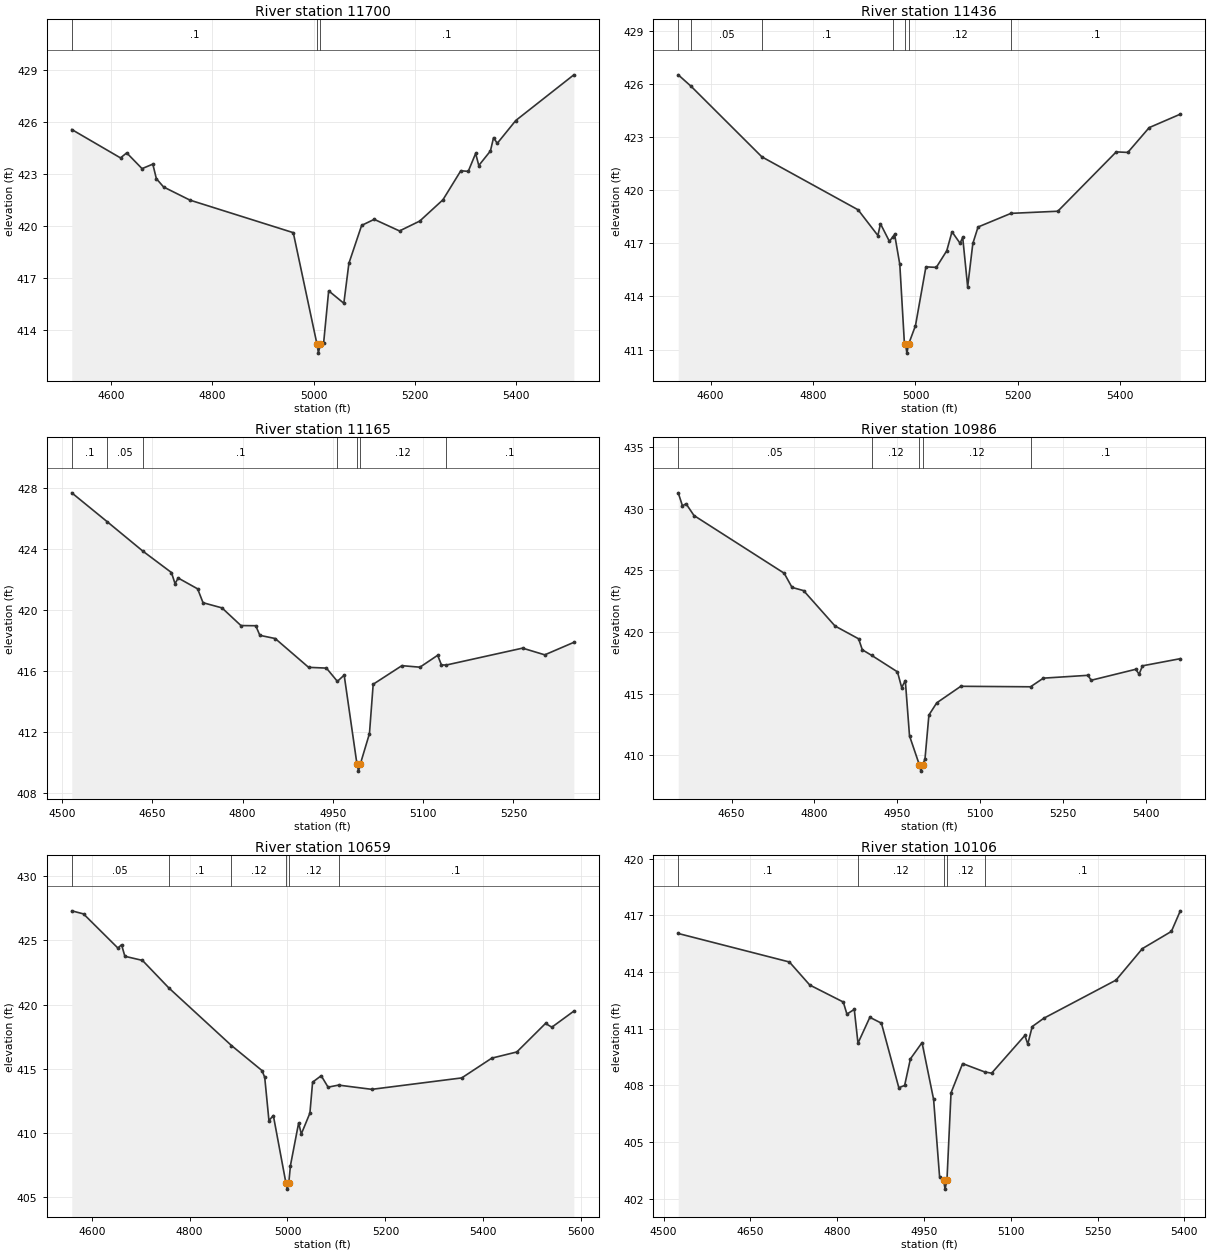
Type RM Length L Ch R = 1,11700,264,264,264
BEGIN DESCRIPTION:
UNT 039 IN LACR 24.0
END DESCRIPTION:
XS GIS Cut Line= 4
      2201554.98     13178268.81      2201818.14     13178429.70
      2202232.60     13178417.43      2202449.35     13178256.57
#Sta/Elev= 30
  4521.9  425.58  4618.3  423.94  4630.6  424.23  4660.9  423.32  4682.2  423.58
  4689.2  422.74  4703.5  422.26  4755.7  421.50  4960.0  419.62  5007.0  413.16
  5009.8  412.66  5013.0  413.16  5020.0  413.24  5030.0  416.26  5060.0  415.54
  5070.0  417.85  5095.2  420.04  5120.1  420.39  5170.1  419.72  5210.1  420.29
  5256.0  421.52  5291.4  423.20  5306.0  423.16  5320.7  424.20  5326.9  423.50
  5349.9  424.34  5356.1  425.11  5363.4  424.78  5400.0  426.10  5514.9  428.74
#Mann=3,-1,0
  4521.9     0.1       0  5007.0    0.07       0  5013.0     0.1       0
Bank Sta=5007,5013
Exp/Cntr=0.3,0.1

Type RM Length L Ch R = 1,11436,271,271,271
BEGIN DESCRIPTION:
Mapping XS a79dc9ba
END DESCRIPTION:
XS GIS Cut Line= 3
      2201532.94     13178776.40      2202152.78     13178656.60
      2202428.81     13178443.06
#Sta/Elev= 30
  4536.8  426.51  4562.0  425.86  4700.1  421.88  4888.0  418.89  4926.6  417.44
  4931.7  418.10  4949.1  417.11  4955.2  417.34  4959.3  417.50  4969.4  415.81
  4978.4  411.35  4980.5  411.30  4983.3  410.80  4986.5  411.30  5000.0  412.35
  5020.4  415.67  5040.7  415.64  5061.1  416.58  5071.3  417.65  5087.1  417.00
  5092.2  417.34  5101.9  414.54  5112.0  416.99  5122.2  417.92  5186.5  418.69
  5277.9  418.81  5392.0  422.16  5414.6  422.13  5456.3  423.53  5517.1  424.29
#Mann=7,-1,0
  4536.8     0.1       0  4562.0    0.05       0  4700.1     0.1       0
  4955.2    0.12       0  4980.5    0.07       0  4986.5    0.12       0
  5186.5     0.1       0
Bank Sta=4980.5,4986.5
Exp/Cntr=0.3,0.1

Type RM Length L Ch R = 1,11165,179,179,179
BEGIN DESCRIPTION:
UNT 039 IN LACR 23.0
END DESCRIPTION:
XS GIS Cut Line= 4
      2201579.89     13179094.09      2201923.61     13178984.73
      2202142.36     13178896.18      2202288.18     13178708.70
#Sta/Elev= 30
  4516.2  427.69  4574.9  425.80  4634.8  423.85  4681.8  422.46  4687.8  421.73
  4693.0  422.10  4725.3  421.39  4734.3  420.48  4765.8  420.14  4797.3  418.98
  4821.9  418.97  4828.7  418.34  4854.2  418.13  4909.7  416.24  4939.3  416.19
  4957.5  415.32  4968.8  415.73  4989.9  409.93  4992.6  409.43  4995.9  409.93
  5010.8  411.89  5017.0  415.13  5064.7  416.35  5094.7  416.25  5124.1  417.03
  5130.4  416.40  5138.3  416.39  5265.2  417.50  5302.1  417.06  5350.4  417.88
#Mann=7,-1,0
  4516.2     0.1       0  4574.9    0.05       0  4634.8     0.1       0
  4957.5    0.12       0  4989.9    0.07       0  4995.9    0.12       0
  5138.3     0.1       0
Bank Sta=4989.9,4995.9
Exp/Cntr=0.3,0.1

Type RM Length L Ch R = 1,10986,327,327,327
BEGIN DESCRIPTION:
Mapping XS 2e07e63a
END DESCRIPTION:
XS GIS Cut Line= 3
      2201793.41     13179432.63      2202126.73     13179052.43
      2202354.97     13178720.45
#Sta/Elev= 30
  4553.5  431.28  4561.1  430.23  4567.7  430.39  4582.0  429.44  4745.2  424.76
  4759.4  423.61  4780.3  423.35  4837.2  420.48  4879.9  419.44  4886.6  418.55
  4903.8  418.09  4950.2  416.76  4957.8  415.49  4964.4  416.05  4972.0  411.57
  4989.9  409.21  4992.6  408.71  4995.9  409.21  5000.0  409.70  5007.1  413.26
  5021.3  414.25  5064.8  415.59  5191.0  415.55  5214.2  416.25  5294.8  416.48
  5300.8  416.08  5381.4  416.97  5387.4  416.57  5393.5  417.25  5462.0  417.83
#Mann=5,-1,0
  4553.5    0.05       0  4903.8    0.12       0  4989.9    0.07       0
  4995.9    0.12       0  5191.0     0.1       0
Bank Sta=4989.9,4995.9
Exp/Cntr=0.3,0.1

Type RM Length L Ch R = 1,10659,553,553,553
BEGIN DESCRIPTION:
UNT 039 IN LACR 22.0
END DESCRIPTION:
XS GIS Cut Line= 4
      2202094.28     13179567.02      2202322.48     13179312.09
      2202502.28     13178915.96      2202554.36     13178672.95
#Sta/Elev= 30
  4559.3  427.31  4583.3  427.07  4653.6  424.41  4661.0  424.67  4667.8  423.77
  4703.7  423.45  4757.5  421.31  4885.6  416.82  4948.0  414.87  4953.5  414.34
  4962.1  410.98  4971.1  411.37  4996.7  406.14  4999.4  405.64  5002.7  406.14
  5006.0  407.47  5022.8  410.80  5028.2  409.93  5045.8  411.56  5051.3  413.97
  5068.9  414.47  5082.9  413.58  5104.3  413.74  5172.2  413.41  5356.0  414.30
  5417.4  415.84  5468.5  416.32  5527.1  418.54  5540.1  418.25  5585.0  419.50
#Mann=6,-1,0
  4559.3    0.05       0  4757.5     0.1       0  4885.6    0.12       0
  4996.7    0.07       0  5002.7    0.12       0  5104.3     0.1       0
Bank Sta=4996.7,5002.7
Exp/Cntr=0.3,0.1

Type RM Length L Ch R = 1,10106,401,401,401
BEGIN DESCRIPTION:
UNT 039 IN LACR 21.0
END DESCRIPTION:
XS GIS Cut Line= 3
      2202694.45     13179573.25      2202881.94     13179333.68
      2202845.50     13178771.48
#Sta/Elev= 30
  4525.4  416.04  4717.5  414.53  4752.7  413.31  4810.6  412.41  4816.9  411.77
  4829.6  412.02  4836.0  410.23  4856.5  411.60  4876.5  411.29  4906.6  407.87
  4916.6  407.99  4926.6  409.40  4946.7  410.26  4966.7  407.25  4977.0  403.16
  4983.8  403.00  4986.5  402.50  4989.8  403.00  4996.8  407.60  5016.8  409.15
  5054.7  408.71  5066.9  408.64  5124.4  410.64  5129.4  410.18  5137.1  411.11
  5157.1  411.55  5281.9  413.57  5327.5  415.24  5377.6  416.15  5393.0  417.24
#Mann=5,-1,0
  4525.4     0.1       0  4836.0    0.12       0  4983.8    0.07       0
  4989.8    0.12       0  5054.7     0.1       0
Bank Sta=4983.8,4989.8
Exp/Cntr=0.3,0.1

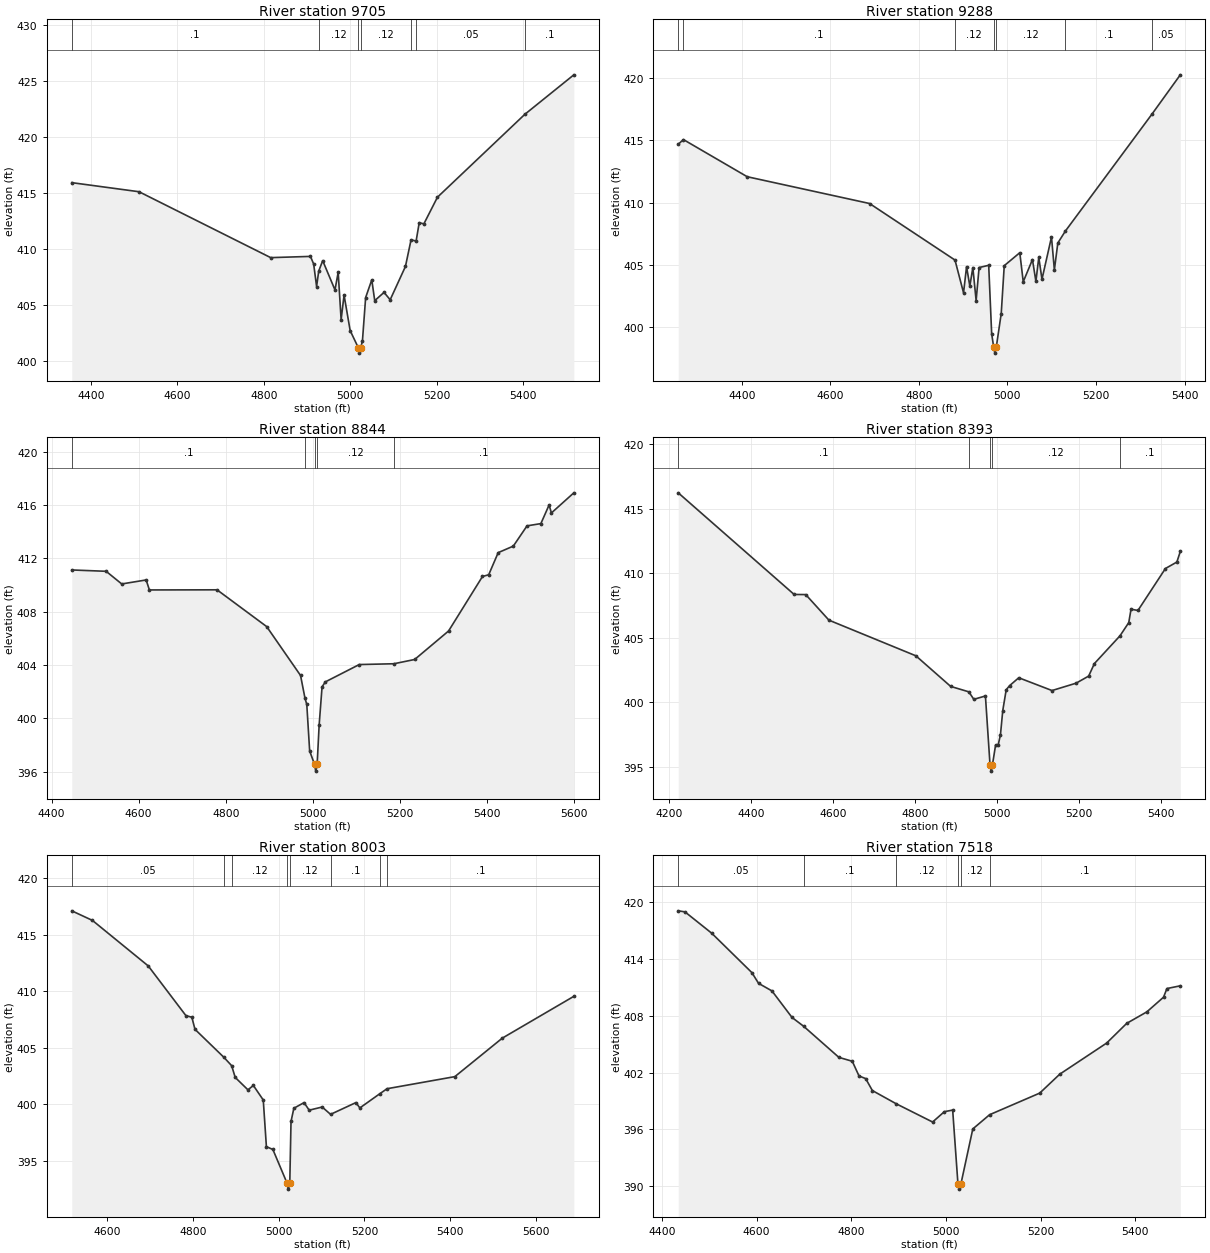
Type RM Length L Ch R = 1,9705,417,417,417
BEGIN DESCRIPTION:
UNT 039 IN LACR 20.0
END DESCRIPTION:
XS GIS Cut Line= 3
      2202724.81     13179643.95      2203280.33     13179131.83
      2203418.85     13178750.89
#Sta/Elev= 30
  4356.0  415.92  4511.5  415.11  4816.0  409.23  4907.9  409.34  4915.3  408.66
  4922.1  406.65  4927.0  408.03  4936.2  408.96  4964.6  406.35  4972.0  407.92
  4978.8  403.69  4985.6  405.89  4999.7  402.72  5018.3  401.21  5021.1  400.71
  5024.3  401.21  5028.1  401.81  5035.5  405.67  5049.7  407.25  5056.5  405.39
  5078.0  406.13  5092.2  405.47  5127.5  408.44  5140.5  410.82  5152.2  410.71
  5159.4  412.35  5170.1  412.24  5201.5  414.62  5403.7  422.02  5516.9  425.54
#Mann=7,-1,0
  4356.0     0.1       0  4927.0    0.12       0  5018.3    0.07       0
  5024.3    0.12       0  5140.5     0.1       0  5152.2    0.05       0
  5403.7     0.1       0
Bank Sta=5018.3,5024.3
Exp/Cntr=0.3,0.1

Type RM Length L Ch R = 1,9288,444,444,444
BEGIN DESCRIPTION:
UNT 039 IN LACR 19.0
END DESCRIPTION:
XS GIS Cut Line= 3
      2202937.72     13180046.85      2203437.72     13179496.85
      2203687.71     13179196.86
#Sta/Elev= 30
  4256.7  414.68  4268.5  415.05  4412.5  412.07  4688.8  409.92  4881.7  405.38
  4901.0  402.75  4907.8  404.85  4915.2  403.29  4922.0  404.78  4929.4  402.13
  4936.1  404.78  4957.8  404.96  4964.5  399.46  4969.0  398.41  4971.7  397.91
  4975.0  398.41  4986.1  401.09  4992.9  404.93  5028.0  405.97  5035.8  403.64
  5056.6  405.42  5064.4  403.67  5070.9  405.60  5078.1  403.84  5099.6  407.23
  5106.1  404.59  5113.9  406.75  5131.0  407.71  5326.8  417.11  5390.5  420.25
#Mann=7,-1,0
  4256.7    0.12       0  4268.5     0.1       0  4881.7    0.12       0
  4969.0    0.07       0  4975.0    0.12       0  5131.0     0.1       0
  5326.8    0.05       0
Bank Sta=4969,4975
Exp/Cntr=0.3,0.1

Type RM Length L Ch R = 1,8844,451,451,451
BEGIN DESCRIPTION:
UNT 039 IN LACR 18.0
END DESCRIPTION:
XS GIS Cut Line= 4
      2203162.00     13180252.77      2203387.72     13180046.85
      2203908.53     13179593.04      2203960.61     13179445.48
#Sta/Elev= 30
  4446.4  411.13  4525.3  411.03  4561.1  410.08  4617.2  410.38  4624.6  409.63
  4779.9  409.64  4893.9  406.88  4971.7  403.21  4981.9  401.50  4986.0  401.04
  4992.6  397.55  5003.8  396.53  5006.6  396.03  5009.8  396.53  5014.4  399.49
  5021.1  402.36  5028.7  402.73  5106.5  404.03  5186.0  404.09  5233.7  404.41
  5311.6  406.55  5389.4  410.64  5403.7  410.77  5425.5  412.43  5460.2  412.92
  5491.7  414.44  5523.5  414.61  5542.4  416.01  5547.7  415.41  5599.2  416.92
#Mann=5,-1,0
  4446.4     0.1       0  4981.9    0.12       0  5003.8    0.07       0
  5009.8    0.12       0  5186.0     0.1       0
Bank Sta=5003.8,5009.8
Exp/Cntr=0.3,0.1

Type RM Length L Ch R = 1,8393,390,390,390
BEGIN DESCRIPTION:
UNT 039 IN LACR 17.0
END DESCRIPTION:
XS GIS Cut Line= 3
      2203287.73     13180746.84      2203837.72     13180196.86
      2204037.71     13179796.87
#Sta/Elev= 30
  4222.2  416.22  4505.0  408.35  4533.3  408.34  4589.9  406.36  4802.0  403.60
  4886.9  401.23  4931.2  400.81  4943.4  400.23  4971.7  400.49  4982.9  395.17
  4985.6  394.67  4988.9  395.17  4996.5  396.69  5002.8  396.69  5008.4  397.49
  5014.0  399.36  5022.4  400.97  5030.7  401.29  5053.1  401.90  5134.2  400.91
  5192.9  401.48  5223.6  402.03  5237.6  403.00  5300.1  405.15  5321.4  406.17
  5327.0  407.21  5343.8  407.11  5410.9  410.36  5438.8  410.86  5447.2  411.68
#Mann=5,-1,0
  4222.2     0.1       0  4931.2    0.12       0  4982.9    0.07       0
  4988.9    0.12       0  5300.1     0.1       0
Bank Sta=4982.9,4988.9
Exp/Cntr=0.3,0.1

Type RM Length L Ch R = 1,8003,485,485,485
BEGIN DESCRIPTION:
UNT 039 IN LACR 16.0
END DESCRIPTION:
XS GIS Cut Line= 3
      2203746.53     13180922.22      2204178.82     13180250.35
      2204137.22     13179881.22
#Sta/Elev= 30
  4517.7  417.13  4565.9  416.28  4696.0  412.25  4783.8  407.85  4797.6  407.71
  4804.9  406.64  4872.3  404.16  4890.4  403.42  4898.7  402.38  4928.4  401.28
  4941.0  401.67  4964.1  400.38  4971.4  396.25  4986.5  396.00  5019.9  392.99
  5022.6  392.49  5025.9  392.99  5028.8  398.48  5035.4  399.65  5059.2  400.15
  5071.1  399.48  5101.4  399.76  5121.0  399.11  5180.0  400.15  5189.3  399.68
  5236.3  400.95  5252.7  401.38  5410.7  402.45  5521.4  405.86  5688.1  409.56
#Mann=8,-1,0
  4517.7    0.05       0  4872.3     0.1       0  4890.4    0.12       0
  5019.9    0.07       0  5025.9    0.12       0  5121.0     0.1       0
  5236.3    0.12       0  5252.7     0.1       0
Bank Sta=5019.9,5025.9
Exp/Cntr=0.3,0.1

Type RM Length L Ch R = 1,7518,374,374,374
BEGIN DESCRIPTION:
UNT 039 IN LACR 15.0
END DESCRIPTION:
XS GIS Cut Line= 3
      2203987.71     13181096.87      2204387.72     13180696.85
      2204737.74     13180346.84
#Sta/Elev= 30
  4434.3  419.06  4448.5  418.95  4505.0  416.70  4589.9  412.54  4604.0  411.41
  4632.3  410.61  4674.7  407.81  4699.0  406.89  4773.7  403.60  4802.0  403.19
  4816.2  401.64  4830.3  401.36  4844.4  400.10  4894.6  398.71  4971.7  396.78
  4996.5  397.87  5014.1  398.04  5025.3  390.20  5028.0  389.70  5031.3  390.20
  5056.6  396.05  5092.1  397.55  5198.0  399.83  5240.4  401.83  5339.4  405.11
  5381.8  407.19  5424.3  408.40  5459.6  409.95  5466.7  410.86  5495.0  411.15
#Mann=6,-1,0
  4434.3    0.05       0  4699.0     0.1       0  4894.6    0.12       0
  5025.3    0.07       0  5031.3    0.12       0  5092.1     0.1       0
Bank Sta=5025.3,5031.3
Exp/Cntr=0.3,0.1

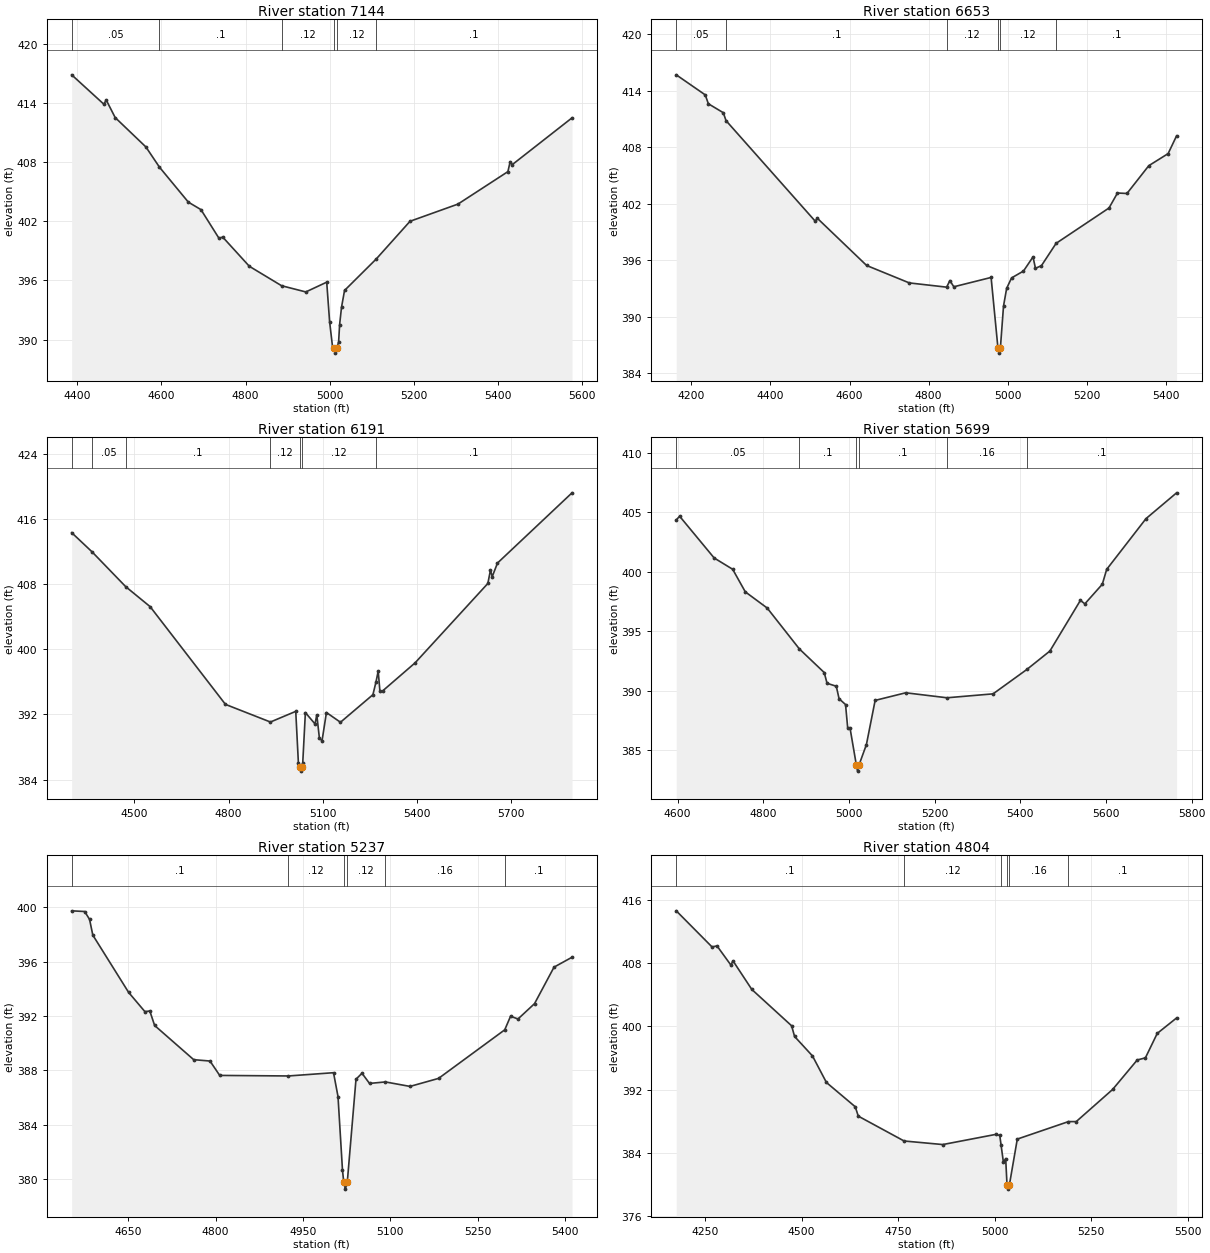
Type RM Length L Ch R = 1,7144,491,491,491
BEGIN DESCRIPTION:
UNT 039 IN LACR 14.0
END DESCRIPTION:
XS GIS Cut Line= 4
      2204212.39     13181224.96      2204537.72     13181021.85
      2204906.80     13180634.71      2204941.51     13180365.65
#Sta/Elev= 30
  4386.6  416.84  4462.9  413.87  4468.8  414.28  4490.0  412.51  4563.1  409.53
  4595.2  407.49  4664.0  403.94  4694.0  403.18  4736.5  400.30  4745.9  400.39
  4809.0  397.44  4885.7  395.47  4943.3  394.84  4993.0  395.83  4999.9  391.82
  5007.1  389.18  5011.0  389.14  5013.8  388.64  5017.0  389.14  5021.3  389.77
  5023.7  391.53  5028.2  393.29  5035.4  394.99  5111.0  398.19  5191.1  402.00
  5305.0  403.74  5423.8  407.03  5429.2  408.04  5434.2  407.74  5576.3  412.48
#Mann=6,-1,0
  4386.6    0.05       0  4595.2     0.1       0  4885.7    0.12       0
  5011.0    0.07       0  5017.0    0.12       0  5111.0     0.1       0
Bank Sta=5011,5017
Exp/Cntr=0.3,0.1

Type RM Length L Ch R = 1,6653,462,462,462
BEGIN DESCRIPTION:
UNT 039 IN LACR 13.0
END DESCRIPTION:
XS GIS Cut Line= 3
      2204287.68     13181346.87      2205087.72     13181096.85
      2205487.72     13180946.85
#Sta/Elev= 30
  4161.8  415.68  4235.2  413.55  4243.0  412.61  4280.8  411.66  4287.7  410.82
  4513.3  400.15  4518.6  400.46  4643.3  395.45  4751.2  393.60  4845.7  393.15
  4853.8  393.85  4863.8  393.19  4958.1  394.18  4975.5  386.65  4978.3  386.15
  4981.5  386.65  4989.5  391.15  4997.4  393.02  5009.8  394.13  5040.0  394.86
  5064.1  396.36  5070.3  395.15  5085.4  395.43  5122.5  397.80  5256.3  401.55
  5277.7  403.14  5301.7  403.09  5356.9  406.04  5405.8  407.32  5427.2  409.21
#Mann=6,-1,0
  4161.8    0.05       0  4287.7     0.1       0  4845.7    0.12       0
  4975.5    0.07       0  4981.5    0.12       0  5122.5     0.1       0
Bank Sta=4975.5,4981.5
Exp/Cntr=0.3,0.1

Type RM Length L Ch R = 1,6191,492,492,492
BEGIN DESCRIPTION:
UNT 039 IN LACR 12.0
END DESCRIPTION:
XS GIS Cut Line= 3
      2204337.72     13181496.85      2205037.72     13181496.86
      2205837.70     13181096.87
#Sta/Elev= 30
  4300.0  414.36  4365.2  411.99  4472.4  407.71  4550.0  405.26  4790.0  393.24
  4933.3  391.07  5014.0  392.38  5022.4  386.07  5027.7  385.53  5030.5  385.03
  5033.7  385.53  5036.3  386.05  5044.7  392.23  5075.5  390.83  5081.1  391.96
  5089.4  389.07  5097.8  388.77  5111.8  392.24  5156.5  391.04  5259.9  394.43
  5269.7  395.99  5276.7  397.33  5282.3  394.84  5290.7  394.89  5394.1  398.34
  5626.1  408.11  5634.5  409.75  5640.1  408.95  5656.8  410.62  5894.4  419.26
#Mann=7,-1,0
  4300.0     0.1       0  4365.2    0.05       0  4472.4     0.1       0
  4933.3    0.12       0  5027.7    0.07       0  5033.7    0.12       0
  5269.7     0.1       0
Bank Sta=5027.7,5033.7
Exp/Cntr=0.3,0.1

Type RM Length L Ch R = 1,5699,462,462,462
BEGIN DESCRIPTION:
UNT 039 IN LACR 11.0
END DESCRIPTION:
XS GIS Cut Line= 3
      2204537.73     13181696.86      2204887.72     13181896.85
      2205637.77     13182046.86
#Sta/Elev= 30
  4596.9  404.37  4604.8  404.68  4685.4  401.17  4728.6  400.22  4758.1  398.32
  4809.2  396.96  4884.3  393.52  4942.4  391.53  4948.9  390.63  4970.5  390.38
  4977.0  389.33  4992.1  388.84  4997.1  386.88  5002.5  386.88  5017.4  383.74
  5020.1  383.24  5023.4  383.74  5040.8  385.47  5061.2  389.19  5132.6  389.83
  5228.9  389.41  5336.5  389.74  5415.3  391.79  5469.1  393.34  5540.5  397.61
  5550.7  397.31  5591.5  398.96  5601.7  400.21  5693.5  404.48  5764.9  406.65
#Mann=6,-1,0
  4596.9    0.05       0  4884.3     0.1       0  5017.4    0.07       0
  5023.4     0.1       0  5228.9    0.16       0  5415.3     0.1       0
Bank Sta=5017.4,5023.4
Exp/Cntr=0.3,0.1

Type RM Length L Ch R = 1,5237,433,433,433
BEGIN DESCRIPTION:
UNT 039 IN LACR 10.0
END DESCRIPTION:
XS GIS Cut Line= 3
      2204637.73     13182496.85      2205037.72     13182296.86
      2205437.71     13182196.86
#Sta/Elev= 30
  4552.8  399.75  4575.1  399.70  4583.5  399.12  4589.1  397.96  4650.6  393.74
  4678.6  392.32  4687.0  392.37  4695.3  391.30  4762.4  388.78  4790.4  388.68
  4807.1  387.62  4925.0  387.58  5002.6  387.82  5010.3  386.06  5018.0  380.63
  5020.2  379.74  5022.9  379.24  5026.2  379.74  5041.2  387.34  5051.5  387.78
  5064.4  387.03  5091.7  387.14  5134.0  386.81  5183.0  387.40  5296.7  390.98
  5306.7  391.98  5319.5  391.78  5347.9  392.91  5381.4  395.60  5412.3  396.33
#Mann=6,-1,0
  4552.8     0.1       0  4925.0    0.12       0  5020.2    0.07       0
  5026.2    0.12       0  5091.7    0.16       0  5296.7     0.1       0
Bank Sta=5020.2,5026.2
Exp/Cntr=0.3,0.1

Type RM Length L Ch R = 1,4804,869,869,869
BEGIN DESCRIPTION:
UNT 039 IN LACR 9.0
END DESCRIPTION:
XS GIS Cut Line= 3
      2204387.74     13182796.85      2205187.72     13182596.85
      2205587.72     13182346.85
#Sta/Elev= 30
  4175.4  414.57  4268.1  410.01  4281.0  410.14  4317.1  407.71  4322.3  408.26
  4371.2  404.64  4474.3  400.05  4482.0  398.70  4528.4  396.24  4564.5  392.89
  4639.2  389.82  4647.0  388.64  4765.7  385.50  4866.0  385.05  5002.9  386.33
  5013.6  386.20  5016.9  385.01  5023.0  382.82  5028.9  383.28  5032.4  379.92
  5035.1  379.42  5038.4  379.92  5059.0  385.74  5191.6  387.95  5211.7  387.95
  5306.0  392.01  5369.7  395.73  5390.9  396.00  5421.6  399.09  5471.7  401.04
#Mann=6,-1,0
  4175.4     0.1       0  4765.7    0.12       0  5016.9    0.16       0
  5032.4    0.07       0  5038.4    0.16       0  5191.6     0.1       0
Bank Sta=5032.4,5038.4
Exp/Cntr=0.3,0.1

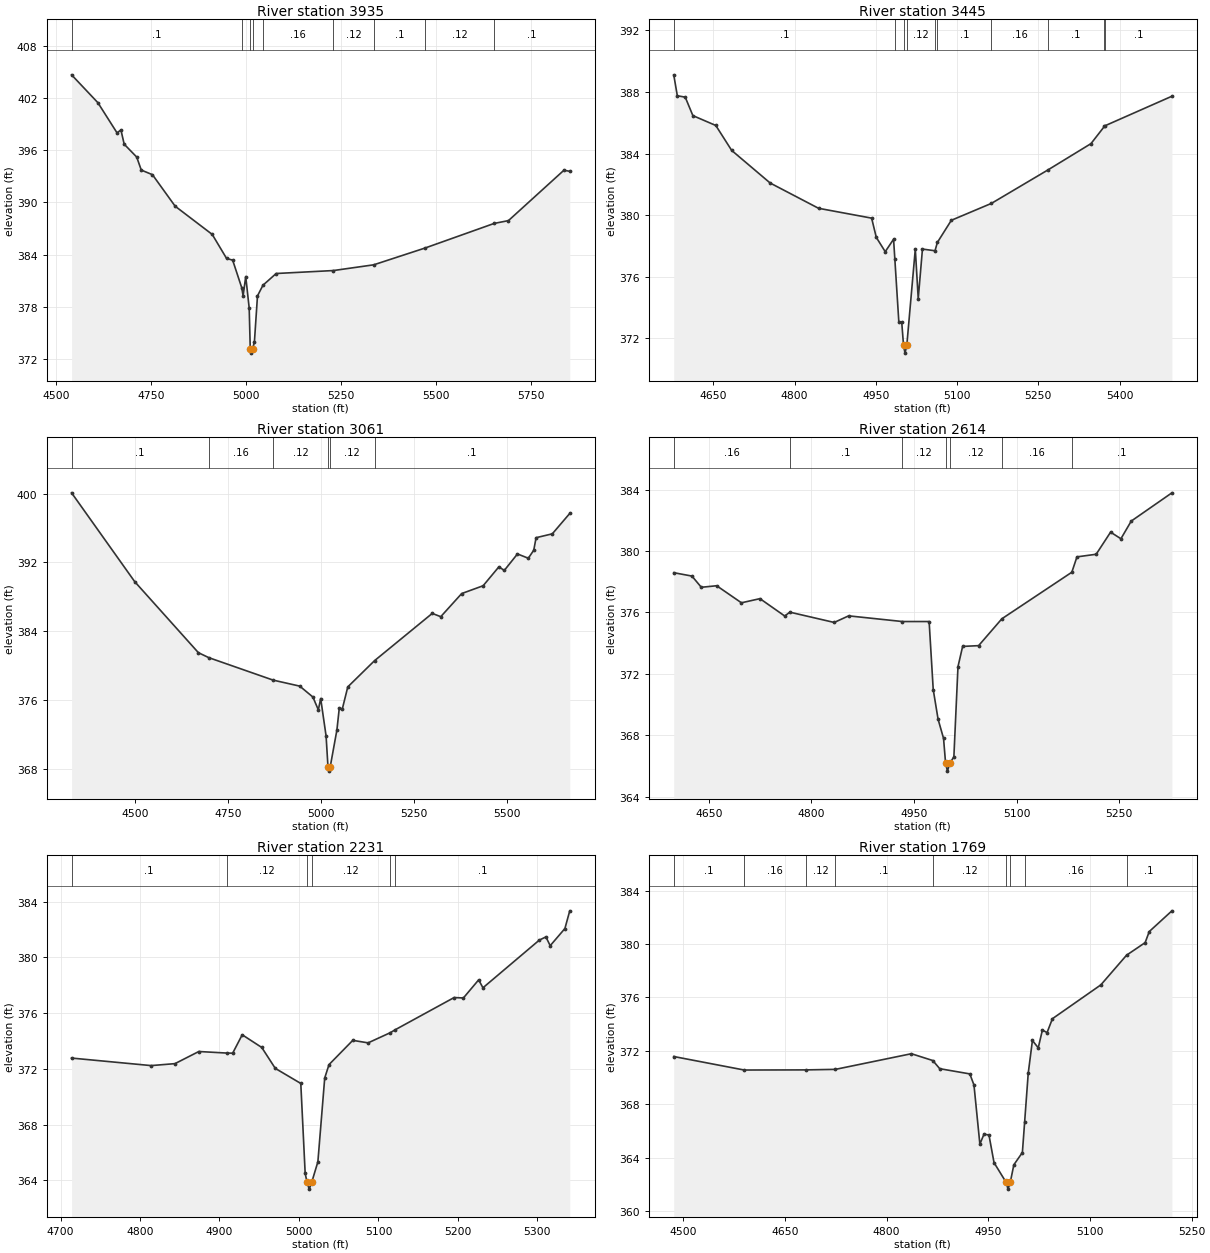
Type RM Length L Ch R = 1,3935,490,490,490
BEGIN DESCRIPTION:
UNT 039 IN LACR 8.0
END DESCRIPTION:
XS GIS Cut Line= 4
      2204672.44     13183369.08      2204937.72     13183296.85
      2205323.46     13183082.63      2205592.54     13182553.16
#Sta/Elev= 30
  4541.2  404.70  4610.4  401.49  4660.7  398.02  4671.0  398.35  4679.6  396.71
  4712.5  395.23  4724.5  393.73  4753.9  393.20  4813.6  389.57  4911.1  386.32
  4948.9  383.55  4964.8  383.36  4988.7  380.18  4992.3  379.26  4999.2  381.47
  5008.3  377.84  5011.1  373.15  5013.8  372.65  5017.1  373.15  5022.0  373.92
  5030.1  379.24  5044.5  380.47  5079.3  381.82  5229.8  382.16  5335.8  382.82
  5471.2  384.76  5652.8  387.59  5690.1  387.91  5835.9  393.71  5851.3  393.59
#Mann=9,-1,0
  4541.2     0.1       0  4988.7    0.12       0  5011.1    0.07       0
  5017.1    0.12       0  5044.5    0.16       0  5229.8    0.12       0
  5335.8     0.1       0  5471.2    0.12       0  5652.8     0.1       0
Bank Sta=5011.1,5017.1
Exp/Cntr=0.3,0.1

Type RM Length L Ch R = 1,3445,384,384,384
BEGIN DESCRIPTION:
UNT 039 IN LACR 7.0
END DESCRIPTION:
XS GIS Cut Line= 3
      2205297.48     13183745.32      2205442.35     13183547.46
      2205675.58     13182914.92
#Sta/Elev= 30
  4577.1  389.12  4583.7  387.76  4598.3  387.67  4612.4  386.47  4654.7  385.83
  4684.0  384.21  4755.1  382.09  4844.3  380.45  4942.3  379.81  4950.9  378.56
  4967.4  377.63  4982.8  378.44  4985.1  377.17  4992.5  373.07  4997.8  373.07
  5001.2  371.54  5003.9  371.04  5007.2  371.54  5022.9  377.80  5028.3  374.58
  5036.1  377.80  5059.3  377.69  5063.6  378.23  5089.4  379.67  5163.5  380.77
  5267.6  382.94  5347.1  384.65  5371.9  385.77  5372.3  385.80  5496.5  387.73
#Mann=10,-1,0
  4577.1     0.1       0  4985.1    0.12       0  5001.2    0.07       0
  5007.2    0.12       0  5059.3    0.16       0  5063.6     0.1       0
  5163.5    0.16       0  5267.6     0.1       0  5371.9    0.12       0
  5372.3     0.1       0
Bank Sta=5001.2,5007.2
Exp/Cntr=0.3,0.1

Type RM Length L Ch R = 1,3061,447,447,447
BEGIN DESCRIPTION:
UNT 039 IN LACR 6.0
END DESCRIPTION:
XS GIS Cut Line= 2
      2205256.04     13183952.99      2206323.23     13183146.09
#Sta/Elev= 30
  4330.5  400.09  4500.0  389.76  4671.1  381.49  4699.2  380.91  4871.7  378.30
  4943.3  377.60  4978.6  376.33  4993.2  374.84  4999.5  376.16  5014.0  371.81
  5019.1  368.21  5021.9  367.71  5025.1  368.21  5043.1  372.50  5049.4  375.02
  5057.7  374.96  5072.3  377.51  5144.1  380.56  5299.1  386.06  5322.0  385.68
  5378.2  388.37  5435.8  389.28  5478.1  391.48  5492.6  391.06  5528.0  392.98
  5557.1  392.48  5571.7  393.41  5578.0  394.87  5621.6  395.32  5668.4  397.69
#Mann=6,-1,0
  4330.5     0.1       0  4699.2    0.16       0  4871.7    0.12       0
  5019.1    0.07       0  5025.1    0.12       0  5144.1     0.1       0
Bank Sta=5019.1,5025.1
Exp/Cntr=0.3,0.1

Type RM Length L Ch R = 1,2614,383,383,383
BEGIN DESCRIPTION:
UNT 039 IN LACR 5.0
END DESCRIPTION:
XS GIS Cut Line= 2
      2205915.85     13184130.55      2206314.29     13183520.55
#Sta/Elev= 30
  4598.6  378.59  4625.2  378.37  4638.9  377.64  4661.4  377.74  4697.6  376.63
  4724.7  376.90  4760.9  375.77  4768.4  376.02  4833.3  375.35  4854.4  375.78
  4933.0  375.41  4972.1  375.41  4978.1  370.98  4985.2  369.05  4993.2  367.80
  4996.2  366.17  4998.9  365.67  5002.2  366.17  5008.3  366.60  5014.3  372.47
  5021.1  373.79  5044.5  373.84  5078.5  375.59  5180.8  378.62  5188.3  379.62
  5216.4  379.79  5237.5  381.23  5252.6  380.80  5267.7  381.95  5327.2  383.79
#Mann=7,-1,0
  4598.6    0.16       0  4768.4     0.1       0  4933.0    0.12       0
  4996.2    0.07       0  5002.2    0.12       0  5078.5    0.16       0
  5180.8     0.1       0
Bank Sta=4996.2,5002.2
Exp/Cntr=0.3,0.1

Type RM Length L Ch R = 1,2231,462,462,462
BEGIN DESCRIPTION:
UNT 039 IN LACR 4.0
END DESCRIPTION:
XS GIS Cut Line= 2
      2206346.97     13184225.97      2206572.45     13183641.13
#Sta/Elev= 30
  4713.9  372.78  4814.0  372.24  4844.0  372.38  4874.0  373.25  4908.9  373.14
  4916.6  373.13  4928.6  374.45  4953.2  373.54  4970.2  372.04  5002.3  370.96
  5007.8  364.52  5010.1  363.88  5012.9  363.38  5016.1  363.88  5023.8  365.34
  5032.4  371.35  5037.8  372.31  5067.7  374.05  5087.0  373.87  5114.9  374.60
  5121.4  374.82  5195.2  377.12  5206.9  377.09  5226.1  378.39  5231.5  377.82
  5302.4  381.24  5310.7  381.47  5316.1  380.84  5334.6  382.07  5340.7  383.34
#Mann=6,-1,0
  4713.9     0.1       0  4908.9    0.12       0  5010.1    0.07       0
  5016.1    0.12       0  5114.9    0.16       0  5121.4     0.1       0
Bank Sta=5010.1,5016.1
Exp/Cntr=0.3,0.1

Type RM Length L Ch R = 1,1769,421,421,421
BEGIN DESCRIPTION:
UNT 039 IN LACR 3.0
END DESCRIPTION:
XS GIS Cut Line= 3
      2206520.10     13184409.71      2206739.23     13184240.06
      2207003.46     13183866.61
#Sta/Elev= 30
  4486.2  371.58  4590.1  370.57  4681.3  370.58  4724.7  370.62  4836.6  371.79
  4868.2  371.28  4878.4  370.67  4922.8  370.28  4928.9  369.45  4937.6  365.03
  4943.7  365.77  4951.0  365.71  4958.5  363.64  4976.4  362.16  4979.1  361.66
  4982.4  362.16  4987.7  363.48  5000.3  364.40  5003.6  366.67  5008.9  370.32
  5015.1  372.78  5023.7  372.23  5029.8  373.56  5036.7  373.37  5044.6  374.41
  5116.0  376.94  5153.9  379.16  5181.3  380.10  5187.4  380.93  5220.8  382.48
#Mann=9,-1,0
  4486.2     0.1       0  4590.1    0.16       0  4681.3    0.12       0
  4724.7     0.1       0  4868.2    0.12       0  4976.4    0.07       0
  4982.4    0.12       0  5003.6    0.16       0  5153.9     0.1       0
Bank Sta=4976.4,4982.4
Exp/Cntr=0.3,0.1

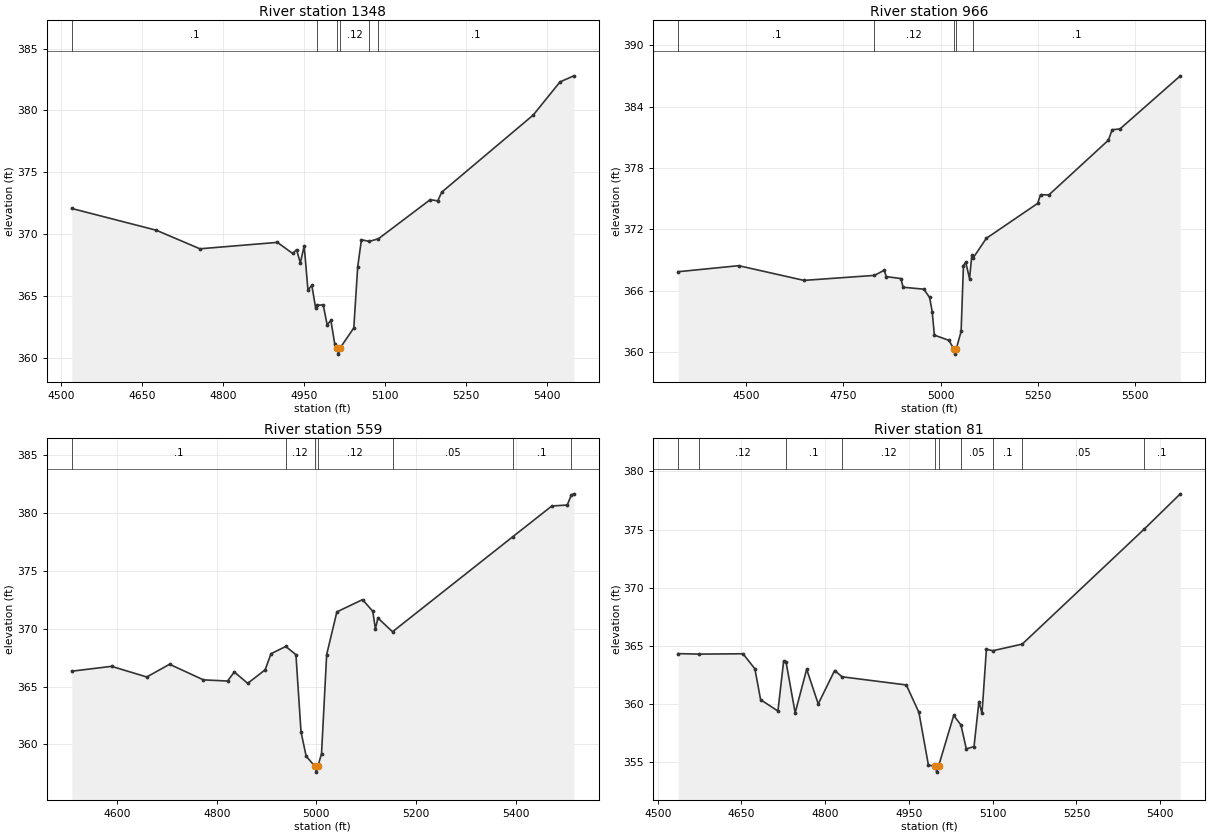
Type RM Length L Ch R = 1,1348,382,382,382
BEGIN DESCRIPTION:
Mapping XS 09afedbd
END DESCRIPTION:
XS GIS Cut Line= 3
      2206580.17     13184621.72      2206898.24     13184508.63
      2207322.27     13184095.20
#Sta/Elev= 30
  4520.1  372.07  4676.7  370.31  4757.4  368.81  4900.9  369.33  4929.2  368.43
  4936.4  368.74  4943.4  367.67  4950.5  369.04  4957.5  365.48  4964.7  365.85
  4971.7  364.03  4975.0  364.25  4985.8  364.27  4993.0  362.67  5000.0  363.01
  5007.1  361.11  5011.1  360.79  5013.8  360.29  5017.1  360.79  5042.4  362.41
  5049.6  367.34  5056.5  369.54  5071.0  369.41  5088.0  369.62  5183.8  372.78
  5198.0  372.69  5205.2  373.39  5374.7  379.63  5424.3  382.31  5449.9  382.80
#Mann=6,-1,0
  4520.1     0.1       0  4975.0    0.12       0  5011.1    0.07       0
  5017.1    0.12       0  5071.0    0.16       0  5088.0     0.1       0
Bank Sta=5011.1,5017.1
Exp/Cntr=0.3,0.1

Type RM Length L Ch R = 1,966,407,407,407
BEGIN DESCRIPTION:
Mapping XS 2e932d37
END DESCRIPTION:
XS GIS Cut Line= 4
      2206753.40     13184900.85      2207191.54     13184727.72
      2207460.10     13184264.80      2207445.97     13183982.14
#Sta/Elev= 30
  4326.2  367.85  4481.4  368.44  4649.0  367.00  4830.1  367.49  4854.9  367.99
  4860.7  367.37  4897.9  367.18  4903.7  366.33  4956.7  366.14  4971.7  365.33
  4978.3  363.95  4984.0  361.64  5021.3  361.13  5034.0  360.28  5036.8  359.78
  5040.0  360.28  5052.6  362.00  5058.6  368.45  5064.4  368.79  5074.3  367.16
  5080.1  369.48  5084.2  369.24  5117.4  371.12  5249.2  374.54  5256.5  375.39
  5278.0  375.37  5430.6  380.72  5440.6  381.75  5460.6  381.83  5615.5  387.03
#Mann=5,-1,0
  4326.2     0.1       0  4830.1    0.12       0  5034.0    0.07       0
  5040.0    0.12       0  5084.2     0.1       0
Bank Sta=5034,5040
Exp/Cntr=0.3,0.1

Type RM Length L Ch R = 1,559,478,478,478
BEGIN DESCRIPTION:
UNT 039 IN LACR 2.0
END DESCRIPTION:
XS GIS Cut Line= 4
      2206961.88     13185021.01      2207315.22     13184929.14
      2207711.00     13184833.73      2207940.66     13184780.73
#Sta/Elev= 30
  4508.9  366.34  4588.7  366.76  4659.5  365.84  4705.2  366.94  4773.2  365.59
  4821.6  365.49  4835.2  366.27  4862.1  365.29  4897.1  366.46  4908.8  367.85
  4938.5  368.48  4958.9  367.77  4969.1  361.10  4979.4  358.99  4997.0  358.11
  4999.8  357.61  5003.0  358.11  5010.3  359.22  5020.6  367.78  5041.1  371.47
  5092.6  372.53  5113.2  371.52  5118.4  370.00  5123.5  370.94  5152.8  369.75
  5394.5  377.98  5472.7  380.63  5503.5  380.71  5511.8  381.58  5516.8  381.68
#Mann=7,-1,0
  4508.9     0.1       0  4938.5    0.12       0  4997.0    0.07       0
  5003.0    0.12       0  5152.8    0.05       0  5394.5     0.1       0
  5511.8    0.05       0
Bank Sta=4997,5003
Exp/Cntr=0.3,0.1

Type RM Length L Ch R = 1,81,0,0,0
BEGIN DESCRIPTION:
UNT 039 IN LACR 1.0
END DESCRIPTION:
XS GIS Cut Line= 4
      2207244.58     13185162.37      2207608.52     13185254.24
      2207813.47     13185155.30      2208094.46     13185060.46
#Sta/Elev= 30
  4536.7  364.34  4573.7  364.30  4652.7  364.33  4674.0  363.04  4684.3  360.38
  4715.3  359.41  4725.6  363.72  4729.9  363.61  4746.2  359.25  4766.8  363.00
  4787.5  360.02  4816.9  362.89  4830.3  362.35  4945.3  361.65  4967.9  359.29
  4984.9  354.77  4997.0  354.66  4999.7  354.16  5003.0  354.66  5030.2  359.03
  5043.2  358.21  5052.8  356.16  5066.6  356.35  5075.4  360.22  5080.9  359.20
  5088.8  364.72  5100.3  364.59  5153.0  365.16  5371.1  375.02  5436.2  378.07
#Mann=10,-1,0
  4536.7     0.1       0  4573.7    0.12       0  4729.9     0.1       0
  4830.3    0.12       0  4997.0    0.07       0  5003.0    0.12       0
  5043.2    0.05       0  5100.3     0.1       0  5153.0    0.05       0
  5371.1     0.1       0
Bank Sta=4997,5003
Exp/Cntr=0.3,0.1

Chan Stop Cuts=-1