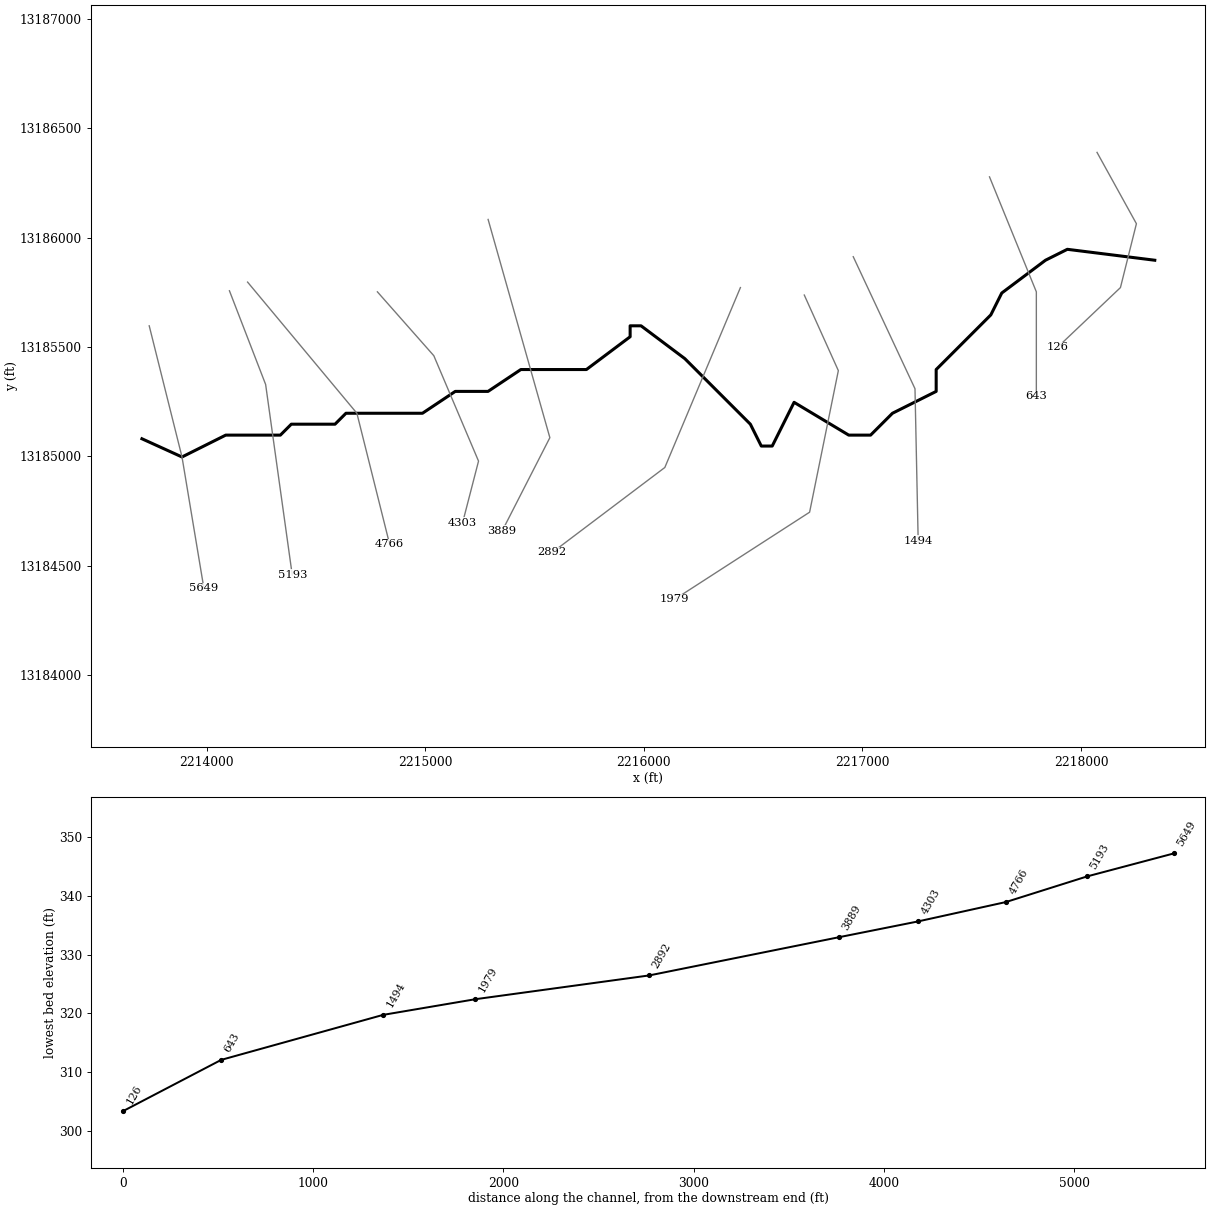
--- UNT 042 IN LACR.prj (project) ---

Proj Title=UNT 042 IN LACR Base Level Engineering
Current Plan=p01
Default Exp/Contr=0.3,0.1
English Units
Geom File=g01
Flow File=f01
Plan File=p01
Y Axis Title=Elevation
X Axis Title(PF)=Main Channel Distance
X Axis Title(XS)=Station
BEGIN DESCRIPTION:
UNT 042 IN LACR
END DESCRIPTION:
DSS Export Rating Curves= 0
DSS Export Rating Curve Sorted= 0
DSS Export Volume Flow Curves= 0
DXF OffsetX= 0
DXF OffsetY= 0
DXF ScaleX= 1
DXF ScaleY= 10

--- UNT 042 IN LACR.p01 (plan) ---

Plan Title=Multiple Run
Short Identifier=Multiple
Geom File=g01
Flow File=f01
Subcritical Flow
K Sum by GR= 0
Std Step Tol= 0.01
Critical Tol= 0.01
Num of Std Step Trials= 20
Max Error Tol= 0.3
Flow Tol Ratio= 0.001
Split Flow NTrial= 30
Split Flow Tol= 0.02
Split Flow Ratio= 0.02
Log Output Level= 0
Friction Slope Method= 1
Unsteady Friction Slope Method= 2
Unsteady Bridges Friction Slope Method= 1
Parabolic Critical Depth
Global Vel Dist=  1 , 1 , 1
Global Log Level= 0
CheckData=True
Encroach Param= -1, 0, 0, 0
BEGIN DESCRIPTION:
Multiple Run
END DESCRIPTION:

--- UNT 042 IN LACR.f01 (steady flow) ---

Flow Title=Multiple
Number of Profiles=7
Profile Names=10-year,25-year,50-year,1pct_min,100-year,1pct_plu,500-year
River Rch & RM= UNT 042 IN LACR,Reach-1,5649
     151     205     250     225     304     411     454
River Rch & RM= UNT 042 IN LACR,Reach-1,4303
     209     290     357     324     439     593     670
Boundary for River Rch & Prof#=UNT 042 IN LACR,Reach-1,1
Up Type=0
Dn Type=3
Dn Slope=0.005
Boundary for River Rch & Prof#=UNT 042 IN LACR,Reach-1,2
Up Type=0
Dn Type=3
Dn Slope=0.005
Boundary for River Rch & Prof#=UNT 042 IN LACR,Reach-1,3
Up Type=0
Dn Type=3
Dn Slope=0.005
Boundary for River Rch & Prof#=UNT 042 IN LACR,Reach-1,4
Up Type=0
Dn Type=3
Dn Slope=0.005
Boundary for River Rch & Prof#=UNT 042 IN LACR,Reach-1,5
Up Type=0
Dn Type=3
Dn Slope=0.005
Boundary for River Rch & Prof#=UNT 042 IN LACR,Reach-1,6
Up Type=0
Dn Type=3
Dn Slope=0.005
Boundary for River Rch & Prof#=UNT 042 IN LACR,Reach-1,7
Up Type=0
Dn Type=3
Dn Slope=0.005

--- UNT 042 IN LACR.g01 (geometry) ---

Geom Title=Existing Conditions
Program Version=4.10

River Reach=UNT 042 IN LACR ,Reach-1
Reach XY= 30
       2213704.4     13185080.17      2213887.72     13184996.85
      2214087.72     13185096.86      2214337.72     13185096.86
      2214387.72     13185146.85      2214587.72     13185146.85
      2214637.72     13185196.85      2214987.72     13185196.85
      2215137.72     13185296.85      2215287.72     13185296.85
      2215437.72     13185396.85      2215737.72     13185396.85
      2215937.72     13185546.85      2215937.72     13185596.86
      2215987.72     13185596.86      2216187.72     13185446.86
      2216487.72     13185146.85      2216537.72     13185046.85
      2216587.72     13185046.85      2216687.72     13185246.86
      2216937.72     13185096.86      2217037.72     13185096.86
      2217137.72     13185196.85      2217337.72     13185296.85
      2217337.72     13185396.85      2217587.72     13185646.85
      2217637.72     13185746.86      2217837.72     13185896.85
      2217937.72     13185946.85      2218337.72     13185896.85

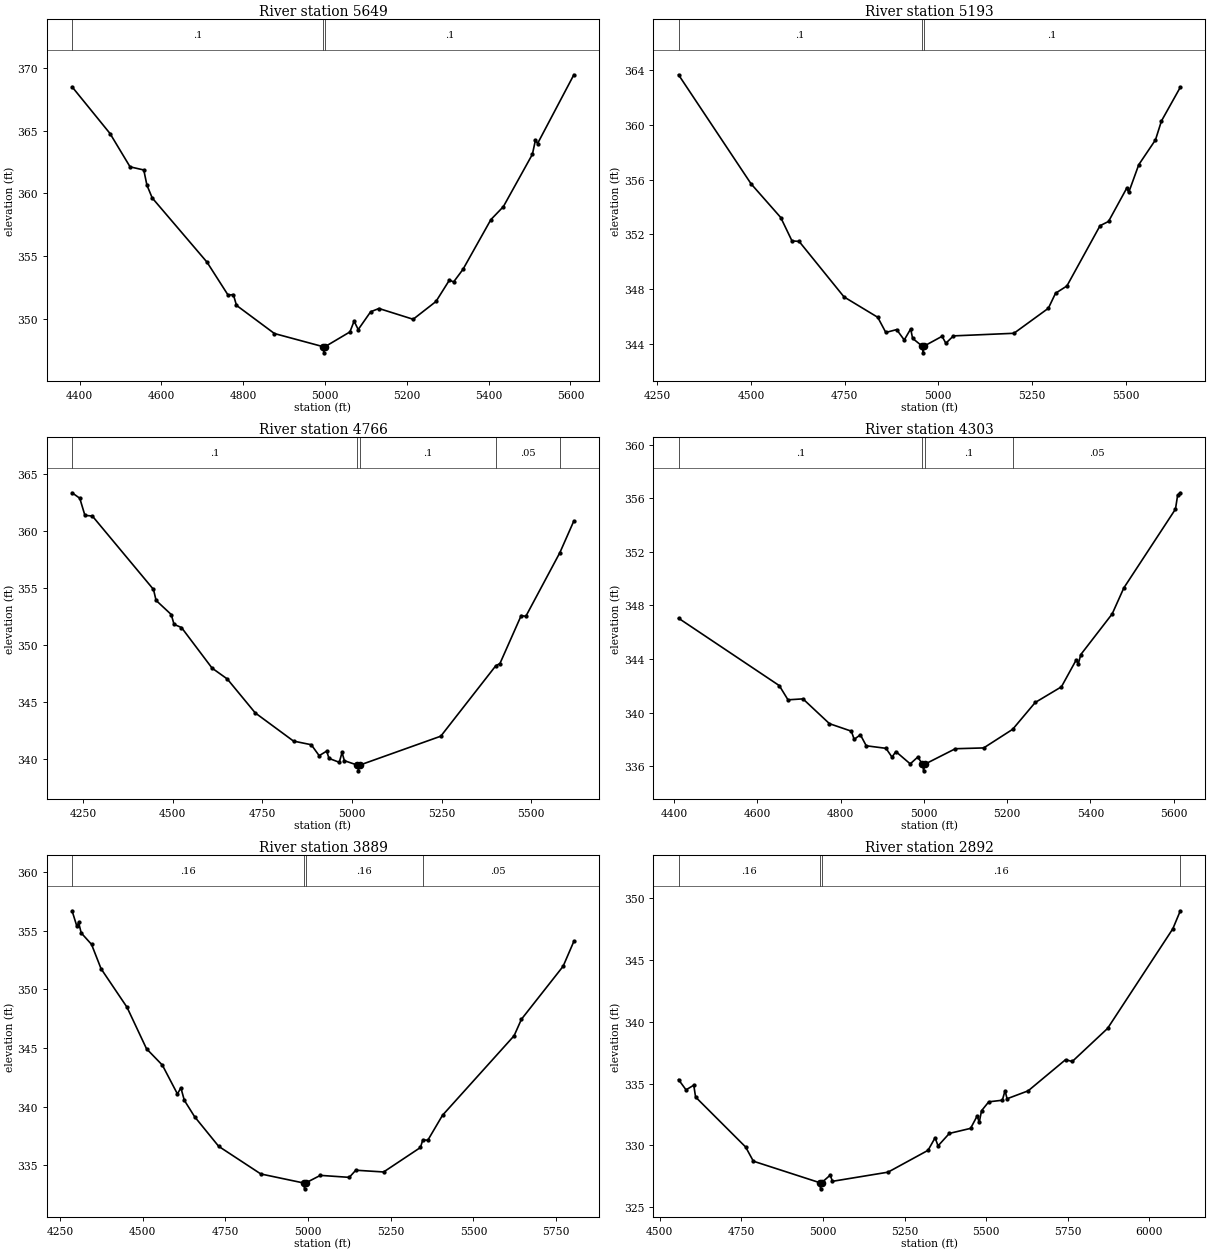
Type RM Length L Ch R = 1 ,5649    ,456,456,456
BEGIN DESCRIPTION:
UNT 042 IN LACR 5.0
END DESCRIPTION:
XS GIS Cut Line= 3
      2213737.71     13185596.89      2213887.72     13184996.85
      2213987.72     13184396.83
#Sta/Elev= 30
  4381.5   368.5  4474.3  364.77  4523.3  362.11  4556.8  361.86  4564.5  360.65
  4577.4  359.63  4711.4   354.5  4762.9  351.87  4775.8  351.91  4783.5  351.05
  4876.3   348.8  4994.4  347.76  4997.2  347.26  5000.4  347.76  5060.8  348.93
    5071  349.79  5081.1  349.12  5111.5  350.54  5131.8   350.8  5215.4  349.94
  5271.2  351.36  5304.1  353.07  5314.3  352.92  5337.1  353.92  5405.5   357.9
  5435.9  358.93  5506.9  363.11  5514.5  364.26  5519.6  363.97  5608.3  369.46
#Mann= 3 ,-1 , 0
  4381.5      .1       0  4994.4     .07       0  5000.4      .1       0
Bank Sta=4994.4,5000.4
XS Rating Curve= 0 ,0
Exp/Cntr=0.3,0.1

Type RM Length L Ch R = 1 ,5193    ,427,427,427
BEGIN DESCRIPTION:
UNT 042 IN LACR 4.0
END DESCRIPTION:
XS GIS Cut Line= 3
       2214104.7     13185757.13      2214270.26     13185328.61
        2214392.     13184456.97
#Sta/Elev= 30
  4306.6  363.68  4500.3   355.7  4579.4  353.24  4609.4  351.53  4628.5  351.49
  4748.4  347.43  4838.4  345.94  4859.9  344.83  4888.9  345.04  4909.1  344.28
  4926.3  345.09  4931.4   344.4  4956.6  343.84  4959.4  343.34  4962.6  343.84
  5010.1  344.55  5020.2  344.04  5040.4  344.58  5201.9  344.77  5293.8   346.6
    5313   347.7  5343.3  348.23  5431.8  352.64  5454.4  352.95  5503.3   355.4
  5508.3  355.07  5535.1   357.1  5579.8  358.92  5595.7   360.3  5646.1  362.77
#Mann= 3 ,-1 , 0
  4306.6      .1       0  4956.6     .07       0  4962.6      .1       0
Bank Sta=4956.6,4962.6
XS Rating Curve= 0 ,0
Exp/Cntr=0.3,0.1

Type RM Length L Ch R = 1 ,4766    ,463,463,463
BEGIN DESCRIPTION:
UNT 042 IN LACR 3.0
END DESCRIPTION:
XS GIS Cut Line= 3
      2214187.74     13185796.84      2214687.72     13185196.85
      2214837.73     13184596.82
#Sta/Elev= 30
    4219  363.36  4240.5  362.88  4254.8  361.38  4275.6  361.32  4446.1  354.88
  4453.3  353.92  4495.6  352.68  4503.4  351.82  4524.2  351.54  4609.5  347.98
  4651.8  347.03  4729.9  344.05  4836.6  341.58  4886.1  341.26  4908.2   340.3
  4929.1   340.7  4935.6  340.06  4964.2  339.72    4972  340.58  4978.5  339.86
    5015  339.47  5017.8  338.97    5021  339.47  5247.4  342.01  5400.8  348.19
  5412.3  348.38  5471.6  352.59  5484.5  352.52  5579.5  358.11  5618.5  360.89
#Mann= 5 ,-1 , 0
    4219      .1       0    5015     .07       0    5021      .1       0
  5400.8     .05       0  5579.5      .1       0
Bank Sta=5015,5021
XS Rating Curve= 0 ,0
Exp/Cntr=0.3,0.1

Type RM Length L Ch R = 1 ,4303    ,414,414,414
BEGIN DESCRIPTION:
UNT 042 IN LACR 2.0
END DESCRIPTION:
XS GIS Cut Line= 4
       2214781.6     13185752.26      2215039.68     13185460.09
      2215244.21     13184977.99      2215171.16      13184695.5
#Sta/Elev= 30
  4410.9  347.05  4652.9  342.02  4673.8  340.96  4709.8  341.03  4773.4  339.18
    4826  338.62  4832.8  338.01  4847.7  338.35  4861.8  337.53  4909.2  337.34
  4923.7  336.68  4932.8   337.1  4967.4  336.18  4985.6  336.69  4996.8  336.16
  4999.5  335.66  5002.8  336.16  5075.8  337.31  5143.9  337.37  5213.5  338.76
  5267.6  340.76  5330.6  341.93    5366  343.93  5371.2  343.65  5377.2  344.34
  5452.5  347.37  5480.5  349.31  5604.5  355.19  5609.8  356.24  5616.2  356.41
#Mann= 4 ,-1 , 0
  4410.9      .1       0  4996.8     .07       0  5002.8      .1       0
  5213.5     .05       0
Bank Sta=4996.8,5002.8
XS Rating Curve= 0 ,0
Exp/Cntr=0.3,0.1

Type RM Length L Ch R = 1 ,3889    ,997,997,997
BEGIN DESCRIPTION:
Mapping XS 8e5a2ca5
END DESCRIPTION:
XS GIS Cut Line= 3
      2215288.04     13186083.41      2215570.49     13185085.12
      2215352.03     13184657.91
#Sta/Elev= 30
  4286.5  356.72  4301.1  355.39  4306.3  355.72  4314.1  354.83  4345.4  353.85
  4374.2  351.77  4452.5  348.49  4511.6  344.94  4559.6  343.54  4605.1  341.08
  4615.5  341.61  4625.9  340.54    4657  339.14  4729.8  336.61  4857.2  334.25
  4986.6  333.48  4989.4  332.98  4992.6  333.48  5037.3  334.13  5124.7  333.96
  5144.4  334.57  5228.6  334.42  5339.9  336.51    5347  337.16  5362.2  337.13
  5406.6  339.26  5623.1  346.05  5645.3  347.46  5771.3  351.98  5803.8  354.11
#Mann= 4 ,-1 , 0
  4286.5     .16       0  4986.6     .07       0  4992.6     .16       0
    5347     .05       0
Bank Sta=4986.6,4992.6
XS Rating Curve= 0 ,0
Exp/Cntr=0.3,0.1

Type RM Length L Ch R = 1 ,2892    ,913,913,913
BEGIN DESCRIPTION:
Mapping XS a7084772
END DESCRIPTION:
XS GIS Cut Line= 3
      2216442.17     13185771.76      2216096.42     13184948.77
      2215581.48     13184560.13
#Sta/Elev= 30
  4557.5  335.32  4580.5  334.49  4604.2  334.87  4609.7  333.91  4763.1  329.86
  4786.8  328.71  4990.1  326.97  4992.9  326.47  4996.1  326.97  5022.3  327.58
  5029.2  327.08  5199.4  327.82  5322.1  329.59  5343.8  330.61  5352.8  329.95
  5387.4  330.96  5452.5  331.37  5472.8  332.38    5479  331.85  5486.1   332.8
  5508.2  333.52  5549.8  333.65  5558.1  334.42  5564.4  333.77  5628.9  334.41
  5743.4  336.93  5764.2  336.79  5872.4  339.47  6072.3  347.54  6095.3     349
#Mann= 4 ,-1 , 0
  4557.5     .16       0  4990.1     .07       0  4996.1     .16       0
  6095.3     .05       0
Bank Sta=4990.1,4996.1
XS Rating Curve= 0 ,0
Exp/Cntr=0.3,0.1

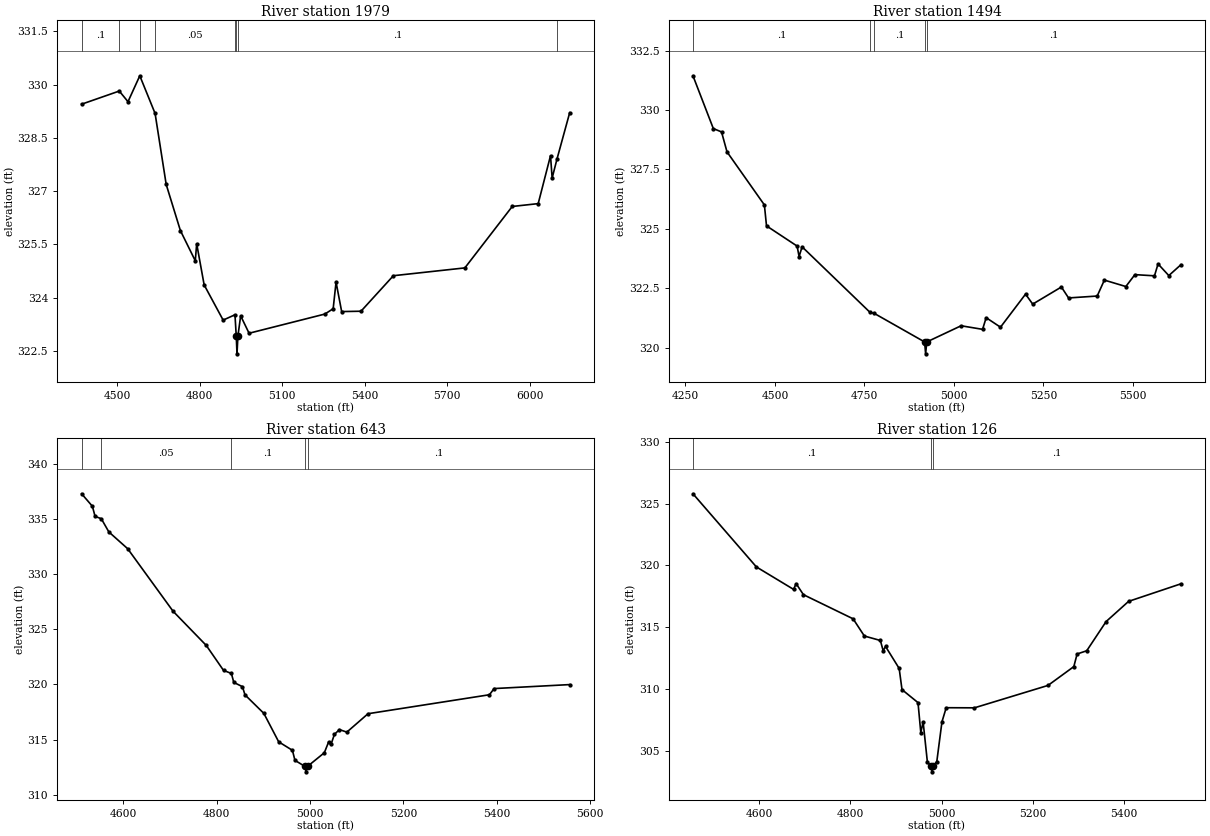
Type RM Length L Ch R = 1 ,1979    ,485,485,485
BEGIN DESCRIPTION:
Mapping XS 9ca90f80
END DESCRIPTION:
XS GIS Cut Line= 4
      2216734.36     13185737.66      2216890.19     13185391.91
       2216758.7     13184744.24      2216141.51     13184345.73
#Sta/Elev= 30
  4370.7  329.45  4507.6  329.82  4539.3  329.52  4582.2  330.25  4637.8  329.19
  4678.2  327.19  4729.9  325.89    4784  325.04  4789.1  325.52  4816.3  324.36
  4885.3  323.37  4928.3  323.52    4933  322.92  4935.7  322.42    4939  322.92
    4949  323.49  4979.6     323  5255.1  323.54  5285.4  323.69  5295.9  324.44
  5316.3  323.61  5386.6  323.62  5504.3  324.62  5764.3  324.84  5936.6  326.57
    6031  326.65  6075.8     328  6081.7  327.37  6099.5  327.91  6145.5  329.21
#Mann= 8 ,-1 , 0
  4370.7      .1       0  4507.6     .05       0  4582.2      .1       0
  4637.8     .05       0  4928.3      .1       0    4933     .07       0
    4939      .1       0  6099.5     .05       0
Bank Sta=4933,4939
XS Rating Curve= 0 ,0
Exp/Cntr=0.3,0.1

Type RM Length L Ch R = 1 ,1494    ,851,851,851
BEGIN DESCRIPTION:
Mapping XS ed993acc
END DESCRIPTION:
XS GIS Cut Line= 3
      2216958.37     13185912.95      2217240.81     13185309.13
      2217255.42     13184612.79
#Sta/Elev= 30
  4271.1  331.44    4328  329.22  4350.9  329.08  4366.2  328.24  4470.6  326.01
  4476.5  325.13    4562  324.28  4567.5  323.84  4575.9  324.25  4765.9  321.49
  4777.5  321.45  4918.1  320.25  4920.9  319.75  4924.1  320.25    5020  320.93
    5080  320.78    5090  321.27    5130  320.87    5200  322.26    5220  321.84
  5300.1  322.56  5320.1   322.1  5400.1  322.18  5420.1  322.85  5480.1  322.58
  5505.4  323.08  5560.1  323.03  5570.1  323.53  5600.1  323.04  5634.2   323.5
#Mann= 5 ,-1 , 0
  4271.1      .1       0  4765.9     .05       0  4777.5      .1       0
  4918.1     .07       0  4924.1      .1       0
Bank Sta=4918.1,4924.1
XS Rating Curve= 0 ,0
Exp/Cntr=0.3,0.1

Type RM Length L Ch R = 1 ,643     ,517,517,517
BEGIN DESCRIPTION:
Mapping XS 25e85d39
END DESCRIPTION:
XS GIS Cut Line= 3
       2217581.7     13186278.19      2217795.96     13185752.28
      2217795.96     13185275.06
#Sta/Elev= 30
    4511  337.29    4534  336.16  4539.8  335.24  4553.1  335.03  4569.3  333.83
  4609.6  332.31  4706.8  326.64  4777.9  323.54  4814.8  321.28  4831.7     321
  4836.8  320.19  4855.4   319.8  4860.8  319.06  4901.2  317.38    4933   314.8
  4962.4  314.03  4967.8  313.12  4988.9  312.58  4991.6  312.08  4994.9  312.58
  5030.7  313.81    5040   314.8  5045.4  314.61  5052.3  315.48  5063.1  315.91
  5078.9  315.68  5124.3  317.35  5384.3  319.07  5394.3  319.63  5556.1  319.99
#Mann= 5 ,-1 , 0
    4511      .1       0  4553.1     .05       0  4831.7      .1       0
  4988.9     .07       0  4994.9      .1       0
Bank Sta=4988.9,4994.9
XS Rating Curve= 0 ,0
Exp/Cntr=0.3,0.1

Type RM Length L Ch R = 1 ,126     ,0,0,0
BEGIN DESCRIPTION:
UNT 042 IN LACR 1.0
END DESCRIPTION:
XS GIS Cut Line= 4
      2218073.56     13186390.17      2218253.72     13186063.94
      2218180.67     13185771.75      2217893.34     13185499.03
#Sta/Elev= 30
  4455.1  325.79  4594.2  319.88  4675.6  318.07  4681.3  318.53  4697.3  317.64
  4806.2  315.69  4830.9   314.3    4866  313.94  4872.1  313.11  4877.3  313.46
  4907.2  311.68  4913.4  309.97  4948.5  308.92  4954.6   306.5  4959.7  307.37
  4969.1   304.1  4976.4  303.83  4979.1  303.33  4982.4  303.83  4989.7  304.16
    5001  307.37  5010.3  308.51  5072.2   308.5  5233.5  310.31  5290.1  311.83
  5297.3  312.85  5318.4  313.11  5360.9  315.47  5410.2   317.1  5525.1  318.52
#Mann= 3 ,-1 , 0
  4455.1      .1       0  4976.4     .07       0  4982.4      .1       0
Bank Sta=4976.4,4982.4
XS Rating Curve= 0 ,0
Exp/Cntr=0.3,0.1

Chan Stop Cuts=-1
Use User Specified Reach Order=0
Composite Channel Slope=5