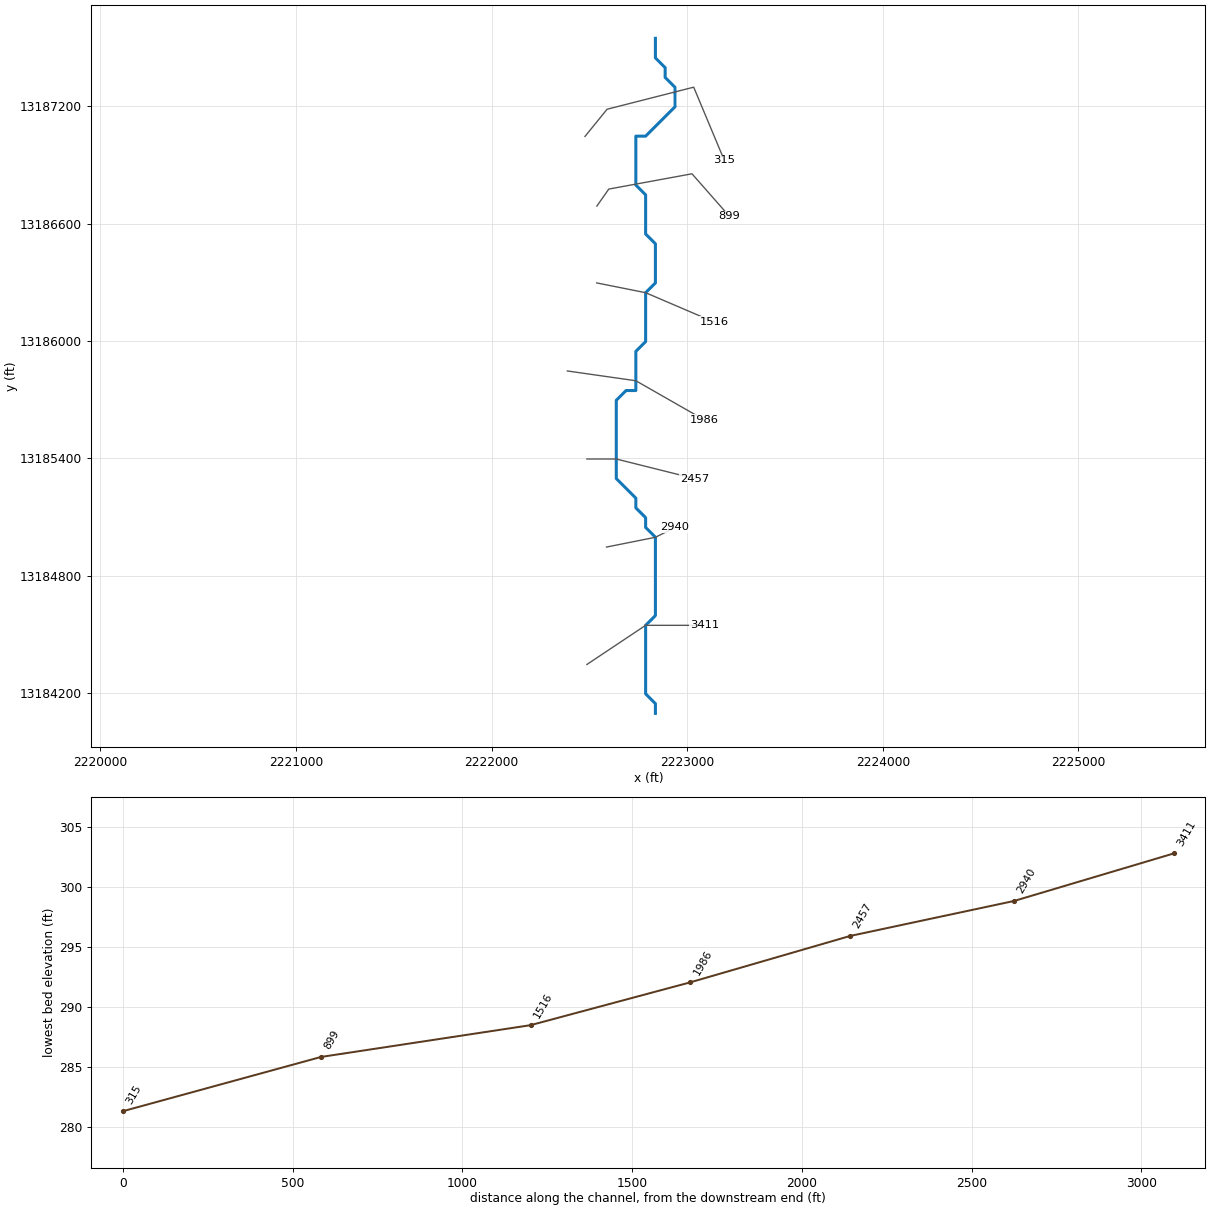
--- UNT 043 IN LACR.prj (project) ---

Proj Title=UNT 043 IN LACR Base Level Engineering
Current Plan=p01
Default Exp/Contr=0.3,0.1
English Units
Geom File=g01
Flow File=f01
Plan File=p01
BEGIN DESCRIPTION:
UNT 043 IN LACR
END DESCRIPTION:

--- UNT 043 IN LACR.p01 (plan) ---

Plan Title=Multiple Run
Short Identifier=Multiple
Geom File=g01
Flow File=f01
Subcritical Flow
K Sum by GR= 0
Std Step Tol= 0.01
Critical Tol= 0.01
Num of Std Step Trials= 20
Max Error Tol= 0.3
Flow Tol Ratio= 0.001
Split Flow NTrial= 30
Split Flow Tol= 0.02
Split Flow Ratio= 0.02
Log Output Level= 0
Friction Slope Method= 1
Unsteady Friction Slope Method= 2
Unsteady Bridges Friction Slope Method= 1
Parabolic Critical Depth
Global Vel Dist=  1 , 1 , 1
Global Log Level= 0
CheckData=True
Encroach Param= -1, 0, 0, 0
BEGIN DESCRIPTION:
Multiple Run
END DESCRIPTION:

--- UNT 043 IN LACR.f01 (steady flow) ---

Flow Title=Multiple
Number of Profiles=7
Profile Names=10-year,25-year,50-year,1pct_min,100-year,1pct_plu,500-year
River Rch & RM= UNT 043 IN LACR,Reach-1,3411
     246     344     426     388     525     710     810
Boundary for River Rch & Prof#=UNT 043 IN LACR,Reach-1,1
Up Type=0
Dn Type=3
Dn Slope=0.005
Boundary for River Rch & Prof#=UNT 043 IN LACR,Reach-1,2
Up Type=0
Dn Type=3
Dn Slope=0.005
Boundary for River Rch & Prof#=UNT 043 IN LACR,Reach-1,3
Up Type=0
Dn Type=3
Dn Slope=0.005
Boundary for River Rch & Prof#=UNT 043 IN LACR,Reach-1,4
Up Type=0
Dn Type=3
Dn Slope=0.005
Boundary for River Rch & Prof#=UNT 043 IN LACR,Reach-1,5
Up Type=0
Dn Type=3
Dn Slope=0.005
Boundary for River Rch & Prof#=UNT 043 IN LACR,Reach-1,6
Up Type=0
Dn Type=3
Dn Slope=0.005
Boundary for River Rch & Prof#=UNT 043 IN LACR,Reach-1,7
Up Type=0
Dn Type=3
Dn Slope=0.005

--- UNT 043 IN LACR.g01 (geometry) ---

Geom Title=Existing Conditions

River Reach=UNT 043 IN LACR,Reach-1
Reach XY= 30
      2222837.72     13184096.86      2222837.72     13184146.85
      2222787.72     13184196.85      2222787.72     13184546.85
      2222837.72     13184596.86      2222837.72     13184996.85
      2222787.72     13185046.85      2222787.72     13185096.86
      2222737.72     13185146.85      2222737.72     13185196.85
      2222637.72     13185296.85      2222637.72     13185696.85
      2222687.72     13185746.86      2222737.72     13185746.86
      2222737.72     13185946.85      2222787.72     13185996.85
      2222787.72     13186246.86      2222837.72     13186296.85
      2222837.72     13186496.85      2222787.72     13186546.85
      2222787.72     13186746.86      2222737.72     13186796.85
      2222737.72     13187046.86      2222787.72     13187046.86
      2222937.72     13187196.85      2222937.72     13187296.85
      2222887.72     13187346.85      2222887.72     13187396.86
      2222837.72     13187446.85      2222837.72     13187546.86

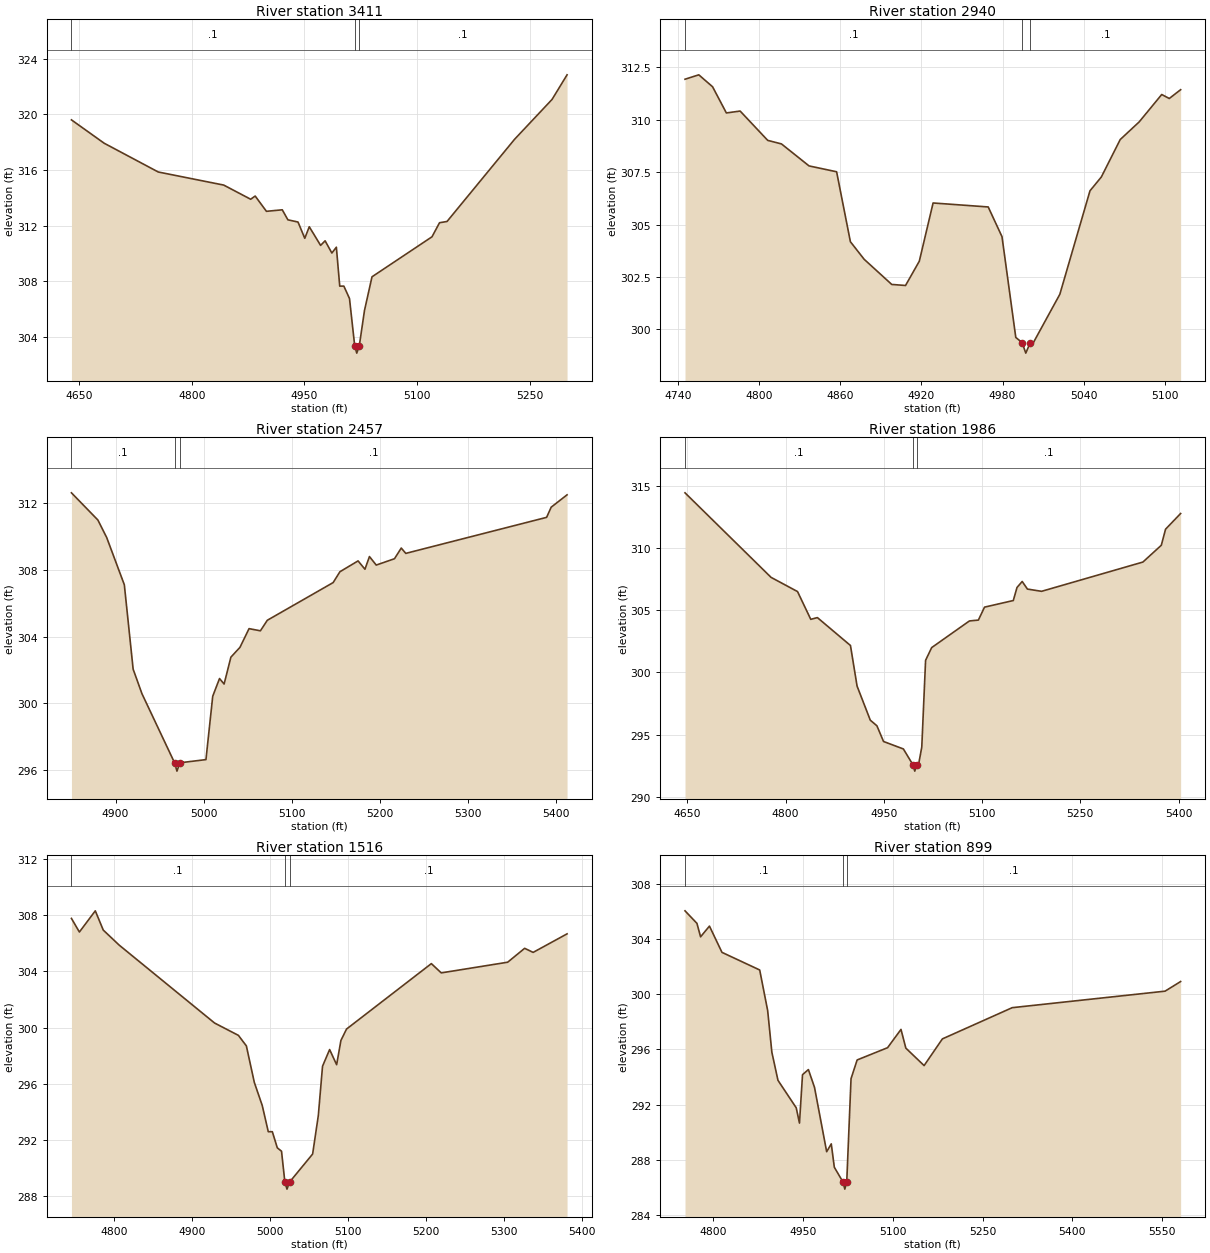
Type RM Length L Ch R = 1,3411,471,471,471
BEGIN DESCRIPTION:
UNT 043 IN LACR 7.0
END DESCRIPTION:
XS GIS Cut Line= 3
      2222487.68     13184346.83      2222787.72     13184546.85
      2223087.72     13184546.85
#Sta/Elev= 30
  4639.4  319.61  4683.0  317.93  4755.1  315.86  4842.3  314.92  4878.3  313.90
  4884.3  314.13  4899.3  313.03  4920.4  313.14  4927.9  312.42  4941.4  312.26
  4950.4  311.09  4956.4  311.92  4971.5  310.58  4977.5  310.91  4986.5  310.03
  4992.5  310.45  4997.0  307.65  5002.5  307.65  5010.0  306.76  5017.0  303.33
  5019.7  302.83  5023.0  303.33  5030.0  305.90  5040.0  308.32  5120.0  311.20
  5130.0  312.21  5140.0  312.30  5230.0  318.21  5280.0  321.08  5300.0  322.85
#Mann=3,-1,0
  4639.4     0.1       0  5017.0    0.07       0  5023.0     0.1       0
Bank Sta=5017,5023
Exp/Cntr=0.3,0.1

Type RM Length L Ch R = 1,2940,483,483,483
BEGIN DESCRIPTION:
UNT 043 IN LACR 6.0
END DESCRIPTION:
XS GIS Cut Line= 3
      2222587.67     13184946.85      2222837.72     13184996.85
      2222937.72     13185046.85
#Sta/Elev= 30
  4745.0  311.94  4755.2  312.15  4765.4  311.58  4775.6  310.33  4785.8  310.42
  4806.2  309.02  4816.4  308.85  4836.8  307.80  4857.2  307.52  4867.4  304.18
  4877.6  303.34  4898.0  302.14  4908.2  302.09  4918.4  303.25  4928.6  306.03
  4969.4  305.84  4979.6  304.42  4989.8  299.61  4994.5  299.36  4997.2  298.86
  5000.5  299.36  5002.8  299.36  5022.4  301.67  5044.7  306.61  5053.1  307.27
  5067.1  309.06  5081.1  309.90  5097.8  311.21  5103.4  311.02  5111.8  311.44
#Mann=3,-1,0
  4745.0     0.1       0  4994.5    0.07       0  5000.5     0.1       0
Bank Sta=4994.5,5000.5
Exp/Cntr=0.3,0.1

Type RM Length L Ch R = 1,2457,471,471,471
BEGIN DESCRIPTION:
UNT 043 IN LACR 5.0
END DESCRIPTION:
XS GIS Cut Line= 3
      2222487.72     13185396.85      2222637.72     13185396.85
      2223037.71     13185296.86
#Sta/Elev= 30
  4850.0  312.62  4880.0  310.99  4890.0  309.94  4910.0  307.11  4920.0  302.05
  4930.0  300.58  4967.0  296.44  4969.7  295.94  4973.0  296.44  5002.6  296.63
  5010.3  300.43  5018.0  301.49  5023.2  301.16  5030.9  302.77  5041.2  303.36
  5051.5  304.48  5064.4  304.35  5072.2  304.98  5146.9  307.24  5154.6  307.89
  5175.2  308.54  5183.0  308.04  5188.1  308.80  5195.8  308.29  5216.5  308.67
  5224.2  309.31  5229.3  308.99  5389.1  311.15  5394.3  311.76  5412.3  312.50
#Mann=3,-1,0
  4850.0     0.1       0  4967.0    0.07       0  4973.0     0.1       0
Bank Sta=4967,4973
Exp/Cntr=0.3,0.1

Type RM Length L Ch R = 1,1986,470,470,470
BEGIN DESCRIPTION:
UNT 043 IN LACR 4.0
END DESCRIPTION:
XS GIS Cut Line= 3
      2222387.67     13185846.86      2222737.72     13185796.85
      2223087.71     13185596.86
#Sta/Elev= 30
  4646.4  314.42  4777.8  307.63  4818.2  306.49  4838.4  304.26  4848.5  304.40
  4899.0  302.16  4909.1  298.90  4929.3  296.16  4939.4  295.71  4949.5  294.45
  4979.8  293.85  4994.5  292.57  4997.2  292.07  5000.5  292.57  5002.9  292.57
  5007.9  294.01  5013.7  300.97  5023.0  301.99  5080.6  304.13  5094.3  304.20
  5103.7  305.24  5147.6  305.77  5153.3  306.82  5161.2  307.30  5169.2  306.69
  5190.8  306.51  5345.5  308.86  5373.6  310.21  5380.1  311.50  5403.1  312.76
#Mann=3,-1,0
  4646.4     0.1       0  4994.5    0.07       0  5000.5     0.1       0
Bank Sta=4994.5,5000.5
Exp/Cntr=0.3,0.1

Type RM Length L Ch R = 1,1516,617,617,617
BEGIN DESCRIPTION:
UNT 043 IN LACR 3.0
END DESCRIPTION:
XS GIS Cut Line= 3
      2222537.67     13186296.86      2222787.72     13186246.86
      2223137.73     13186096.85
#Sta/Elev= 30
  4745.0  307.78  4755.2  306.81  4775.6  308.32  4785.8  306.95  4806.2  305.88
  4928.6  300.33  4959.2  299.45  4969.4  298.70  4979.6  296.10  4989.8  294.45
  4997.5  292.59  5002.7  292.59  5009.1  291.44  5014.5  291.20  5018.8  289.00
  5021.5  288.50  5024.8  289.00  5054.4  291.00  5061.7  293.74  5067.1  297.25
  5076.2  298.44  5085.2  297.36  5090.7  299.09  5097.9  299.90  5206.7  304.56
  5219.4  303.90  5304.6  304.66  5326.4  305.65  5337.3  305.36  5380.8  306.68
#Mann=3,-1,0
  4745.0     0.1       0  5018.8    0.07       0  5024.8     0.1       0
Bank Sta=5018.8,5024.8
Exp/Cntr=0.3,0.1

Type RM Length L Ch R = 1,899,584,584,584
BEGIN DESCRIPTION:
UNT 043 IN LACR 2.0
END DESCRIPTION:
XS GIS Cut Line= 4
      2222538.55     13186689.57      2222599.34     13186776.42
      2223024.69     13186854.54      2223215.63     13186637.56
#Sta/Elev= 30
  4753.3  306.08  4773.2  305.17  4779.3  304.19  4794.1  304.97  4815.0  303.06
  4878.0  301.78  4891.3  298.83  4898.3  295.80  4908.5  293.76  4939.0  291.76
  4944.4  290.65  4949.5  294.17  4959.3  294.54  4969.5  293.25  4989.8  288.57
  4997.5  289.14  5002.6  287.44  5017.3  286.35  5020.1  285.85  5023.3  286.35
  5030.5  293.88  5040.7  295.24  5091.5  296.13  5113.9  297.46  5122.0  296.10
  5152.5  294.83  5183.0  296.77  5299.6  299.04  5554.8  300.24  5580.8  300.94
#Mann=3,-1,0
  4753.3     0.1       0  5017.3    0.07       0  5023.3     0.1       0
Bank Sta=5017.3,5023.3
Exp/Cntr=0.3,0.1

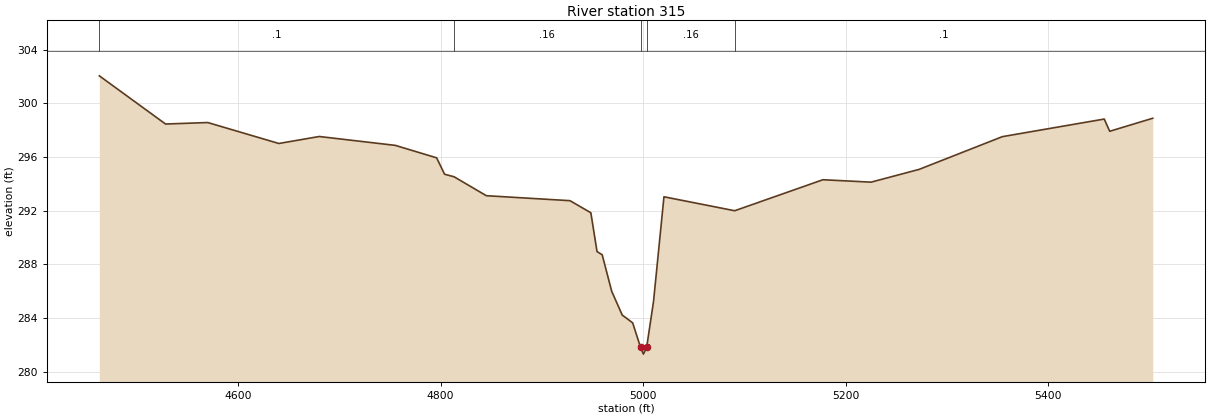
Type RM Length L Ch R = 1,315,0,0,0
BEGIN DESCRIPTION:
UNT 043 IN LACR 1.0
END DESCRIPTION:
XS GIS Cut Line= 4
      2222477.82     13187045.52      2222590.66     13187184.40
      2223033.37     13187297.25      2223189.64     13186923.94
#Sta/Elev= 30
  4462.9  302.05  4528.3  298.46  4570.0  298.57  4640.2  297.01  4680.1  297.53
  4755.2  296.87  4796.1  295.94  4803.9  294.72  4813.3  294.53  4845.2  293.12
  4927.8  292.75  4948.4  291.85  4954.5  288.96  4959.6  288.72  4969.0  286.00
  4979.4  284.23  4989.7  283.65  4997.5  281.82  5000.3  281.32  5003.5  281.82
  5010.3  285.24  5020.6  293.04  5090.5  292.00  5177.6  294.31  5225.2  294.13
  5272.6  295.08  5354.9  297.52  5455.5  298.83  5460.9  297.92  5503.4  298.89
#Mann=5,-1,0
  4462.9     0.1       0  4813.3    0.16       0  4997.5    0.07       0
  5003.5    0.16       0  5090.5     0.1       0
Bank Sta=4997.5,5003.5
Exp/Cntr=0.3,0.1

Chan Stop Cuts=-1