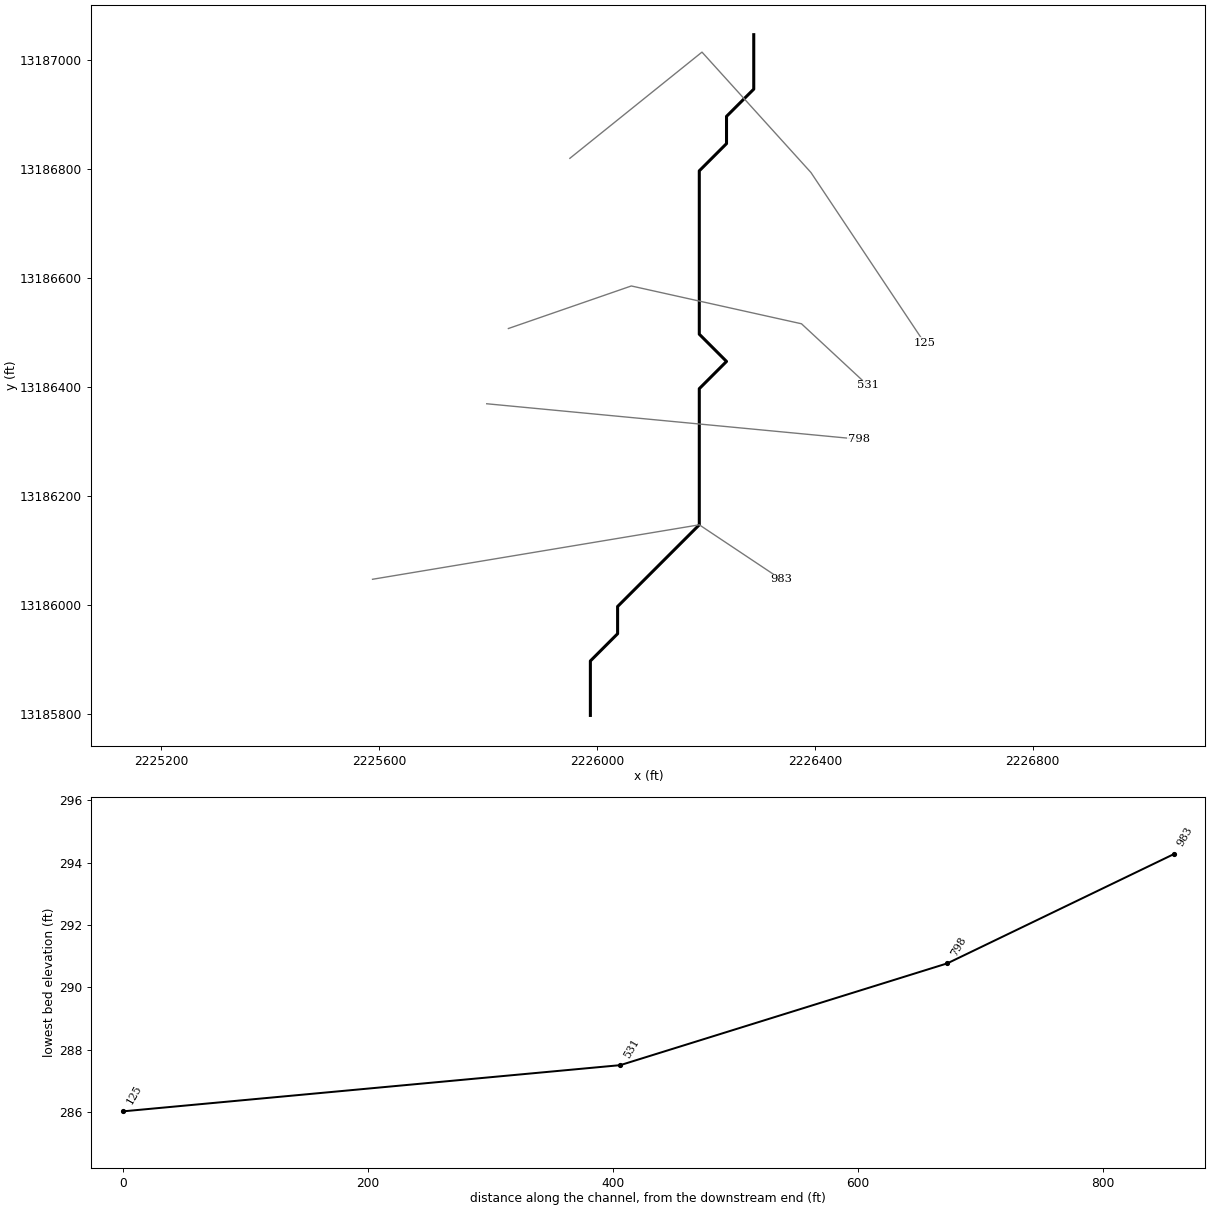
--- UNT 045 IN LACR.prj (project) ---

Proj Title=UNT 045 IN LACR Base Level Engineering
Current Plan=p01
Default Exp/Contr=0.3,0.1
English Units
Geom File=g01
Flow File=f01
Plan File=p01
BEGIN DESCRIPTION:
UNT 045 IN LACR
END DESCRIPTION:

--- UNT 045 IN LACR.p01 (plan) ---

Plan Title=Multiple Run
Short Identifier=Multiple
Geom File=g01
Flow File=f01
Subcritical Flow
K Sum by GR= 0
Std Step Tol= 0.01
Critical Tol= 0.01
Num of Std Step Trials= 20
Max Error Tol= 0.3
Flow Tol Ratio= 0.001
Split Flow NTrial= 30
Split Flow Tol= 0.02
Split Flow Ratio= 0.02
Log Output Level= 0
Friction Slope Method= 1
Unsteady Friction Slope Method= 2
Unsteady Bridges Friction Slope Method= 1
Parabolic Critical Depth
Global Vel Dist=  1 , 1 , 1
Global Log Level= 0
CheckData=True
Encroach Param= -1, 0, 0, 0
BEGIN DESCRIPTION:
Multiple Run
END DESCRIPTION:

--- UNT 045 IN LACR.f01 (steady flow) ---

Flow Title=Multiple
Number of Profiles=7
Profile Names=10-year,25-year,50-year,1pct_min,100-year,1pct_plu,500-year
River Rch & RM= UNT 045 IN LACR,Reach-1,983
     259     362     449     410     554     749     857
Boundary for River Rch & Prof#=UNT 045 IN LACR,Reach-1,1
Up Type=0
Dn Type=3
Dn Slope=0.005
Boundary for River Rch & Prof#=UNT 045 IN LACR,Reach-1,2
Up Type=0
Dn Type=3
Dn Slope=0.005
Boundary for River Rch & Prof#=UNT 045 IN LACR,Reach-1,3
Up Type=0
Dn Type=3
Dn Slope=0.005
Boundary for River Rch & Prof#=UNT 045 IN LACR,Reach-1,4
Up Type=0
Dn Type=3
Dn Slope=0.005
Boundary for River Rch & Prof#=UNT 045 IN LACR,Reach-1,5
Up Type=0
Dn Type=3
Dn Slope=0.005
Boundary for River Rch & Prof#=UNT 045 IN LACR,Reach-1,6
Up Type=0
Dn Type=3
Dn Slope=0.005
Boundary for River Rch & Prof#=UNT 045 IN LACR,Reach-1,7
Up Type=0
Dn Type=3
Dn Slope=0.005

--- UNT 045 IN LACR.g01 (geometry) ---

Geom Title=Existing Conditions

River Reach=UNT 045 IN LACR,Reach-1
Reach XY= 26
      2225987.72     13185796.85      2225987.72     13185846.85
      2225987.72     13185896.85      2226037.72     13185946.85
      2226037.72     13185996.85      2226087.72     13186046.85
      2226137.72     13186096.86      2226187.72     13186146.85
      2226187.72     13186196.85      2226187.72     13186246.86
      2226187.72     13186296.85      2226187.72     13186346.85
      2226187.72     13186396.86      2226237.72     13186446.85
      2226187.72     13186496.85      2226187.72     13186546.85
      2226187.72     13186596.85      2226187.72     13186646.85
      2226187.72     13186696.85      2226187.72     13186746.86
      2226187.72     13186796.85      2226237.72     13186846.85
      2226237.72     13186896.86      2226287.72     13186946.85
      2226287.72     13186996.85      2226287.72     13187046.86

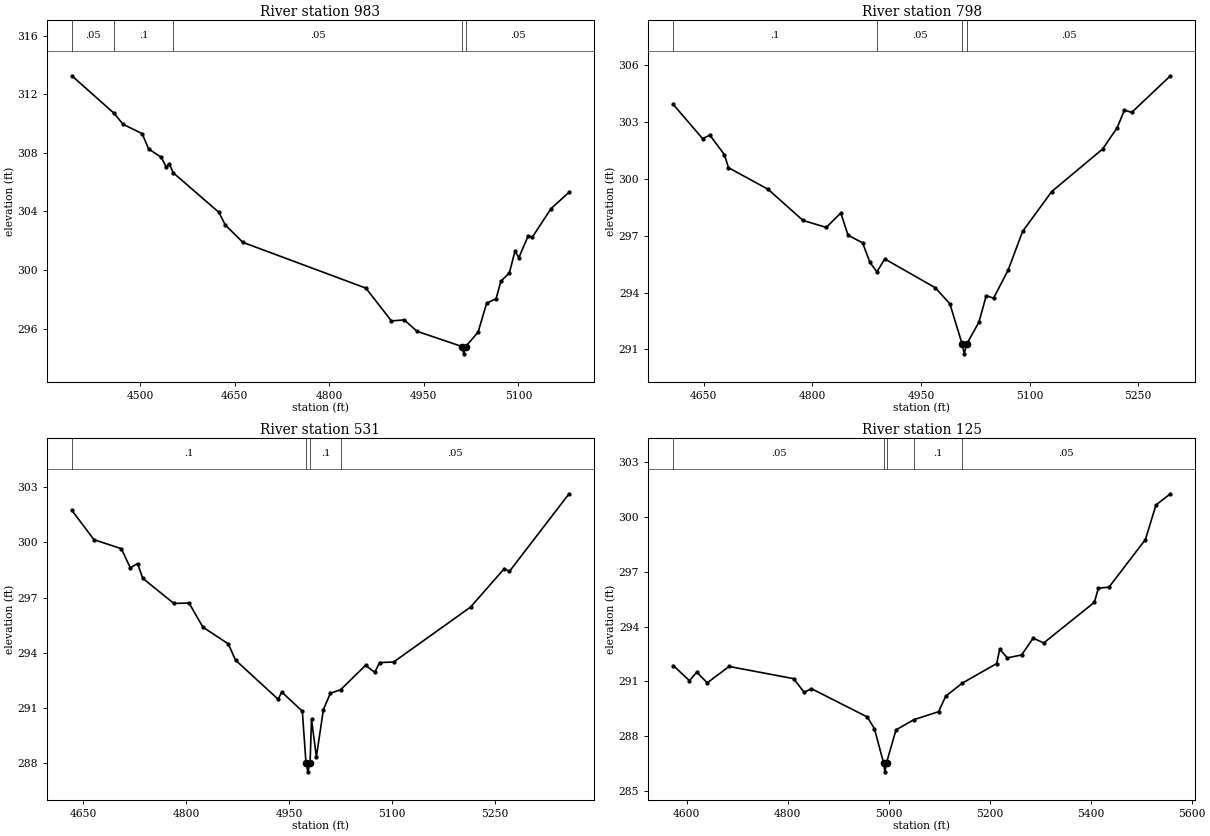
Type RM Length L Ch R = 1,983,185,185,185
BEGIN DESCRIPTION:
UNT 045 IN LACR 2.0
END DESCRIPTION:
XS GIS Cut Line= 3
      2225587.70     13186046.85      2226187.72     13186146.85
      2226337.74     13186046.84
#Sta/Elev= 30
  4391.7  313.27  4458.9  310.70  4472.8  309.96  4503.2  309.32  4513.4  308.28
  4533.7  307.69  4541.3  307.04  4546.3  307.25  4552.6  306.64  4624.9  303.94
  4635.0  303.08  4662.9  301.89  4858.1  298.76  4898.6  296.52  4918.9  296.59
  4939.2  295.81  5010.5  294.77  5013.3  294.27  5016.5  294.77  5036.1  295.76
  5049.6  297.73  5064.6  298.04  5072.1  299.22  5085.6  299.80  5094.6  301.29
  5100.7  300.84  5115.7  302.35  5121.7  302.22  5151.7  304.19  5180.3  305.31
#Mann=5,-1,0
  4391.7    0.05       0  4458.9     0.1       0  4552.6    0.05       0
  5010.5    0.03       0  5016.5    0.05       0
Bank Sta=5010.5,5016.5
Exp/Cntr=0.3,0.1

Type RM Length L Ch R = 1,798,267,267,267
BEGIN DESCRIPTION:
Mapping XS 33ead550
END DESCRIPTION:
XS GIS Cut Line= 2
      2225797.39     13186369.14      2226480.99     13186304.03
#Sta/Elev= 30
  4607.9  303.91  4648.4  302.11  4658.5  302.29  4678.6  301.26  4684.1  300.58
  4738.8  299.44  4787.1  297.80  4819.2  297.43  4839.3  298.19  4849.3  297.02
  4869.4  296.62  4879.5  295.59  4889.1  295.09  4900.1  295.77  4969.9  294.25
  4990.0  293.40  5007.0  291.27  5009.8  290.77  5013.0  291.27  5030.1  292.44
  5040.2  293.84  5050.2  293.70  5070.3  295.17  5090.4  297.22  5130.6  299.32
  5200.9  301.56  5221.0  302.68  5231.0  303.61  5241.1  303.49  5294.6  305.42
#Mann=4,-1,0
  4607.9     0.1       0  4889.1    0.05       0  5007.0    0.03       0
  5013.0    0.05       0
Bank Sta=5007,5013
Exp/Cntr=0.3,0.1

Type RM Length L Ch R = 1,531,406,406,406
BEGIN DESCRIPTION:
Mapping XS 52c78929
END DESCRIPTION:
XS GIS Cut Line= 4
      2225837.20     13186507.32      2226062.88     13186585.44
      2226375.38     13186516.00      2226496.92     13186403.14
#Sta/Elev= 30
  4633.3  301.75  4665.6  300.15  4705.5  299.66  4718.5  298.62  4729.1  298.85
  4736.6  298.05  4782.0  296.68  4804.2  296.70  4824.3  295.39  4861.3  294.48
  4872.0  293.59  4934.1  291.46  4939.2  291.86  4969.3  290.81  4974.6  288.01
  4977.4  287.51  4980.6  288.01  4982.7  290.36  4989.8  288.33  5000.0  290.90
  5010.2  291.79  5025.1  291.98  5061.5  293.31  5074.9  292.93  5082.0  293.46
  5102.4  293.49  5214.5  296.48  5263.8  298.58  5271.1  298.42  5358.1  302.65
#Mann=4,-1,0
  4633.3     0.1       0  4974.6    0.07       0  4980.6     0.1       0
  5025.1    0.05       0
Bank Sta=4974.6,4980.6
Exp/Cntr=0.3,0.1

Type RM Length L Ch R = 1,125,0,0,0
BEGIN DESCRIPTION:
UNT 045 IN LACR 1.0
END DESCRIPTION:
XS GIS Cut Line= 4
      2225950.07     13186819.85      2226192.67     13187014.86
      2226392.74     13186793.78      2226600.90     13186481.53
#Sta/Elev= 30
  4573.3  291.86  4605.4  291.03  4619.8  291.50  4640.6  290.91  4683.8  291.81
  4811.8  291.14  4832.6  290.39  4847.0  290.59  4957.6  289.04  4971.8  288.39
  4989.7  286.53  4992.5  286.03  4995.7  286.53  5014.4  288.33  5049.8  288.89
  5098.8  289.33  5113.0  290.18  5145.4  290.89  5213.9  291.97  5219.9  292.76
  5234.9  292.28  5263.2  292.44  5286.0  293.36  5307.1  293.10  5407.4  295.33
  5415.2  296.10  5436.3  296.16  5508.4  298.77  5529.4  300.67  5558.0  301.28
#Mann=5,-1,0
  4573.3    0.05       0  4989.7    0.03       0  4995.7    0.05       0
  5049.8     0.1       0  5145.4    0.05       0
Bank Sta=4989.7,4995.7
Exp/Cntr=0.3,0.1

Chan Stop Cuts=-1