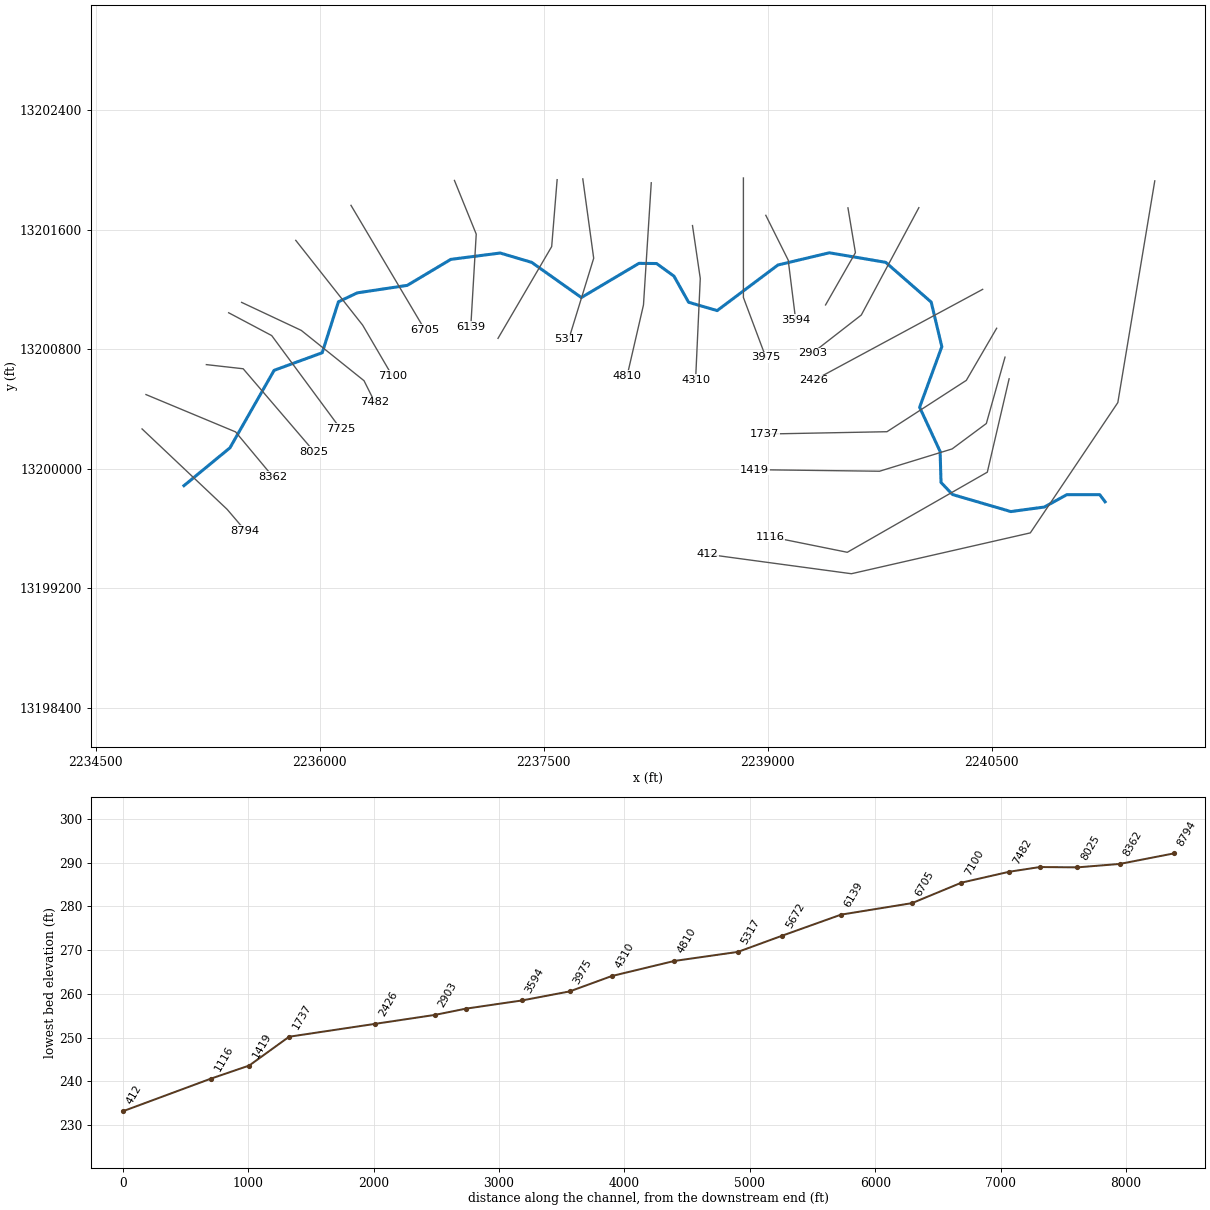
--- UNT 047 IN LACR.prj (project) ---

Proj Title=UNT 047 IN LACR Base Level Engineering
Current Plan=p01
Default Exp/Contr=0.3,0.1
English Units
Geom File=g01
Flow File=f01
Plan File=p01
Y Axis Title=Elevation
X Axis Title(PF)=Main Channel Distance
X Axis Title(XS)=Station
BEGIN DESCRIPTION:
UNT 047 IN LACR
END DESCRIPTION:
DSS Export Rating Curves= 0
DSS Export Rating Curve Sorted= 0
DSS Export Volume Flow Curves= 0
DXF OffsetX= 0
DXF OffsetY= 0
DXF ScaleX= 1
DXF ScaleY= 10

--- UNT 047 IN LACR.p01 (plan) ---

Plan Title=Multiple Run
Short Identifier=Multiple
Geom File=g01
Flow File=f01
Subcritical Flow
K Sum by GR= 0
Std Step Tol= 0.01
Critical Tol= 0.01
Num of Std Step Trials= 20
Max Error Tol= 0.3
Flow Tol Ratio= 0.001
Split Flow NTrial= 30
Split Flow Tol= 0.02
Split Flow Ratio= 0.02
Log Output Level= 0
Friction Slope Method= 1
Unsteady Friction Slope Method= 2
Unsteady Bridges Friction Slope Method= 1
Parabolic Critical Depth
Global Vel Dist=  1 , 1 , 1
Global Log Level= 0
CheckData=True
Encroach Param= -1, 0, 0, 0
BEGIN DESCRIPTION:
Multiple Run
END DESCRIPTION:

--- UNT 047 IN LACR.f01 (steady flow) ---

Flow Title=Multiple
Program Version=4.10
Number of Profiles= 7
Profile Names=10-year,25-year,50-year,1pct_min,100-year,1pct_plu,500-year
River Rch & RM=UNT 047 IN LACR,Reach-1         ,8794
     167     228     278     249     337     456     505
River Rch & RM=UNT 047 IN LACR,Reach-1         ,4810
     167     228     278     249     337     456     505
River Rch & RM=UNT 047 IN LACR,Reach-1         ,8025
     202     278     341     308     416     563     631
River Rch & RM=UNT 047 IN LACR,Reach-1         ,7725
     202     278     341     308     416     563     631
River Rch & RM=UNT 047 IN LACR,Reach-1         ,7100
     313     441     550     504     682     922    1064
Boundary for River Rch & Prof#=UNT 047 IN LACR,Reach-1         , 1
Up Type= 0
Dn Type= 3
Dn Slope=0.005
Boundary for River Rch & Prof#=UNT 047 IN LACR,Reach-1         , 2
Up Type= 0
Dn Type= 3
Dn Slope=0.005
Boundary for River Rch & Prof#=UNT 047 IN LACR,Reach-1         , 3
Up Type= 0
Dn Type= 3
Dn Slope=0.005
Boundary for River Rch & Prof#=UNT 047 IN LACR,Reach-1         , 4
Up Type= 0
Dn Type= 3
Dn Slope=0.005
Boundary for River Rch & Prof#=UNT 047 IN LACR,Reach-1         , 5
Up Type= 0
Dn Type= 3
Dn Slope=0.005
Boundary for River Rch & Prof#=UNT 047 IN LACR,Reach-1         , 6
Up Type= 0
Dn Type= 3
Dn Slope=0.005
Boundary for River Rch & Prof#=UNT 047 IN LACR,Reach-1         , 7
Up Type= 0
Dn Type= 3
Dn Slope=0.005
DSS Import GetInterval= 0
DSS Import GetPeak= 0
DSS Import FillOption= 0

--- UNT 047 IN LACR.g01 (geometry) ---

Geom Title=Existing Conditions
Program Version=4.10

River Reach=UNT 047 IN LACR ,Reach-1
Reach XY= 30
      2235092.14     13199886.83      2235400.13     13200140.44
      2235695.77     13200659.07      2236017.72     13200776.85
      2236126.25     13201117.94      2236252.36     13201177.66
      2236587.43       13201228.      2236878.68     13201401.92
      2237209.46     13201444.47      2237420.36     13201381.85
       2237752.7     13201146.45      2238138.42     13201375.32
      2238256.57     13201374.02      2238372.85     13201289.68
      2238470.85     13201114.68      2238661.84     13201058.99
      2239068.81     13201364.22      2239413.01     13201446.09
      2239790.49     13201382.15      2240095.12     13201115.78
      2240166.24     13200817.43      2240017.55     13200411.96
      2240154.75     13200115.56      2240160.87     13199908.19
       2240237.9     13199827.49      2240628.23     13199713.43
      2240852.93     13199743.92      2241002.63     13199826.39
      2241223.14     13199826.72      2241259.38     13199779.01

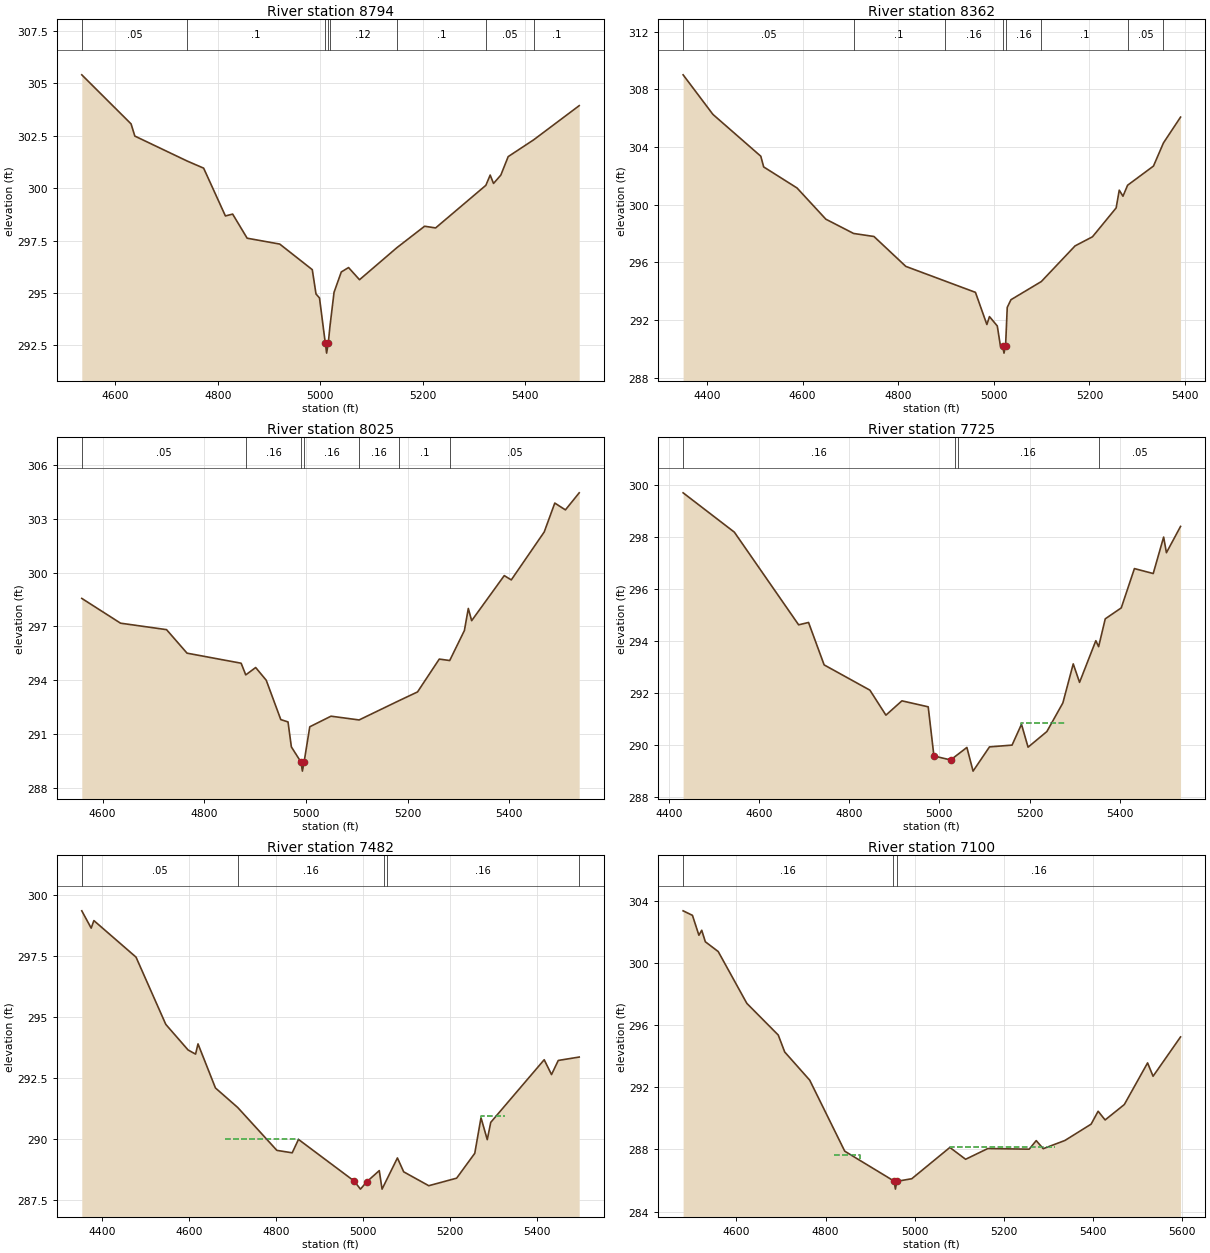
Type RM Length L Ch R = 1 ,8794    ,432,432,432
BEGIN DESCRIPTION:
UNT 047 IN LACR 17.0
END DESCRIPTION:
XS GIS Cut Line= 3
      2234811.53     13200266.74      2235380.96     13199728.56
       2235502.5     13199586.19
#Sta/Elev= 30
  4534.3   305.4  4630.5  303.06  4637.8  302.48  4739.9  301.29  4772.1  300.95
  4814.6  298.67  4828.7  298.76    4857  297.61  4920.6  297.33  4984.1  296.11
  4991.4  294.95  4998.2  294.76  5009.4  292.63  5012.1  292.13  5015.4  292.63
  5018.7  293.43  5026.6  295.03  5040.7     296  5054.9  296.21  5076.3  295.63
  5148.8  297.15  5203.3  298.18  5224.8   298.1  5322.8  300.13  5331.3  300.62
  5337.8  300.22  5352.1  300.62  5366.4   301.5  5416.1   302.3    5505  303.93
#Mann= 8 ,-1 , 0
  4534.3     .05       0  4739.9      .1       0  5009.4     .07       0
  5015.4      .1       0  5018.7     .12       0  5148.8      .1       0
  5322.8     .05       0  5416.1      .1       0
Bank Sta=5009.4,5015.4
XS Rating Curve= 0 ,0
Exp/Cntr=0.3,0.1

Type RM Length L Ch R = 1 ,8362    ,337,337,337
BEGIN DESCRIPTION:
UNT 047 IN LACR 16.0
END DESCRIPTION:
XS GIS Cut Line= 3
      2234837.72     13200496.85      2235437.72     13200246.85
      2235687.71     13199946.86
#Sta/Elev= 30
    4350     309  4412.3  306.26  4512.5  303.36  4518.5  302.62  4588.3  301.16
  4648.5     299  4706.6  298.01  4749.2   297.8  4815.8  295.73  4897.5  294.72
  4961.5  293.93  4985.4   291.7  4990.8  292.25  5007.2   291.6  5013.7  290.22
  5018.5  290.22  5021.2  289.72  5024.5  290.22    5028  292.89  5035.8  293.42
  5099.3  294.68  5169.9  297.15  5206.3  297.78  5255.8  299.78  5262.3  301.01
  5270.1  300.59  5279.7  301.35  5333.9  302.68  5354.7  304.28  5390.5  306.07
#Mann= 8 ,-1 , 0
    4350     .05       0  4706.6      .1       0  4897.5     .16       0
  5018.5     .07       0  5024.5     .16       0  5099.3      .1       0
  5279.7     .05       0  5354.7      .1       0
Bank Sta=5018.5,5024.5
XS Rating Curve= 0 ,0
Exp/Cntr=0.3,0.1

Type RM Length L Ch R = 1 ,8025    ,300,300,300
BEGIN DESCRIPTION:
Mapping XS 3876df7a
END DESCRIPTION:
XS GIS Cut Line= 3
      2235242.03     13200697.32       2235488.6     13200669.53
       2235963.5      13200114.9
#Sta/Elev= 30
  4559.1  298.56  4635.3  297.18  4725.8  296.82  4766.1  295.51  4872.5  294.95
  4881.6   294.3  4901.1  294.71  4921.9     294  4950.5  291.81  4964.7  291.68
  4971.3  290.29  4990.3  289.44    4993  288.94  4996.3  289.44  5007.5  291.41
  5049.3     292  5104.5  291.79  5182.7  292.86  5219.4  293.35  5262.2  295.18
  5282.7   295.1  5311.6  296.77  5319.3     298  5325.9  297.32    5390  299.83
  5403.8  299.59  5468.6  302.26  5489.4  303.87  5510.3  303.49  5537.4  304.44
#Mann= 7 ,-1 , 0
  4559.1     .05       0  4881.6     .16       0  4990.3     .07       0
  4996.3     .16       0  5104.5     .16       0  5182.7      .1       0
  5282.7     .05       0
Bank Sta=4990.3,4996.3
XS Rating Curve= 0 ,0
Exp/Cntr=0.3,0.1

Type RM Length L Ch R = 1 ,7725    ,243,243,243
BEGIN DESCRIPTION:
Mapping XS 5e9835c1
END DESCRIPTION:
XS GIS Cut Line= 3
      2235391.39     13201044.52      2235679.57     13200891.76
      2236141.39     13200266.73
#Sta/Elev= 30
  4431.5   299.7  4545.1  298.19  4687.7  294.63  4709.7  294.72  4744.3  293.09
  4845.8  292.12  4881.3  291.16  4916.8  291.71  4975.1  291.48  4987.8  289.59
  5024.9  289.44  5060.9  289.92  5074.6  289.01    5111  289.94  5161.1  290.01
    5182  290.81  5196.6  289.93  5238.3  290.53  5273.8  291.63  5296.8  293.13
  5310.8  292.42  5346.9  294.02  5353.1  293.79  5367.8  294.86  5403.3  295.28
  5432.5  296.79  5474.2   296.6  5497.3     298  5503.5   297.4  5534.8  298.41
#Mann= 4 ,-1 , 0
  4431.5     .16       0  5034.9     .07       0  5040.9     .16       0
  5353.1     .05       0
#XS Ineff= 2 ,-1
  4431.5 4916.14  291.69 5180.24 5279.84  290.85
Permanent Ineff=
       F       F
Bank Sta=4987.8,5024.9
XS Rating Curve= 0 ,0
Exp/Cntr=0.3,0.1

Type RM Length L Ch R = 1 ,7482    ,382,382,382
BEGIN DESCRIPTION:
UNT 047 IN LACR 15.0
END DESCRIPTION:
XS GIS Cut Line= 4
      2235478.18     13201113.98      2235877.48     13200926.48
      2236297.62     13200589.67      2236370.56      13200443.8
#Sta/Elev= 30
  4353.5  299.36  4375.1  298.65  4381.3  298.96  4478.1  297.46  4546.5   294.7
  4597.7  293.65  4614.9  293.48  4620.5   293.9  4660.6  292.09  4711.7  291.29
  4801.7  289.53  4836.9  289.43  4851.3  289.98  4979.3  288.27  4993.7  287.94
  5008.1  288.24  5036.9   288.7  5043.3  287.94  5078.6  289.22    5093  288.65
  5150.6  288.08  5214.6  288.39  5256.3  289.41  5270.6  290.87    5285  289.97
    5293  290.68  5415.8  293.25  5432.6  292.64  5448.1  293.22  5496.2  293.36
#Mann= 5 ,-1 , 0
  4353.5     .05       0  4711.7     .16       0  5048.3     .07       0
  5054.3     .16       0  5496.2      .1       0
#XS Ineff= 2 ,-1
 4681.42  4850.2  289.98 5270.75 5326.09  290.94
Permanent Ineff=
       F       F
Bank Sta=4979.3,5008.1
XS Rating Curve= 0 ,0
Exp/Cntr=0.3,0.1

Type RM Length L Ch R = 1 ,7100    ,395,395,395
BEGIN DESCRIPTION:
UNT 047 IN LACR 14.0
END DESCRIPTION:
XS GIS Cut Line= 3
      2235840.59     13201529.35      2236288.51     13200961.63
      2236486.43     13200623.08
#Sta/Elev= 30
  4480.5  303.34  4501.4  303.05  4515.9  301.77  4522.2  302.09  4530.3  301.35
  4559.2  300.72  4623.3  297.39  4693.8  295.35  4708.3  294.26  4764.3  292.45
  4842.9  287.88  4950.4  286.01  4953.7  285.94  4956.5  285.44  4959.7  285.94
  4993.2  286.11  5078.6  288.12  5113.9  287.36  5163.6  288.05  5256.5  288.01
  5272.2  288.56  5287.9  288.04  5336.6  288.57  5395.3  289.62    5411  290.45
  5426.7  289.89  5469.7  290.88  5521.9  293.56  5534.2   292.7  5595.8  295.23
#Mann= 3 ,-1 , 0
  4480.5     .16       0  4950.4     .07       0  4959.7     .16       0
#XS Ineff= 2 ,-1
 4819.76 4877.87  287.63 5078.26 5315.42  288.15
Permanent Ineff=
       F       F
Bank Sta=4953.7,4959.7
XS Rating Curve= 0 ,0
Exp/Cntr=0.3,0.1

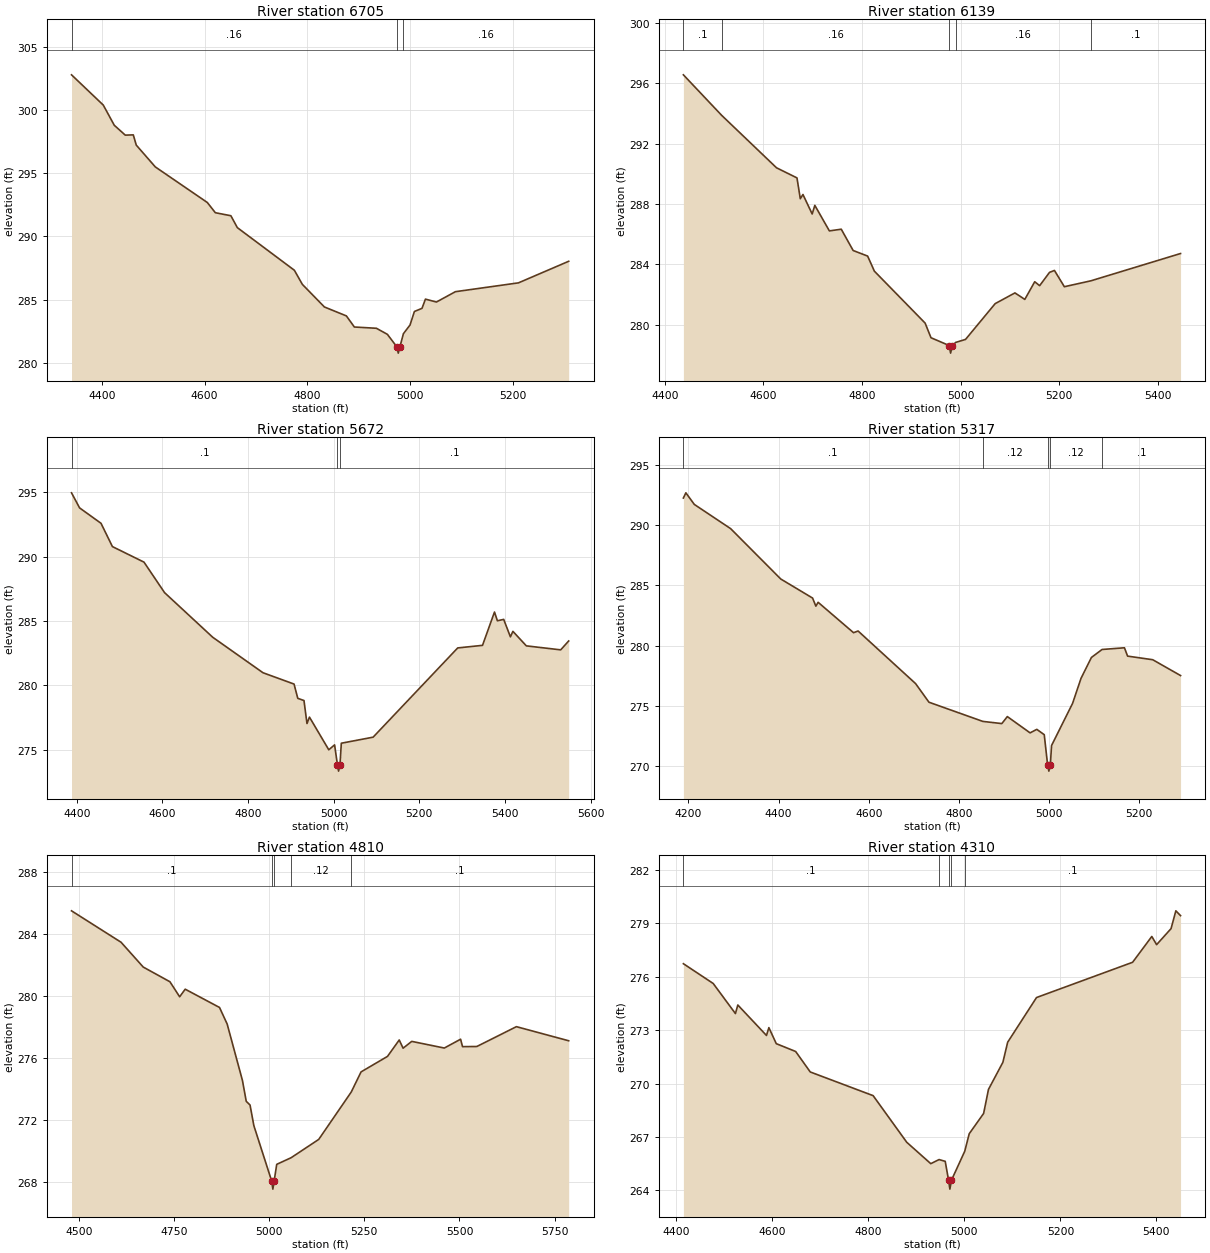
Type RM Length L Ch R = 1 ,6705    ,566,566,566
BEGIN DESCRIPTION:
UNT 047 IN LACR 13.0
END DESCRIPTION:
XS GIS Cut Line= 2
      2236210.36     13201763.76      2236704.72     13200931.16
#Sta/Elev= 30
  4340.7  302.81  4402.6  300.41    4424  298.81  4445.4  298.03    4461  298.05
  4466.8  297.24  4503.9  295.51  4605.2  292.69  4620.8  291.88  4651.1  291.64
  4663.6   290.7  4774.7  287.32  4790.3   286.2  4833.2  284.41    4876   283.7
  4891.6  282.82  4934.5  282.72  4955.9  282.24  4974.3  281.25  4977.1  280.75
  4980.3  281.25  4987.1  282.29    5000  282.98  5008.5  284.05  5023.3   284.3
    5030  285.03  5051.4   284.8  5088.4  285.62  5211.2  286.32    5309  288.03
#Mann= 3 ,-1 , 0
  4340.7     .16       0  4974.3     .07       0  4987.1     .16       0
Bank Sta=4974.3,4980.3
XS Rating Curve= 0 ,0
Exp/Cntr=0.3,0.1

Type RM Length L Ch R = 1 ,6139    ,467,467,467
BEGIN DESCRIPTION:
UNT 047 IN LACR 12.0
END DESCRIPTION:
XS GIS Cut Line= 3
      2236903.09     13201930.39      2237048.93     13201571.01
      2237012.49     13200951.52
#Sta/Elev= 30
  4437.7  296.56  4515.2  293.88  4626.6   290.4  4668.1  289.73  4674.8  288.35
  4680.2  288.63  4698.9  287.34  4704.3  287.91  4733.8  286.22  4757.9  286.33
    4782  284.92  4811.4  284.55  4825.1  283.55    4928  280.11  4939.9  279.14
    4977  278.62  4979.7  278.12    4983  278.62    4990  278.83    5010  279.03
  5070.1   281.4  5110.2  282.11  5130.2  281.68  5150.3  282.85  5160.3  282.59
  5180.3  283.47  5190.3   283.6  5210.4  282.52  5264.1  282.91  5446.1  284.72
#Mann= 5 ,-1 , 0
  4437.7      .1       0  4515.2     .16       0    4977     .07       0
    4990     .16       0  5264.1      .1       0
Bank Sta=4977,4983
XS Rating Curve= 0 ,0
Exp/Cntr=0.3,0.1

Type RM Length L Ch R = 1 ,5672    ,355,355,355
BEGIN DESCRIPTION:
UNT 047 IN LACR 11.0
END DESCRIPTION:
XS GIS Cut Line= 3
      2237590.59     13201935.57      2237554.13     13201487.68
      2237194.77      13200873.1
#Sta/Elev= 30
  4387.5  294.97  4406.3   293.8  4456.4   292.6    4483  290.79  4556.8  289.58
  4604.8  287.21  4717.3  283.74  4834.8  280.98  4907.3   280.1    4916  278.99
  4930.5  278.82  4937.5  277.03  4943.3  277.53  4988.4  274.99    5002  275.37
  5008.6  273.83  5011.3  273.33  5014.6  273.83  5017.7   275.5    5092  275.97
  5289.6  282.91  5347.5  283.11  5375.5   285.7  5382.3  285.02    5397  285.13
  5412.7  283.77  5418.5   284.2  5449.9  283.07  5530.1  282.76  5548.8  283.45
#Mann= 3 ,-1 , 0
  4387.5      .1       0  5008.6     .07       0  5014.6      .1       0
Bank Sta=5008.6,5014.6
XS Rating Curve= 0 ,0
Exp/Cntr=0.3,0.1

Type RM Length L Ch R = 1 ,5317    ,507,507,507
BEGIN DESCRIPTION:
UNT 047 IN LACR 10.0
END DESCRIPTION:
XS GIS Cut Line= 3
      2237762.46     13201940.82      2237835.38     13201409.55
      2237668.71     13200867.86
#Sta/Elev= 30
  4188.9  292.23  4194.4  292.66  4213.1   291.7  4293.8  289.69  4404.9  285.52
  4475.5  283.94  4482.8  283.27  4487.8  283.59  4566.4  281.07  4576.5  281.21
  4704.1  276.85  4733.7  275.31  4853.2  273.72  4895.4  273.54  4907.6  274.12
  4958.1  272.77    4973  273.06  4989.5  272.62    4997   270.1  4999.7   269.6
    5003   270.1  5005.7  271.72  5052.3  275.21  5071.1  277.29  5094.2  279.02
  5117.8  279.68  5167.4  279.82  5174.4  279.13  5230.2  278.83  5291.9  277.52
#Mann= 5 ,-1 , 0
  4188.9      .1       0  4853.2     .12       0    4997     .07       0
    5003     .12       0  5117.8      .1       0
Bank Sta=4997,5003
XS Rating Curve= 0 ,0
Exp/Cntr=0.3,0.1

Type RM Length L Ch R = 1 ,4810    ,500,500,500
BEGIN DESCRIPTION:
UNT 047 IN LACR 9.0
END DESCRIPTION:
XS GIS Cut Line= 3
       2238220.8     13201914.81      2238168.72     13201097.05
      2238059.35     13200623.12
#Sta/Elev= 30
    4481   285.5  4611.2  283.47  4669.3  281.87  4739.5  280.92    4765  279.95
  4779.6  280.44  4869.7  279.26  4889.8  278.19  4929.9  274.55  4939.9   273.2
  4949.9  272.96  4959.9  271.63    5007  268.03  5009.8  267.53    5013  268.03
    5020  269.13  5057.9  269.56  5130.3  270.74  5215.7   273.8  5241.5   275.1
  5310.9   276.1  5341.7  277.16  5351.9  276.63  5374.6  277.07  5460.1  276.64
  5502.9  277.21    5508  276.73  5545.6  276.74  5649.5  278.02  5786.8  277.11
#Mann= 5 ,-1 , 0
    4481      .1       0    5007     .07       0    5013      .1       0
  5057.9     .12       0  5215.7      .1       0
Bank Sta=5007,5013
XS Rating Curve= 0 ,0
Exp/Cntr=0.3,0.1

Type RM Length L Ch R = 1 ,4310    ,335,335,335
BEGIN DESCRIPTION:
UNT 047 IN LACR 8.0
END DESCRIPTION:
XS GIS Cut Line= 3
      2238496.84      13201628.3      2238548.93     13201274.13
      2238517.68     13200597.03
#Sta/Elev= 30
  4414.5  276.73  4476.6  275.62  4522.9  273.93  4527.9  274.41  4587.6   272.7
  4592.6  273.14    4608  272.24  4648.4   271.8  4678.8  270.65  4809.8  269.32
  4879.9   266.7  4929.9   265.5  4947.2  265.73    4960  265.63    4967  264.57
  4969.7  264.07    4973  264.57  5000.7   266.2    5010  267.18    5040  268.32
  5050.1  269.67  5080.1  271.19  5090.1  272.32  5150.2  274.83  5350.4  276.81
  5390.4  278.26  5400.4   277.8  5430.5   278.7  5440.5   279.7  5450.3  279.43
#Mann= 5 ,-1 , 0
  4414.5      .1       0  4947.2     .12       0    4967     .07       0
    4973     .12       0  5000.7      .1       0
Bank Sta=4967,4973
XS Rating Curve= 0 ,0
Exp/Cntr=0.3,0.1

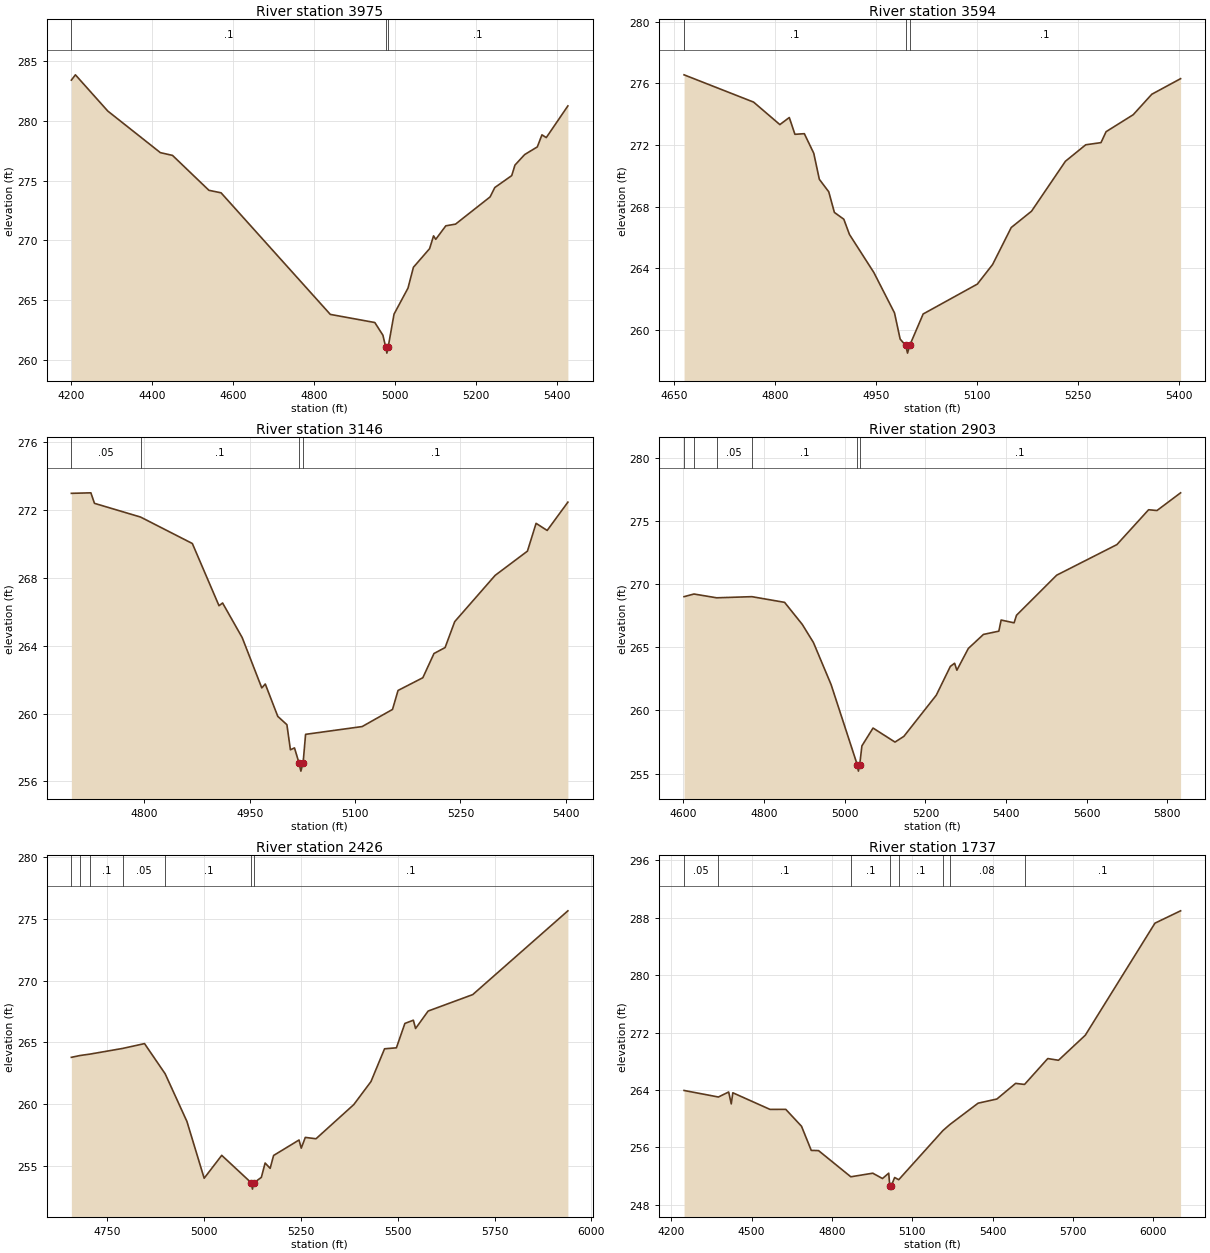
Type RM Length L Ch R = 1 ,3975    ,381,381,381
BEGIN DESCRIPTION:
UNT 047 IN LACR 7.0
END DESCRIPTION:
XS GIS Cut Line= 3
      2238837.72     13201946.85      2238837.72     13201146.85
      2238987.72     13200746.85
#Sta/Elev= 30
    4200   283.4    4210  283.84    4290  280.81    4420  277.33    4450   277.1
    4540  274.18    4570  273.97    4840   263.8    4950  263.12    4970  262.06
    4977  261.06  4979.8  260.56    4983  261.06  4997.5  263.82    5032     266
  5045.4  267.74  5085.4   269.3  5095.2  270.37  5100.6  270.08  5125.5  271.21
  5149.5  271.35    5235  273.63  5246.5  274.41  5288.4  275.41  5296.4  276.29
  5320.4  277.17  5351.6  277.81  5363.1  278.82  5373.8  278.59  5427.2  281.24
#Mann= 3 ,-1 , 0
    4200      .1       0    4977     .07       0    4983      .1       0
Bank Sta=4977,4983
XS Rating Curve= 0 ,0
Exp/Cntr=0.3,0.1

Type RM Length L Ch R = 1 ,3594    ,448,448,448
BEGIN DESCRIPTION:
UNT 047 IN LACR 6.0
END DESCRIPTION:
XS GIS Cut Line= 3
      2238987.72     13201696.85      2239137.72     13201396.85
      2239187.72     13200996.87
#Sta/Elev= 30
  4664.6  276.55    4768  274.78  4807.1  273.32  4821.1  273.78  4829.5  272.69
  4843.5  272.73  4857.5  271.46  4865.8  269.77  4879.8  268.96  4888.2  267.62
  4902.2  267.18  4910.6  266.19  4946.9  263.72  4977.6   261.1    4986   259.4
  4994.2  258.99    4997  258.49  5000.2  258.99  5020.2  261.03  5100.8  262.97
  5123.5  264.24  5151.2  266.64  5181.4   267.7  5231.8  270.94    5262  272.01
  5284.7  272.15  5292.3  272.86  5332.6  273.96  5360.3  275.29  5403.1   276.3
#Mann= 3 ,-1 , 0
  4664.6      .1       0  4994.2     .07       0  5000.2      .1       0
Bank Sta=4994.2,5000.2
XS Rating Curve= 0 ,0
Exp/Cntr=0.3,0.1

Type RM Length L Ch R = 1 ,3146    ,243,243,243
BEGIN DESCRIPTION:
UNT 047 IN LACR 5.0
END DESCRIPTION:
XS GIS Cut Line= 3
      2239537.73     13201746.82      2239587.72     13201446.85
      2239387.73     13201096.87
#Sta/Elev= 30
  4695.9     273  4723.7  273.03  4728.8  272.41  4794.5   271.6  4868.2  270.04
  4906.2  266.37  4911.3  266.53  4939.2  264.49  4967.1  261.52  4972.1  261.75
  4989.9  259.84  5002.9  259.35  5007.9  257.87  5013.7  257.98    5020  257.11
  5022.8  256.61    5026  257.11  5029.5  258.78  5110.1  259.24  5153.3  260.25
  5161.2  261.37  5196.5  262.12  5212.4  263.55  5228.2   263.9  5241.9  265.43
  5299.5  268.16  5345.5  269.59  5357.8  271.23  5373.6  270.81  5403.1  272.48
#Mann= 4 ,-1 , 0
  4695.9     .05       0  4794.5      .1       0    5020     .07       0
    5026      .1       0
Bank Sta=5020,5026
XS Rating Curve= 0 ,0
Exp/Cntr=0.3,0.1

Type RM Length L Ch R = 1 ,2903    ,477,477,477
BEGIN DESCRIPTION:
Mapping XS 11c7f288
END DESCRIPTION:
XS GIS Cut Line= 3
      2240012.44     13201748.05      2239627.05     13201029.34
      2239298.93     13200774.14
#Sta/Elev= 30
  4601.5  269.01    4626  269.22  4682.3  268.92  4769.7  269.01  4850.8  268.56
  4894.7  266.81  4922.3  265.38  4966.1  262.05    5031   255.7  5033.8   255.2
    5037   255.7  5042.5   257.2  5070.1  258.61  5124.5   257.5  5146.5  257.95
  5226.9  261.21  5261.8  263.49  5272.3  263.74    5278  263.19  5306.4  264.91
  5343.8  266.02    5382  266.28  5387.7  267.16  5419.8  266.94  5425.9  267.54
  5525.4  270.71  5674.7  273.13  5753.4  275.89  5774.2  275.83  5832.7  277.23
#Mann= 6 ,-1 , 0
  4601.5     .05       0    4626      .1       0  4682.3     .05       0
  4769.7      .1       0    5031     .07       0    5037      .1       0
Bank Sta=5031,5037
XS Rating Curve= 0 ,0
Exp/Cntr=0.3,0.1

Type RM Length L Ch R = 1 ,2426    ,689,689,689
BEGIN DESCRIPTION:
UNT 047 IN LACR 4.0
END DESCRIPTION:
XS GIS Cut Line= 2
      2240439.54     13201201.21      2239311.03     13200592.75
#Sta/Elev= 30
  4657.1   263.8  4679.8  263.95    4705  264.06  4789.5  264.52    4846  264.91
  4899.3  262.47  4955.5  258.62    5000  254.03  5045.4  255.88    5122  253.65
  5124.7  253.15    5128  253.65  5147.7   254.1  5157.4  255.26  5170.4  254.83
  5179.3  255.87    5245  257.12  5250.7  256.46  5261.2  257.33  5288.8  257.22
  5386.3  259.98  5430.7  261.84  5465.8  264.49  5496.4  264.57  5518.3  266.54
  5540.2   266.8  5545.9  266.13  5578.3  267.54  5693.5  268.87  5939.2  275.64
#Mann= 7 ,-1 , 0
  4657.1      .1       0  4679.8     .05       0    4705      .1       0
  4789.5     .05       0  4899.3      .1       0    5122     .07       0
    5128      .1       0
Bank Sta=5122,5128
XS Rating Curve= 0 ,0
Exp/Cntr=0.3,0.1

Type RM Length L Ch R = 1 ,1737    ,318,318,318
BEGIN DESCRIPTION:
UNT 047 IN LACR 3.0
END DESCRIPTION:
XS GIS Cut Line= 4
       2240533.3     13200940.79      2240330.18     13200591.84
      2239798.93     13200248.09        2238982.     13200232.48
#Sta/Elev= 30
  4247.9  263.94  4376.1  263.03  4414.4  263.73  4424.1  262.07  4429.9  263.62
  4568.9   261.3  4627.6  261.31  4686.4  258.95  4722.7  255.59  4749.9  255.56
  4870.4  251.91  4952.4  252.41  4988.5  251.67  5011.9  252.41  5015.8  250.69
  5018.6  250.19  5021.8  250.69    5034  251.81  5049.2   251.5  5214.5  258.36
    5240  259.19  5345.6  262.17  5415.7  262.75  5485.7  264.93  5518.9  264.78
  5605.7  268.39  5645.7  268.15  5745.7  271.64  6005.8  287.26  6101.5  288.98
#Mann= 8 ,-1 , 0
  4247.9     .05       0  4376.1      .1       0  4870.4      .1       0
  5015.8     .04       0  5049.2      .1       0  5214.5      .1       0
    5240     .08       0  5518.9      .1       0
Bank Sta=5015.8,5021.8
XS Rating Curve= 0 ,0
Exp/Cntr=0.3,0.1

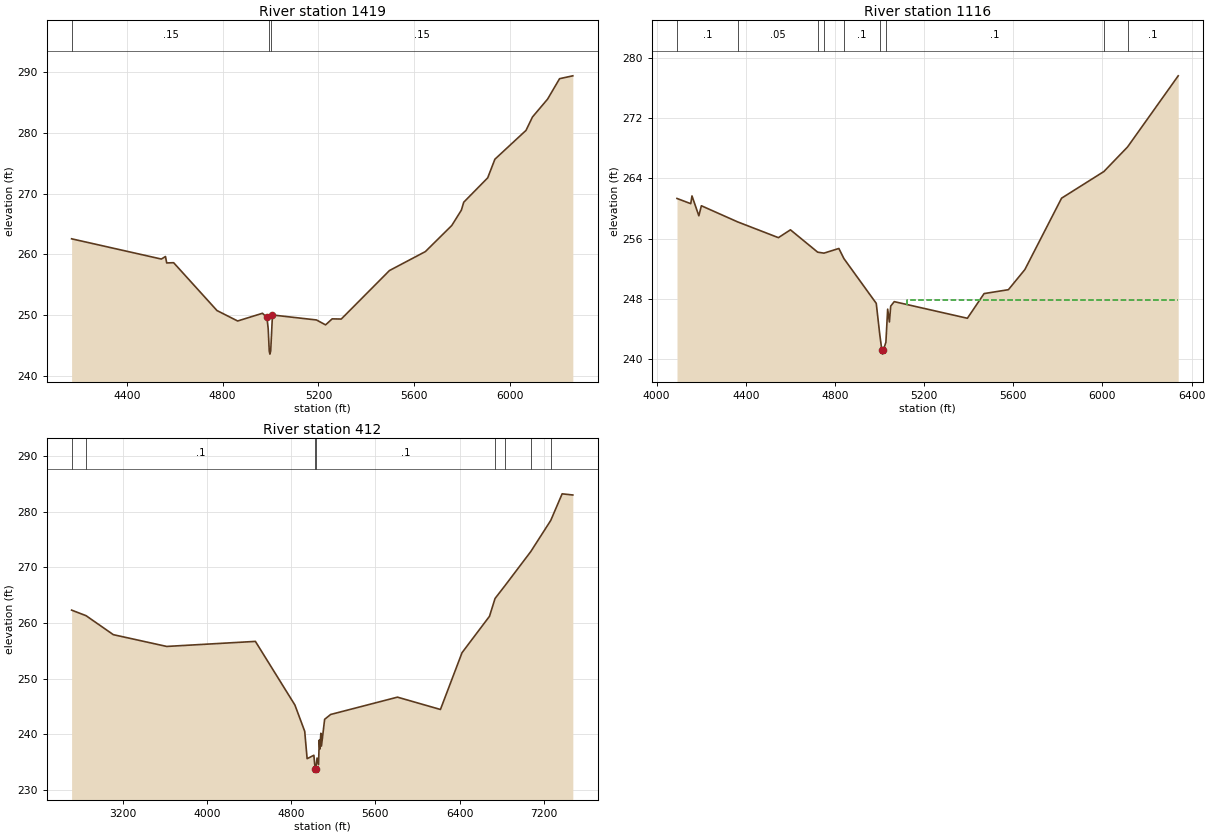
Type RM Length L Ch R = 1 ,1419    ,303,303,303
BEGIN DESCRIPTION:
Mapping XS 648f8864
END DESCRIPTION:
XS GIS Cut Line= 5
     2240589.261    13200747.403     2240464.261    13200302.959
     2240235.095     13200132.82     2239748.984    13199983.514
     2238912.178    13199993.931
#Sta/Elev= 30
  4169.8  262.57  4544.4  259.24  4561.7  259.66  4566.8   258.6  4595.7  258.64
  4776.7  250.77  4862.9  249.05  4966.5  250.32  4985.3  249.64  4990.5  247.76
  4994.9   244.1  4997.6   243.6  5000.9   244.1  5008.3  250.04  5192.1  249.22
    5230  248.41  5257.5   249.4  5295.5  249.37  5496.7  257.35  5646.7  260.47
  5756.8  264.76  5796.8  267.28  5806.8  268.59  5906.8   272.6  5936.8  275.66
  6066.8  280.41  6093.7  282.61  6156.8  285.55  6206.8  288.91  6262.1  289.38
#Mann= 3 ,-1 , 0
  4169.8     .15       0  4994.9     .05       0  5000.9     .15       0
Bank Sta=4985.3,5008.3
XS Rating Curve= 0 ,0
Exp/Cntr=0.3,0.1

Type RM Length L Ch R = 1 ,1116    ,704,704,704
BEGIN DESCRIPTION:
UNT 047 IN LACR 2.0
END DESCRIPTION:
XS GIS Cut Line= 4
      2240616.64      13200602.3       2240470.8     13199977.26
       2239533.3      13199440.8      2239017.69     13199544.97
#Sta/Elev= 30
  4091.8  261.33  4153.5  260.64    4159  261.67  4189.8  259.03  4201.2  260.36
  4363.4  258.22  4546.6  256.12  4600.6  257.16  4722.7  254.19  4750.8  254.06
  4817.8  254.68  4840.3  253.34  4985.5  247.38  5001.3  243.23  5010.7  241.13
  5013.4  240.63  5016.7  241.13  5028.7   242.2  5036.7  246.61  5044.5  244.91
  5050.3  247.01  5066.1  247.61  5394.2   245.4  5469.1  248.68  5578.2   249.2
  5651.9  251.87  5816.7  261.37  6006.3  264.91  6112.6  268.18  6339.8  277.64
#Mann= 9 ,-1 , 0
  4091.8      .1       0  4363.4     .05       0  4722.7      .1       0
  4750.8     .05       0  4840.3      .1       0  5001.3     .07       0
  5028.7      .1       0  6006.3     .08       0  6112.6      .1       0
#XS Ineff= 2 , 0
                         5123.58          247.81
Permanent Ineff=
       F       F
Bank Sta=5010.7,5016.7
XS Rating Curve= 0 ,0
Exp/Cntr=0.3,0.1

Type RM Length L Ch R = 1 ,412     ,0,0,0
BEGIN DESCRIPTION:
UNT 047 IN LACR 1.0
END DESCRIPTION:
XS GIS Cut Line= 5
      2241591.99     13201927.54      2241344.59     13200443.13
      2240758.66     13199570.74      2239560.74      13199297.3
      2238597.21     13199427.51
#Sta/Elev= 30
  2716.6  262.32  2853.7  261.32  3112.7   257.9  3619.5  255.78    4461  256.69
    4836  245.23    4929   240.5  4951.8  235.57    5016  236.19    5028  233.65
  5030.8  233.15    5034  233.65    5046  235.69  5060.2   234.5    5067  238.93
  5073.1   237.3    5082  240.15    5088  237.84    5118  242.66    5175  243.53
  5809.2  246.65    6217  244.43  6422.1  254.66  6682.6  261.21  6735.4  264.42
  6828.6   266.7  7074.3  272.86  7264.3  278.48    7372  283.26  7473.4  283.05
#Mann= 8 ,-1 , 0
  2716.6     .05       0  2853.7      .1       0    5028     .07       0
    5034      .1       0  6735.4     .08       0  6828.6      .1       0
  7074.3     .05       0  7264.3      .1       0
Bank Sta=5028,5034
XS Rating Curve= 0 ,0
Exp/Cntr=0.3,0.1
Stream Node=UNT 047 IN LACR ,Reach-1         , 0 , 0 ,Upstream end
Stream Node=UNT 047 IN LACR ,Reach-1         , 0 , 1 ,Downstream end

Chan Stop Cuts=-1
Use User Specified Reach Order=0
Composite Channel Slope=5