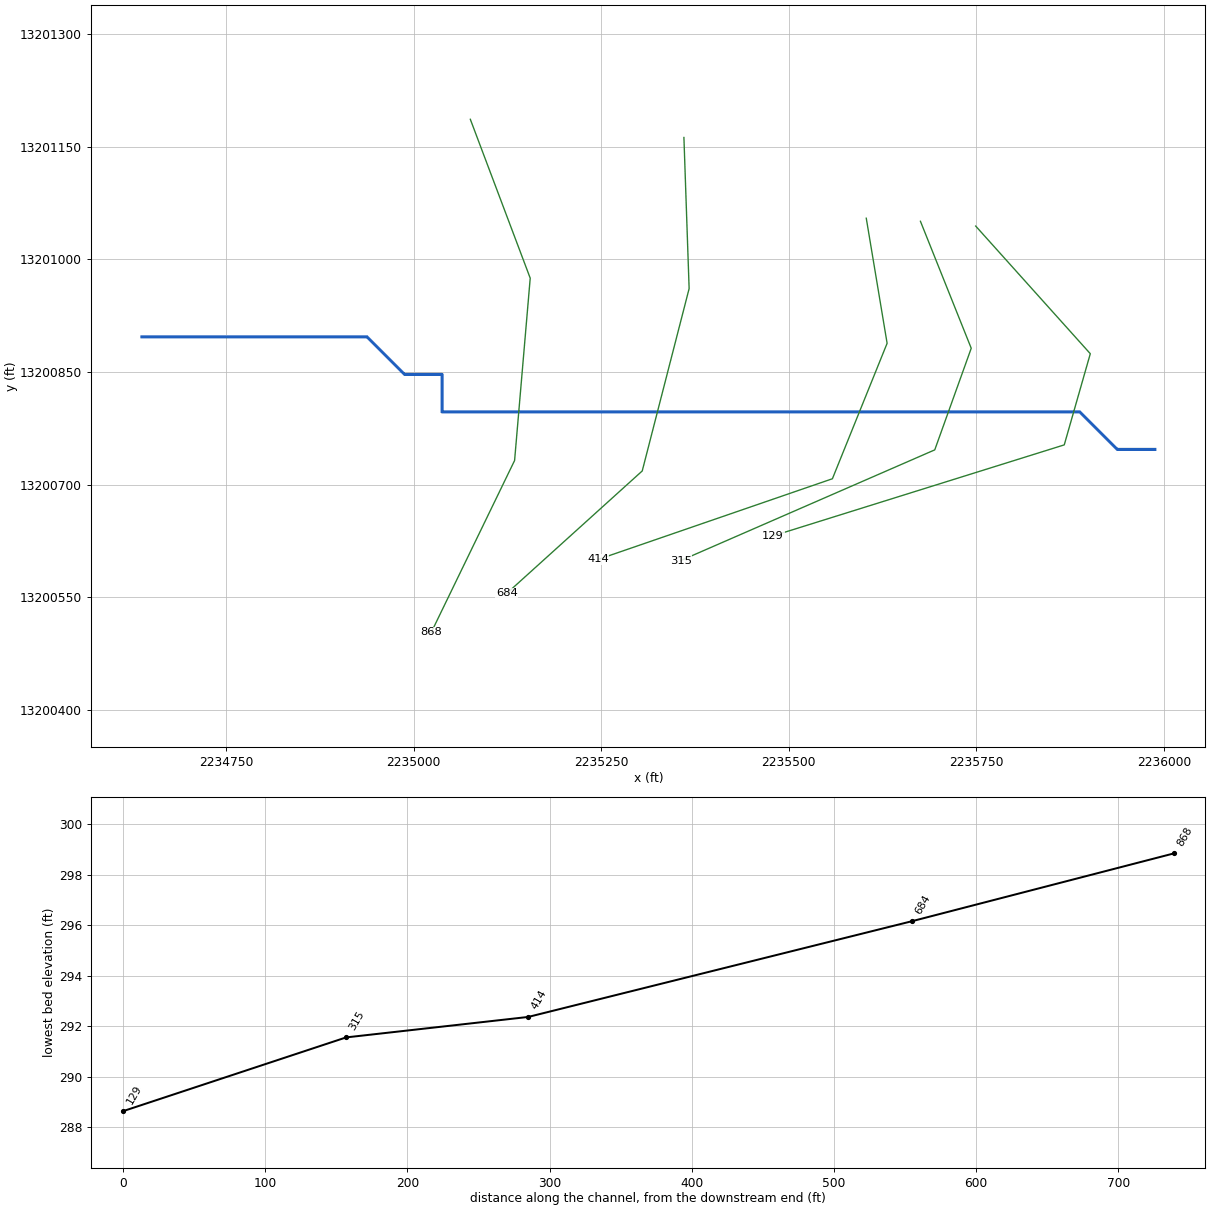
--- UNT 048 IN LACR.prj (project) ---

Proj Title=UNT 048 IN LACR Base Level Engineering
Current Plan=p01
Default Exp/Contr=0.3,0.1
English Units
Geom File=g01
Flow File=f01
Plan File=p01
Y Axis Title=Elevation
X Axis Title(PF)=Main Channel Distance
X Axis Title(XS)=Station
BEGIN DESCRIPTION:
UNT 048 IN LACR
END DESCRIPTION:
DSS File=dss
DSS Export Rating Curves= 0
DSS Export Rating Curve Sorted= 0
DSS Export Volume Flow Curves= 0
DXF OffsetX= 0
DXF OffsetY= 0
DXF ScaleX= 1
DXF ScaleY= 10

--- UNT 048 IN LACR.p01 (plan) ---

Plan Title=Multiple Run
Program Version=4.10
Short Identifier=Multiple Run
Geom File=g01
Flow File=f01
Subcritical Flow
K Sum by GR= 0
Std Step Tol= 0.01
Critical Tol= 0.01
Num of Std Step Trials= 20
Max Error Tol= 0.3
Flow Tol Ratio= 0.001
Split Flow NTrial= 30
Split Flow Tol= 0.02
Split Flow Ratio= 0.02
Log Output Level= 0
Friction Slope Method= 1
Unsteady Friction Slope Method= 2
Unsteady Bridges Friction Slope Method= 1
Parabolic Critical Depth
Global Vel Dist= 1 , 1 , 1
Global Log Level= 0
CheckData=True
Encroach Param=-1 ,0,0, 0
BEGIN DESCRIPTION:
Multiple Run
END DESCRIPTION:
Computation Interval=1HOUR
Output Interval=1HOUR
Run HTab= 0
Run UNet= 0
Run PostProcess= 0
Run WQNet= 0
UNET Theta= 1
UNET Theta Warmup= 1
UNET ZTol= 0.02
UNET ZSATol= 0.05
UNET MxIter= 20
UNET MaxInSteps= 0
UNET DtIC= 0
UNET DtMin= 0
UNET MaxCRTS= 20
UNET WFStab= 2
UNET SFStab= 1
UNET WFX= 1
UNET SFX= 1
UNET DSS MLevel= 4
UNET DZMax Abort= 100
UNET Convert EG Bridges= 0
UNET Use Existing IB Tables=-1
UNET Froude Reduction=False
UNET Froude Limit= 1
UNET Froude Power= 10
UNET Time Slicing=0,0, 5
UNET Junction Losses=0
Instantaneous Interval=1HOUR
DSS File=dss
Write IC File= 0
Write IC File at Sim End=0
Echo Input=False
Echo Parameters=False
Echo Output=False
Write Detailed= 0
WQ AD Non Conservative
WQ ULTIMATE=-1
WQ Max Comp Step=1HOUR
WQ Output Interval=15MIN
WQ Output Selected Increments= 0
WQ Output face flow=0
WQ Output face velocity=0
WQ Output face area=0
WQ Output face dispersion=0
WQ Output cell volume=0
WQ Output cell surface area=0
WQ Output cell continuity=0
WQ Output cumulative cell continuity=0
WQ Output face conc=0
WQ Output face dconc_dx=0
WQ Output face courant=0
WQ Output face peclet=0
WQ Output face adv mass=0
WQ Output face disp mass=0
WQ Output cell mass=0
WQ Output cell source sink temp=0
WQ Output cell source sink nsm=0
WQ Output MaxMinRange=-1
WQ Daily Max Min Mean=-1
WQ Daily Range=0
WQ Daily Time=0
WQ Create Restart=0
WQ Fixed Restart=0
WQ System Summary=0
WQ Use Fixed Temperature=0
Sorting and Armoring Iterations= 10
XS Update Threshold= 0.02
Hydraulics Update Threshold= 0.02
Energy Slope Method= 1
Volume Change Method= 0
XS Weighting Method= 0
Number of US Weighted Cross Sections= 1
Number of DS Weighted Cross Sections= 1
Upstream XS Weight=0.25
Main XS Weight=0.5
Downstream XS Weight=0.25
Number of DS XS's Weighted with US Boundary= 1
Upstream Boundary Weight= 1
Weight of XSs Associated with US Boundary= 0
Number of US XS's Weighted with DS Boundary= 1
Downstream Boundary Weight= 0.5
Weight of XSs Associated with DS Boundary= 0.5
Sediment Output Level= 4
Mass or Volume Output= 0
Output Increment Type= 1
Profile and TS Output Increment= 10
XS Output Flag= 0
XS Output Increment= 10
Disregard all LS=0
Disregard all Conn=0
Disregard all Breaches=0
Disregard all Pumps=0

--- UNT 048 IN LACR.f01 (steady flow) ---

Flow Title=Multiple
Program Version=4.10
Number of Profiles= 7
Profile Names=10-year,25-year,50-year,1pct_min,100-year,1pct_plu,500-year
River Rch & RM=UNT 048 IN LACR,Reach-1         ,868
      56      71      83      72      97     131     133
Boundary for River Rch & Prof#=UNT 048 IN LACR,Reach-1         , 1
Up Type= 0
Dn Type= 3
Dn Slope=0.01
Boundary for River Rch & Prof#=UNT 048 IN LACR,Reach-1         , 2
Up Type= 0
Dn Type= 3
Dn Slope=0.01
Boundary for River Rch & Prof#=UNT 048 IN LACR,Reach-1         , 3
Up Type= 0
Dn Type= 3
Dn Slope=0.01
Boundary for River Rch & Prof#=UNT 048 IN LACR,Reach-1         , 4
Up Type= 0
Dn Type= 3
Dn Slope=0.01
Boundary for River Rch & Prof#=UNT 048 IN LACR,Reach-1         , 5
Up Type= 0
Dn Type= 3
Dn Slope=0.01
Boundary for River Rch & Prof#=UNT 048 IN LACR,Reach-1         , 6
Up Type= 0
Dn Type= 3
Dn Slope=0.01
Boundary for River Rch & Prof#=UNT 048 IN LACR,Reach-1         , 7
Up Type= 0
Dn Type= 3
Dn Slope=0.01
DSS Import GetInterval= 0
DSS Import GetPeak= 0
DSS Import FillOption= 0

--- UNT 048 IN LACR.g01 (geometry) ---

Geom Title=Existing Conditions
Program Version=4.10

River Reach=UNT 048 IN LACR ,Reach-1
Reach XY= 29
      2234637.72     13200896.85      2234687.72     13200896.85
      2234737.72     13200896.85      2234787.72     13200896.85
      2234837.72     13200896.85      2234887.72     13200896.85
      2234937.72     13200896.85      2234987.72     13200846.86
      2235037.72     13200846.86      2235037.72     13200796.85
      2235087.72     13200796.85      2235137.72     13200796.85
      2235187.72     13200796.85      2235237.72     13200796.85
      2235287.72     13200796.85      2235337.72     13200796.85
      2235387.72     13200796.85      2235437.72     13200796.85
      2235487.72     13200796.85      2235537.72     13200796.85
      2235587.72     13200796.85      2235637.72     13200796.85
      2235687.72     13200796.85      2235737.72     13200796.85
      2235787.72     13200796.85      2235837.72     13200796.85
      2235887.72     13200796.85      2235937.72     13200746.85
      2235987.72     13200746.85

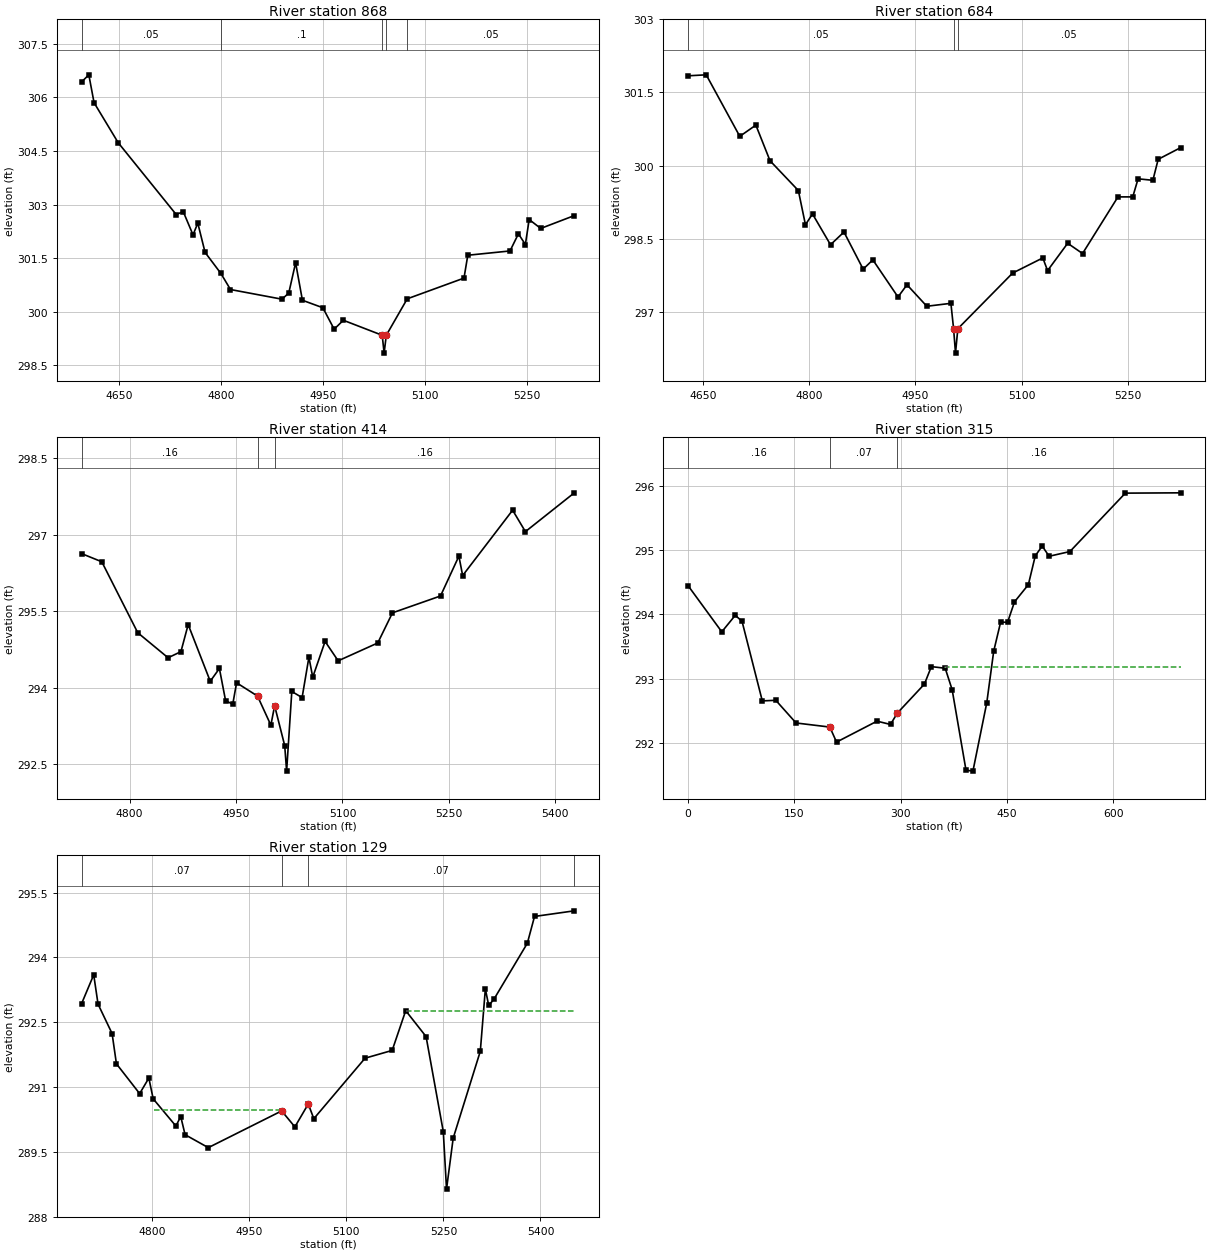
Type RM Length L Ch R = 1 ,868     ,184,184,184
BEGIN DESCRIPTION:
UNT 048 IN LACR 17.0
END DESCRIPTION:
XS GIS Cut Line= 4
      2235075.42     13201186.85      2235155.26     13200975.09
      2235134.43     13200732.03      2235023.34      13200502.9
#Sta/Elev= 30
  4594.8  306.43  4605.5  306.63  4613.2  305.85  4648.7  304.73    4734  302.72
  4744.4   302.8  4758.8  302.15  4765.8  302.48  4776.5  301.66  4799.8  301.07
  4813.9  300.62  4889.6  300.35  4899.6  300.52  4909.7  301.37  4919.7  300.32
  4949.8  300.11  4966.4  299.51  4979.9  299.76  5037.1  299.34  5039.9  298.84
  5043.1  299.34  5073.9  300.36  5157.4  300.94    5163  301.58  5225.1   301.7
  5237.5  302.18  5247.7  301.88  5253.3  302.58  5270.3  302.33  5319.7  302.69
#Mann= 5 ,-1 , 0
  4594.8     .05       0  4799.8      .1       0  5037.1     .07       0
  5043.1      .1       0  5073.9     .05       0
Bank Sta=5037.1,5043.1
XS Rating Curve= 0 ,0
Exp/Cntr=0.3,0.1

Type RM Length L Ch R = 1 ,684     ,270,270,270
BEGIN DESCRIPTION:
Mapping XS 2fd4677b
END DESCRIPTION:
XS GIS Cut Line= 4
      2235360.12     13201162.59      2235367.07      13200961.2
      2235304.57     13200718.14      2235124.05     13200554.98
#Sta/Elev= 30
  4628.8  301.84  4654.5  301.86  4701.9   300.6  4724.6  300.83  4744.6   300.1
  4784.6  299.49  4794.6  298.79  4804.6  299.01    4830  298.38    4849  298.64
  4876.1  297.88  4889.8  298.07  4925.3  297.31    4938  297.56    4966  297.12
    5000  297.18  5003.8  296.66  5006.5  296.16  5009.8  296.66  5087.2   297.8
  5129.8  298.11  5136.5  297.85  5164.9  298.41  5185.9   298.2  5235.9  299.36
  5256.8  299.36  5264.3  299.73  5285.2   299.7  5292.7  300.13  5324.6  300.37
#Mann= 3 ,-1 , 0
  4628.8     .05       0  5003.8     .03       0  5009.8     .05       0
Bank Sta=5003.8,5009.8
XS Rating Curve= 0 ,0
Exp/Cntr=0.3,0.1

Type RM Length L Ch R = 1 ,414     ,128,128,128
BEGIN DESCRIPTION:
Mapping XS c8f7ad24
END DESCRIPTION:
XS GIS Cut Line= 4
      2235603.17     13201054.98      2235630.96     13200888.28
      2235558.04     13200707.73      2235245.58      13200600.1
#Sta/Elev= 30
  4732.4  296.63  4760.9  296.47  4811.6  295.08  4854.3  294.59  4872.4  294.71
  4882.6  295.24  4913.7  294.13  4926.6  294.38  4935.3  293.75  4945.4  293.68
  4950.8   294.1  4980.3  293.84  4999.1  293.27  5004.4  293.65  5018.6  292.87
  5021.3  292.37  5028.6  293.93  5043.1  293.81  5052.7   294.6  5058.1  294.21
  5075.5  294.91  5093.9  294.53  5149.7  294.88  5170.4  295.47  5238.1   295.8
    5264  296.58  5269.3   296.2  5339.7  297.48  5357.7  297.06  5426.6  297.82
#Mann= 3 , 0 , 0
  4732.4     .16       0  4980.3     .07       0  5004.4     .16       0
Bank Sta=4980.3,5004.4
XS Rating Curve= 0 ,0
Exp/Cntr=0.3,0.1

Type RM Length L Ch R = 1 ,315     ,157,157,157
XS GIS Cut Line= 4
     2235675.373    13201050.917     2235743.081    13200881.647
      2235694.47     13200746.23     2235355.928    13200598.661
#Sta/Elev= 30
       0294.448847.63856293.729166.69398293.986476.22169293.8924104.8048292.6542
123.8603292.6631152.4434292.3103200.0623292.2467209.5802292.0129266.6874292.3385
285.7231292.2874 295.241292.4628 333.571292.9155343.3473293.1876362.8999293.1621
372.6762292.8288392.2289291.5757402.0052291.5608421.5579292.6255431.3342293.4281
441.1105293.8806450.8869293.8771460.6632294.1956480.2159294.4629489.9922294.9123
499.7685 295.064509.5448294.9053538.8738294.9787617.0844295.8879 695.295295.8927
#Mann= 3 , 0 , 0
       0     .16       0200.0623     .07       0 295.241     .16       0
#XS Ineff= 2 , 0
                          362.45          293.18
Permanent Ineff=
       F       F
Bank Sta=200.0623,295.241
XS Rating Curve= 0 ,0
Exp/Cntr=0.3,0.1

Type RM Length L Ch R = 1 ,129     ,0,0,0
BEGIN DESCRIPTION:
UNT 048 IN LACR 1.0
END DESCRIPTION:
XS GIS Cut Line= 4
      2235749.02     13201044.53      2235901.79     13200874.39
      2235867.07     13200752.87      2235479.02      13200631.6
#Sta/Elev= 30
  4690.7  292.93  4709.5   293.6  4716.2  292.92  4737.9  292.24  4744.6  291.54
  4780.5  290.85  4794.7  291.21  4801.4  290.73  4836.5   290.1    4844  290.32
  4850.7   289.9  4886.6   289.6    5000  290.45  5020.4  290.08  5041.1  290.61
  5049.7  290.27  5128.9  291.67  5170.8  291.85  5191.7  292.77  5223.2  292.17
  5249.8  289.97  5254.8  288.64  5265.1  289.82    5307  291.83  5314.8  293.27
    5320  292.89  5327.9  293.03  5379.7  294.33  5390.8  294.95  5452.3  295.08
#Mann= 4 ,-1 , 0
  4690.7     .07       0    5000     .05       0  5041.1     .07       0
  5452.3     .05       0
#XS Ineff= 2 ,-1
 4802.84 4999.43  290.46 5191.48  5452.3  292.77
Permanent Ineff=
       T       T
Bank Sta=5000,5041.1
XS Rating Curve= 0 ,0
Exp/Cntr=0.3,0.1

Chan Stop Cuts=-1
Use User Specified Reach Order=0
Composite Channel Slope=5