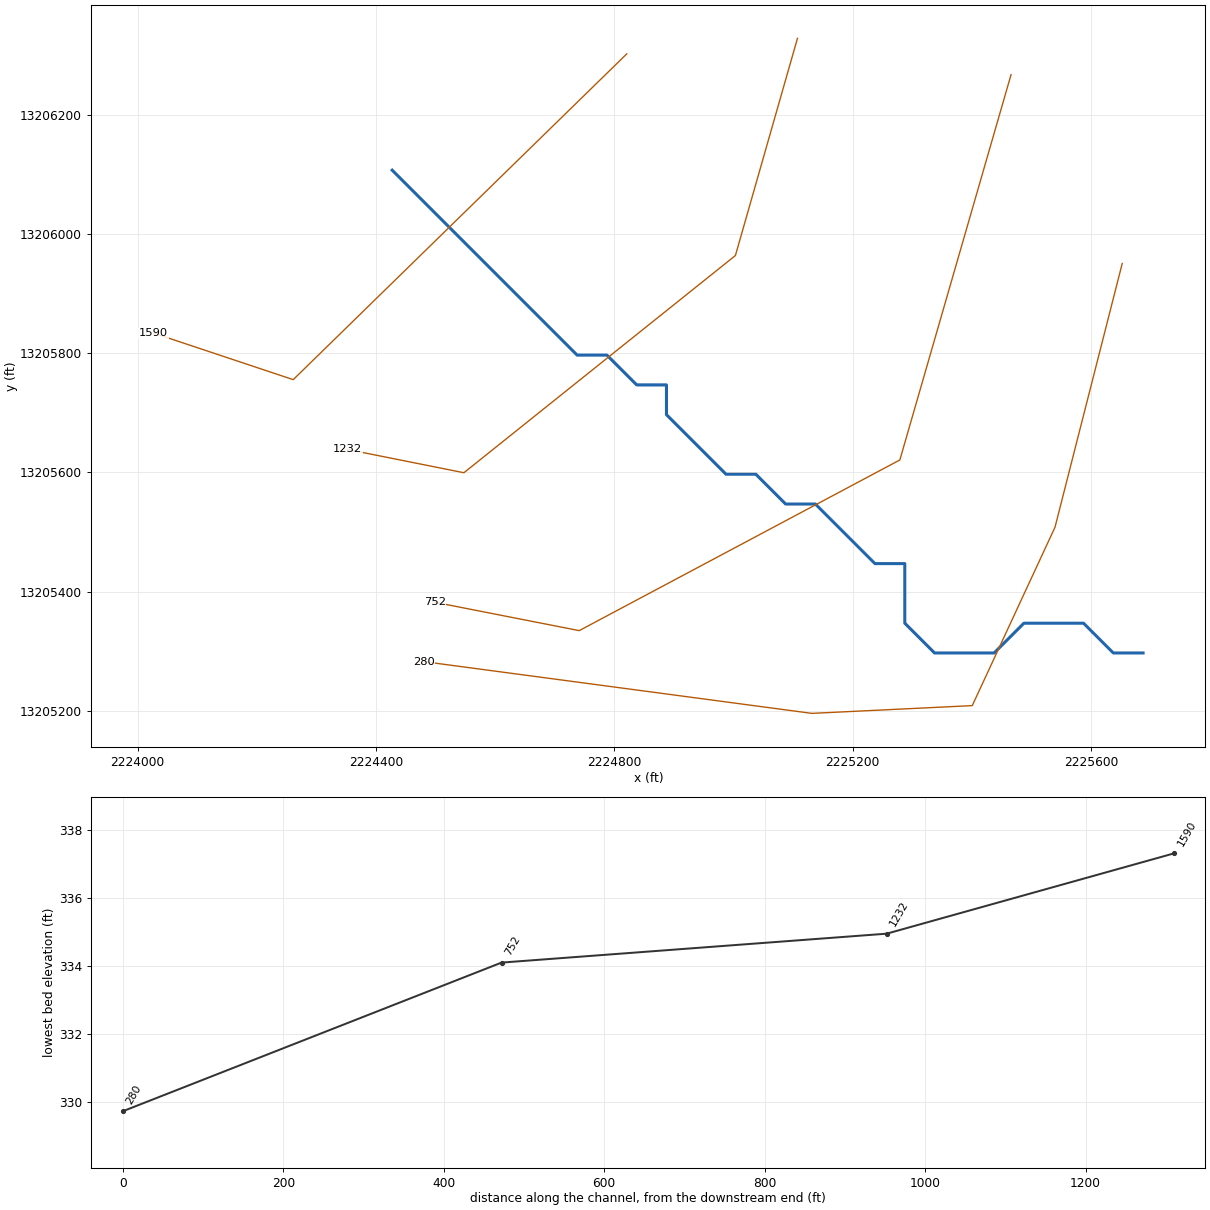
--- UNT 050 IN LACR.prj (project) ---

Proj Title=UNT 050 IN LACR Base Level Engineering
Current Plan=p01
Default Exp/Contr=0.3,0.1
English Units
Geom File=g01
Flow File=f01
Plan File=p01
BEGIN DESCRIPTION:
UNT 050 IN LACR
END DESCRIPTION:

--- UNT 050 IN LACR.p01 (plan) ---

Plan Title=Multiple Run
Short Identifier=Multiple
Geom File=g01
Flow File=f01
Subcritical Flow
K Sum by GR= 0
Std Step Tol= 0.01
Critical Tol= 0.01
Num of Std Step Trials= 20
Max Error Tol= 0.3
Flow Tol Ratio= 0.001
Split Flow NTrial= 30
Split Flow Tol= 0.02
Split Flow Ratio= 0.02
Log Output Level= 0
Friction Slope Method= 1
Unsteady Friction Slope Method= 2
Unsteady Bridges Friction Slope Method= 1
Parabolic Critical Depth
Global Vel Dist=  1 , 1 , 1
Global Log Level= 0
CheckData=True
Encroach Param= -1, 0, 0, 0
BEGIN DESCRIPTION:
Multiple Run
END DESCRIPTION:

--- UNT 050 IN LACR.f01 (steady flow) ---

Flow Title=Multiple
Number of Profiles=7
Profile Names=10-year,25-year,50-year,1pct_min,100-year,1pct_plu,500-year
River Rch & RM= UNT 050 IN LACR,Reach-1,1590
     184     252     308     278     375     508     565
Boundary for River Rch & Prof#=UNT 050 IN LACR,Reach-1,1
Up Type=0
Dn Type=3
Dn Slope=0.005
Boundary for River Rch & Prof#=UNT 050 IN LACR,Reach-1,2
Up Type=0
Dn Type=3
Dn Slope=0.005
Boundary for River Rch & Prof#=UNT 050 IN LACR,Reach-1,3
Up Type=0
Dn Type=3
Dn Slope=0.005
Boundary for River Rch & Prof#=UNT 050 IN LACR,Reach-1,4
Up Type=0
Dn Type=3
Dn Slope=0.005
Boundary for River Rch & Prof#=UNT 050 IN LACR,Reach-1,5
Up Type=0
Dn Type=3
Dn Slope=0.005
Boundary for River Rch & Prof#=UNT 050 IN LACR,Reach-1,6
Up Type=0
Dn Type=3
Dn Slope=0.005
Boundary for River Rch & Prof#=UNT 050 IN LACR,Reach-1,7
Up Type=0
Dn Type=3
Dn Slope=0.005

--- UNT 050 IN LACR.g01 (geometry) ---

Geom Title=Existing Conditions

River Reach=UNT 050 IN LACR,Reach-1
Reach XY= 25
      2224427.34     13206107.23      2224437.72     13206096.86
      2224737.72     13205796.85      2224787.72     13205796.85
      2224837.72     13205746.86      2224887.72     13205746.86
      2224887.72     13205696.85      2224937.72     13205646.85
      2224987.72     13205596.86      2225037.72     13205596.86
      2225087.72     13205546.85      2225137.72     13205546.85
      2225187.72     13205496.85      2225237.72     13205446.86
      2225287.72     13205446.86      2225287.72     13205396.85
      2225287.72     13205346.85      2225337.72     13205296.85
      2225387.72     13205296.85      2225437.72     13205296.85
      2225487.72     13205346.85      2225537.72     13205346.85
      2225587.72     13205346.85      2225637.72     13205296.85
      2225687.72     13205296.85

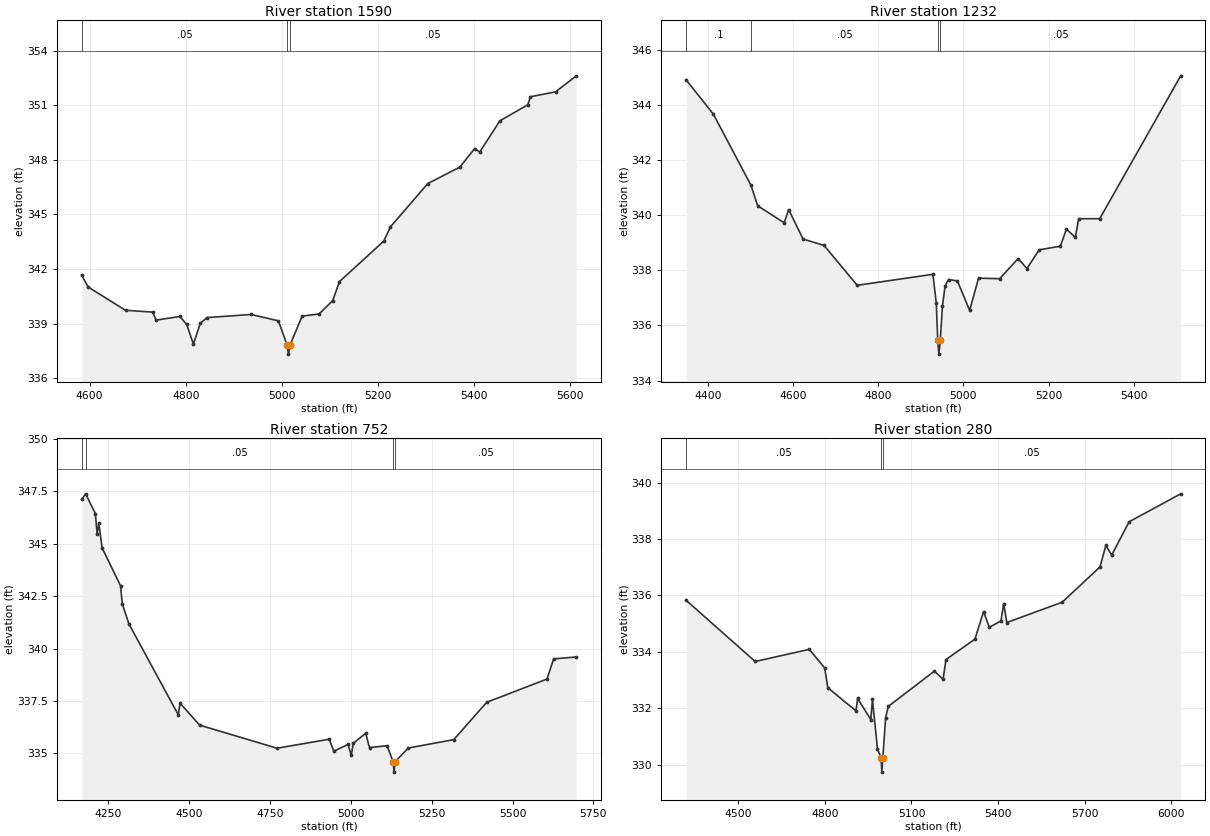
Type RM Length L Ch R = 1,1590,358,358,358
BEGIN DESCRIPTION:
UNT 050 IN LACR 2.0
END DESCRIPTION:
XS GIS Cut Line= 3
      2224821.17     13206302.52      2224261.26     13205755.63
      2224026.92     13205833.75
#Sta/Elev= 30
  4583.4  341.67  4596.9  341.01  4674.7  339.73  4731.2  339.63  4738.4  339.19
  4787.8  339.39  4802.0  338.95  4816.1  337.87  4830.3  339.01  4844.4  339.33
  4936.4  339.50  4993.0  339.15  5011.1  337.82  5013.9  337.32  5017.1  337.82
  5042.4  339.41  5077.7  339.53  5106.0  340.26  5120.1  341.31  5212.2  343.53
  5226.3  344.32  5304.0  346.70  5370.6  347.60  5401.4  348.62  5412.0  348.43
  5454.2  350.15  5512.2  351.03  5517.5  351.47  5570.1  351.74  5613.1  352.62
#Mann=3,-1,0
  4583.4    0.05       0  5011.1    0.03       0  5017.1    0.05       0
Bank Sta=5011.1,5017.1
Exp/Cntr=0.3,0.1

Type RM Length L Ch R = 1,1232,480,480,480
BEGIN DESCRIPTION:
Mapping XS 428a3483
END DESCRIPTION:
XS GIS Cut Line= 4
      2225107.60     13206328.51      2225003.45     13205963.97
      2224547.72     13205599.38      2224352.53     13205638.42
#Sta/Elev= 30
  4348.5  344.93  4412.6  343.68  4500.9  341.10  4516.8  340.35  4579.0  339.73
  4589.6  340.21  4623.4  339.14  4672.6  338.91  4750.6  337.46  4928.3  337.86
  4936.3  336.82  4939.7  335.46  4942.4  334.96  4945.7  335.46  4950.7  336.71
  4957.1  337.44  4965.1  337.67  4985.9  337.62  5014.7  336.55  5035.5  337.72
  5085.2  337.70  5128.4  338.43  5149.2  338.07  5178.0  338.75  5227.6  338.88
  5242.0  339.50  5262.8  339.20  5270.8  339.88  5320.1  339.88  5510.3  345.07
#Mann=4,-1,0
  4348.5     0.1       0  4500.9    0.05       0  4939.7    0.03       0
  4945.7    0.05       0
Bank Sta=4939.7,4945.7
Exp/Cntr=0.3,0.1

Type RM Length L Ch R = 1,752,472,472,472
BEGIN DESCRIPTION:
Mapping XS 3154c102
END DESCRIPTION:
XS GIS Cut Line= 4
      2225466.10     13206267.55      2225279.46     13205620.82
      2224741.27     13205334.36      2224498.81     13205381.99
#Sta/Elev= 30
  4167.4  347.11  4179.7  347.38  4209.8  346.44  4215.3  345.47  4220.5  345.97
  4230.6  344.81  4287.8  342.99  4293.0  342.14  4313.8  341.17  4466.4  336.84
  4471.6  337.40  4532.4  336.35  4771.8  335.25  4933.1  335.68  4947.4  335.11
  4991.4  335.43  5001.1  334.91  5007.7  335.49  5045.9  335.96  5057.7  335.28
  5111.9  335.37  5130.8  334.61  5133.6  334.11  5136.8  334.61  5177.8  335.26
  5318.3  335.66  5420.2  337.44  5606.7  338.55  5627.1  339.51  5697.3  339.60
#Mann=4,-1,0
  4167.4     0.1       0  4179.7    0.05       0  5130.8    0.03       0
  5136.8    0.05       0
Bank Sta=5130.8,5136.8
Exp/Cntr=0.3,0.1

Type RM Length L Ch R = 1,280,0,0,0
BEGIN DESCRIPTION:
UNT 050 IN LACR 1.0
END DESCRIPTION:
XS GIS Cut Line= 5
      2225652.72     13205950.64      2225539.88     13205507.97
      2225400.99     13205208.50      2225131.89     13205195.47
      2224480.80     13205282.29
#Sta/Elev= 30
  4319.2  335.83  4558.7  333.66  4746.2  334.09  4799.3  333.43  4810.3  332.73
  4907.9  331.91  4913.5  332.35  4959.3  331.60  4964.8  332.32  4982.2  330.57
  4994.7  330.24  4997.5  329.74  5000.7  330.24  5010.6  331.67  5019.8  332.07
  5179.5  333.32  5209.5  333.03  5219.5  333.73  5319.7  334.45  5349.7  335.43
  5369.7  334.87  5410.0  335.10  5419.4  335.71  5430.2  335.04  5621.9  335.76
  5753.0  337.01  5773.2  337.77  5793.4  337.43  5853.9  338.61  6032.4  339.60
#Mann=3,-1,0
  4319.2    0.05       0  4994.7    0.03       0  5000.7    0.05       0
Bank Sta=4994.7,5000.7
Exp/Cntr=0.3,0.1

Chan Stop Cuts=-1