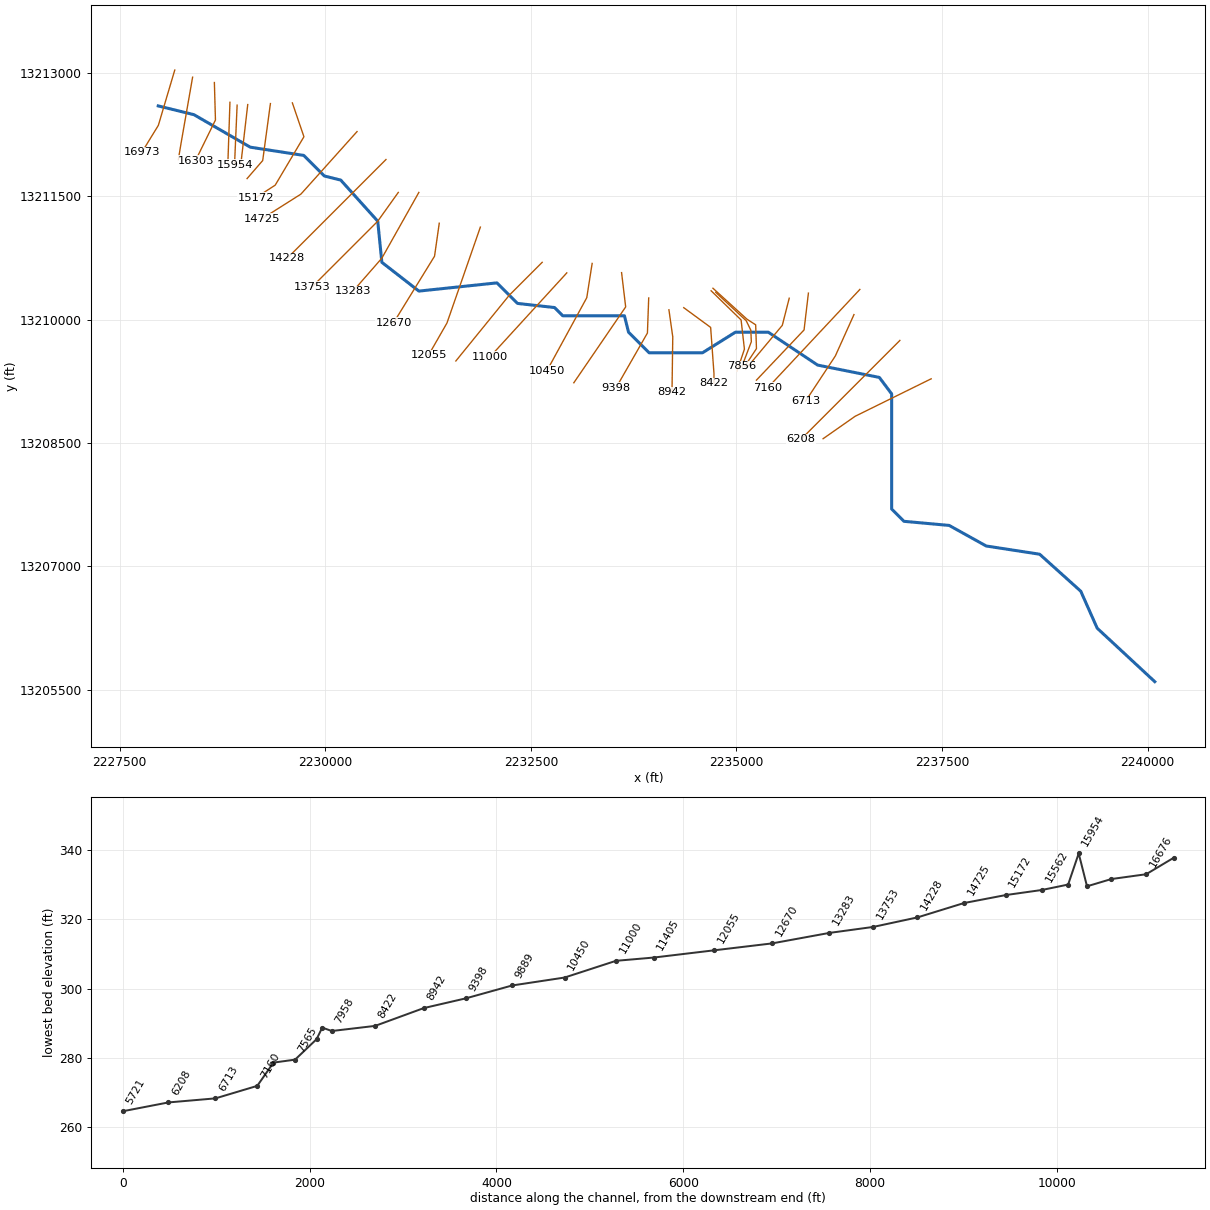
--- UNT 051 IN LACR.prj (project) ---

Proj Title=UNT 051 IN LACR Base Level Engineering
Current Plan=p01
Default Exp/Contr=0.3,0.1
English Units
Geom File=g01
Flow File=f01
Plan File=p01
BEGIN DESCRIPTION:
UNT 051 IN LACR
END DESCRIPTION:

--- UNT 051 IN LACR.p01 (plan) ---

Plan Title=Multiple Run
Short Identifier=Multiple
Geom File=g01
Flow File=f01
Subcritical Flow
K Sum by GR= 0
Std Step Tol= 0.01
Critical Tol= 0.01
Num of Std Step Trials= 20
Max Error Tol= 0.3
Flow Tol Ratio= 0.001
Split Flow NTrial= 30
Split Flow Tol= 0.02
Split Flow Ratio= 0.02
Log Output Level= 0
Friction Slope Method= 1
Unsteady Friction Slope Method= 2
Unsteady Bridges Friction Slope Method= 1
Parabolic Critical Depth
Global Vel Dist=  1 , 1 , 1
Global Log Level= 0
CheckData=True
Encroach Param= -1, 0, 0, 0
BEGIN DESCRIPTION:
Multiple Run
END DESCRIPTION:

--- UNT 051 IN LACR.f01 (steady flow) ---

Flow Title=Multiple
Number of Profiles=7
Profile Names=10-year,25-year,50-year,1pct_min,100-year,1pct_plu,500-year
River Rch & RM= UNT 051 IN LACR,Reach-1,16973
     225     312     385     349     473     639     723
River Rch & RM= UNT 051 IN LACR,Reach-1,14725
     308     433     539     494     667     903    1038
River Rch & RM= UNT 051 IN LACR,Reach-1,7565
     477     687     867     804    1087    1470    1737
River Rch & RM= UNT 051 IN LACR,Reach-1,7160
     568     823    1044     972    1314    1777    2116
Boundary for River Rch & Prof#=UNT 051 IN LACR,Reach-1,1
Up Type=0
Dn Type=3
Dn Slope=0.005
Boundary for River Rch & Prof#=UNT 051 IN LACR,Reach-1,2
Up Type=0
Dn Type=3
Dn Slope=0.005
Boundary for River Rch & Prof#=UNT 051 IN LACR,Reach-1,3
Up Type=0
Dn Type=3
Dn Slope=0.005
Boundary for River Rch & Prof#=UNT 051 IN LACR,Reach-1,4
Up Type=0
Dn Type=3
Dn Slope=0.005
Boundary for River Rch & Prof#=UNT 051 IN LACR,Reach-1,5
Up Type=0
Dn Type=3
Dn Slope=0.005
Boundary for River Rch & Prof#=UNT 051 IN LACR,Reach-1,6
Up Type=0
Dn Type=3
Dn Slope=0.005
Boundary for River Rch & Prof#=UNT 051 IN LACR,Reach-1,7
Up Type=0
Dn Type=3
Dn Slope=0.005

--- UNT 051 IN LACR.g01 (geometry) ---

Geom Title=Existing Conditions

River Reach=UNT 051 IN LACR,Reach-1
Reach XY= 30
      2227968.09     13212598.90      2228402.05     13212492.50
      2229087.72     13212096.85      2229737.72     13211996.86
      2229987.72     13211746.85      2230187.72     13211696.85
      2230637.72     13211196.86      2230687.72     13210696.86
      2231137.72     13210346.86      2232087.72     13210446.85
      2232337.72     13210196.86      2232787.72     13210146.85
      2232887.72     13210046.86      2233637.72     13210046.86
      2233687.72     13209846.85      2233937.72     13209596.85
      2234587.72     13209596.85      2234987.72     13209846.85
      2235387.72     13209846.85      2235987.72     13209446.85
      2236737.72     13209296.85      2236887.72     13209096.85
      2236887.72     13207696.85      2237037.72     13207546.85
      2237587.72     13207496.85      2238037.72     13207246.86
      2238687.72     13207146.85      2239187.72     13206696.85
      2239387.72     13206246.86      2240087.72     13205596.86

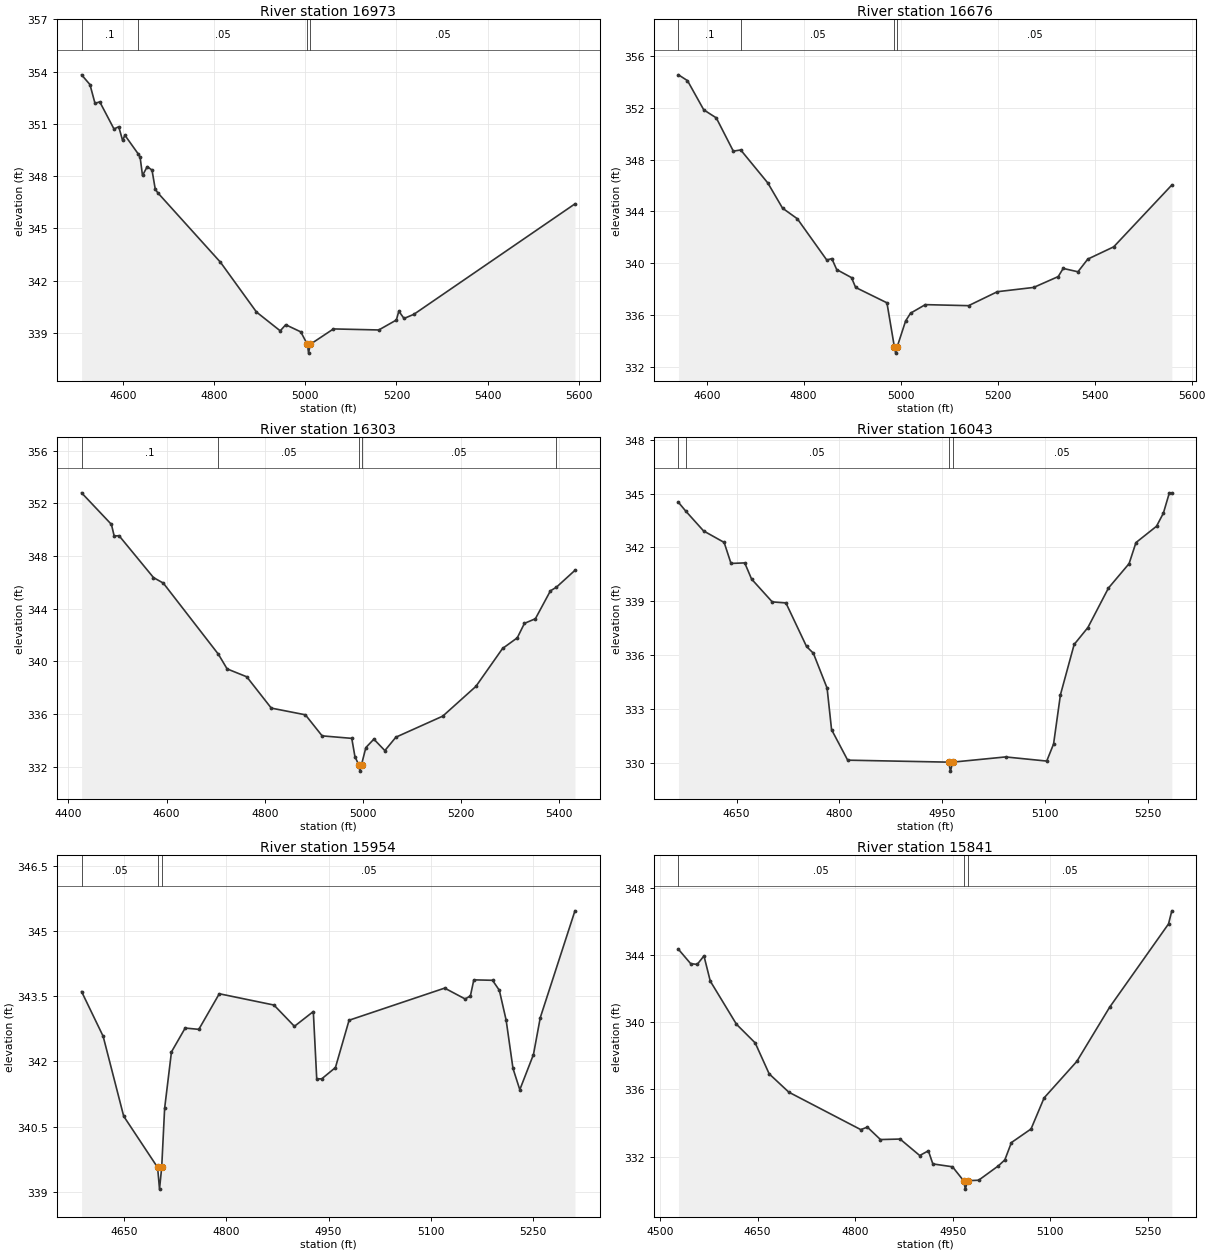
Type RM Length L Ch R = 1,16973,297,297,297
BEGIN DESCRIPTION:
UNT 051 IN LACR 33.0
END DESCRIPTION:
XS GIS Cut Line= 3
      2228169.23     13213035.12      2227969.58     13212362.37
      2227769.94     13212036.87
#Sta/Elev= 30
  4508.4  353.81  4526.8  353.25  4537.9  352.17  4548.3  352.26  4579.6  350.70
  4590.0  350.83  4598.4  350.05  4603.6  350.34  4632.2  349.29  4636.9  349.09
  4642.2  348.03  4652.6  348.54  4663.1  348.34  4670.1  347.26  4675.3  347.05
  4813.4  343.05  4892.5  340.19  4944.7  339.11  4956.7  339.46  4989.9  339.05
  5004.3  338.33  5007.0  337.83  5010.3  338.33  5061.6  339.22  5161.2  339.16
  5199.7  339.73  5205.2  340.24  5216.6  339.82  5238.3  340.06  5592.0  346.40
#Mann=4,-1,0
  4508.4     0.1       0  4632.2    0.05       0  5004.3    0.03       0
  5010.3    0.05       0
Bank Sta=5004.3,5010.3
Exp/Cntr=0.3,0.1

Type RM Length L Ch R = 1,16676,373,373,373
BEGIN DESCRIPTION:
Mapping XS 56f88d
END DESCRIPTION:
XS GIS Cut Line= 3
      2228386.24     13212948.29      2228247.36     13212154.03
      2228212.67     13211945.91
#Sta/Elev= 30
  4541.8  354.56  4560.4  354.11  4594.0  351.85  4619.8  351.23  4654.9  348.66
  4670.2  348.75  4726.0  346.20  4756.4  344.25  4786.9  343.43  4847.6  340.24
  4858.0  340.35  4868.1  339.50  4898.6  338.88  4907.1  338.12  4971.7  336.93
  4986.9  333.54  4989.7  333.04  4992.9  333.54  5010.2  335.53  5020.4  336.13
  5050.8  336.79  5140.0  336.71  5199.4  337.79  5274.2  338.12  5324.9  338.96
  5335.1  339.59  5365.5  339.33  5385.8  340.31  5439.3  341.26  5559.1  346.04
#Mann=4,-1,0
  4541.8     0.1       0  4670.2    0.05       0  4986.9    0.03       0
  4992.9    0.05       0
Bank Sta=4986.9,4992.9
Exp/Cntr=0.3,0.1

Type RM Length L Ch R = 1,16303,260,260,260
BEGIN DESCRIPTION:
Mapping XS 56f88dcb
END DESCRIPTION:
XS GIS Cut Line= 3
      2228651.00     13212883.25      2228664.02     13212427.47
      2228421.86     13211934.50
#Sta/Elev= 30
  4426.8  352.80  4487.6  350.40  4493.2  349.52  4503.2  349.54  4573.3  346.36
  4593.3  345.94  4705.6  340.53  4723.3  339.42  4763.3  338.82  4813.3  336.44
  4882.8  335.93  4916.9  334.33  4977.3  334.14  4983.7  332.76  4991.2  332.15
  4994.0  331.65  4997.2  332.15  5006.0  333.44  5022.3  334.08  5044.7  333.21
  5067.2  334.23  5162.7  335.83  5230.2  338.09  5284.5  340.97  5314.5  341.78
  5329.1  342.88  5351.4  343.23  5382.0  345.35  5394.3  345.63  5432.0  346.91
#Mann=5,-1,0
  4426.8     0.1       0  4705.6    0.05       0  4991.2    0.03       0
  4997.2    0.05       0  5394.3     0.1       0
Bank Sta=4991.2,4997.2
Exp/Cntr=0.3,0.1

Type RM Length L Ch R = 1,16043,89,89,89
BEGIN DESCRIPTION:
Mapping XS 56f88dc
END DESCRIPTION:
XS GIS Cut Line= 2
      2228840.35     13212643.44      2228815.92     13211924.55
#Sta/Elev= 30
  4565.3  344.51  4576.0  344.02  4601.9  342.92  4631.9  342.28  4641.9  341.11
  4661.9  341.14  4671.9  340.24  4702.0  338.97  4722.0  338.91  4752.0  336.49
  4762.0  336.11  4782.0  334.17  4788.5  331.86  4812.0  330.16  4959.1  330.05
  4961.9  329.55  4965.1  330.05  5042.2  330.34  5102.2  330.11  5112.2  331.06
  5122.2  333.80  5142.2  336.60  5162.2  337.54  5192.2  339.74  5222.3  341.10
  5232.3  342.27  5262.3  343.18  5272.3  343.91  5281.0  345.04  5284.6  345.04
#Mann=4,-1,0
  4565.3     0.1       0  4576.0    0.05       0  4959.1    0.03       0
  4965.1    0.05       0
Bank Sta=4959.1,4965.1
Exp/Cntr=0.3,0.1

Type RM Length L Ch R = 1,15954,113,113,113
BEGIN DESCRIPTION:
Mapping XS 0ea1f141
END DESCRIPTION:
XS GIS Cut Line= 2
      2228927.59     13212608.47      2228896.18     13211886.15
#Sta/Elev= 30
  4588.0  343.61  4619.6  342.58  4649.7  340.74  4699.4  339.56  4702.2  339.06
  4705.4  339.56  4709.7  340.92  4719.7  342.22  4739.8  342.77  4759.8  342.74
  4789.8  343.56  4869.9  343.30  4899.9  342.81  4927.6  343.15  4932.6  341.60
  4939.9  341.60  4960.0  341.86  4980.0  342.95  5120.1  343.69  5150.1  343.44
  5157.8  343.51  5162.8  343.88  5190.2  343.87  5200.2  343.64  5210.2  342.95
  5220.2  341.84  5230.2  341.35  5250.2  342.16  5260.2  343.01  5311.0  345.47
#Mann=3,-1,0
  4588.0    0.05       0  4699.4    0.03       0  4705.4    0.05       0
Bank Sta=4699.4,4705.4
Exp/Cntr=0.3,0.1

Type RM Length L Ch R = 1,15841,279,279,279
BEGIN DESCRIPTION:
Mapping XS 1ed006e0
END DESCRIPTION:
XS GIS Cut Line= 2
      2229056.70     13212615.43      2228969.47     13211861.76
#Sta/Elev= 30
  4528.3  344.33  4547.0  343.48  4557.1  343.43  4567.5  343.94  4577.2  342.44
  4617.5  339.87  4646.3  338.76  4667.8  336.92  4698.0  335.83  4808.7  333.60
  4818.8  333.75  4838.9  333.01  4869.1  333.04  4899.3  332.06  4912.6  332.34
  4919.5  331.56  4949.7  331.39  4966.8  330.56  4969.5  330.06  4972.8  330.56
  4989.9  330.59  5020.1  331.44  5030.2  331.80  5040.3  332.83  5070.5  333.64
  5090.6  335.49  5140.9  337.66  5191.3  340.88  5281.9  345.84  5287.0  346.62
#Mann=3,-1,0
  4528.3    0.05       0  4966.8    0.03       0  4972.8    0.05       0
Bank Sta=4966.8,4972.8
Exp/Cntr=0.3,0.1

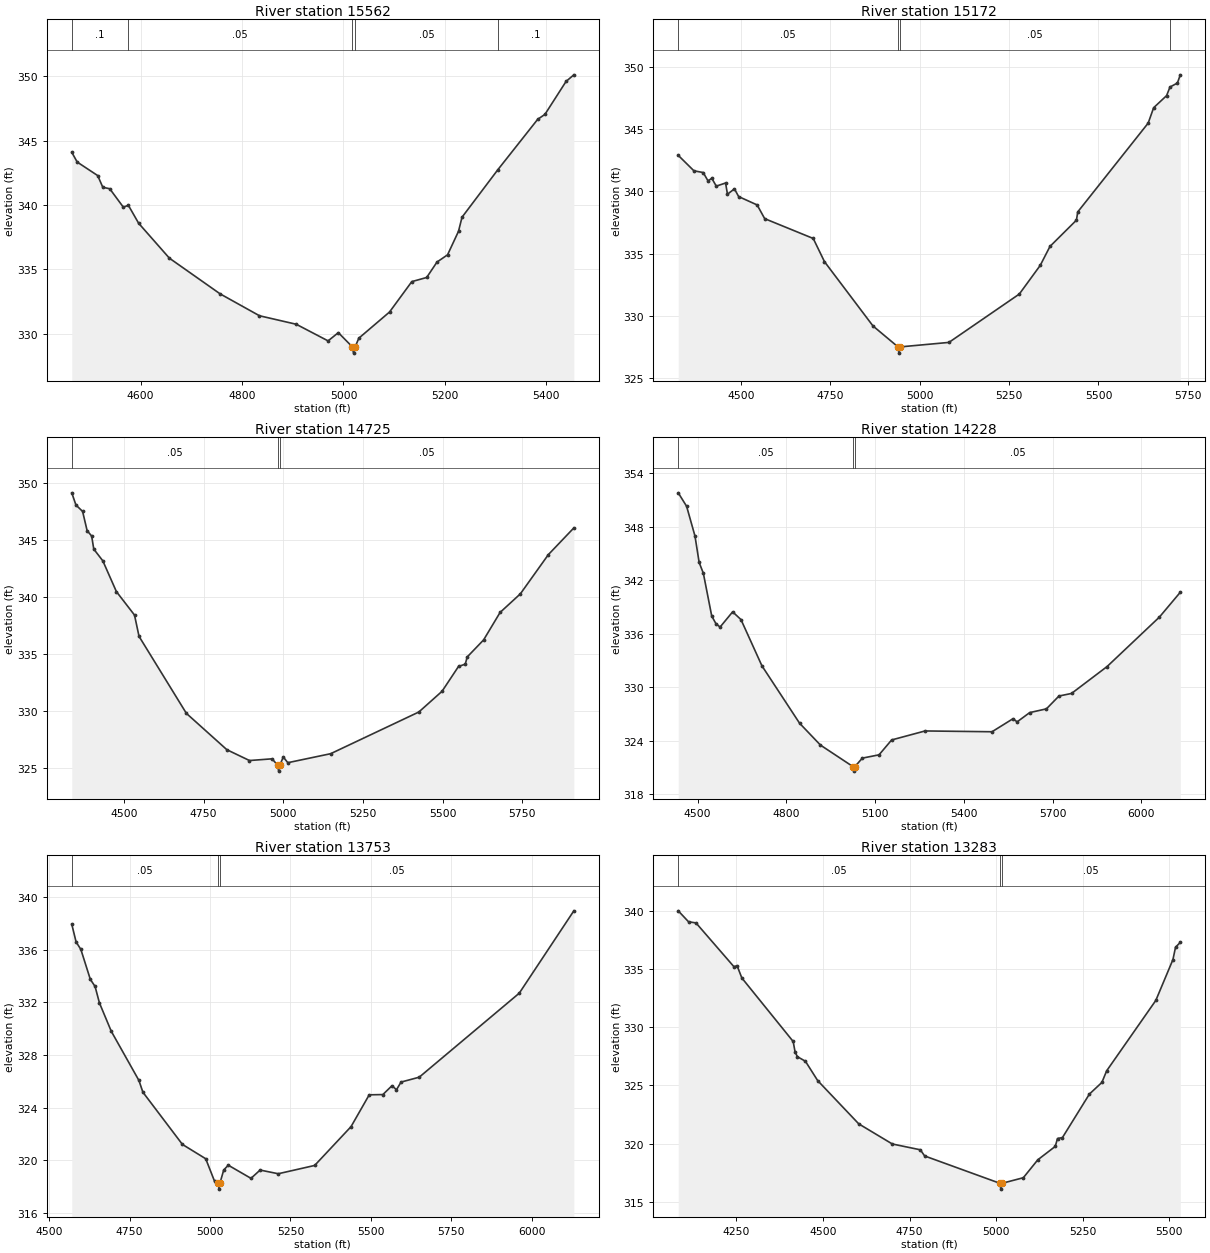
Type RM Length L Ch R = 1,15562,390,390,390
BEGIN DESCRIPTION:
UNT 051 IN LACR 32.0
END DESCRIPTION:
XS GIS Cut Line= 3
      2229332.56     13212627.50      2229238.57     13211934.37
      2229048.63     13211715.06
#Sta/Elev= 30
  4464.5  344.09  4475.2  343.33  4515.6  342.28  4525.7  341.37  4539.3  341.26
  4566.1  339.83  4576.1  339.97  4596.3  338.58  4656.9  335.87  4756.9  333.10
  4834.5  331.40  4907.0  330.74  4969.7  329.45  4989.9  330.09  5017.2  329.00
  5019.9  328.50  5023.2  329.00  5030.3  329.66  5090.8  331.69  5134.7  334.05
  5164.0  334.37  5184.4  335.57  5205.2  336.13  5226.8  337.96  5233.7  339.05
  5304.4  342.74  5382.9  346.65  5397.1  347.03  5438.8  349.59  5454.1  350.10
#Mann=5,-1,0
  4464.5     0.1       0  4576.1    0.05       0  5017.2    0.03       0
  5023.2    0.05       0  5304.4     0.1       0
Bank Sta=5017.2,5023.2
Exp/Cntr=0.3,0.1

Type RM Length L Ch R = 1,15172,447,447,447
BEGIN DESCRIPTION:
UNT 051 IN LACR 31.0
END DESCRIPTION:
XS GIS Cut Line= 4
      2229599.37     13212635.65      2229740.00     13212224.18
      2229391.04     13211635.63      2229152.13     13211479.82
#Sta/Elev= 30
  4324.6  342.89  4368.4  341.65  4394.4  341.51  4407.9  340.84  4418.4  341.05
  4431.0  340.42  4457.0  340.67  4462.3  339.77  4481.8  340.20  4493.6  339.58
  4545.3  338.91  4566.4  337.81  4702.2  336.22  4733.6  334.36  4869.3  329.20
  4939.3  327.52  4942.1  327.02  4945.3  327.52  5081.7  327.88  5278.6  331.76
  5337.1  334.06  5364.3  335.58  5438.4  337.69  5442.0  338.35  5639.1  345.48
  5654.3  346.71  5690.5  347.68  5700.0  348.37  5720.7  348.69  5728.9  349.35
#Mann=4,-1,0
  4324.6    0.05       0  4939.3    0.03       0  4945.3    0.05       0
  5700.0     0.1       0
Bank Sta=4939.3,4945.3
Exp/Cntr=0.3,0.1

Type RM Length L Ch R = 1,14725,497,497,497
BEGIN DESCRIPTION:
UNT 051 IN LACR 30.0
END DESCRIPTION:
XS GIS Cut Line= 3
      2230385.84     13212286.68      2229703.54     13211526.26
      2229234.80     13211229.39
#Sta/Elev= 30
  4335.8  349.14  4348.9  348.07  4369.8  347.51  4384.0  345.82  4398.2  345.35
  4404.9  344.20  4433.3  343.17  4475.9  340.47  4532.8  338.41  4547.0  336.54
  4695.7  329.78  4822.8  326.59  4893.8  325.64  4964.8  325.79  4982.8  325.21
  4985.5  324.71  4988.8  325.21  5000.0  325.95  5014.2  325.45  5148.7  326.24
  5425.6  329.90  5498.5  331.72  5550.2  333.90  5571.4  334.10  5577.4  334.73
  5629.0  336.23  5680.7  338.64  5744.3  340.27  5832.4  343.72  5912.3  346.06
#Mann=3,-1,0
  4335.8    0.05       0  4982.8    0.03       0  4988.8    0.05       0
Bank Sta=4982.8,4988.8
Exp/Cntr=0.3,0.1

Type RM Length L Ch R = 1,14228,475,475,475
BEGIN DESCRIPTION:
UNT 051 IN LACR 29.0
END DESCRIPTION:
XS GIS Cut Line= 3
      2230737.73     13211946.87      2230337.72     13211546.85
      2229537.70     13210746.83
#Sta/Elev= 30
  4434.3  351.81  4462.6  350.30  4490.9  346.96  4505.0  343.99  4519.2  342.78
  4547.5  337.98  4561.6  337.13  4575.7  336.74  4618.2  338.45  4646.4  337.58
  4717.2  332.39  4844.4  325.95  4915.1  323.49  5025.3  321.07  5028.0  320.57
  5031.3  321.07  5056.6  322.03  5113.1  322.40  5155.6  324.07  5268.7  325.08
  5495.0  324.99  5565.7  326.45  5579.8  326.10  5622.3  327.14  5678.8  327.56
  5721.2  329.00  5763.7  329.29  5883.9  332.31  6060.7  337.86  6131.4  340.65
#Mann=3,-1,0
  4434.3    0.05       0  5025.3    0.03       0  5031.3    0.05       0
Bank Sta=5025.3,5031.3
Exp/Cntr=0.3,0.1

Type RM Length L Ch R = 1,13753,470,470,470
BEGIN DESCRIPTION:
UNT 051 IN LACR 28.0
END DESCRIPTION:
XS GIS Cut Line= 3
      2230887.71     13211546.84      2230637.72     13211196.86
      2229837.70     13210396.83
#Sta/Elev= 30
  4569.9  337.95  4583.4  336.60  4598.1  336.04  4627.6  333.76  4642.4  333.22
  4655.9  331.97  4692.8  329.81  4778.8  326.07  4791.1  325.18  4914.0  321.21
  4986.5  320.12  5014.1  318.40  5025.3  318.31  5028.0  317.81  5031.3  318.31
  5042.4  319.26  5056.6  319.63  5127.3  318.63  5155.6  319.26  5212.1  318.98
  5325.3  319.61  5438.4  322.56  5495.0  324.98  5537.4  325.00  5565.7  325.67
  5579.8  325.37  5594.0  325.95  5650.5  326.32  5961.7  332.71  6131.4  338.97
#Mann=3,-1,0
  4569.9    0.05       0  5025.3    0.03       0  5031.3    0.05       0
Bank Sta=5025.3,5031.3
Exp/Cntr=0.3,0.1

Type RM Length L Ch R = 1,13283,613,613,613
BEGIN DESCRIPTION:
UNT 051 IN LACR 27.0
END DESCRIPTION:
XS GIS Cut Line= 3
      2231137.73     13211546.87      2230687.72     13210746.85
      2230337.73     13210346.86
#Sta/Elev= 30
  4082.1  340.00  4111.8  339.06  4133.4  338.96  4242.8  335.20  4252.0  335.28
  4265.7  334.23  4413.9  328.77  4419.6  327.84  4426.3  327.46  4449.3  327.07
  4484.6  325.41  4603.2  321.69  4700.1  319.96  4781.0  319.46  4793.5  318.93
  5010.8  316.58  5013.5  316.08  5016.8  316.58  5078.3  317.06  5120.1  318.60
  5170.4  319.75  5177.0  320.43  5191.2  320.51  5269.1  324.25  5305.1  325.25
  5318.9  326.25  5460.8  332.30  5510.2  335.81  5517.7  336.87  5531.5  337.29
#Mann=3,-1,0
  4082.1    0.05       0  5010.8    0.03       0  5016.8    0.05       0
Bank Sta=5010.8,5016.8
Exp/Cntr=0.3,0.1

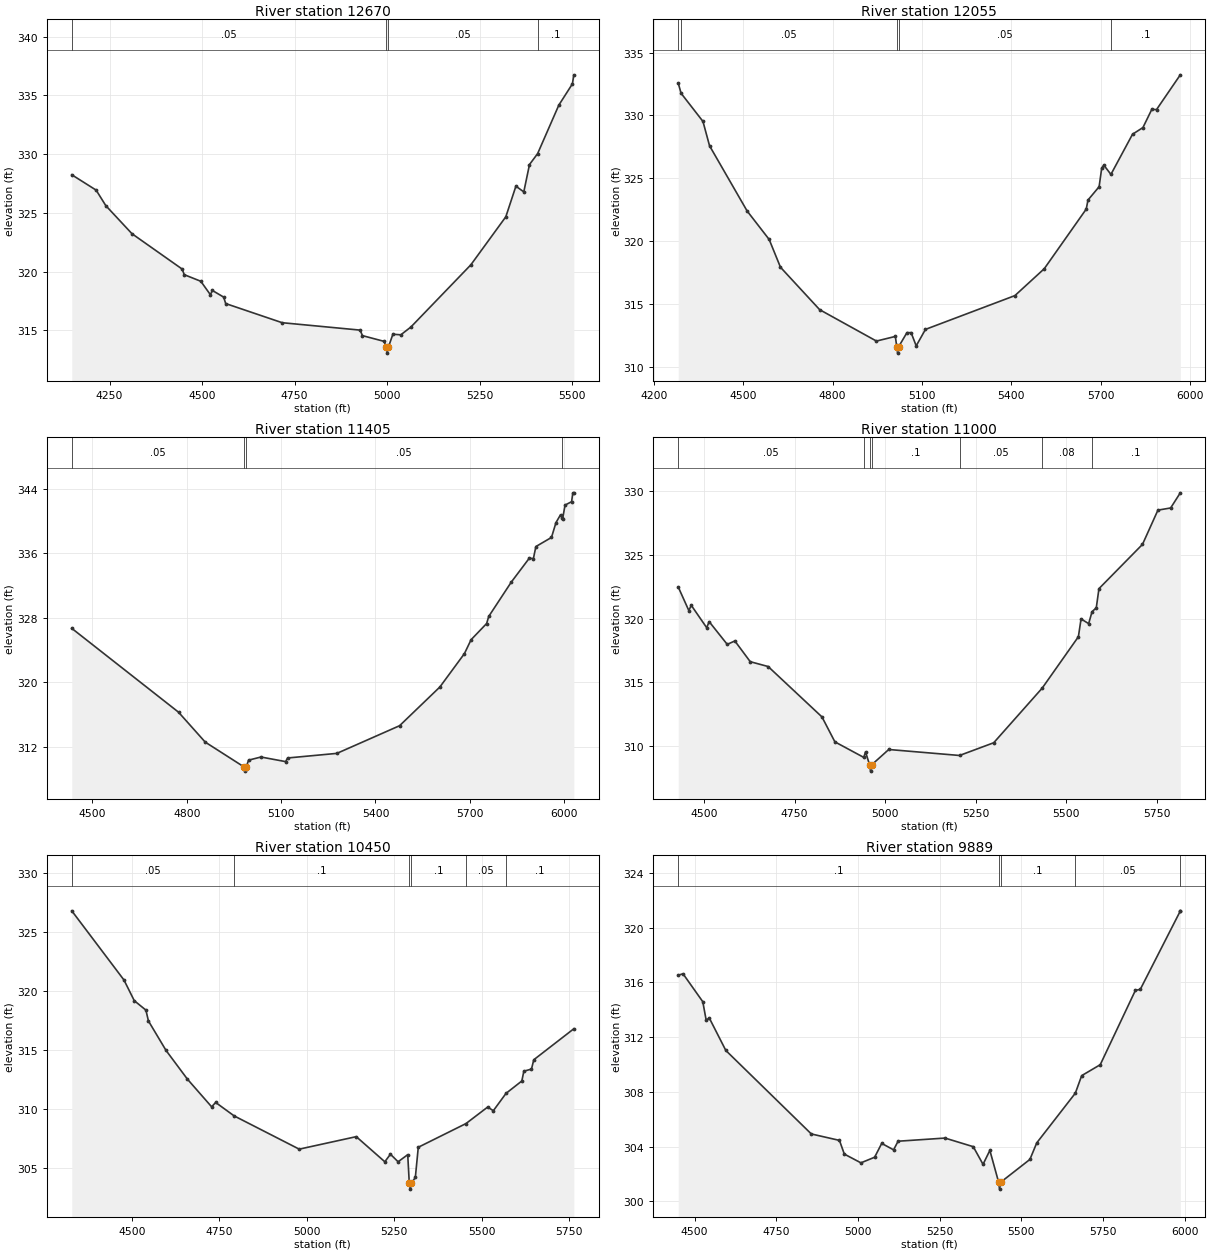
Type RM Length L Ch R = 1,12670,615,615,615
BEGIN DESCRIPTION:
UNT 051 IN LACR 26.0
END DESCRIPTION:
XS GIS Cut Line= 3
      2231385.84     13211172.14      2231328.54     13210771.05
      2230829.58     13209960.24
#Sta/Elev= 30
  4147.8  328.24  4213.7  326.93  4239.8  325.61  4310.5  323.22  4446.1  320.21
  4451.9  319.73  4496.6  319.17  4522.6  318.02  4527.7  318.39  4558.4  317.82
  4563.9  317.27  4716.6  315.64  4927.2  315.01  4933.6  314.54  4992.3  314.05
  4997.6  313.55  5000.3  313.05  5003.6  313.55  5015.8  314.66  5037.3  314.61
  5064.4  315.27  5226.6  320.57  5321.1  324.66  5348.4  327.27  5369.7  326.78
  5385.1  329.11  5407.1  330.04  5464.4  334.17  5501.1  335.98  5505.0  336.75
#Mann=4,-1,0
  4147.8    0.05       0  4997.6    0.03       0  5003.6    0.05       0
  5407.1     0.1       0
Bank Sta=4997.6,5003.6
Exp/Cntr=0.3,0.1

Type RM Length L Ch R = 1,12055,650,650,650
BEGIN DESCRIPTION:
UNT 051 IN LACR 25.0
END DESCRIPTION:
XS GIS Cut Line= 3
      2231885.83     13211125.21      2231479.59     13209958.55
      2231255.64     13209567.96
#Sta/Elev= 30
  4281.7  332.57  4291.3  331.76  4364.7  329.52  4386.8  327.58  4512.9  322.39
  4587.0  320.12  4624.9  317.91  4756.5  314.53  4947.1  312.03  5010.6  312.40
  5015.4  311.57  5018.2  311.07  5021.4  311.57  5049.5  312.70  5063.5  312.70
  5080.6  311.65  5111.7  312.96  5412.0  315.65  5510.5  317.79  5651.5  322.54
  5657.3  323.26  5694.7  324.32  5703.4  325.80  5710.5  326.04  5734.3  325.30
  5806.9  328.50  5841.8  329.03  5871.6  330.48  5887.4  330.46  5967.3  333.23
#Mann=5,-1,0
  4281.7     0.1       0  4291.3    0.05       0  5015.4    0.03       0
  5021.4    0.05       0  5734.3     0.1       0
Bank Sta=5015.4,5021.4
Exp/Cntr=0.3,0.1

Type RM Length L Ch R = 1,11405,405,405,405
BEGIN DESCRIPTION:
UNT 051 IN LACR 23.0
END DESCRIPTION:
XS GIS Cut Line= 3
      2232637.73     13210696.87      2232237.72     13210296.85
      2231587.71     13209496.84
#Sta/Elev= 30
  4434.3  326.67  4773.7  316.28  4858.6  312.57  4982.9  309.47  4985.6  308.97
  4988.9  309.47  4996.5  310.33  5035.9  310.72  5114.2  310.15  5120.7  310.60
  5277.3  311.17  5476.7  314.60  5604.8  319.40  5682.9  323.54  5704.0  325.26
  5753.5  327.27  5760.2  328.15  5831.8  332.40  5889.0  335.36  5902.2  335.32
  5910.1  336.81  5959.7  337.94  5974.0  339.78  5988.4  340.75  5993.2  340.32
  5994.8  340.17  6002.8  341.95  6023.6  342.37  6027.6  343.47  6030.8  343.47
#Mann=4,-1,0
  4434.3    0.05       0  4982.9    0.03       0  4988.9    0.05       0
  5993.2     0.1       0
Bank Sta=4982.9,4988.9
Exp/Cntr=0.3,0.1

Type RM Length L Ch R = 1,11000,550,550,550
BEGIN DESCRIPTION:
UNT 051 IN LACR 22.0
END DESCRIPTION:
XS GIS Cut Line= 2
      2232937.10     13210568.36      2232001.46     13209545.69
#Sta/Elev= 30
  4428.7  322.49  4457.9  320.64  4464.7  321.05  4507.3  319.29  4514.0  319.77
  4564.0  317.98  4585.0  318.25  4627.5  316.62  4676.9  316.24  4825.5  312.28
  4861.2  310.32  4940.8  309.10  4945.8  309.53  4956.9  308.52  4959.7  308.02
  4962.9  308.52  5009.9  309.72  5205.3  309.25  5299.7  310.25  5433.4  314.54
  5533.4  318.58  5540.8  319.98  5561.8  319.61  5571.1  320.55  5582.8  320.85
  5590.2  322.36  5710.4  325.84  5753.0  328.53  5788.1  328.70  5814.8  329.89
#Mann=7,-1,0
  4428.7    0.05       0  4940.8     0.1       0  4956.9    0.07       0
  4962.9     0.1       0  5205.3    0.05       0  5433.4    0.08       0
  5571.1     0.1       0
Bank Sta=4956.9,4962.9
Exp/Cntr=0.3,0.1

Type RM Length L Ch R = 1,10450,561,561,561
BEGIN DESCRIPTION:
UNT 051 IN LACR 21.0
END DESCRIPTION:
XS GIS Cut Line= 3
      2233245.23     13210683.53      2233179.86     13210266.42
      2232694.30     13209376.23
#Sta/Elev= 30
  4327.7  326.79  4477.1  320.92  4506.5  319.17  4539.8  318.37  4547.0  317.45
  4597.4  314.95  4658.4  312.52  4727.8  310.17  4739.3  310.54  4792.2  309.40
  4978.3  306.58  5141.5  307.64  5223.2  305.51  5239.2  306.15  5261.2  305.51
  5288.7  306.11  5293.2  303.69  5295.9  303.19  5299.2  303.69  5310.5  304.18
  5318.9  306.74  5455.4  308.75  5517.4  310.15  5533.6  309.84  5569.9  311.31
  5615.1  312.36  5620.9  313.19  5642.7  313.37  5649.3  314.16  5763.9  316.79
#Mann=6,-1,0
  4327.7    0.05       0  4792.2     0.1       0  5293.2    0.07       0
  5299.2     0.1       0  5455.4    0.05       0  5569.9     0.1       0
Bank Sta=5293.2,5299.2
Exp/Cntr=0.3,0.1

Type RM Length L Ch R = 1,9889,491,491,491
BEGIN DESCRIPTION:
UNT 051 IN LACR 20.0
END DESCRIPTION:
XS GIS Cut Line= 3
      2233603.17     13210571.48      2233652.98     13210154.36
      2233022.60     13209232.09
#Sta/Elev= 30
  4449.7  316.53  4464.4  316.63  4524.9  314.59  4535.1  313.26  4545.0  313.39
  4595.4  311.03  4857.2  304.93  4943.3  304.46  4958.2  303.46  5009.0  302.82
  5051.0  303.23  5072.7  304.24  5109.0  303.77  5122.8  304.40  5266.5  304.63
  5353.0  304.00  5382.9  302.71  5403.8  303.73  5430.7  301.40  5433.4  300.90
  5436.7  301.40  5526.4  303.07  5547.4  304.28  5665.5  307.91  5684.9  309.19
  5741.8  309.99  5849.4  315.42  5864.3  315.49  5986.5  321.20  5986.9  321.23
#Mann=5,-1,0
  4449.7     0.1       0  5430.7    0.07       0  5436.7     0.1       0
  5665.5    0.05       0  5986.5     0.1       0
Bank Sta=5430.7,5436.7
Exp/Cntr=0.3,0.1

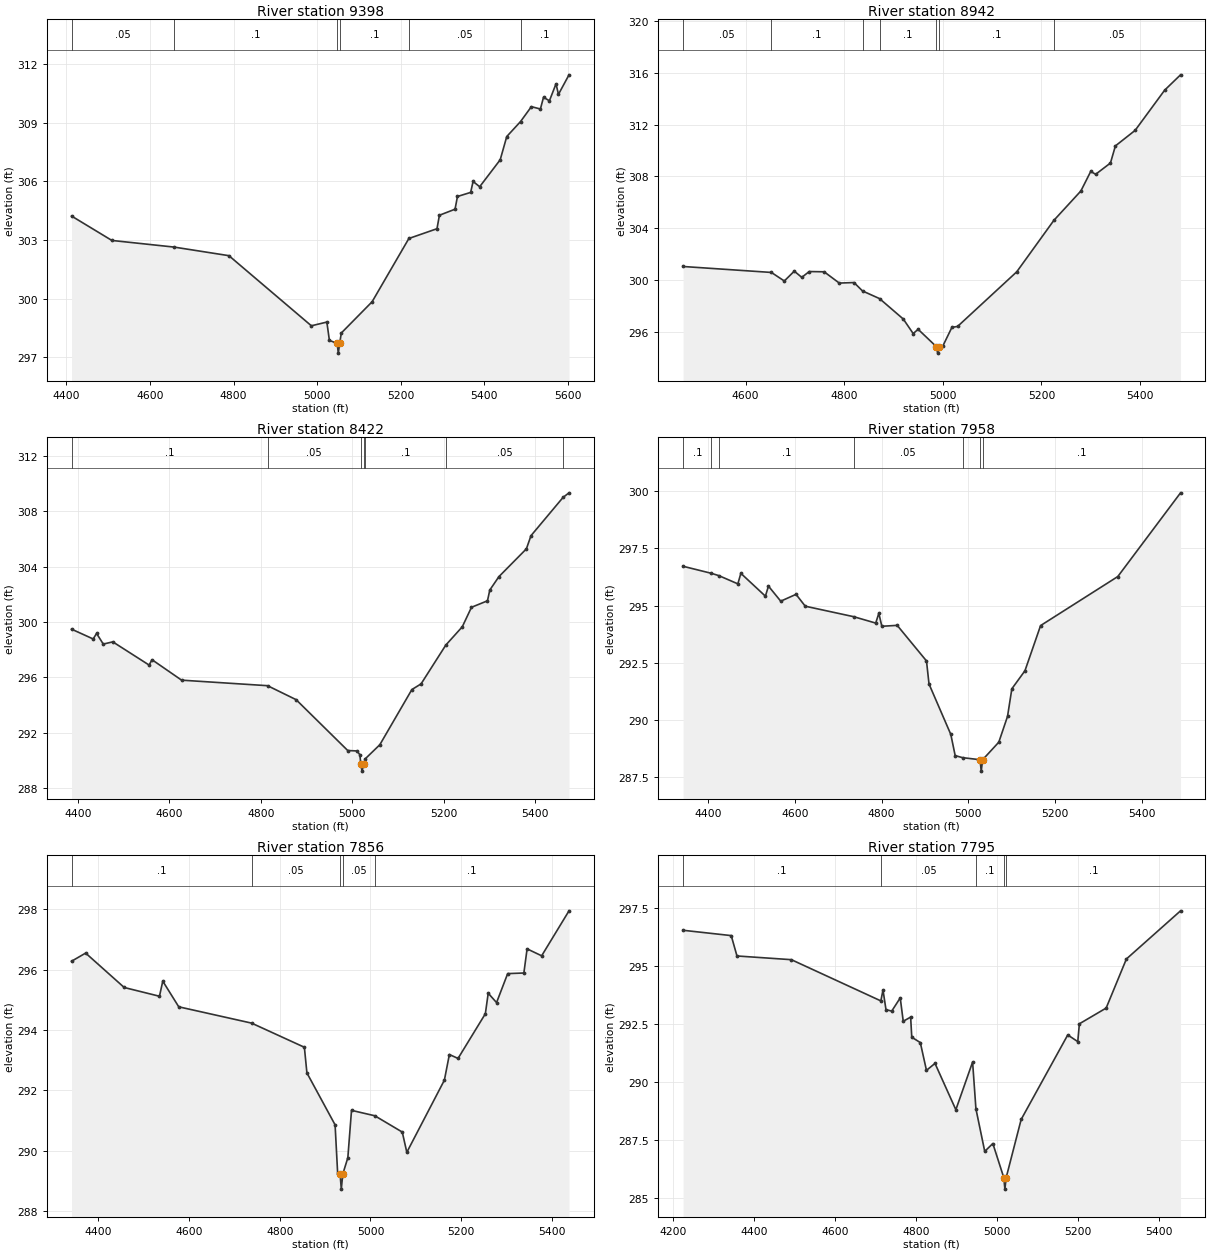
Type RM Length L Ch R = 1,9398,456,456,456
BEGIN DESCRIPTION:
Mapping XS 2a9ce09a
END DESCRIPTION:
XS GIS Cut Line= 3
      2233933.11     13210263.30      2233917.55     13209836.88
      2233537.83     13209173.93
#Sta/Elev= 30
  4412.2  304.23  4508.7  302.98  4657.6  302.64  4788.9  302.20  4986.2  298.61
  5023.3  298.80  5029.4  297.86  5048.0  297.71  5050.7  297.21  5054.0  297.71
  5057.9  298.24  5131.6  299.84  5219.6  303.08  5286.9  303.58  5292.7  304.27
  5330.1  304.58  5335.9  305.23  5367.5  305.44  5373.3  306.00  5389.1  305.73
  5438.2  307.11  5453.9  308.30  5487.0  309.07  5512.8  309.83  5534.4  309.71
  5541.9  310.31  5556.0  310.13  5571.8  311.00  5577.6  310.46  5602.9  311.46
#Mann=6,-1,0
  4412.2    0.05       0  4657.6     0.1       0  5048.0    0.07       0
  5054.0     0.1       0  5219.6    0.05       0  5487.0     0.1       0
Bank Sta=5048,5054
Exp/Cntr=0.3,0.1

Type RM Length L Ch R = 1,8942,520,520,520
BEGIN DESCRIPTION:
UNT 051 IN LACR 19.0
END DESCRIPTION:
XS GIS Cut Line= 3
      2234179.00     13210120.15      2234225.70     13209790.19
      2234216.36     13209114.80
#Sta/Elev= 30
  4473.4  301.05  4652.5  300.59  4678.7  299.93  4698.9  300.69  4714.1  300.21
  4729.2  300.66  4759.5  300.64  4790.1  299.77  4820.0  299.81  4837.3  299.16
  4871.8  298.57  4920.0  296.99  4940.0  295.87  4950.0  296.20  4987.0  294.86
  4989.7  294.36  4993.0  294.86  5000.0  294.90  5018.5  296.35  5030.0  296.42
  5150.0  300.64  5225.2  304.61  5280.0  306.88  5300.0  308.39  5310.0  308.17
  5340.0  309.04  5350.0  310.36  5390.0  311.56  5450.0  314.67  5482.1  315.85
#Mann=7,-1,0
  4473.4    0.05       0  4652.5     0.1       0  4837.3    0.05       0
  4871.8     0.1       0  4987.0    0.07       0  4993.0     0.1       0
  5225.2    0.05       0
Bank Sta=4987,4993
Exp/Cntr=0.3,0.1

Type RM Length L Ch R = 1,8422,464,464,464
BEGIN DESCRIPTION:
UNT 051 IN LACR 18.0
END DESCRIPTION:
XS GIS Cut Line= 4
      2234359.56     13210145.01      2234686.36     13209905.36
      2234726.83     13209345.09      2234726.83     13209223.67
#Sta/Elev= 30
  4385.7  299.49  4433.0  298.78  4440.5  299.18  4455.1  298.41  4476.0  298.57
  4555.5  296.89  4561.7  297.28  4626.5  295.80  4814.5  295.40  4877.0  294.39
  4990.0  290.71  5010.0  290.68  5016.5  290.41  5018.6  289.72  5021.3  289.22
  5024.6  289.72  5028.6  290.12  5060.2  291.13  5130.3  295.12  5150.4  295.53
  5204.6  298.34  5240.6  299.66  5260.7  301.07  5295.7  301.54  5300.8  302.32
  5320.8  303.29  5380.9  305.30  5390.9  306.25  5461.1  309.02  5474.1  309.35
#Mann=7,-1,0
  4385.7     0.1       0  4814.5    0.05       0  5018.6    0.03       0
  5024.6    0.05       0  5028.6     0.1       0  5204.6    0.05       0
  5461.1     0.1       0
Bank Sta=5018.6,5024.6
Exp/Cntr=0.3,0.1

Type RM Length L Ch R = 1,7958,102,102,102
BEGIN DESCRIPTION:
Mapping XS 1f4b1248
END DESCRIPTION:
XS GIS Cut Line= 4
      2234692.58     13210350.46      2235056.76     13209995.62
      2235097.23     13209640.78      2235006.96     13209373.10
#Sta/Elev= 30
  4341.8  296.72  4407.4  296.41  4424.4  296.31  4468.2  295.95  4475.2  296.41
  4531.8  295.41  4538.9  295.85  4567.2  295.19  4602.5  295.49  4623.8  294.97
  4735.6  294.51  4786.4  294.23  4793.6  294.66  4800.5  294.09  4836.0  294.13
  4903.6  292.57  4909.4  291.56  4959.7  289.35  4969.8  288.42  4987.0  288.33
  5027.2  288.24  5029.9  287.74  5033.2  288.24  5070.5  289.01  5090.6  290.14
  5100.6  291.35  5130.8  292.14  5166.9  294.12  5345.1  296.27  5489.9  299.94
#Mann=7,-1,0
  4341.8     0.1       0  4407.4    0.05       0  4424.4     0.1       0
  4735.6    0.05       0  4987.0     0.1       0  5027.2    0.07       0
  5033.2     0.1       0
Bank Sta=5027.2,5033.2
Exp/Cntr=0.3,0.1

Type RM Length L Ch R = 1,7856,61,61,61
BEGIN DESCRIPTION:
Mapping XS 43ecc493
END DESCRIPTION:
XS GIS Cut Line= 5
      2234748.60     13210331.80      2235119.01     13209986.28
      2235175.04     13209871.12      2235181.27     13209731.05
      2235066.62     13209430.49
#Sta/Elev= 30
  4341.1  296.28  4372.2  296.55  4457.2  295.41  4534.9  295.12  4542.2  295.62
  4577.4  294.77  4737.9  294.23  4854.3  293.43  4859.9  292.58  4922.0  290.86
  4927.6  289.27  4933.0  289.23  4935.7  288.73  4939.0  289.23  4950.1  289.77
  4958.2  291.34  5009.6  291.16  5070.1  290.62  5080.1  289.95  5162.9  292.34
  5173.9  293.19  5193.0  293.06  5253.2  294.54  5259.5  295.22  5277.9  294.91
  5302.4  295.87  5338.1  295.89  5345.2  296.69  5377.3  296.46  5437.6  297.95
#Mann=5,-1,0
  4341.1     0.1       0  4737.9    0.05       0  4933.0    0.03       0
  4939.0    0.05       0  5009.6     0.1       0
Bank Sta=4933,4939
Exp/Cntr=0.3,0.1

Type RM Length L Ch R = 1,7795,230,230,230
BEGIN DESCRIPTION:
UNT 051 IN LACR 17.0
END DESCRIPTION:
XS GIS Cut Line= 5
      2234714.37     13210381.59      2235128.35     13210004.96
      2235234.18     13209936.48      2235243.52     13209647.01
      2235103.43     13209435.32
#Sta/Elev= 30
  4224.6  296.55  4343.6  296.32  4357.8  295.44  4492.2  295.28  4713.3  293.50
  4718.6  293.97  4726.0  293.12  4740.2  293.06  4761.2  293.63  4768.6  292.62
  4786.9  292.80  4789.7  291.93  4810.8  291.70  4826.0  290.50  4847.1  290.80
  4898.6  288.80  4940.0  290.86  4948.2  288.84  4970.0  287.00  4990.0  287.34
  5017.0  285.87  5019.8  285.37  5023.0  285.87  5060.0  288.38  5175.1  292.03
  5199.9  291.74  5203.8  292.51  5270.0  293.19  5320.0  295.31  5453.8  297.39
#Mann=5,-1,0
  4224.6     0.1       0  4713.3    0.05       0  4948.2     0.1       0
  5017.0    0.07       0  5023.0     0.1       0
Bank Sta=5017,5023
Exp/Cntr=0.3,0.1

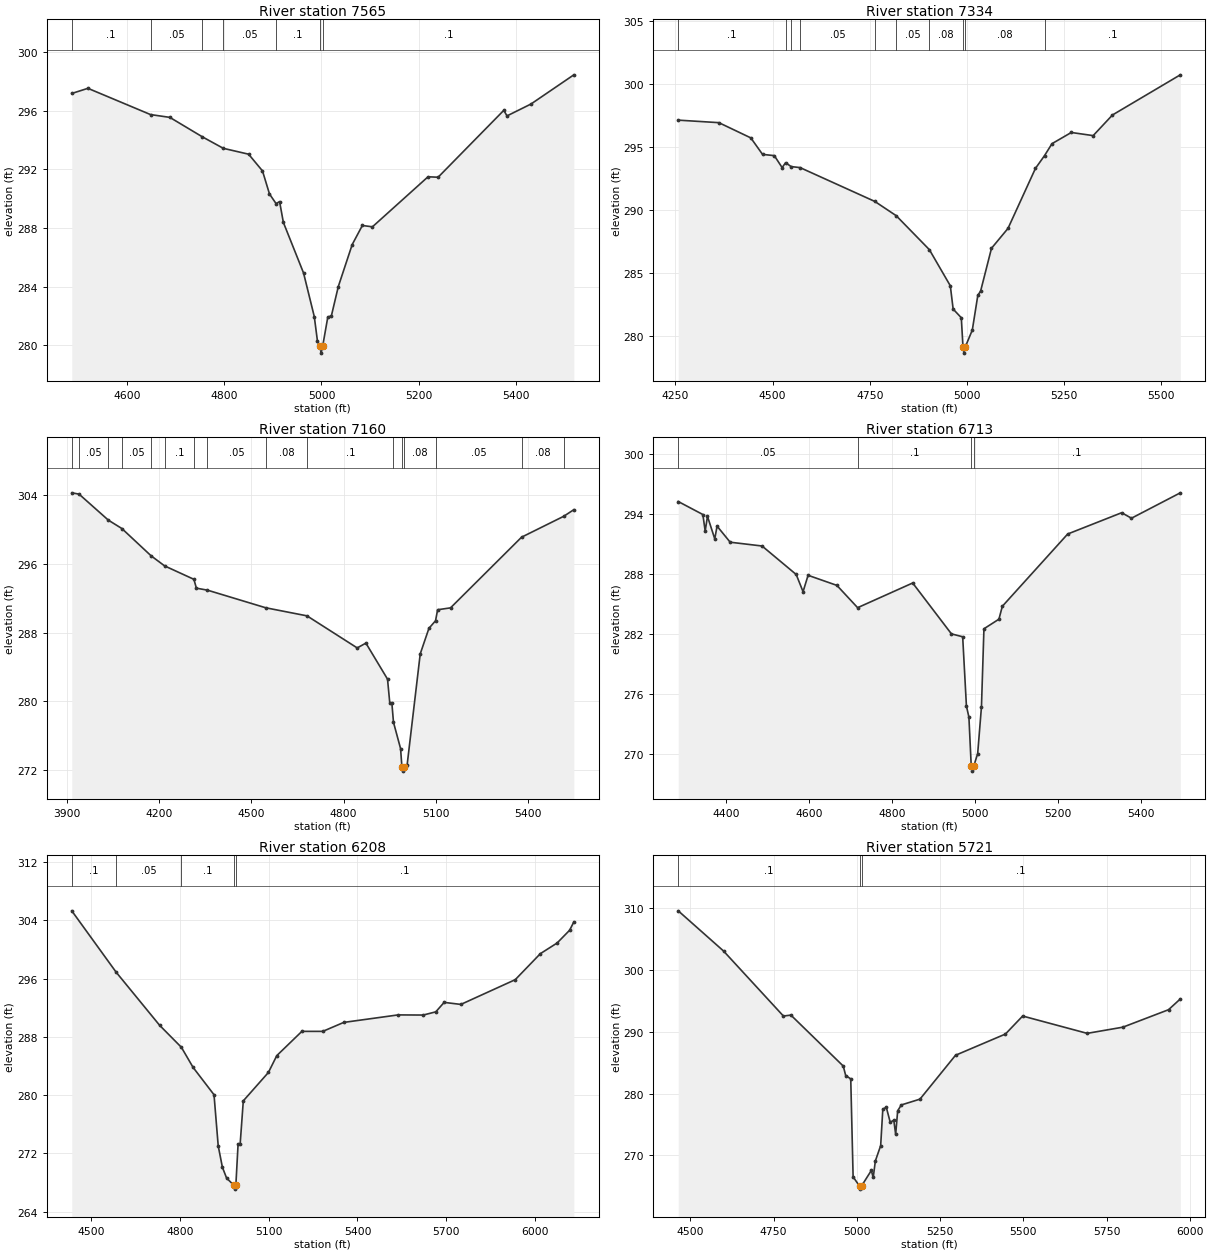
Type RM Length L Ch R = 1,7565,231,231,231
BEGIN DESCRIPTION:
UNT 051 IN LACR 16.0
END DESCRIPTION:
XS GIS Cut Line= 3
      2235641.94     13210260.22      2235557.89     13209930.26
      2235112.81     13209398.03
#Sta/Elev= 30
  4485.6  297.17  4518.9  297.52  4647.9  295.73  4687.6  295.54  4754.8  294.21
  4797.8  293.43  4849.9  293.03  4878.5  291.89  4892.9  290.32  4906.5  289.66
  4913.7  289.80  4921.5  288.38  4963.1  284.93  4985.2  281.96  4991.8  280.27
  4996.6  279.97  4999.3  279.47  5002.6  279.97  5013.0  281.92  5020.4  282.01
  5034.7  284.01  5063.3  286.87  5084.2  288.17  5105.0  288.08  5219.5  291.49
  5240.3  291.46  5375.6  296.02  5382.2  295.64  5431.6  296.45  5519.9  298.44
#Mann=7,-1,0
  4485.6     0.1       0  4647.9    0.05       0  4754.8     0.1       0
  4797.8    0.05       0  4906.5     0.1       0  4996.6    0.07       0
  5002.6     0.1       0
Bank Sta=4996.6,5002.6
Exp/Cntr=0.3,0.1

Type RM Length L Ch R = 1,7334,174,174,174
BEGIN DESCRIPTION:
Mapping XS 4c1f6085
END DESCRIPTION:
XS GIS Cut Line= 3
      2235875.37     13210322.41      2235822.46     13209874.23
      2235243.54     13209264.19
#Sta/Elev= 30
  4257.2  297.12  4361.8  296.92  4444.0  295.71  4474.2  294.40  4504.5  294.30
  4524.6  293.35  4533.6  293.74  4547.8  293.43  4570.8  293.35  4763.3  290.66
  4818.2  289.53  4903.6  286.83  4957.5  283.96  4964.8  282.11  4985.8  281.42
  4990.1  279.11  4992.8  278.61  4996.1  279.11  5014.1  280.44  5028.3  283.20
  5035.5  283.54  5063.5  286.94  5106.0  288.52  5176.7  293.29  5200.0  294.30
  5219.2  295.25  5268.9  296.14  5325.2  295.89  5374.9  297.53  5549.5  300.72
#Mann=10,-1,0
  4257.2     0.1       0  4533.6    0.05       0  4547.8     0.1       0
  4570.8    0.05       0  4763.3    0.08       0  4818.2    0.05       0
  4903.6    0.08       0  4990.1    0.07       0  4996.1    0.08       0
  5200.0     0.1       0
Bank Sta=4990.1,4996.1
Exp/Cntr=0.3,0.1

Type RM Length L Ch R = 1,7160,447,447,447
BEGIN DESCRIPTION:
UNT 051 IN LACR 15.0
END DESCRIPTION:
XS GIS Cut Line= 2
      2236501.00     13210366.90      2235383.62     13209173.84
#Sta/Elev= 30
  3915.2  304.26  3938.9  304.11  4034.4  301.08  4078.2  300.11  4173.6  296.93
  4217.5  295.76  4312.8  294.20  4320.9  293.17  4356.9  292.94  4546.7  290.89
  4681.1  289.95  4844.5  286.22  4872.8  286.78  4943.2  282.59  4950.5  279.83
  4957.4  279.77  4962.6  277.57  4985.7  274.51  4990.0  272.39  4992.7  271.89
  4996.0  272.39  5007.2  272.66  5049.7  285.53  5078.0  288.50  5099.5  289.38
  5106.3  290.66  5148.3  290.88  5379.6  299.10  5516.8  301.53  5549.8  302.30
#Mann=16,-1,0
  3915.2    0.08       0  3938.9    0.05       0  4034.4    0.08       0
  4078.2    0.05       0  4173.6    0.08       0  4217.5     0.1       0
  4312.8    0.08       0  4356.9    0.05       0  4546.7    0.08       0
  4681.1     0.1       0  4962.6    0.08       0  4990.0    0.07       0
  4996.0    0.08       0  5099.5    0.05       0  5379.6    0.08       0
  5516.8     0.1       0
Bank Sta=4990,4996
Exp/Cntr=0.3,0.1

Type RM Length L Ch R = 1,6713,505,505,505
BEGIN DESCRIPTION:
UNT 051 IN LACR 14.0
END DESCRIPTION:
XS GIS Cut Line= 3
      2236429.41     13210060.95      2236202.20     13209556.74
      2235841.16     13209008.95
#Sta/Elev= 30
  4285.0  295.25  4344.3  293.95  4349.9  292.29  4355.4  293.77  4373.0  291.51
  4378.5  292.79  4410.1  291.18  4486.9  290.80  4569.1  287.95  4585.6  286.23
  4597.7  287.87  4667.1  286.86  4717.0  284.63  4849.6  287.10  4942.9  282.01
  4970.0  281.72  4979.0  274.80  4985.0  273.68  4990.6  268.78  4993.3  268.28
  4996.6  268.78  5006.1  270.03  5015.2  274.70  5021.2  282.52  5057.3  283.48
  5065.5  284.77  5222.9  292.00  5352.9  294.13  5376.5  293.58  5494.1  296.12
#Mann=4,-1,0
  4285.0    0.05       0  4717.0     0.1       0  4990.6    0.07       0
  4996.6     0.1       0
Bank Sta=4990.6,4996.6
Exp/Cntr=0.3,0.1

Type RM Length L Ch R = 1,6208,487,487,487
BEGIN DESCRIPTION:
UNT 051 IN LACR 13.0
END DESCRIPTION:
XS GIS Cut Line= 3
      2236987.73     13209746.87      2236587.72     13209346.85
      2235787.70     13208546.83
#Sta/Elev= 30
  4434.3  305.31  4584.2  296.89  4731.3  289.59  4804.9  286.57  4844.4  283.81
  4915.1  280.06  4929.3  273.04  4943.4  270.11  4957.6  268.62  4982.9  267.60
  4985.6  267.10  4988.9  267.60  4996.5  273.31  5003.5  273.31  5014.1  279.22
  5099.0  283.12  5127.3  285.43  5212.1  288.76  5282.8  288.76  5353.6  289.99
  5537.4  291.02  5622.3  291.00  5664.7  291.44  5693.0  292.74  5749.5  292.46
  5933.4  295.86  6018.2  299.43  6074.8  300.89  6117.2  302.65  6131.4  303.79
#Mann=5,-1,0
  4434.3     0.1       0  4584.2    0.05       0  4804.9     0.1       0
  4982.9    0.07       0  4988.9     0.1       0
Bank Sta=4982.9,4988.9
Exp/Cntr=0.3,0.1

Type RM Length L Ch R = 1,5721,469,469,469
BEGIN DESCRIPTION:
UNT 051 IN LACR 12.0
END DESCRIPTION:
XS GIS Cut Line= 3
      2237368.39     13209280.12      2236443.90     13208824.38
      2236053.96     13208551.43
#Sta/Elev= 30
  4464.1  309.53  4600.0  303.04  4779.7  292.53  4802.2  292.68  4959.4  284.44
  4966.6  282.92  4981.8  282.37  4988.9  266.54  5008.1  265.06  5010.9  264.56
  5014.1  265.06  5043.6  267.58  5049.2  266.44  5055.7  269.12  5071.6  271.59
  5078.0  277.46  5088.5  277.79  5100.3  275.35  5111.0  275.70  5116.6  273.40
  5122.6  277.21  5133.4  278.16  5189.5  279.10  5296.2  286.19  5446.0  289.62
  5497.7  292.53  5691.3  289.73  5798.5  290.73  5935.4  293.55  5970.8  295.29
#Mann=3,-1,0
  4464.1     0.1       0  5008.1    0.07       0  5014.1     0.1       0
Bank Sta=5008.1,5014.1
Exp/Cntr=0.3,0.1