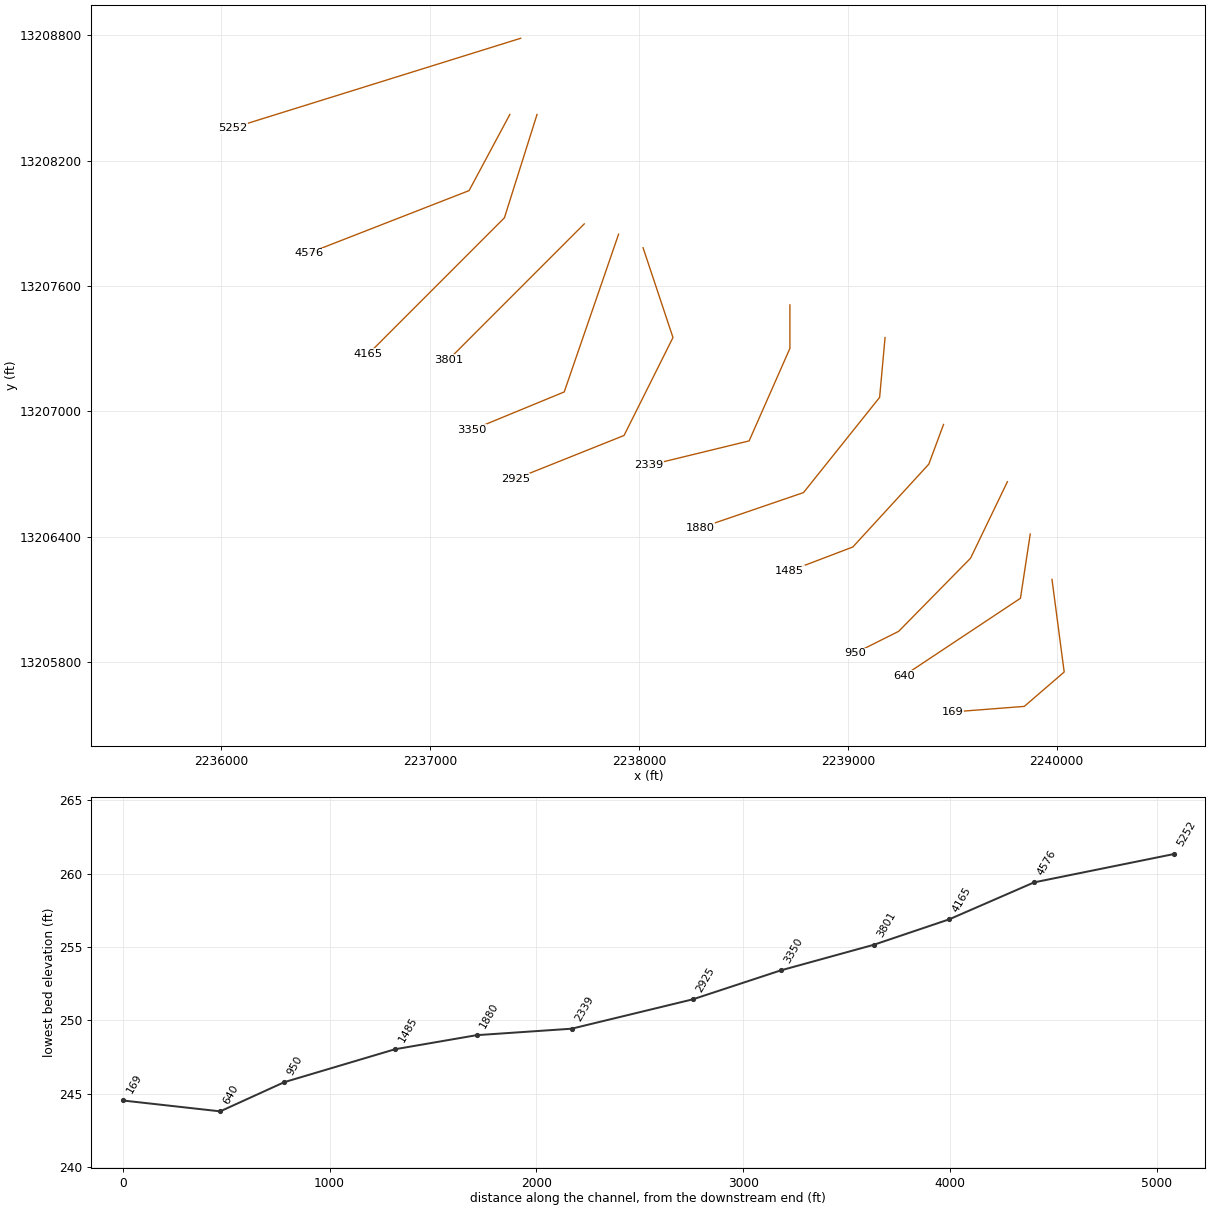
HEC-RAS study UNT 051 IN LACR.prj: UNT 051 IN LACR Base Level Engineering

--- UNT 051 IN LACR.g01 (geometry) --- (continued)

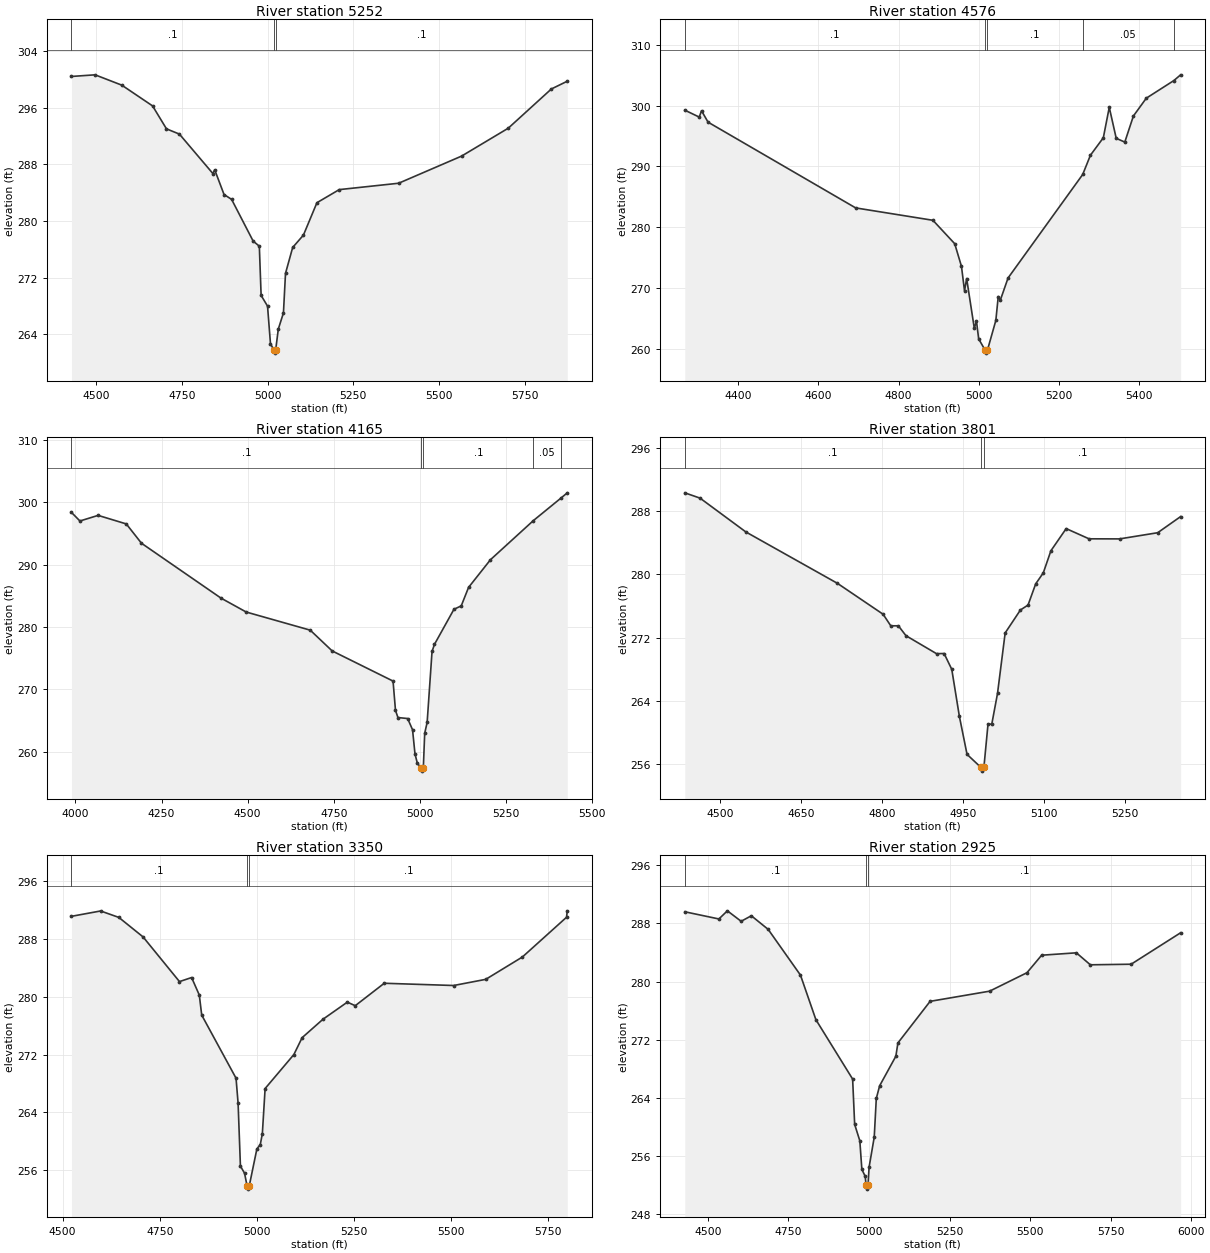
Type RM Length L Ch R = 1,5252,676,676,676
BEGIN DESCRIPTION:
UNT 051 IN LACR 11.0
END DESCRIPTION:
XS GIS Cut Line= 2
      2237433.48     13208785.32      2236053.32     13208355.65
#Sta/Elev= 30
  4428.4  300.40  4497.3  300.63  4575.2  299.17  4664.9  296.24  4705.4  293.00
  4743.1  292.26  4840.7  286.69  4846.0  287.22  4873.2  283.73  4895.3  283.04
  4958.1  277.15  4976.1  276.43  4981.3  269.48  5000.0  267.97  5008.6  262.65
  5017.9  261.83  5020.7  261.33  5023.9  261.83  5031.4  264.72  5046.4  267.01
  5052.4  272.59  5073.3  276.25  5104.7  278.00  5144.0  282.57  5209.0  284.42
  5382.2  285.32  5565.6  289.15  5701.7  293.09  5827.4  298.63  5873.9  299.73
#Mann=3,-1,0
  4428.4     0.1       0  5017.9    0.07       0  5023.9     0.1       0
Bank Sta=5017.9,5023.9
Exp/Cntr=0.3,0.1

Type RM Length L Ch R = 1,4576,411,411,411
BEGIN DESCRIPTION:
UNT 051 IN LACR 10.0
END DESCRIPTION:
XS GIS Cut Line= 3
      2237381.38     13208420.70      2237186.09     13208056.16
      2236417.86     13207756.68
#Sta/Elev= 30
  4266.2  299.24  4302.3  298.10  4308.0  299.14  4324.3  297.27  4692.9  283.21
  4885.8  281.18  4940.2  277.34  4957.1  273.62  4964.7  269.61  4970.0  271.63
  4989.2  263.45  4994.5  264.69  5000.0  261.74  5016.0  259.90  5018.8  259.40
  5022.0  259.90  5042.9  264.76  5048.9  268.68  5054.3  268.12  5073.4  271.72
  5259.8  288.69  5279.1  291.85  5311.3  294.71  5326.1  299.70  5343.5  294.62
  5364.9  294.00  5386.4  298.28  5418.6  301.20  5487.4  304.09  5504.3  305.03
#Mann=5,-1,0
  4266.2     0.1       0  5016.0    0.07       0  5022.0     0.1       0
  5259.8    0.05       0  5487.4     0.1       0
Bank Sta=5016,5022
Exp/Cntr=0.3,0.1

Type RM Length L Ch R = 1,4165,364,364,364
BEGIN DESCRIPTION:
UNT 051 IN LACR 9.0
END DESCRIPTION:
XS GIS Cut Line= 3
      2237511.60     13208420.70      2237355.36     13207925.95
      2236704.28     13207274.87
#Sta/Elev= 30
  3988.5  298.40  4013.1  297.02  4065.9  297.92  4147.7  296.55  4191.8  293.45
  4422.5  284.65  4495.9  282.41  4681.8  279.50  4745.4  276.17  4922.2  271.33
  4929.3  266.62  4936.4  265.48  4964.6  265.32  4978.8  263.52  4985.9  259.64
  4992.9  258.12  5004.1  257.38  5006.8  256.88  5010.1  257.38  5014.1  262.95
  5021.2  264.70  5035.4  276.08  5042.4  277.22  5099.0  282.85  5120.2  283.40
  5141.4  286.36  5205.1  290.81  5329.5  297.08  5408.9  300.66  5428.1  301.54
#Mann=5,-1,0
  3988.5     0.1       0  5004.1    0.07       0  5010.1     0.1       0
  5329.5    0.05       0  5408.9     0.1       0
Bank Sta=5004.1,5010.1
Exp/Cntr=0.3,0.1

Type RM Length L Ch R = 1,3801,451,451,451
BEGIN DESCRIPTION:
UNT 051 IN LACR 8.0
END DESCRIPTION:
XS GIS Cut Line= 3
      2237737.73     13207896.87      2237337.72     13207496.85
      2237087.69     13207246.82
#Sta/Elev= 30
  4434.3  290.31  4462.6  289.64  4547.5  285.37  4717.2  278.88  4802.0  274.97
  4816.2  273.51  4830.3  273.51  4844.4  272.26  4901.0  269.99  4915.1  270.01
  4929.3  268.01  4943.4  262.07  4957.6  257.27  4982.9  255.65  4985.6  255.15
  4988.9  255.65  4996.5  261.09  5003.5  261.09  5014.1  264.96  5028.3  272.61
  5056.6  275.51  5070.7  276.13  5084.9  278.81  5099.0  280.20  5113.1  282.99
  5141.4  285.79  5183.8  284.50  5240.4  284.49  5311.1  285.27  5353.6  287.31
#Mann=3,-1,0
  4434.3     0.1       0  4982.9    0.07       0  4988.9     0.1       0
Bank Sta=4982.9,4988.9
Exp/Cntr=0.3,0.1

Type RM Length L Ch R = 1,3350,425,425,425
BEGIN DESCRIPTION:
UNT 051 IN LACR 7.0
END DESCRIPTION:
XS GIS Cut Line= 3
      2237902.22     13207847.80      2237641.81     13207092.61
      2237200.95     13206911.08
#Sta/Elev= 30
  4523.0  291.10  4598.0  291.84  4644.9  290.95  4707.3  288.25  4800.9  282.08
  4832.1  282.64  4851.9  280.22  4858.1  277.45  4946.4  268.73  4951.7  265.27
  4957.7  256.58  4968.3  255.60  4974.6  253.90  4977.3  253.40  4980.6  253.90
  5000.0  258.95  5008.8  259.56  5014.1  261.07  5021.2  267.30  5095.2  272.00
  5116.4  274.33  5170.1  276.88  5232.7  279.24  5253.1  278.75  5327.7  281.85
  5506.2  281.54  5588.8  282.39  5683.1  285.48  5796.6  290.97  5798.6  291.86
#Mann=3,-1,0
  4523.0     0.1       0  4974.6    0.07       0  4980.6     0.1       0
Bank Sta=4974.6,4980.6
Exp/Cntr=0.3,0.1

Type RM Length L Ch R = 1,2925,586,586,586
BEGIN DESCRIPTION:
UNT 051 IN LACR 6.0
END DESCRIPTION:
XS GIS Cut Line= 4
      2238019.43     13207782.68      2238162.65     13207353.03
      2237928.27     13206884.28      2237407.46     13206675.96
#Sta/Elev= 30
  4428.4  289.61  4534.2  288.62  4560.5  289.74  4603.2  288.30  4634.8  289.06
  4687.0  287.19  4787.2  280.89  4835.1  274.75  4949.0  266.58  4955.3  260.34
  4971.3  258.08  4977.6  254.15  4988.1  253.18  4990.7  251.93  4993.4  251.43
  4996.7  251.93  5000.0  254.44  5016.0  258.58  5022.4  263.91  5032.8  265.66
  5083.1  269.73  5089.4  271.55  5189.3  277.28  5373.8  278.68  5489.7  281.22
  5535.2  283.63  5642.9  283.96  5686.3  282.31  5812.8  282.39  5966.3  286.72
#Mann=3,-1,0
  4428.4     0.1       0  4990.7    0.07       0  4996.7     0.1       0
Bank Sta=4990.7,4996.7
Exp/Cntr=0.3,0.1

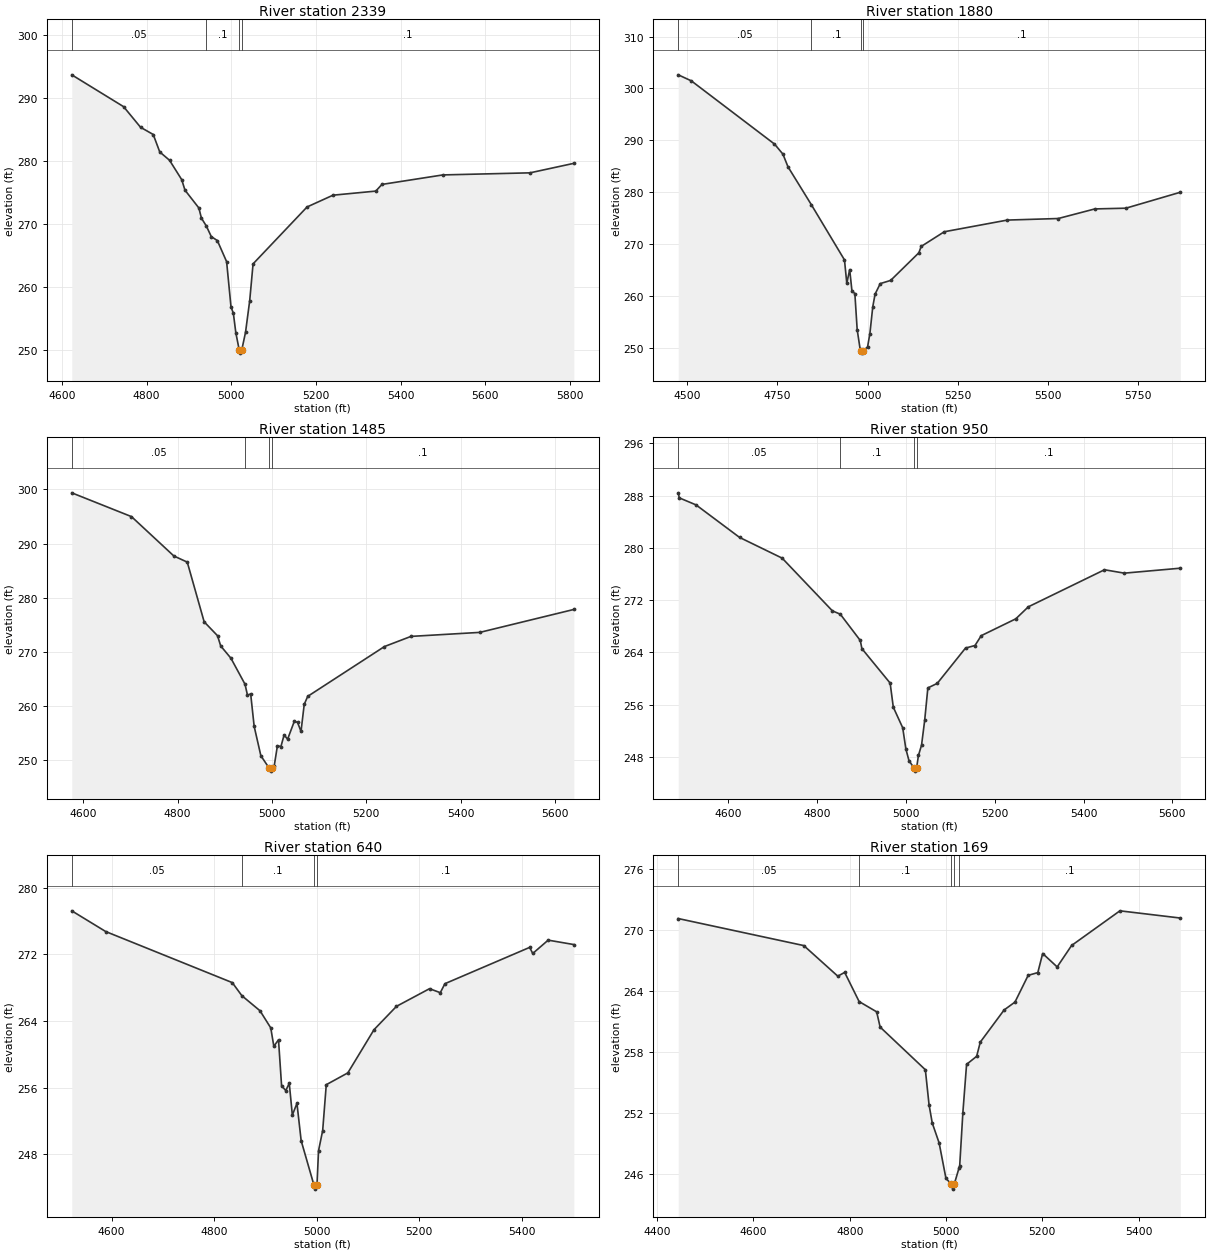
Type RM Length L Ch R = 1,2339,459,459,459
BEGIN DESCRIPTION:
UNT 051 IN LACR 5.0
END DESCRIPTION:
XS GIS Cut Line= 4
      2238722.54     13207509.33      2238722.54     13207300.95
      2238527.23     13206858.24      2238047.09     13206741.45
#Sta/Elev= 30
  4623.2  293.64  4745.7  288.58  4785.7  285.31  4815.7  284.16  4831.1  281.39
  4854.2  280.07  4883.0  276.99  4890.7  275.32  4923.5  272.49  4929.6  270.87
  4941.2  269.62  4952.9  267.94  4967.2  267.31  4989.1  263.96  4999.5  256.75
  5005.0  255.78  5010.9  252.66  5018.9  249.93  5021.6  249.43  5024.9  249.93
  5033.8  252.74  5043.7  257.79  5051.6  263.61  5179.2  272.65  5240.5  274.52
  5341.6  275.17  5356.1  276.23  5500.2  277.74  5706.0  278.07  5809.6  279.58
#Mann=4,-1,0
  4623.2    0.05       0  4941.2     0.1       0  5018.9    0.07       0
  5024.9     0.1       0
Bank Sta=5018.9,5024.9
Exp/Cntr=0.3,0.1

Type RM Length L Ch R = 1,1880,395,395,395
BEGIN DESCRIPTION:
UNT 051 IN LACR 4.0
END DESCRIPTION:
XS GIS Cut Line= 4
      2239178.27     13207353.00      2239152.23     13207066.57
      2238787.65     13206610.84      2238293.30     13206441.73
#Sta/Elev= 30
  4474.6  302.62  4510.9  301.46  4741.8  289.28  4765.2  287.34  4779.2  284.90
  4844.3  277.57  4936.1  266.95  4942.5  262.44  4950.5  265.09  4956.9  260.92
  4964.9  260.48  4971.3  253.53  4979.3  249.86  4982.7  249.49  4985.5  248.99
  4988.7  249.49  5000.2  250.20  5006.6  252.75  5014.6  257.92  5021.0  260.36
  5035.4  262.39  5064.2  263.00  5142.6  268.33  5149.0  269.55  5213.1  272.38
  5388.0  274.63  5529.4  274.93  5631.1  276.78  5717.2  276.92  5868.3  279.99
#Mann=4,-1,0
  4474.6    0.05       0  4844.3     0.1       0  4982.7    0.07       0
  4988.7     0.1       0
Bank Sta=4982.7,4988.7
Exp/Cntr=0.3,0.1

Type RM Length L Ch R = 1,1485,535,535,535
BEGIN DESCRIPTION:
UNT 051 IN LACR 3.0
END DESCRIPTION:
XS GIS Cut Line= 4
      2239458.23     13206936.74      2239387.72     13206746.85
      2239024.07     13206350.60      2238721.47     13206235.32
#Sta/Elev= 30
  4575.6  299.36  4702.2  294.97  4792.0  287.71  4820.4  286.58  4856.2  275.57
  4884.5  273.01  4891.3  271.12  4912.9  268.86  4942.8  264.06  4948.0  262.05
  4954.8  262.27  4962.2  256.29  4976.4  250.87  4994.4  248.53  4997.1  248.03
  5000.4  248.53  5004.8  249.04  5011.5  252.72  5018.9  252.56  5025.7  254.70
  5033.1  253.92  5047.3  257.22  5054.1  257.03  5061.5  255.35  5068.3  260.34
  5075.7  261.82  5238.4  271.01  5294.6  272.88  5440.5  273.62  5639.8  277.85
#Mann=4,-1,0
  4575.6    0.05       0  4942.8     0.1       0  4994.4    0.07       0
  5000.4     0.1       0
Bank Sta=4994.4,5000.4
Exp/Cntr=0.3,0.1

Type RM Length L Ch R = 1,950,310,310,310
BEGIN DESCRIPTION:
UNT 051 IN LACR 2.0
END DESCRIPTION:
XS GIS Cut Line= 4
      2239764.23     13206662.96      2239587.72     13206296.85
      2239243.38     13205946.78      2239035.04     13205842.61
#Sta/Elev= 30
  4487.5  288.44  4489.8  287.67  4527.6  286.59  4625.5  281.61  4721.5  278.43
  4834.6  270.35  4852.4  269.84  4897.4  265.81  4901.0  264.56  4964.6  259.28
  4971.7  255.59  4992.9  252.43  5000.0  249.19  5007.0  247.40  5018.2  246.29
  5020.9  245.79  5024.2  246.29  5028.3  248.19  5035.3  249.77  5042.4  253.59
  5049.5  258.54  5070.7  259.24  5134.3  264.65  5155.6  265.04  5169.7  266.55
  5247.5  269.13  5275.7  270.97  5447.2  276.65  5491.9  276.13  5617.9  276.89
#Mann=4,-1,0
  4487.5    0.05       0  4852.4     0.1       0  5018.2    0.07       0
  5024.2     0.1       0
Bank Sta=5018.2,5024.2
Exp/Cntr=0.3,0.1

Type RM Length L Ch R = 1,640,471,471,471
BEGIN DESCRIPTION:
Mapping XS 5bc9c98c
END DESCRIPTION:
XS GIS Cut Line= 3
      2239873.54     13206412.38      2239826.66     13206105.07
      2239269.35     13205735.27
#Sta/Elev= 30
  4522.4  277.22  4588.7  274.73  4835.6  268.60  4854.3  267.03  4889.7  265.22
  4910.7  263.16  4916.7  260.95  4925.8  261.74  4931.8  256.21  4940.0  255.63
  4946.8  256.52  4952.8  252.69  4961.8  254.10  4970.0  249.62  4994.9  244.30
  4997.7  243.80  5000.9  244.30  5003.9  248.41  5012.0  250.84  5019.0  256.34
  5061.1  257.76  5112.2  262.95  5156.0  265.75  5220.5  267.87  5241.5  267.39
  5250.5  268.47  5415.9  272.83  5421.9  272.10  5452.0  273.70  5502.1  273.17
#Mann=4,-1,0
  4522.4    0.05       0  4854.3     0.1       0  4994.9    0.07       0
  5000.9     0.1       0
Bank Sta=4994.9,5000.9
Exp/Cntr=0.3,0.1

Type RM Length L Ch R = 1,169,0,0,0
BEGIN DESCRIPTION:
UNT 051 IN LACR 1.0
END DESCRIPTION:
XS GIS Cut Line= 4
      2239977.69     13206195.36      2240036.08     13205752.14
      2239845.01     13205587.60      2239502.74     13205561.07
#Sta/Elev= 30
  4444.0  271.17  4704.7  268.51  4775.3  265.50  4789.6  265.87  4819.6  263.00
  4856.0  261.99  4863.2  260.49  4957.1  256.29  4964.8  252.84  4971.4  251.05
  4985.7  249.09  4999.9  245.59  5011.2  245.04  5013.9  244.54  5017.2  245.04
  5027.2  246.65  5028.4  246.82  5035.0  252.06  5042.7  256.82  5063.6  257.61
  5071.2  259.01  5120.6  262.17  5143.2  262.95  5170.6  265.58  5190.6  265.85
  5200.7  267.73  5230.8  266.41  5260.8  268.52  5361.1  271.93  5486.5  271.22
#Mann=5,-1,0
  4444.0    0.05       0  4819.6     0.1       0  5011.2    0.07       0
  5017.2     0.1       0  5027.2     0.1       0
Bank Sta=5011.2,5017.2
Exp/Cntr=0.3,0.1

Chan Stop Cuts=-1