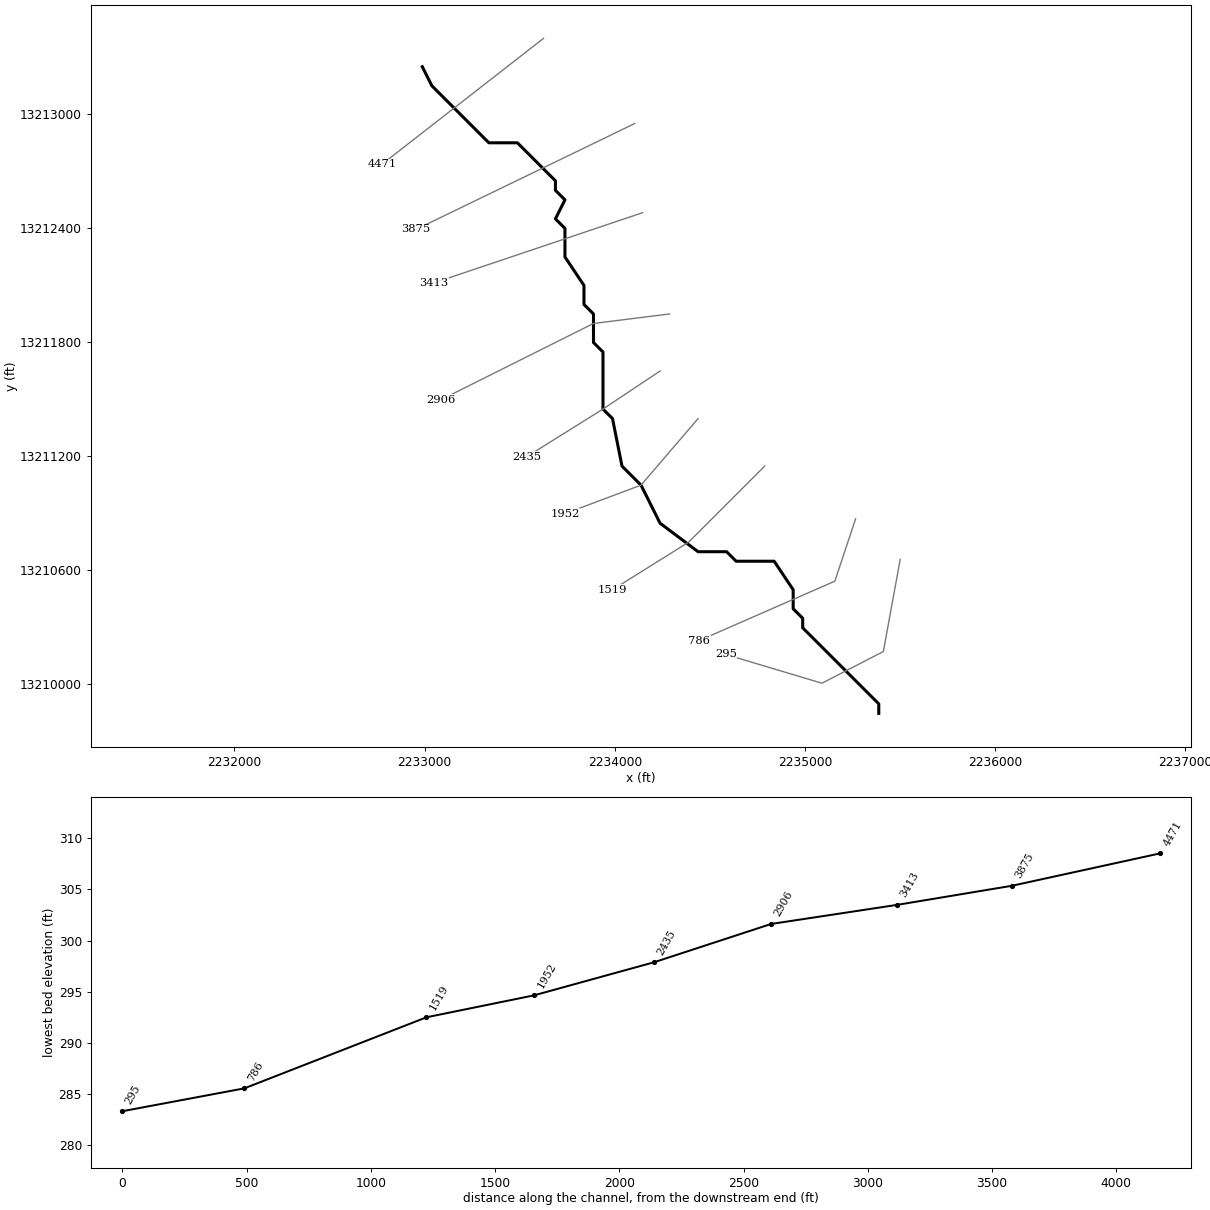
--- UNT 052 IN LACR.prj (project) ---

Proj Title=UNT 052 IN LACR Base Level Engineering
Current Plan=p01
Default Exp/Contr=0.3,0.1
English Units
Geom File=g01
Flow File=f01
Plan File=p01
Y Axis Title=Elevation
X Axis Title(PF)=Main Channel Distance
X Axis Title(XS)=Station
BEGIN DESCRIPTION:
UNT 052 IN LACR
END DESCRIPTION:
DSS Export Rating Curves= 0
DSS Export Rating Curve Sorted= 0
DSS Export Volume Flow Curves= 0
DXF OffsetX= 0
DXF OffsetY= 0
DXF ScaleX= 1
DXF ScaleY= 10

--- UNT 052 IN LACR.p01 (plan) ---

Plan Title=Multiple Run
Short Identifier=Multiple
Geom File=g01
Flow File=f01
Subcritical Flow
K Sum by GR= 0
Std Step Tol= 0.01
Critical Tol= 0.01
Num of Std Step Trials= 20
Max Error Tol= 0.3
Flow Tol Ratio= 0.001
Split Flow NTrial= 30
Split Flow Tol= 0.02
Split Flow Ratio= 0.02
Log Output Level= 0
Friction Slope Method= 1
Unsteady Friction Slope Method= 2
Unsteady Bridges Friction Slope Method= 1
Parabolic Critical Depth
Global Vel Dist=  1 , 1 , 1
Global Log Level= 0
CheckData=True
Encroach Param= -1, 0, 0, 0
BEGIN DESCRIPTION:
Multiple Run
END DESCRIPTION:

--- UNT 052 IN LACR.f01 (steady flow) ---

Flow Title=Multiple
Program Version=4.10
Number of Profiles= 7
Profile Names=10-year,25-year,50-year,1pct_min,100-year,1pct_plu,500-year
River Rch & RM=UNT 052 IN LACR,Reach-1         ,4471
     290     408     509     466     631     853     985
Boundary for River Rch & Prof#=UNT 052 IN LACR,Reach-1         , 1
Up Type= 0
Dn Type= 3
Dn Slope=0.007
Boundary for River Rch & Prof#=UNT 052 IN LACR,Reach-1         , 2
Up Type= 0
Dn Type= 3
Dn Slope=0.007
Boundary for River Rch & Prof#=UNT 052 IN LACR,Reach-1         , 3
Up Type= 0
Dn Type= 3
Dn Slope=0.007
Boundary for River Rch & Prof#=UNT 052 IN LACR,Reach-1         , 4
Up Type= 0
Dn Type= 3
Dn Slope=0.007
Boundary for River Rch & Prof#=UNT 052 IN LACR,Reach-1         , 5
Up Type= 0
Dn Type= 3
Dn Slope=0.007
Boundary for River Rch & Prof#=UNT 052 IN LACR,Reach-1         , 6
Up Type= 0
Dn Type= 3
Dn Slope=0.007
Boundary for River Rch & Prof#=UNT 052 IN LACR,Reach-1         , 7
Up Type= 0
Dn Type= 3
Dn Slope=0.007
DSS Import GetInterval= 0
DSS Import GetPeak= 0
DSS Import FillOption= 0

--- UNT 052 IN LACR.g01 (geometry) ---

Geom Title=Existing Conditions

River Reach=UNT 052 IN LACR,Reach-1
Reach XY= 30
      2232987.72     13213246.85      2233037.72     13213146.86
      2233337.72     13212846.85      2233487.72     13212846.85
      2233687.72     13212646.86      2233687.72     13212596.85
      2233737.72     13212546.85      2233687.72     13212446.85
      2233737.72     13212396.85      2233737.72     13212246.85
      2233837.72     13212096.85      2233837.72     13211996.86
      2233887.72     13211946.85      2233887.72     13211796.85
      2233937.72     13211746.85      2233937.72     13211446.85
      2233987.72     13211396.85      2234037.72     13211146.85
      2234137.72     13211046.85      2234237.72     13210846.86
      2234437.72     13210696.86      2234587.72     13210696.86
      2234637.72     13210646.85      2234837.72     13210646.85
      2234937.72     13210496.85      2234937.72     13210396.85
      2234987.72     13210346.86      2234987.72     13210296.85
      2235387.72     13209896.85      2235387.72     13209846.85

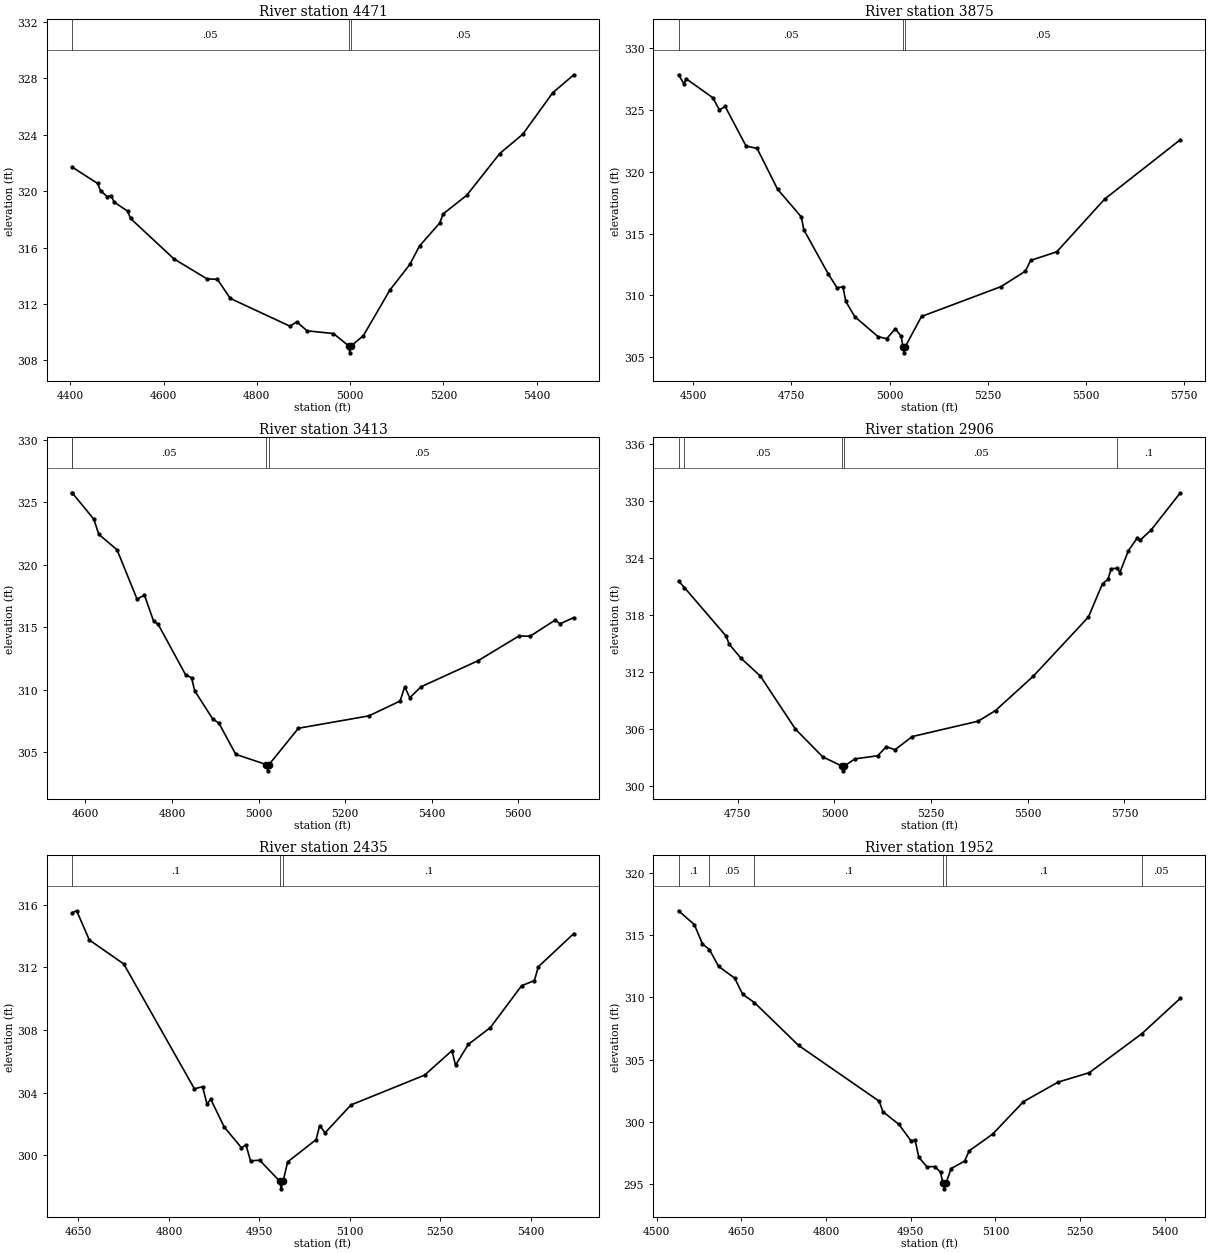
Type RM Length L Ch R = 1,4471,596,596,596
BEGIN DESCRIPTION:
UNT 052 IN LACR 8.0
END DESCRIPTION:
XS GIS Cut Line= 2
      2233625.41     13213396.04      2232776.47     13212734.60
#Sta/Elev= 30
  4403.7  321.71  4458.6  320.54  4464.9  320.01  4479.4  319.61  4487.5  319.68
  4493.9  319.22  4522.8  318.58  4529.1  318.06  4622.3  315.19  4692.9  313.78
  4715.5  313.74  4743.0  312.39  4871.1  310.42  4885.6  310.73  4907.8  310.09
  4964.3  309.90  4996.6  309.03  4999.3  308.53  5002.6  309.03  5028.5  309.75
  5085.3  312.98  5128.1  314.80  5148.9  316.11  5192.3  317.74  5199.4  318.38
  5250.1  319.70  5320.8  322.66  5370.5  324.04  5434.7  326.98  5479.9  328.25
#Mann=3,-1,0
  4403.7    0.05       0  4996.6    0.03       0  5002.6    0.05       0
Bank Sta=4996.6,5002.6
Exp/Cntr=0.3,0.1

Type RM Length L Ch R = 1,3875,462,462,462
BEGIN DESCRIPTION:
UNT 052 IN LACR 7.0
END DESCRIPTION:
XS GIS Cut Line= 2
      2234104.58     13212948.13      2232954.58     13212391.34
#Sta/Elev= 30
  4462.4  327.84  4476.2  327.11  4481.7  327.52  4549.5  325.99  4566.5  325.00
  4581.1  325.28  4634.3  322.08  4662.4  321.89  4714.5  318.59  4775.3  316.34
  4781.1  315.33  4843.1  311.77  4865.7  310.63  4881.1  310.69  4888.3  309.52
  4910.9  308.29  4970.0  306.68  4992.2  306.50  5014.4  307.31  5029.3  306.69
  5033.7  305.86  5036.4  305.36  5039.7  305.86  5081.1  308.30  5283.3  310.71
  5345.5  311.96  5358.9  312.83  5425.5  313.53  5547.7  317.80  5740.1  322.59
#Mann=3,-1,0
  4462.4    0.05       0  5033.7    0.03       0  5039.7    0.05       0
Bank Sta=5033.7,5039.7
Exp/Cntr=0.3,0.1

Type RM Length L Ch R = 1,3413,507,507,507
BEGIN DESCRIPTION:
UNT 052 IN LACR 6.0
END DESCRIPTION:
XS GIS Cut Line= 2
      2234146.21     13212479.37      2233047.26     13212109.58
#Sta/Elev= 30
  4569.0  325.75  4569.2  325.75  4619.4  323.63  4630.7  322.42  4672.9  321.19
  4719.2  317.23  4736.2  317.57  4757.3  315.48  4767.9  315.22  4831.2  311.19
  4845.2  310.93  4852.3  309.90  4894.5  307.62  4908.2  307.32  4947.2  304.81
  5018.1  303.99  5020.9  303.49  5024.1  303.99  5092.0  306.90  5254.8  307.89
  5327.1  309.08  5337.6  310.22  5349.3  309.34  5375.5  310.22  5506.8  312.30
  5601.4  314.28  5627.5  314.27  5685.3  315.56  5696.4  315.26  5728.5  315.76
#Mann=4,-1,0
  4569.0     0.1       0  4569.2    0.05       0  5018.1    0.03       0
  5024.1    0.05       0
Bank Sta=5018.1,5024.1
Exp/Cntr=0.3,0.1

Type RM Length L Ch R = 1,2906,471,471,471
BEGIN DESCRIPTION:
UNT 052 IN LACR 5.0
END DESCRIPTION:
XS GIS Cut Line= 3
      2234287.71     13211946.85      2233887.72     13211896.85
      2233087.74     13211496.87
#Sta/Elev= 30
  4596.9  321.62  4612.3  320.91  4720.3  315.79  4727.9  314.95  4758.1  313.49
  4808.5  311.60  4899.2  306.01  4969.8  303.09  5019.4  302.12  5022.1  301.62
  5025.4  302.12  5053.1  302.88  5111.8  303.21  5134.2  304.16  5156.5  303.84
  5201.2  305.23  5371.7  306.85  5416.5  307.97  5514.3  311.59  5656.8  317.82
  5693.2  321.33  5707.2  321.78  5715.5  322.90  5731.6  322.96  5737.9  322.49
  5760.3  324.82  5782.6  326.11  5791.0  325.93  5819.0  326.99  5894.4  330.90
#Mann=5,-1,0
  4596.9     0.1       0  4612.3    0.05       0  5019.4    0.03       0
  5025.4    0.05       0  5731.6     0.1       0
Bank Sta=5019.4,5025.4
Exp/Cntr=0.3,0.1

Type RM Length L Ch R = 1,2435,483,483,483
BEGIN DESCRIPTION:
UNT 052 IN LACR 4.0
END DESCRIPTION:
XS GIS Cut Line= 3
      2234237.76     13211646.88      2233937.72     13211446.85
      2233537.72     13211196.85
#Sta/Elev= 30
  4639.4  315.48  4647.0  315.60  4668.0  313.74  4725.1  312.21  4842.3  304.25
  4855.8  304.38  4863.3  303.27  4869.3  303.59  4891.8  301.81  4920.4  300.49
  4927.9  300.67  4935.4  299.65  4950.4  299.70  4983.5  298.37  4986.2  297.87
  4989.5  298.37  4997.0  299.59  5044.2  301.01  5050.1  301.90  5059.0  301.44
  5102.0  303.22  5224.1  305.12  5269.5  306.68  5275.4  305.75  5296.6  307.08
  5333.1  308.15  5385.0  310.82  5406.3  311.15  5412.7  312.03  5471.7  314.15
#Mann=3,-1,0
  4639.4     0.1       0  4983.5    0.07       0  4989.5     0.1       0
Bank Sta=4983.5,4989.5
Exp/Cntr=0.3,0.1

Type RM Length L Ch R = 1,1952,433,433,433
BEGIN DESCRIPTION:
UNT 052 IN LACR 3.0
END DESCRIPTION:
XS GIS Cut Line= 3
      2234437.74     13211396.87      2234137.72     13211046.85
      2233737.72     13210896.86
#Sta/Elev= 30
  4539.0  316.96  4567.0  315.85  4581.3  314.30  4593.7  313.85  4609.8  312.50
  4638.4  311.55  4652.6  310.25  4673.3  309.59  4751.4  306.15  4894.1  301.67
  4900.7  300.83  4929.2  299.80  4950.1  298.51  4957.7  298.53  4964.3  297.17
  4978.6  296.40  4992.9  296.42  5002.7  295.96  5006.8  295.13  5009.5  294.63
  5012.8  295.13  5021.4  296.26  5045.4  296.86  5053.4  297.68  5095.2  299.03
  5149.5  301.63  5210.9  303.20  5266.1  303.96  5359.4  307.10  5427.2  309.93
#Mann=6,-1,0
  4539.0     0.1       0  4593.7    0.05       0  4673.3     0.1       0
  5006.8    0.07       0  5012.8     0.1       0  5359.4    0.05       0
Bank Sta=5006.8,5012.8
Exp/Cntr=0.3,0.1

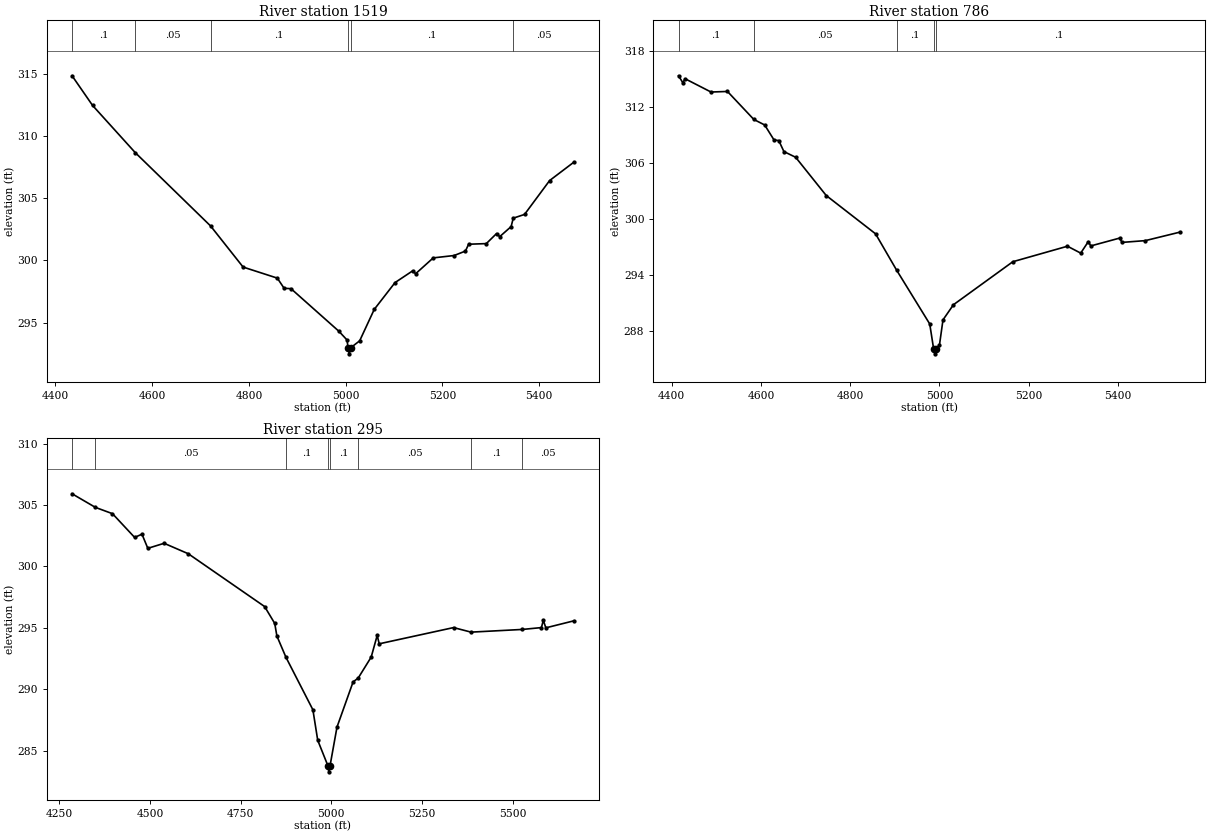
Type RM Length L Ch R = 1,1519,733,733,733
BEGIN DESCRIPTION:
UNT 052 IN LACR 2.0
END DESCRIPTION:
XS GIS Cut Line= 3
      2234787.73     13211146.87      2234387.72     13210746.85
      2233987.72     13210496.85
#Sta/Elev= 30
  4434.3  314.88  4476.7  312.49  4564.9  308.69  4720.7  302.78  4787.9  299.47
  4858.6  298.58  4872.7  297.76  4886.9  297.73  4985.9  294.30  5002.9  293.59
  5004.7  292.98  5007.4  292.48  5010.7  292.98  5028.9  293.53  5059.0  296.06
  5102.0  298.22  5138.6  299.17  5144.5  298.93  5181.0  300.21  5224.1  300.40
  5247.6  300.76  5254.1  301.31  5290.7  301.36  5311.9  302.17  5318.4  301.92
  5342.0  302.73  5346.4  303.41  5369.7  303.71  5421.6  306.44  5471.7  307.92
#Mann=6,-1,0
  4434.3     0.1       0  4564.9    0.05       0  4720.7     0.1       0
  5004.7    0.07       0  5010.7     0.1       0  5346.4    0.05       0
Bank Sta=5004.7,5010.7
Exp/Cntr=0.3,0.1

Type RM Length L Ch R = 1,786,491,491,491
BEGIN DESCRIPTION:
Mapping XS 97a13021
END DESCRIPTION:
XS GIS Cut Line= 3
      2235266.04     13210870.01      2235156.67     13210541.88
      2234443.17     13210229.40
#Sta/Elev= 30
  4415.1  315.31  4424.7  314.57  4429.9  314.99  4487.9  313.57  4524.8  313.63
  4583.9  310.63  4608.2  310.04  4629.2  308.43  4639.8  308.37  4651.3  307.19
  4677.6  306.58  4746.2  302.48  4856.7  298.38  4903.9  294.49  4978.2  288.72
  4987.0  286.02  4989.7  285.52  4993.0  286.02  5000.0  286.47  5007.9  289.16
  5031.3  290.78  5164.5  295.39  5286.9  297.05  5316.6  296.31  5333.7  297.55
  5339.1  297.08  5403.8  297.92  5409.3  297.46  5461.5  297.65  5539.9  298.57
#Mann=5,-1,0
  4415.1     0.1       0  4583.9    0.05       0  4903.9     0.1       0
  4987.0    0.07       0  4993.0     0.1       0
Bank Sta=4987,4993
Exp/Cntr=0.3,0.1

Type RM Length L Ch R = 1,295,0,0,0
BEGIN DESCRIPTION:
UNT 052 IN LACR 1.0
END DESCRIPTION:
XS GIS Cut Line= 4
      2235500.41     13210656.44      2235411.88     13210172.09
      2235088.96     13210005.43      2234583.72     13210156.48
#Sta/Elev= 30
  4285.4  305.91  4349.9  304.80  4396.8  304.29  4457.8  302.36  4478.1  302.62
  4494.2  301.47  4539.1  301.88  4605.7  301.03  4816.2  296.73  4844.0  295.36
  4850.0  294.33  4875.0  292.60  4949.2  288.33  4962.5  285.85  4990.5  283.78
  4993.2  283.28  4996.5  283.78  5015.6  286.92  5060.0  290.60  5074.0  290.91
  5109.9  292.62  5126.4  294.38  5132.0  293.70  5336.9  295.02  5385.1  294.65
  5526.8  294.87  5579.1  295.02  5584.3  295.61  5591.3  295.00  5668.5  295.57
#Mann=8,-1,0
  4285.4     0.1       0  4349.9    0.05       0  4875.0     0.1       0
  4990.5    0.07       0  4996.5     0.1       0  5074.0    0.05       0
  5385.1     0.1       0  5526.8    0.05       0
Bank Sta=4990.5,4996.5
Exp/Cntr=0.3,0.1

Chan Stop Cuts=-1