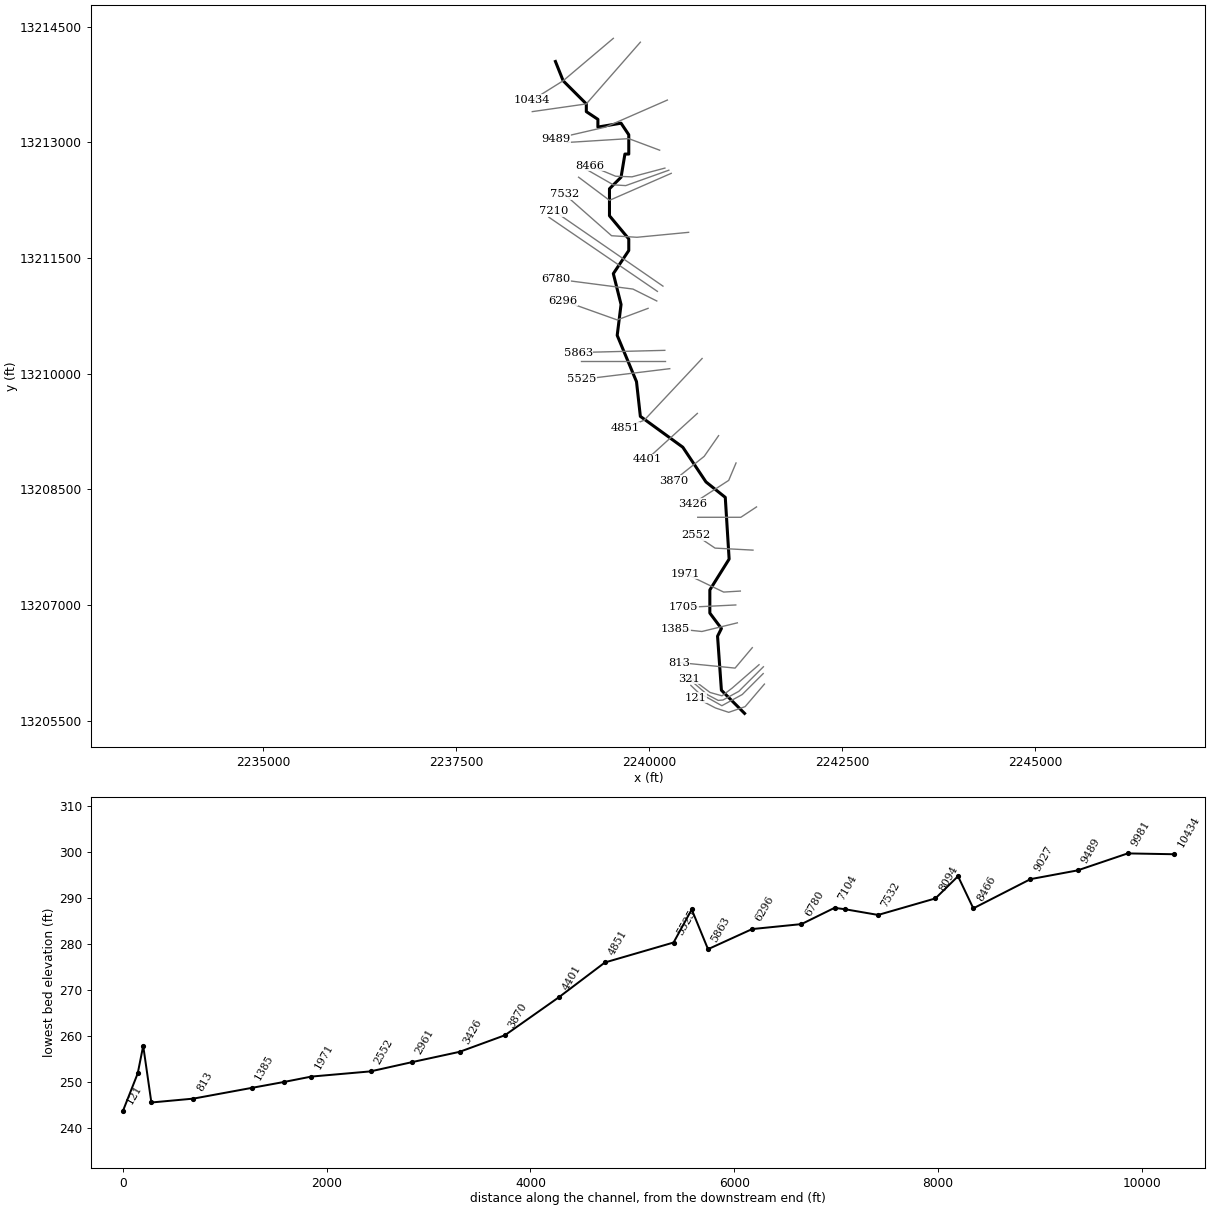
--- UNT 053 IN LACR.prj (project) ---

Proj Title=UNT 053 IN LACR Base Level Engineering
Current Plan=p01
Default Exp/Contr=0.3,0.1
English Units
Geom File=g01
Flow File=f01
Plan File=p01
BEGIN DESCRIPTION:
UNT 053 IN LACR
END DESCRIPTION:

--- UNT 053 IN LACR.p01 (plan) ---

Plan Title=Multiple Run
Short Identifier=Multiple
Geom File=g01
Flow File=f01
Subcritical Flow
K Sum by GR= 0
Std Step Tol= 0.01
Critical Tol= 0.01
Num of Std Step Trials= 20
Max Error Tol= 0.3
Flow Tol Ratio= 0.001
Split Flow NTrial= 30
Split Flow Tol= 0.02
Split Flow Ratio= 0.02
Log Output Level= 0
Friction Slope Method= 1
Unsteady Friction Slope Method= 2
Unsteady Bridges Friction Slope Method= 1
Parabolic Critical Depth
Global Vel Dist=  1 , 1 , 1
Global Log Level= 0
CheckData=True
Encroach Param= -1, 0, 0, 0
BEGIN DESCRIPTION:
Multiple Run
END DESCRIPTION:

--- UNT 053 IN LACR.f01 (steady flow) ---

Flow Title=Multiple
Number of Profiles=7
Profile Names=10-year,25-year,50-year,1pct_min,100-year,1pct_plu,500-year
River Rch & RM= UNT 053 IN LACR,Reach-1,10434
     247     344     425     386     522     706     802
River Rch & RM= UNT 053 IN LACR,Reach-1,6780
     320     451     561     514     695     940    1083
Boundary for River Rch & Prof#=UNT 053 IN LACR,Reach-1,1
Up Type=0
Dn Type=3
Dn Slope=0.005
Boundary for River Rch & Prof#=UNT 053 IN LACR,Reach-1,2
Up Type=0
Dn Type=3
Dn Slope=0.005
Boundary for River Rch & Prof#=UNT 053 IN LACR,Reach-1,3
Up Type=0
Dn Type=3
Dn Slope=0.005
Boundary for River Rch & Prof#=UNT 053 IN LACR,Reach-1,4
Up Type=0
Dn Type=3
Dn Slope=0.005
Boundary for River Rch & Prof#=UNT 053 IN LACR,Reach-1,5
Up Type=0
Dn Type=3
Dn Slope=0.005
Boundary for River Rch & Prof#=UNT 053 IN LACR,Reach-1,6
Up Type=0
Dn Type=3
Dn Slope=0.005
Boundary for River Rch & Prof#=UNT 053 IN LACR,Reach-1,7
Up Type=0
Dn Type=3
Dn Slope=0.005

--- UNT 053 IN LACR.g01 (geometry) ---

Geom Title=Existing Conditions

River Reach=UNT 053 IN LACR,Reach-1
Reach XY= 30
      2238787.72     13214046.85      2238887.72     13213796.86
      2239187.72     13213496.86      2239187.72     13213396.85
      2239337.72     13213296.86      2239337.72     13213196.85
      2239637.72     13213246.85      2239737.72     13213096.85
      2239737.72     13212846.85      2239687.72     13212846.85
      2239637.72     13212546.85      2239487.72     13212396.85
      2239487.72     13212046.85      2239737.72     13211746.85
      2239737.72     13211596.85      2239537.72     13211296.85
      2239637.72     13210896.85      2239587.72     13210496.85
      2239837.72     13209896.85      2239887.72     13209446.85
      2240437.72     13209046.86      2240737.72     13208596.85
      2240987.72     13208396.86      2241037.72     13207596.85
      2240787.72     13207196.85      2240787.72     13206896.86
      2240937.72     13206696.85      2240887.72     13206596.86
      2240937.72     13205896.85      2241237.72     13205596.86

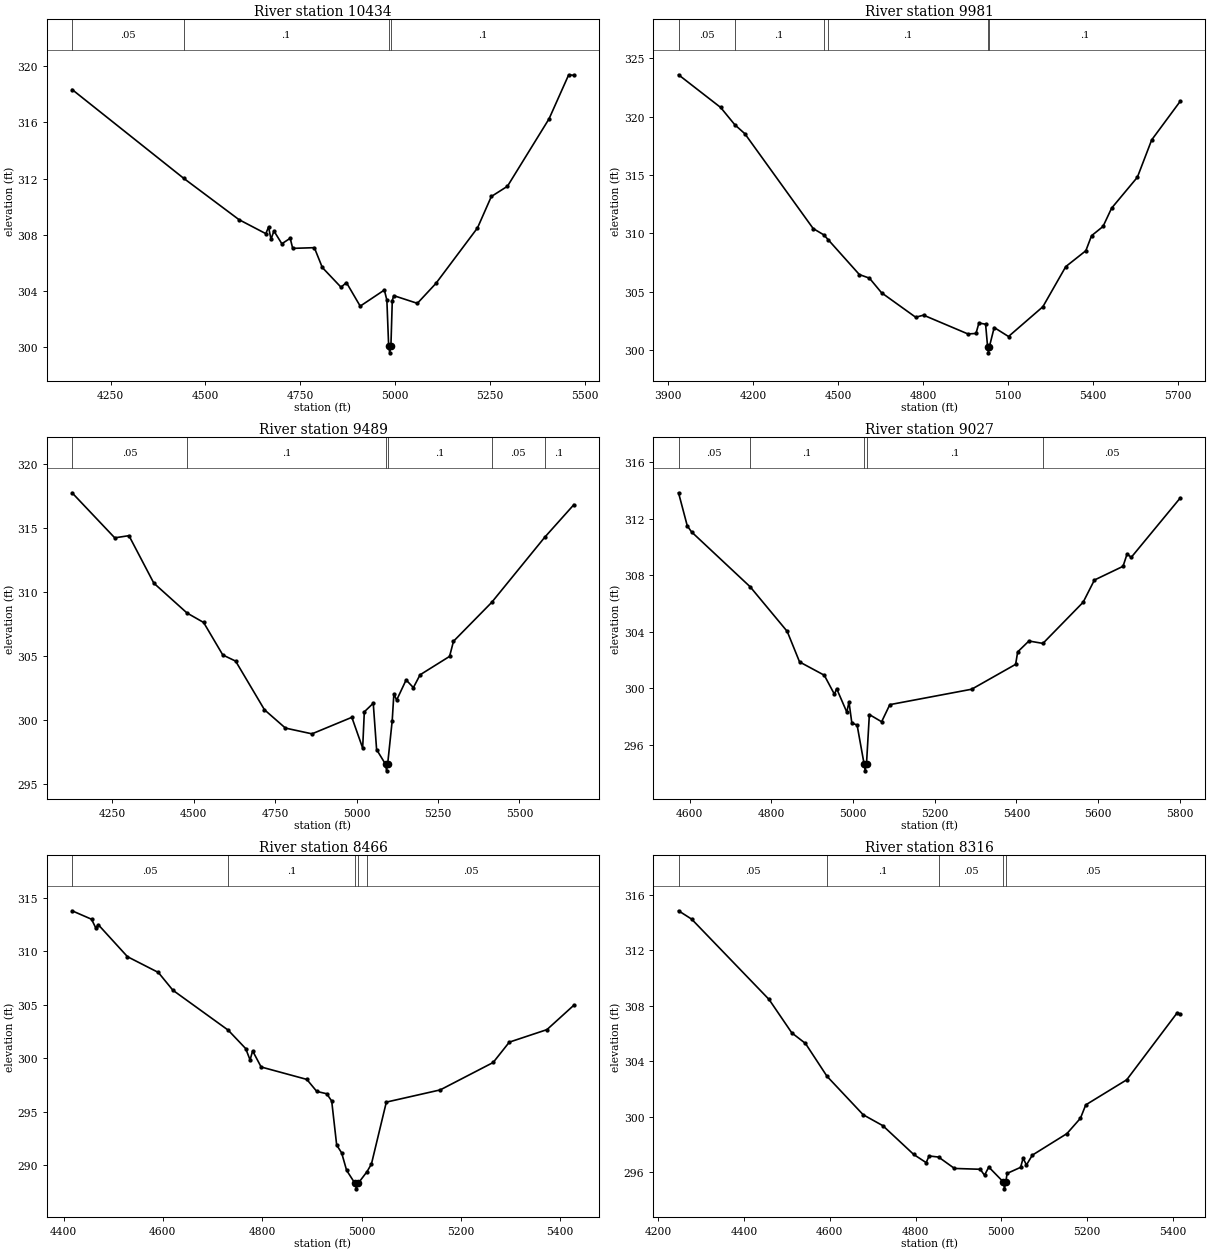
Type RM Length L Ch R = 1,10434,453,453,453
BEGIN DESCRIPTION:
UNT 053 IN LACR 22.0
END DESCRIPTION:
XS GIS Cut Line= 3
      2239537.74     13214346.87      2238887.72     13213796.86
      2238487.72     13213546.85
#Sta/Elev= 30
  4148.5  318.35  4442.7  312.02  4588.6  309.07  4659.4  308.07  4666.6  308.54
  4673.1  307.67  4680.8  308.26  4701.7  307.35  4723.7  307.74  4730.3  307.02
  4787.4  307.07  4808.3  305.66  4857.7  304.25  4872.0  304.58  4908.3  302.90
  4972.0  304.05  4978.6  303.33  4983.3  300.07  4986.1  299.57  4989.3  300.07
  4992.9  303.30  4996.7  303.65  5059.0  303.10  5107.9  304.52  5217.6  308.48
  5254.1  310.72  5296.6  311.45  5406.3  316.26  5458.1  319.40  5471.7  319.36
#Mann=4,-1,0
  4148.5    0.05       0  4442.7     0.1       0  4983.3    0.07       0
  4989.3     0.1       0
Bank Sta=4983.3,4989.3
Exp/Cntr=0.3,0.1

Type RM Length L Ch R = 1,9981,492,492,492
BEGIN DESCRIPTION:
UNT 053 IN LACR 21.0
END DESCRIPTION:
XS GIS Cut Line= 3
      2239887.71     13214296.84      2239187.72     13213496.86
      2238487.73     13213396.86
#Sta/Elev= 30
  3937.0  323.58  4085.5  320.78  4135.4  319.30  4170.9  318.53  4412.0  310.40
  4449.5  309.86  4464.4  309.46  4574.8  306.46  4610.4  306.15  4653.1  304.90
  4773.6  302.80  4801.2  302.98  4957.8  301.37  4986.2  301.41  4996.7  302.31
  5020.2  302.20  5027.3  300.25  5030.1  299.75  5033.3  300.25  5050.5  301.92
  5101.0  301.15  5222.2  303.70  5303.0  307.14  5373.8  308.50  5394.0  309.79
  5434.4  310.58  5464.7  312.15  5555.6  314.80  5606.1  318.00  5707.1  321.32
#Mann=6,-1,0
  3937.0    0.05       0  4135.4     0.1       0  4449.5    0.05       0
  4464.4     0.1       0  5027.3    0.07       0  5033.3     0.1       0
Bank Sta=5027.3,5033.3
Exp/Cntr=0.3,0.1

Type RM Length L Ch R = 1,9489,462,462,462
BEGIN DESCRIPTION:
UNT 053 IN LACR 20.0
END DESCRIPTION:
XS GIS Cut Line= 3
      2240237.71     13213546.85      2239437.72     13213196.85
      2238787.70     13213046.85
#Sta/Elev= 30
  4126.8  317.78  4257.8  314.26  4301.4  314.43  4377.8  310.72  4479.6  308.39
  4530.6  307.65  4589.5  305.11  4628.9  304.63  4717.4  300.83  4781.7  299.40
  4863.2  298.95  4985.6  300.24  5018.8  297.84  5023.9  300.67  5051.3  301.34
  5061.6  297.72  5089.4  296.56  5092.1  296.06  5095.4  296.56  5109.5  299.98
  5114.6  302.07  5123.2  301.59  5152.2  303.16  5174.5  302.56  5195.0  303.56
  5285.6  305.00  5297.6  306.18  5414.6  309.21  5577.5  314.30  5667.1  316.85
#Mann=6,-1,0
  4126.8    0.05       0  4479.6     0.1       0  5089.4    0.07       0
  5095.4     0.1       0  5414.6    0.05       0  5577.5     0.1       0
Bank Sta=5089.4,5095.4
Exp/Cntr=0.3,0.1

Type RM Length L Ch R = 1,9027,561,561,561
BEGIN DESCRIPTION:
UNT 053 IN LACR 19.0
END DESCRIPTION:
XS GIS Cut Line= 3
      2240137.72     13212896.85      2239737.72     13213046.85
      2238937.68     13212996.85
#Sta/Elev= 30
  4572.8  313.82  4594.2  311.48  4604.8  311.05  4748.3  307.17  4838.9  304.02
  4869.2  301.86  4929.7  300.92  4954.6  299.57  4960.0  299.97  4984.9  298.31
  4990.2  299.03  4997.3  297.52  5010.0  297.41  5027.1  294.66  5029.8  294.16
  5033.1  294.66  5040.1  298.14  5070.1  297.63  5090.2  298.84  5290.6  299.93
  5398.3  301.69  5403.3  302.57  5430.8  303.34  5465.1  303.17  5563.6  306.08
  5591.2  307.65  5661.3  308.62  5671.3  309.50  5681.3  309.25  5801.6  313.46
#Mann=5,-1,0
  4572.8    0.05       0  4748.3     0.1       0  5027.1    0.07       0
  5033.1     0.1       0  5465.1    0.05       0
Bank Sta=5027.1,5033.1
Exp/Cntr=0.3,0.1

Type RM Length L Ch R = 1,8466,150,150,150
BEGIN DESCRIPTION:
UNT 053 IN LACR 18.0
END DESCRIPTION:
XS GIS Cut Line= 4
      2240205.58     13212664.95      2239778.97     13212551.45
      2239567.64     13212559.28      2239237.71     13212696.86
#Sta/Elev= 30
  4417.2  313.78  4456.4  312.99  4464.8  312.19  4470.0  312.48  4528.8  309.49
  4590.9  308.02  4620.2  306.36  4731.6  302.63  4766.8  300.91  4775.6  299.85
  4780.8  300.69  4797.9  299.19  4889.9  298.03  4909.9  296.91  4930.0  296.69
  4940.0  296.01  4950.0  291.90  4960.0  291.17  4970.0  289.54  4987.0  288.31
  4989.7  287.81  4993.0  288.31  5011.2  289.42  5020.0  290.13  5050.0  295.91
  5158.5  297.05  5265.1  299.61  5297.6  301.51  5373.4  302.68  5427.6  304.96
#Mann=5,-1,0
  4417.2    0.05       0  4731.6     0.1       0  4987.0    0.07       0
  4993.0     0.1       0  5011.2    0.05       0
Bank Sta=4987,4993
Exp/Cntr=0.3,0.1

Type RM Length L Ch R = 1,8316,222,222,222
BEGIN DESCRIPTION:
Mapping XS abff1f83
END DESCRIPTION:
XS GIS Cut Line= 4
      2240256.45     13212637.55      2239698.75     13212437.96
      2239538.29     13212447.74      2239176.30     13212655.15
#Sta/Elev= 30
  4247.2  314.83  4277.7  314.23  4458.3  308.44  4511.4  306.03  4543.2  305.27
  4593.5  302.90  4677.8  300.13  4723.8  299.34  4795.6  297.27  4824.7  296.68
  4831.6  297.16  4853.7  297.08  4890.7  296.26  4950.8  296.20  4960.8  295.77
  4970.8  296.36  5004.6  295.29  5007.4  294.79  5010.6  295.29  5013.4  295.90
  5045.0  296.34  5050.8  297.00  5058.6  296.51  5072.4  297.22  5153.0  298.77
  5184.6  299.88  5196.9  300.84  5292.5  302.65  5410.5  307.49  5417.5  307.37
#Mann=5,-1,0
  4247.2    0.05       0  4593.5     0.1       0  4853.7    0.05       0
  5004.6    0.03       0  5010.6    0.05       0
Bank Sta=5004.6,5010.6
Exp/Cntr=0.3,0.1

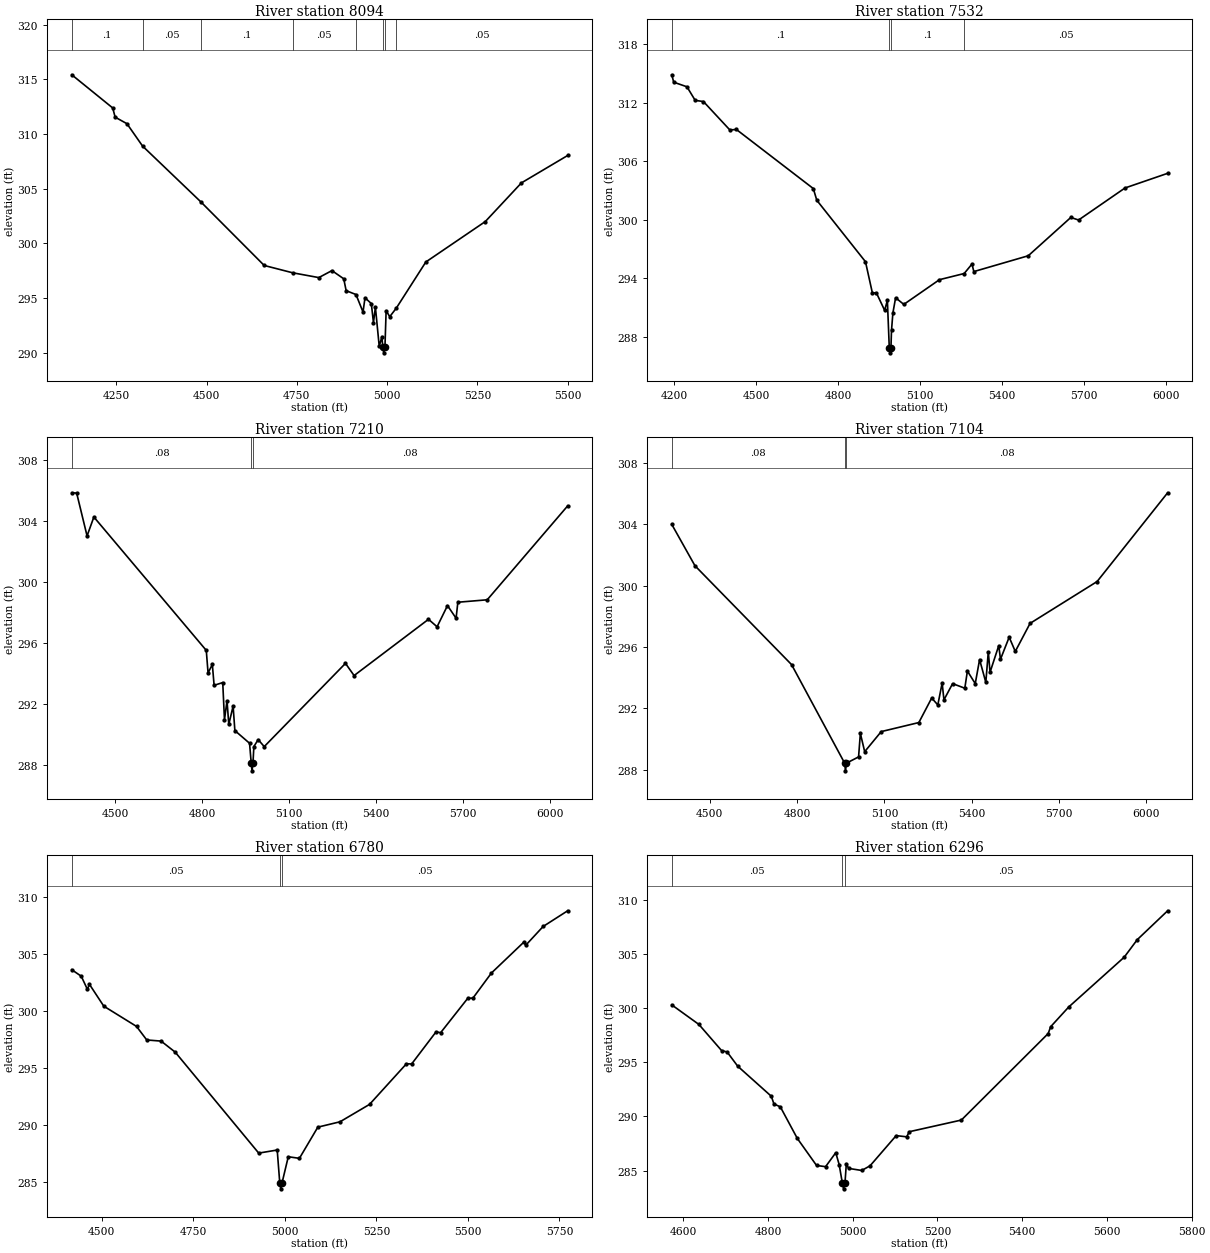
Type RM Length L Ch R = 1,8094,562,562,562
BEGIN DESCRIPTION:
UNT 053 IN LACR 17.0
END DESCRIPTION:
XS GIS Cut Line= 3
      2240287.71     13212596.85      2239487.72     13212246.85
      2239087.72     13212546.85
#Sta/Elev= 30
  4126.8  315.43  4240.2  312.39  4246.9  311.55  4279.6  310.95  4322.9  308.90
  4483.7  303.81  4659.7  297.97  4738.4  297.30  4810.9  296.86  4847.2  297.50
  4879.9  296.75  4886.6  295.66  4913.8  295.31  4933.3  293.71  4938.8  295.01
  4956.3  294.48  4962.2  292.74  4967.6  294.14  4978.2  290.56  4985.6  291.46
  4988.0  290.47  4990.8  289.97  4994.0  290.47  4997.3  293.83  5007.3  293.28
  5025.6  294.07  5107.3  298.29  5271.9  301.99  5371.9  305.53  5500.0  308.04
#Mann=8,-1,0
  4126.8     0.1       0  4322.9    0.05       0  4483.7     0.1       0
  4738.4    0.05       0  4913.8     0.1       0  4988.0    0.07       0
  4994.0     0.1       0  5025.6    0.05       0
Bank Sta=4988,4994
Exp/Cntr=0.3,0.1

Type RM Length L Ch R = 1,7532,322,322,322
BEGIN DESCRIPTION:
Mapping XS 0c9c8cdf
END DESCRIPTION:
XS GIS Cut Line= 4
      2240513.07     13211832.24      2239843.83     13211768.12
      2239515.20     13211788.16      2238906.05     13212325.16
#Sta/Elev= 30
  4191.8  314.85  4199.0  314.09  4247.4  313.62  4277.5  312.23  4307.7  312.11
  4404.3  309.20  4428.2  309.25  4709.5  303.20  4722.3  302.00  4900.3  295.71
  4925.4  292.53  4940.4  292.51  4970.4  290.73  4980.4  291.75  4987.4  286.88
  4990.2  286.38  4993.4  286.88  4995.5  288.67  5000.5  290.45  5010.5  292.02
  5040.5  291.34  5170.8  293.87  5261.2  294.50  5289.8  295.47  5296.6  294.70
  5495.7  296.32  5651.2  300.24  5679.7  299.98  5849.5  303.26  6005.4  304.76
#Mann=4,-1,0
  4191.8     0.1       0  4987.4    0.07       0  4993.4     0.1       0
  5261.2    0.05       0
Bank Sta=4987.4,4993.4
Exp/Cntr=0.3,0.1

Type RM Length L Ch R = 1,7210,106,106,106
BEGIN DESCRIPTION:
UNT 053 IN LACR 16.0
END DESCRIPTION:
XS GIS Cut Line= 2
      2240180.50     13211134.89      2238771.28     13212107.73
#Sta/Elev= 30
  4349.6  305.85  4366.5  305.83  4402.4  303.02  4425.9  304.26  4814.1  295.51
  4820.2  294.03  4835.0  294.59  4841.1  293.22  4870.9  293.40  4876.9  290.96
  4885.7  292.21  4891.8  290.65  4906.7  291.86  4912.8  290.25  4963.5  289.42
  4969.3  288.11  4972.0  287.61  4975.3  288.11  4978.4  289.20  4993.2  289.66
  5014.2  289.20  5294.7  294.66  5324.5  293.86  5581.4  297.55  5611.1  297.06
  5647.0  298.45  5676.7  297.62  5682.8  298.67  5784.2  298.83  6062.0  304.99
#Mann=3,-1,0
  4349.6    0.08       0  4969.3    0.07       0  4975.3    0.08       0
Bank Sta=4969.3,4975.3
Exp/Cntr=0.3,0.1

Type RM Length L Ch R = 1,7104,324,324,324
BEGIN DESCRIPTION:
UNT 053 IN LACR 15.0
END DESCRIPTION:
XS GIS Cut Line= 2
      2240108.35     13211066.76      2238702.15     13212028.27
#Sta/Elev= 30
  4369.3  304.00  4449.0  301.30  4780.9  294.85  4963.3  288.42  4966.1  287.92
  4969.3  288.42  5011.1  288.83  5017.2  290.36  5032.1  289.17  5088.9  290.48
  5218.1  291.07  5262.3  292.67  5283.3  292.22  5298.2  293.65  5304.3  292.55
  5334.1  293.61  5376.0  293.31  5384.9  294.43  5411.9  293.61  5426.8  295.18
  5448.2  293.69  5456.7  295.69  5462.7  294.35  5492.6  296.09  5498.6  295.20
  5528.4  296.64  5549.4  295.71  5600.2  297.54  5830.5  300.27  6072.8  306.06
#Mann=3,-1,0
  4369.3    0.08       0  4963.3    0.07       0  4969.3    0.08       0
Bank Sta=4963.3,4969.3
Exp/Cntr=0.3,0.1

Type RM Length L Ch R = 1,6780,484,484,484
BEGIN DESCRIPTION:
UNT 053 IN LACR 14.0
END DESCRIPTION:
XS GIS Cut Line= 3
      2240100.33     13210942.53      2239791.73     13211096.85
      2238791.29     13211226.89
#Sta/Elev= 30
  4418.5  303.64  4444.4  303.07  4461.1  301.92  4466.7  302.36  4505.9  300.44
  4595.3  298.66  4623.2  297.47  4662.4  297.37  4700.9  296.40  4928.9  287.53
  4979.4  287.80  4986.4  284.89  4989.2  284.39  4992.4  284.89  5009.6  287.21
  5040.0  287.07  5090.3  289.81  5150.8  290.28  5231.5  291.81  5332.3  295.38
  5346.4  295.36  5413.0  298.18  5425.6  298.11  5499.6  301.13  5513.8  301.15
  5564.2  303.35  5652.9  306.07  5657.9  305.79  5705.4  307.44  5772.4  308.82
#Mann=3,-1,0
  4418.5    0.05       0  4986.4    0.03       0  4992.4    0.05       0
Bank Sta=4986.4,4992.4
Exp/Cntr=0.3,0.1

Type RM Length L Ch R = 1,6296,433,433,433
BEGIN DESCRIPTION:
UNT 053 IN LACR 13.0
END DESCRIPTION:
XS GIS Cut Line= 3
      2239987.72     13210846.85      2239587.72     13210696.86
      2238887.72     13210946.85
#Sta/Elev= 30
  4572.8  300.32  4636.9  298.51  4690.3  296.10  4703.6  295.96  4728.5  294.65
  4807.8  291.87  4814.0  291.16  4829.1  290.89  4869.2  287.97  4914.6  285.47
  4935.9  285.36  4959.9  286.65  4968.0  285.55  4975.6  283.81  4978.4  283.31
  4981.6  283.81  4984.9  285.64  4990.2  285.20  5021.2  285.01  5040.9  285.44
  5102.5  288.23  5127.4  288.12  5133.3  288.59  5256.4  289.67  5461.4  297.67
  5467.2  298.30  5509.7  300.12  5640.8  304.73  5671.6  306.35  5743.3  309.02
#Mann=3,-1,0
  4572.8    0.05       0  4975.6    0.03       0  4981.6    0.05       0
Bank Sta=4975.6,4981.6
Exp/Cntr=0.3,0.1

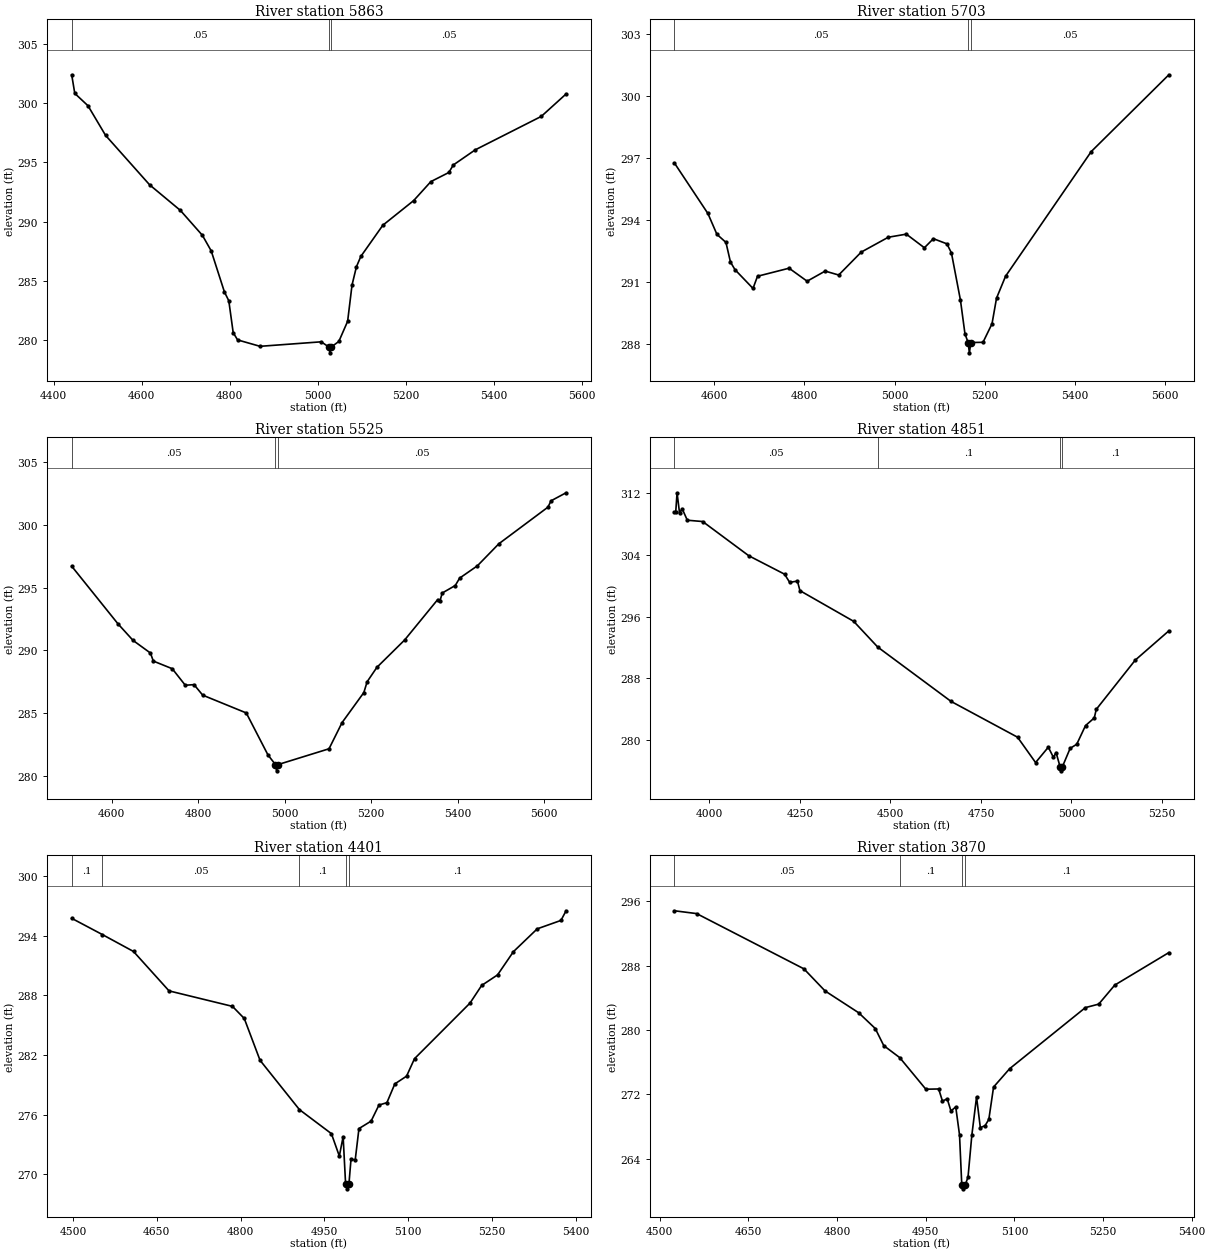
Type RM Length L Ch R = 1,5863,160,160,160
BEGIN DESCRIPTION:
Mapping XS 229b5477
END DESCRIPTION:
XS GIS Cut Line= 2
      2240204.74     13210302.56      2239081.40     13210274.21
#Sta/Elev= 30
  4441.2  302.39  4448.2  300.82  4478.2  299.78  4518.2  297.28  4618.3  293.11
  4688.3  290.95  4738.3  288.85  4758.3  287.54  4788.3  284.08  4798.3  283.33
  4808.3  280.64  4818.3  280.03  4869.3  279.49  5008.4  279.87  5025.4  279.44
  5028.2  278.94  5031.4  279.44  5048.4  279.90  5068.4  281.60  5078.4  284.66
  5088.4  286.20  5098.4  287.07  5148.4  289.70  5218.5  291.78  5257.6  293.38
  5298.5  294.15  5308.5  294.78  5358.5  296.06  5508.6  298.88  5564.9  300.77
#Mann=3,-1,0
  4441.2    0.05       0  5025.4    0.03       0  5031.4    0.05       0
Bank Sta=5025.4,5031.4
Exp/Cntr=0.3,0.1

Type RM Length L Ch R = 1,5703,178,178,178
BEGIN DESCRIPTION:
UNT 053 IN LACR 12.0
END DESCRIPTION:
XS GIS Cut Line= 2
      2240211.83     13210160.65      2239115.63     13210160.65
#Sta/Elev= 30
  4512.1  296.76  4586.2  294.32  4606.2  293.31  4626.2  292.92  4636.2  291.97
  4646.2  291.60  4686.2  290.69  4696.2  291.28  4766.2  291.67  4806.2  291.04
  4846.2  291.53  4876.2  291.34  4926.2  292.45  4986.2  293.17  5026.2  293.32
  5066.2  292.66  5086.2  293.10  5116.2  292.85  5126.2  292.41  5146.2  290.12
  5156.2  288.49  5163.2  288.07  5166.0  287.57  5169.2  288.07  5196.2  288.08
  5216.2  288.98  5226.2  290.22  5246.2  291.28  5436.2  297.32  5608.3  301.04
#Mann=3,-1,0
  4512.1    0.05       0  5163.2    0.03       0  5169.2    0.05       0
Bank Sta=5163.2,5169.2
Exp/Cntr=0.3,0.1

Type RM Length L Ch R = 1,5525,674,674,674
BEGIN DESCRIPTION:
UNT 053 IN LACR 11.0
END DESCRIPTION:
XS GIS Cut Line= 2
      2240268.62     13210064.87      2239133.32     13209926.50
#Sta/Elev= 30
  4507.1  296.72  4614.2  292.12  4649.0  290.80  4689.3  289.79  4695.9  289.15
  4739.7  288.54  4769.9  287.22  4790.1  287.27  4810.2  286.43  4911.0  285.01
  4961.3  281.65  4978.5  280.89  4981.2  280.39  4984.5  280.89  5102.4  282.15
  5132.6  284.24  5183.0  286.64  5190.6  287.50  5213.2  288.65  5277.3  290.83
  5353.9  294.06  5358.9  293.92  5364.3  294.58  5394.5  295.18  5404.6  295.77
  5445.6  296.75  5495.3  298.51  5608.8  301.43  5616.1  301.94  5650.8  302.58
#Mann=3,-1,0
  4507.1    0.05       0  4978.5    0.03       0  4984.5    0.05       0
Bank Sta=4978.5,4984.5
Exp/Cntr=0.3,0.1

Type RM Length L Ch R = 1,4851,450,450,450
BEGIN DESCRIPTION:
UNT 053 IN LACR 10.0
END DESCRIPTION:
XS GIS Cut Line= 3
      2240687.73     13210196.87      2239937.72     13209396.86
      2239687.68     13209296.84
#Sta/Elev= 30
  3903.4  309.50  3906.8  309.50  3910.5  312.02  3917.3  309.43  3924.7  309.95
  3938.8  308.47  3981.3  308.30  4108.8  303.87  4207.5  301.49  4221.7  300.43
  4243.1  300.60  4250.0  299.36  4398.5  295.39  4465.0  292.06  4667.6  285.03
  4851.3  280.40  4901.1  277.12  4936.3  279.11  4950.4  277.79  4957.7  278.42
  4968.9  276.55  4971.6  276.05  4974.9  276.55  4996.6  278.96  5014.8  279.49
  5039.0  281.90  5063.3  282.90  5068.7  284.00  5176.4  290.37  5269.3  294.16
#Mann=4,-1,0
  3903.4    0.05       0  4465.0     0.1       0  4968.9    0.07       0
  4974.9     0.1       0
Bank Sta=4968.9,4974.9
Exp/Cntr=0.3,0.1

Type RM Length L Ch R = 1,4401,531,531,531
BEGIN DESCRIPTION:
UNT 053 IN LACR 9.0
END DESCRIPTION:
XS GIS Cut Line= 2
      2240626.09     13209484.92      2239971.84     13208889.55
#Sta/Elev= 30
  4497.7  295.77  4552.7  294.13  4608.3  292.43  4671.9  288.46  4785.4  286.90
  4806.5  285.68  4834.7  281.47  4905.2  276.50  4962.4  274.08  4976.6  271.82
  4983.4  273.78  4987.8  269.02  4990.5  268.52  4993.8  269.02  4997.5  271.52
  5005.0  271.42  5011.7  274.59  5033.4  275.34  5047.5  276.96  5061.7  277.20
  5075.9  279.09  5096.9  279.87  5111.1  281.63  5210.4  287.23  5231.3  289.01
  5259.7  290.07  5288.1  292.41  5330.7  294.71  5373.2  295.56  5382.3  296.53
#Mann=5,-1,0
  4497.7     0.1       0  4552.7    0.05       0  4905.2     0.1       0
  4987.8    0.07       0  4993.8     0.1       0
Bank Sta=4987.8,4993.8
Exp/Cntr=0.3,0.1

Type RM Length L Ch R = 1,3870,444,444,444
BEGIN DESCRIPTION:
UNT 053 IN LACR 8.0
END DESCRIPTION:
XS GIS Cut Line= 3
      2240901.25     13209196.71      2240714.53     13208928.10
      2240315.82     13208611.10
#Sta/Elev= 30
  4524.8  294.82  4562.3  294.47  4743.8  287.60  4779.6  284.85  4836.4  282.14
  4864.5  280.18  4878.9  278.05  4905.9  276.56  4950.1  272.63  4971.8  272.66
  4978.2  271.16  4986.3  271.43  4992.6  269.92  5000.7  270.43  5007.1  266.95
  5010.9  260.74  5013.7  260.24  5016.9  260.74  5021.5  261.72  5027.9  266.89
  5035.9  271.67  5042.3  267.86  5050.3  268.09  5056.7  268.88  5064.7  272.90
  5091.9  275.18  5220.1  282.78  5242.6  283.21  5269.8  285.58  5361.3  289.62
#Mann=4,-1,0
  4524.8    0.05       0  4905.9     0.1       0  5010.9    0.07       0
  5016.9     0.1       0
Bank Sta=5010.9,5016.9
Exp/Cntr=0.3,0.1

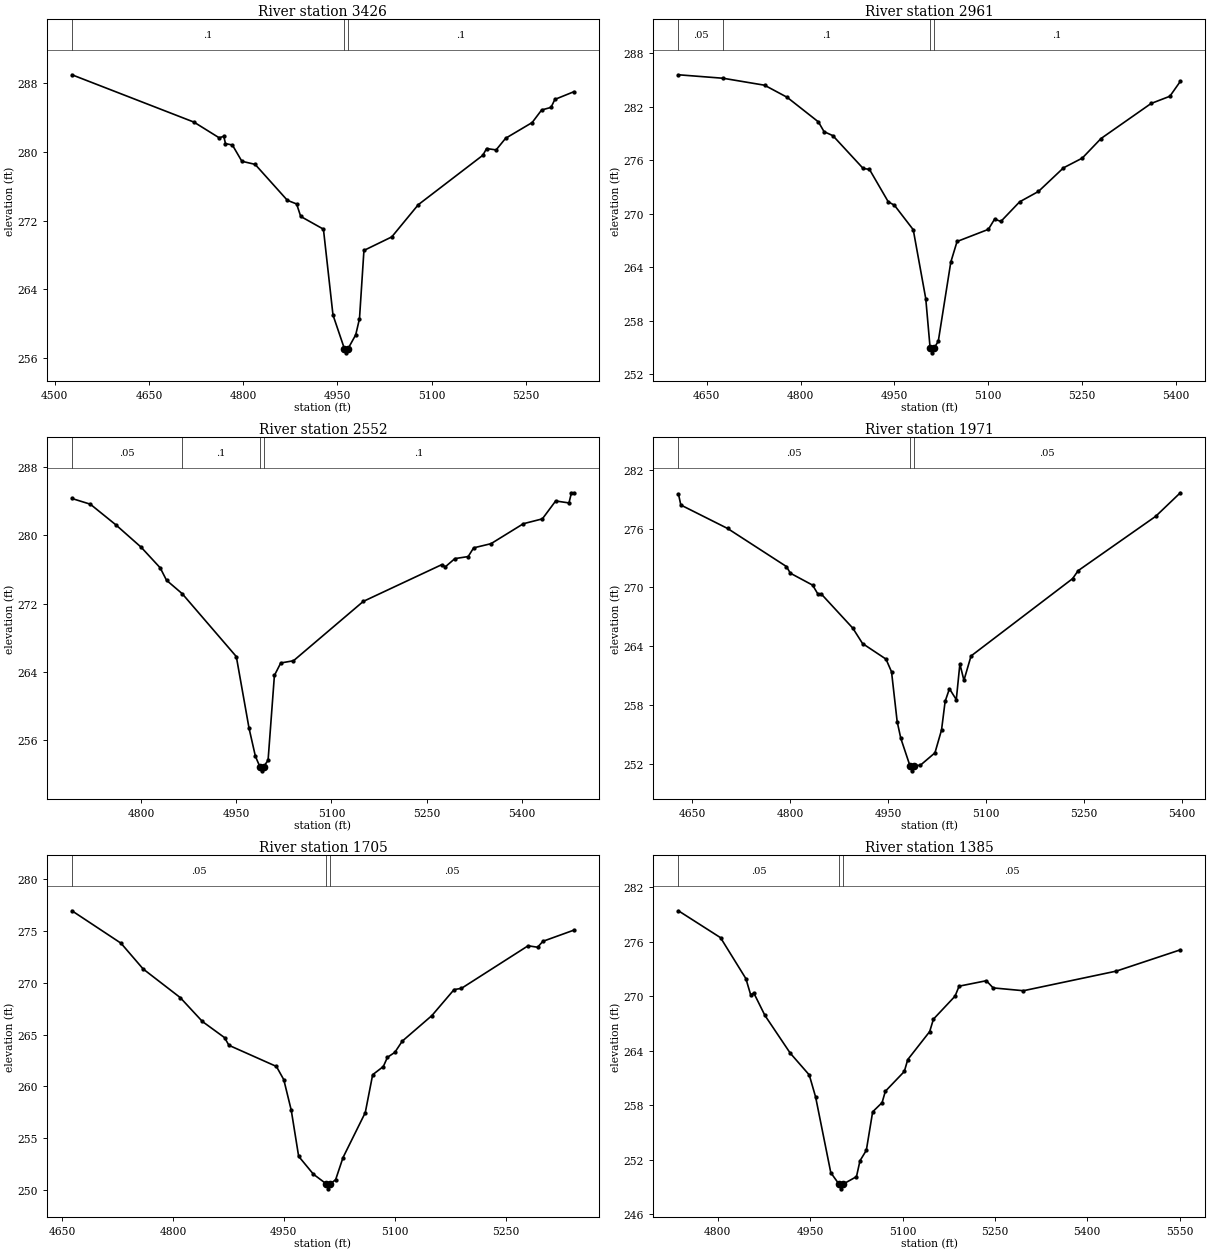
Type RM Length L Ch R = 1,3426,465,465,465
BEGIN DESCRIPTION:
UNT 053 IN LACR 7.0
END DESCRIPTION:
XS GIS Cut Line= 3
      2241127.22     13208842.90      2241032.25     13208616.94
      2240567.15     13208315.60
#Sta/Elev= 30
  4527.4  288.95  4721.7  283.45  4761.8  281.63  4769.2  281.80  4771.9  280.95
  4782.9  280.79  4798.0  278.90  4819.1  278.54  4870.5  274.36  4885.2  273.94
  4891.7  272.49  4927.9  271.01  4943.1  261.04  4961.2  257.14  4963.9  256.64
  4967.2  257.14  4979.3  258.73  4985.3  260.60  4992.4  268.54  5036.7  270.11
  5078.9  273.85  5181.8  279.60  5187.7  280.38  5202.9  280.22  5218.0  281.57
  5260.3  283.40  5275.4  284.86  5290.3  285.16  5296.5  286.09  5326.7  286.98
#Mann=3,-1,0
  4527.4     0.1       0  4961.2    0.07       0  4967.2     0.1       0
Bank Sta=4961.2,4967.2
Exp/Cntr=0.3,0.1

Type RM Length L Ch R = 1,2961,409,409,409
BEGIN DESCRIPTION:
UNT 053 IN LACR 6.0
END DESCRIPTION:
XS GIS Cut Line= 3
      2241392.54     13208273.01      2241189.47     13208138.72
      2240631.02     13208138.72
#Sta/Elev= 30
  4604.8  285.60  4676.2  285.21  4742.4  284.43  4778.4  283.08  4828.4  280.32
  4837.5  279.22  4851.6  278.77  4900.0  275.09  4910.0  274.99  4940.0  271.36
  4950.0  270.96  4980.0  268.22  5000.0  260.48  5007.0  254.91  5009.7  254.41
  5013.0  254.91  5020.0  255.71  5040.0  264.59  5050.0  266.90  5100.0  268.26
  5110.0  269.41  5120.0  269.15  5150.0  271.35  5180.0  272.51  5220.0  275.16
  5250.0  276.25  5280.0  278.45  5360.0  282.38  5390.0  283.19  5406.7  284.86
#Mann=4,-1,0
  4604.8    0.05       0  4676.2     0.1       0  5007.0    0.07       0
  5013.0     0.1       0
Bank Sta=5007,5013
Exp/Cntr=0.3,0.1

Type RM Length L Ch R = 1,2552,581,581,581
BEGIN DESCRIPTION:
UNT 053 IN LACR 5.0
END DESCRIPTION:
XS GIS Cut Line= 3
      2241346.68     13207712.91      2240855.38     13207739.12
      2240606.44     13207906.17
#Sta/Elev= 30
  4690.6  284.33  4719.6  283.66  4759.7  281.25  4799.7  278.62  4829.8  276.20
  4839.8  274.74  4864.5  273.17  4949.9  265.79  4970.0  257.38  4980.0  254.10
  4987.0  252.89  4989.7  252.39  4993.0  252.89  5000.0  253.62  5010.0  263.58
  5020.0  265.04  5040.1  265.30  5150.2  272.26  5273.7  276.56  5279.7  276.32
  5294.7  277.28  5315.7  277.52  5324.3  278.54  5351.7  279.03  5402.7  281.37
  5432.7  281.94  5453.7  284.04  5474.7  283.81  5478.6  285.00  5482.4  285.00
#Mann=4,-1,0
  4690.6    0.05       0  4864.5     0.1       0  4987.0    0.07       0
  4993.0     0.1       0
Bank Sta=4987,4993
Exp/Cntr=0.3,0.1

Type RM Length L Ch R = 1,1971,266,266,266
BEGIN DESCRIPTION:
UNT 053 IN LACR 4.0
END DESCRIPTION:
XS GIS Cut Line= 3
      2241182.95     13207182.29      2240966.74     13207169.19
      2240468.88     13207408.29
#Sta/Elev= 30
  4628.5  279.57  4632.2  278.43  4703.9  276.03  4794.0  272.14  4800.0  271.46
  4834.1  270.24  4842.1  269.34  4847.3  269.34  4895.7  265.84  4910.6  264.27
  4946.5  262.68  4955.0  261.38  4963.6  256.30  4969.2  254.58  4983.3  251.76
  4986.0  251.26  4989.3  251.76  4999.3  251.84  5021.5  253.10  5031.6  255.44
  5037.1  258.36  5043.7  259.65  5054.2  258.54  5059.7  262.19  5065.9  260.51
  5076.8  263.00  5232.3  270.90  5240.9  271.72  5359.6  277.27  5397.4  279.68
#Mann=3,-1,0
  4628.5    0.05       0  4983.3    0.03       0  4989.3    0.05       0
Bank Sta=4983.3,4989.3
Exp/Cntr=0.3,0.1

Type RM Length L Ch R = 1,1705,320,320,320
BEGIN DESCRIPTION:
Mapping XS 1ea6b92f
END DESCRIPTION:
XS GIS Cut Line= 2
      2241123.93     13207002.14      2240445.92     13206969.39
#Sta/Elev= 30
  4663.4  276.95  4729.7  273.82  4759.7  271.33  4809.8  268.57  4839.8  266.26
  4869.8  264.70  4875.7  263.96  4939.9  261.92  4949.9  260.64  4960.0  257.69
  4970.0  253.24  4990.0  251.51  5007.0  250.60  5009.8  250.10  5013.0  250.60
  5020.0  250.98  5030.0  253.12  5060.1  257.46  5070.1  261.12  5084.5  261.91
  5090.1  262.80  5100.1  263.28  5110.1  264.36  5150.2  266.83  5180.2  269.34
  5190.2  269.46  5280.3  273.57  5293.2  273.43  5300.3  274.00  5342.2  275.08
#Mann=3,-1,0
  4663.4    0.05       0  5007.0    0.03       0  5013.0    0.05       0
Bank Sta=5007,5013
Exp/Cntr=0.3,0.1

Type RM Length L Ch R = 1,1385,572,572,572
BEGIN DESCRIPTION:
UNT 053 IN LACR 3.0
END DESCRIPTION:
XS GIS Cut Line= 3
      2241144.19     13206770.29      2240685.05     13206658.22
      2240344.37     13206694.25
#Sta/Elev= 30
  4736.0  279.41  4804.4  276.45  4845.6  271.94  4853.3  270.17  4858.5  270.35
  4876.5  267.89  4917.7  263.73  4948.5  261.34  4958.8  258.92  4983.5  250.58
  4997.0  249.30  4999.8  248.80  5003.0  249.30  5025.2  250.14  5030.9  251.89
  5041.2  253.04  5051.5  257.28  5066.8  258.29  5072.1  259.54  5102.9  261.72
  5108.5  263.03  5144.1  266.11  5150.2  267.48  5185.3  270.01  5191.9  271.11
  5236.1  271.71  5247.2  270.92  5296.4  270.61  5447.3  272.77  5551.2  275.11
#Mann=3,-1,0
  4736.0    0.05       0  4997.0    0.03       0  5003.0    0.05       0
Bank Sta=4997,5003
Exp/Cntr=0.3,0.1

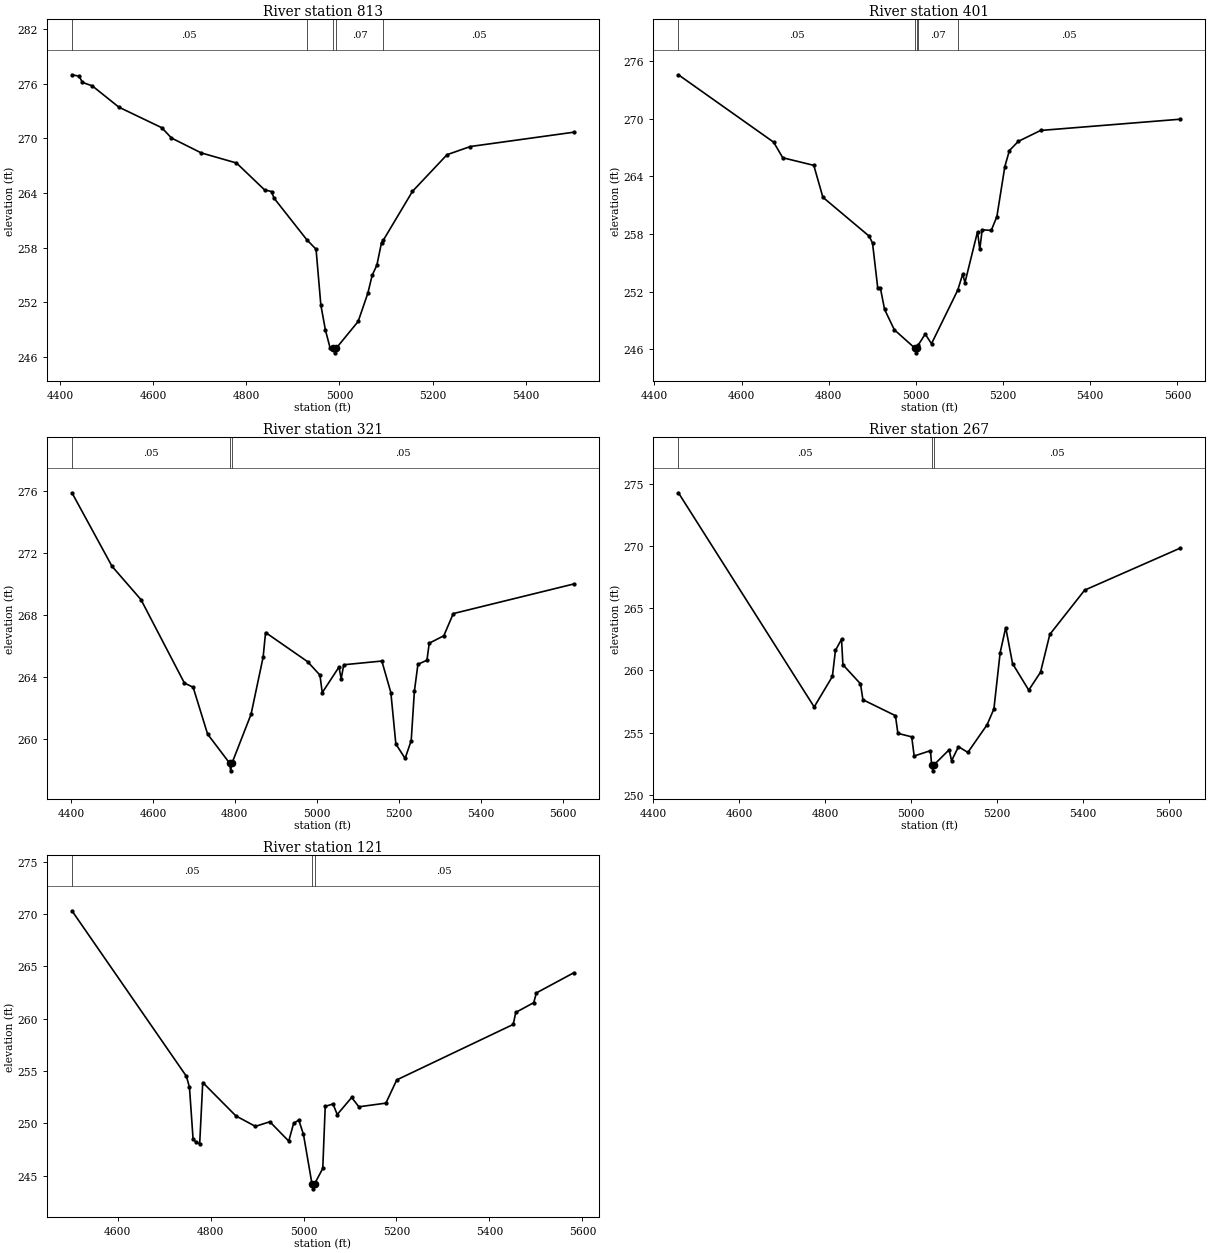
Type RM Length L Ch R = 1,813,412,412,412
BEGIN DESCRIPTION:
UNT 053 IN LACR 2.0
END DESCRIPTION:
XS GIS Cut Line= 3
      2241337.76     13206448.59      2241115.02     13206183.71
      2240386.68     13206255.94
#Sta/Elev= 30
  4425.5  276.98  4440.8  276.83  4448.1  276.14  4469.0  275.77  4526.2  273.43
  4618.5  271.17  4639.3  270.04  4703.1  268.41  4778.9  267.30  4839.2  264.35
  4854.2  264.17  4859.3  263.46  4929.9  258.88  4949.8  257.84  4960.1  251.71
  4969.9  248.97  4979.9  247.02  4987.0  246.97  4989.7  246.47  4993.0  246.97
  5040.2  249.91  5061.0  253.01  5070.3  254.97  5080.4  256.09  5090.4  258.56
  5094.5  258.85  5156.9  264.19  5231.1  268.21  5281.4  269.11  5503.5  270.68
#Mann=5,-1,0
  4425.5    0.05       0  4929.9    0.07       0  4987.0    0.07       0
  4993.0    0.07       0  5094.5    0.05       0
Bank Sta=4987,4993
Exp/Cntr=0.3,0.1

Type RM Length L Ch R = 1,401,80,80,80
BEGIN DESCRIPTION:
Mapping XS 338556a5
END DESCRIPTION:
XS GIS Cut Line= 6
      2241424.95     13206227.59      2241077.29     13205924.88
      2240945.12     13205824.42      2240790.47     13205868.04
      2240571.05     13206033.27      2240504.12     13206092.32
#Sta/Elev= 30
  4455.1  274.55  4673.6  267.54  4694.5  265.92  4765.7  265.13  4786.6  261.81
  4892.9  257.76  4900.5  257.04  4912.5  252.35  4918.6  252.35  4928.1  250.15
  4950.5  248.03  4997.4  246.13  5000.2  245.63  5003.4  246.13  5005.5  246.45
  5021.3  247.58  5035.8  246.58  5096.0  252.15  5107.4  253.82  5112.6  252.94
  5141.4  258.23  5146.6  256.39  5152.1  258.43  5172.9  258.36  5185.8  259.80
  5204.1  265.01  5214.5  266.67  5235.2  267.63  5286.2  268.76  5606.7  269.93
#Mann=5,-1,0
  4455.1    0.05       0  4997.4    0.03       0  5003.4    0.05       0
  5005.5    0.07       0  5096.0    0.05       0
Bank Sta=4997.4,5003.4
Exp/Cntr=0.3,0.1

Type RM Length L Ch R = 1,321,54,54,54
BEGIN DESCRIPTION:
Mapping XS 71475bca
END DESCRIPTION:
XS GIS Cut Line= 6
      2241481.73     13206201.10      2241163.21     13205882.58
      2240958.33     13205770.23      2240896.21     13205764.94
      2240756.10     13205838.96      2240514.18     13206047.83
#Sta/Elev= 30
  4402.4  275.87  4500.2  271.13  4570.9  268.98  4676.9  263.60  4698.2  263.33
  4733.5  260.31  4787.1  258.44  4789.8  257.94  4793.1  258.44  4839.6  261.59
  4869.1  265.28  4875.0  266.86  4977.6  264.98  5007.8  264.11  5013.3  262.98
  5054.1  264.63  5059.6  263.88  5065.8  264.78  5158.8  265.02  5180.8  262.99
  5193.0  259.67  5215.6  258.74  5230.5  259.89  5238.2  263.06  5246.9  264.81
  5268.9  265.07  5274.5  266.17  5310.1  266.65  5333.2  268.08  5627.5  269.99
#Mann=3,-1,0
  4402.4    0.05       0  4787.1    0.03       0  4793.1    0.05       0
Bank Sta=4787.1,4793.1
Exp/Cntr=0.3,0.1

Type RM Length L Ch R = 1,267,146,146,146
BEGIN DESCRIPTION:
Mapping XS 67a5643d
END DESCRIPTION:
XS GIS Cut Line= 5
      2241479.09     13206112.54      2241208.15     13205841.61
      2240943.79     13205696.21      2240637.14     13205868.04
      2240541.71     13205959.55
#Sta/Elev= 30
  4458.4  274.27  4774.5  257.07  4816.9  259.52  4824.0  261.61  4838.2  262.51
  4841.4  260.46  4882.3  258.93  4888.0  257.65  4963.7  256.37  4969.4  254.95
  5001.6  254.67  5007.3  253.13  5045.2  253.56  5047.9  252.44  5050.6  251.94
  5053.9  252.44  5088.7  253.63  5094.4  252.75  5110.5  253.88  5132.3  253.42
  5177.1  255.64  5193.0  256.92  5207.5  261.43  5220.5  263.45  5236.4  260.55
  5274.1  258.42  5301.5  259.86  5323.2  262.90  5404.2  266.45  5627.0  269.83
#Mann=3,-1,0
  4458.4    0.05       0  5047.9    0.03       0  5053.9    0.05       0
Bank Sta=5047.9,5053.9
Exp/Cntr=0.3,0.1

Type RM Length L Ch R = 1,121,0,0,0
BEGIN DESCRIPTION:
UNT 053 IN LACR 1.0
END DESCRIPTION:
XS GIS Cut Line= 5
      2241494.98     13205976.43      2241245.16     13205684.31
      2241032.35     13205610.29      2240860.52     13205667.13
      2240604.07     13205800.64
#Sta/Elev= 30
  4501.8  270.30  4748.1  254.48  4754.6  253.44  4762.3  248.54  4768.9  248.16
  4776.6  248.03  4783.2  253.89  4854.5  250.70  4896.5  249.70  4927.6  250.14
  4968.2  248.29  4978.8  250.00  4989.8  250.30  4999.9  248.93  5018.1  244.23
  5020.9  243.73  5024.1  244.23  5041.4  245.68  5046.7  251.61  5063.5  251.84
  5072.5  250.83  5103.6  252.46  5119.1  251.57  5177.2  251.92  5200.6  254.14
  5451.1  259.44  5456.7  260.59  5495.3  261.52  5500.9  262.45  5581.6  264.38
#Mann=3,-1,0
  4501.8    0.05       0  5018.1    0.03       0  5024.1    0.05       0
Bank Sta=5018.1,5024.1
Exp/Cntr=0.3,0.1

Chan Stop Cuts=-1