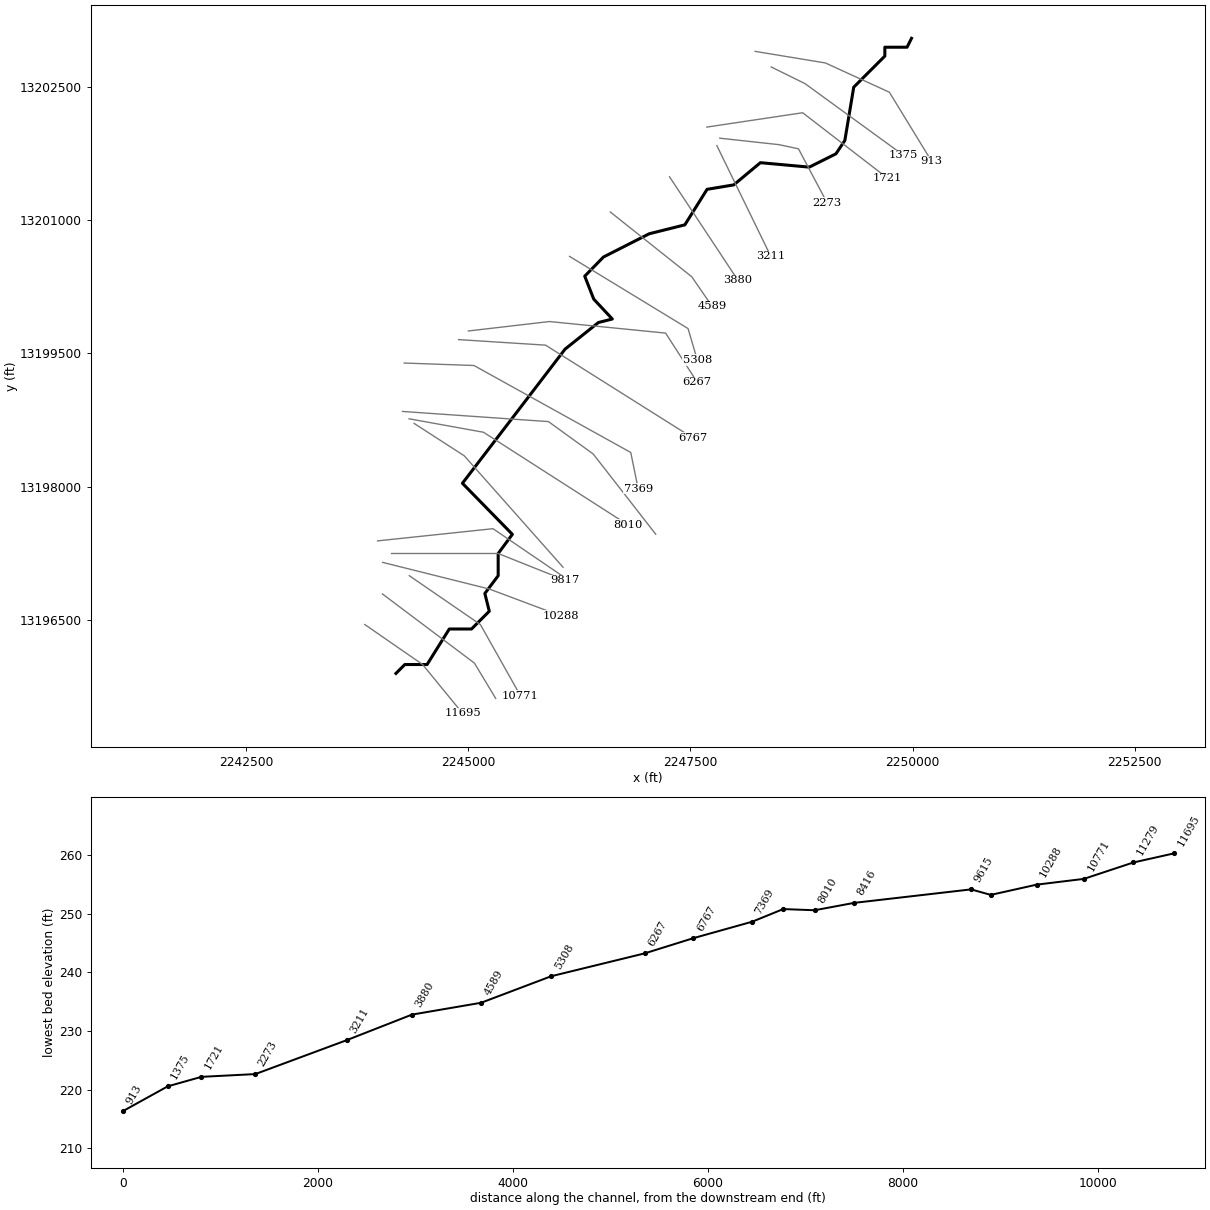
--- UNT 054 IN LACR.prj (project) ---

Proj Title=UNT 054 IN LACR Base Level Engineering
Current Plan=p01
Default Exp/Contr=0.3,0.1
English Units
Geom File=g01
Flow File=f01
Plan File=p01
BEGIN DESCRIPTION:
UNT 054 IN LACR
END DESCRIPTION:

--- UNT 054 IN LACR.p01 (plan) ---

Plan Title=Multiple Run
Short Identifier=Multiple
Geom File=g01
Flow File=f01
Subcritical Flow
K Sum by GR= 0
Std Step Tol= 0.01
Critical Tol= 0.01
Num of Std Step Trials= 20
Max Error Tol= 0.3
Flow Tol Ratio= 0.001
Split Flow NTrial= 30
Split Flow Tol= 0.02
Split Flow Ratio= 0.02
Log Output Level= 0
Friction Slope Method= 1
Unsteady Friction Slope Method= 2
Unsteady Bridges Friction Slope Method= 1
Parabolic Critical Depth
Global Vel Dist=  1 , 1 , 1
Global Log Level= 0
CheckData=True
Encroach Param= -1, 0, 0, 0
BEGIN DESCRIPTION:
Multiple Run
END DESCRIPTION:

--- UNT 054 IN LACR.f01 (steady flow) ---

Flow Title=Multiple
Number of Profiles=7
Profile Names=10-year,25-year,50-year,1pct_min,100-year,1pct_plu,500-year
River Rch & RM= UNT 054 IN LACR,Reach-1,11695
     305     426     528     481     651     880    1003
River Rch & RM= UNT 054 IN LACR,Reach-1,3880
     340     478     593     540     731     988    1128
River Rch & RM= UNT 054 IN LACR,Reach-1,1375
     360     508     633     580     784    1060    1220
Boundary for River Rch & Prof#=UNT 054 IN LACR,Reach-1,1
Up Type=0
Dn Type=3
Dn Slope=0.005
Boundary for River Rch & Prof#=UNT 054 IN LACR,Reach-1,2
Up Type=0
Dn Type=3
Dn Slope=0.005
Boundary for River Rch & Prof#=UNT 054 IN LACR,Reach-1,3
Up Type=0
Dn Type=3
Dn Slope=0.005
Boundary for River Rch & Prof#=UNT 054 IN LACR,Reach-1,4
Up Type=0
Dn Type=3
Dn Slope=0.005
Boundary for River Rch & Prof#=UNT 054 IN LACR,Reach-1,5
Up Type=0
Dn Type=3
Dn Slope=0.005
Boundary for River Rch & Prof#=UNT 054 IN LACR,Reach-1,6
Up Type=0
Dn Type=3
Dn Slope=0.005
Boundary for River Rch & Prof#=UNT 054 IN LACR,Reach-1,7
Up Type=0
Dn Type=3
Dn Slope=0.005

--- UNT 054 IN LACR.g01 (geometry) ---

Geom Title=Existing Conditions

River Reach=UNT 054 IN LACR,Reach-1
Reach XY= 30
      2244187.72     13195896.85      2244287.72     13195996.85
      2244537.72     13195996.85      2244787.72     13196396.86
      2245037.72     13196396.86      2245237.72     13196596.86
      2245187.72     13196796.85      2245337.72     13196996.85
      2245337.72     13197246.86      2245497.45     13197462.54
      2244935.47     13198037.54      2246090.59     13199548.09
      2246465.59     13199847.57      2246621.92     13199886.81
      2246412.74     13200111.03      2246311.58     13200369.00
      2246521.99     13200584.62      2247037.72     13200846.86
      2247437.72     13200946.85      2247687.72     13201346.86
      2247987.72     13201396.85      2248287.72     13201646.86
      2248837.72     13201596.85      2249137.72     13201746.85
      2249237.72     13201896.85      2249337.72     13202496.86
      2249687.72     13202846.85      2249687.72     13202946.85
      2249937.72     13202946.85      2249987.72     13203046.85

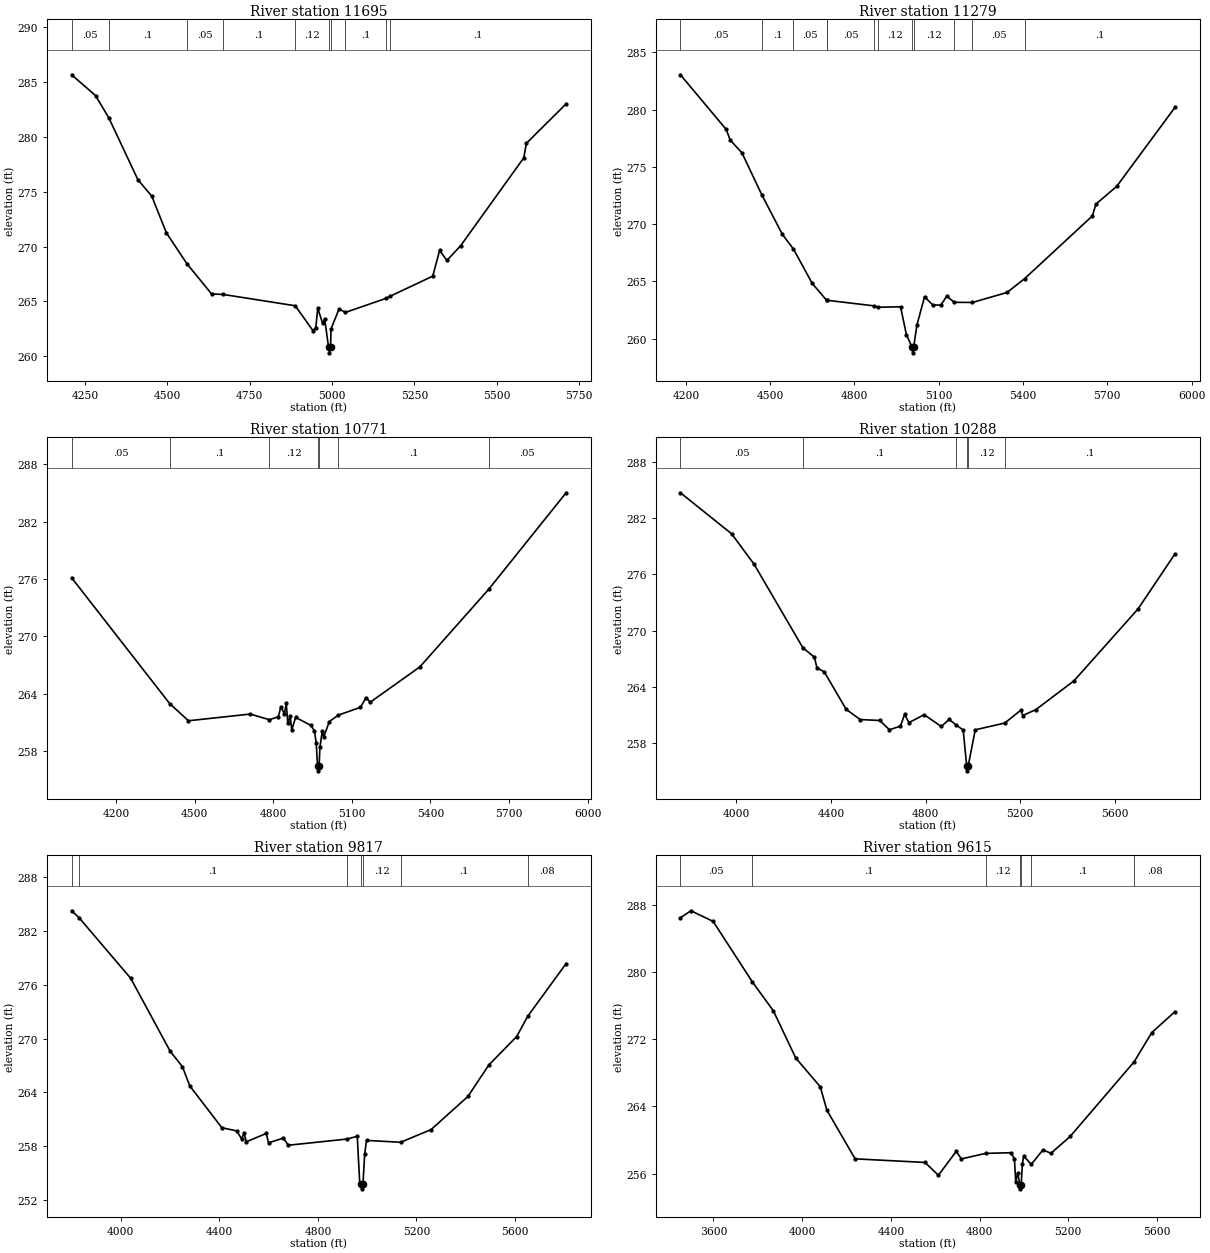
Type RM Length L Ch R = 1,11695,416,416,416
BEGIN DESCRIPTION:
UNT 054 IN LACR 14.0
END DESCRIPTION:
XS GIS Cut Line= 3
      2243837.70     13196446.87      2244487.72     13195996.85
      2244937.70     13195446.88
#Sta/Elev= 30
  4209.4  285.65  4282.4  283.75  4323.0  281.69  4410.8  276.08  4452.7  274.60
  4497.3  271.24  4560.0  268.41  4634.4  265.68  4670.0  265.63  4888.4  264.60
  4941.9  262.34  4950.7  262.61  4956.8  264.37  4971.6  262.99  4977.7  263.40
  4989.6  260.81  4992.3  260.31  4995.6  260.81  4997.0  262.49  5021.5  264.32
  5040.1  263.99  5164.7  265.28  5176.6  265.47  5305.8  267.30  5326.6  269.64
  5348.9  268.73  5390.5  270.07  5582.1  278.08  5590.0  279.40  5710.6  283.00
#Mann=10,-1,0
  4209.4    0.05       0  4323.0     0.1       0  4560.0    0.05       0
  4670.0     0.1       0  4888.4    0.12       0  4989.6    0.07       0
  4995.6    0.12       0  5040.1     0.1       0  5164.7    0.05       0
  5176.6     0.1       0
Bank Sta=4989.6,4995.6
Exp/Cntr=0.3,0.1

Type RM Length L Ch R = 1,11279,508,508,508
BEGIN DESCRIPTION:
UNT 054 IN LACR 13.0
END DESCRIPTION:
XS GIS Cut Line= 3
      2244035.37     13196791.64      2245070.54     13196012.74
      2245309.92     13195614.88
#Sta/Elev= 30
  4180.8  283.04  4343.5  278.27  4358.0  277.34  4399.7  276.22  4470.7  272.54
  4543.4  269.11  4582.6  267.84  4649.6  264.83  4700.9  263.35  4702.5  263.35
  4870.5  262.86  4882.4  262.74  4964.0  262.78  4984.9  260.36  5004.7  259.26
  5007.5  258.76  5010.7  259.26  5022.2  261.17  5049.4  263.66  5078.6  262.94
  5107.7  262.93  5128.5  263.71  5155.5  263.17  5219.9  263.16  5343.0  264.03
  5405.7  265.24  5646.5  270.71  5659.6  271.75  5733.4  273.30  5940.6  280.19
#Mann=12,-1,0
  4180.8    0.05       0  4470.7     0.1       0  4582.6    0.05       0
  4700.9     0.1       0  4702.5    0.05       0  4870.5     0.1       0
  4882.4    0.12       0  5004.7    0.07       0  5010.7    0.12       0
  5155.5     0.1       0  5219.9    0.05       0  5405.7     0.1       0
Bank Sta=5004.7,5010.7
Exp/Cntr=0.3,0.1

Type RM Length L Ch R = 1,10771,483,483,483
BEGIN DESCRIPTION:
UNT 054 IN LACR 12.0
END DESCRIPTION:
XS GIS Cut Line= 3
      2244337.74     13196996.84      2245137.72     13196446.85
      2245587.73     13195646.84
#Sta/Elev= 30
  4029.2  276.13  4404.3  262.97  4475.7  261.19  4711.8  261.89  4784.7  261.30
  4819.3  261.61  4828.2  262.65  4842.2  261.93  4849.1  263.00  4855.2  260.91
  4864.0  261.68  4870.1  260.24  4885.0  261.54  4941.8  260.73  4956.7  260.15
  4963.6  258.85  4968.6  256.46  4971.3  255.96  4974.6  256.46  4977.7  258.43
  4986.5  260.07  4992.6  259.52  5013.7  261.11  5048.0  261.78  5132.3  262.59
  5153.9  263.60  5169.9  263.13  5359.2  266.81  5621.7  274.90  5917.9  285.00
#Mann=7,-1,0
  4029.2    0.05       0  4404.3     0.1       0  4784.7    0.12       0
  4968.6    0.07       0  4974.6    0.12       0  5048.0     0.1       0
  5621.7    0.05       0
Bank Sta=4968.6,4974.6
Exp/Cntr=0.3,0.1

Type RM Length L Ch R = 1,10288,471,471,471
BEGIN DESCRIPTION:
UNT 054 IN LACR 11.0
END DESCRIPTION:
XS GIS Cut Line= 3
      2244037.75     13197146.85      2245237.72     13196846.85
      2246037.72     13196546.85
#Sta/Elev= 30
  3763.1  284.74  3979.5  280.35  4074.9  277.08  4280.4  268.17  4330.0  267.13
  4340.3  266.00  4371.2  265.58  4464.0  261.56  4523.3  260.47  4605.7  260.37
  4647.0  259.38  4693.3  259.76  4711.4  261.02  4729.4  260.14  4793.8  260.99
  4866.0  259.73  4899.5  260.48  4928.5  259.90  4958.8  259.35  4973.8  255.48
  4976.6  254.98  4979.8  255.48  5009.8  259.37  5134.9  260.10  5202.9  261.48
  5210.9  260.90  5266.1  261.53  5427.2  264.61  5698.7  272.32  5854.4  278.20
#Mann=6,-1,0
  3763.1    0.05       0  4280.4     0.1       0  4928.5    0.12       0
  4973.8    0.07       0  4979.8    0.12       0  5134.9     0.1       0
Bank Sta=4973.8,4979.8
Exp/Cntr=0.3,0.1

Type RM Length L Ch R = 1,9817,202,202,202
BEGIN DESCRIPTION:
UNT 054 IN LACR 10.0
END DESCRIPTION:
XS GIS Cut Line= 3
      2244137.72     13197246.85      2245337.72     13197246.86
      2246087.74     13196946.85
#Sta/Elev= 30
  3800.0  284.28  3830.3  283.51  4040.0  276.74  4200.0  268.61  4250.0  266.87
  4280.0  264.72  4410.0  260.06  4470.0  259.70  4490.0  258.83  4500.0  259.41
  4510.0  258.49  4590.0  259.41  4600.0  258.37  4660.0  258.90  4680.0  258.10
  4918.6  258.79  4960.0  259.10  4970.0  253.81  4977.0  253.73  4979.8  253.23
  4983.0  253.73  4990.0  257.11  4997.5  258.64  5136.0  258.43  5259.8  259.85
  5409.3  263.55  5494.1  267.06  5607.2  270.24  5651.7  272.49  5807.8  278.38
#Mann=7,-1,0
  3800.0    0.05       0  3830.3     0.1       0  4918.6    0.12       0
  4977.0    0.07       0  4983.0    0.12       0  5136.0     0.1       0
  5651.7    0.08       0
Bank Sta=4977,4983
Exp/Cntr=0.3,0.1

Type RM Length L Ch R = 1,9615,1199,1199,1199
BEGIN DESCRIPTION:
UNT 054 IN LACR 9.0
END DESCRIPTION:
XS GIS Cut Line= 3
      2243980.92     13197388.98      2245279.55     13197526.14
      2246043.11     13197005.53
#Sta/Elev= 30
  3451.3  286.52  3498.4  287.35  3598.9  286.08  3775.1  278.88  3870.4  275.41
  3971.0  269.79  4081.6  266.36  4111.8  263.55  4238.9  257.75  4554.2  257.32
  4614.5  255.79  4695.0  258.64  4718.3  257.74  4827.1  258.40  4942.4  258.48
  4957.3  257.75  4963.4  254.93  4972.3  256.06  4981.9  254.67  4984.7  254.17
  4987.9  254.67  4993.2  257.15  4999.3  258.08  5033.4  257.09  5086.0  258.82
  5121.9  258.41  5208.7  260.42  5497.3  269.33  5576.6  272.81  5681.3  275.31
#Mann=7,-1,0
  3451.3    0.05       0  3775.1     0.1       0  4827.1    0.12       0
  4981.9    0.07       0  4987.9    0.12       0  5033.4     0.1       0
  5497.3    0.08       0
Bank Sta=4981.9,4987.9
Exp/Cntr=0.3,0.1

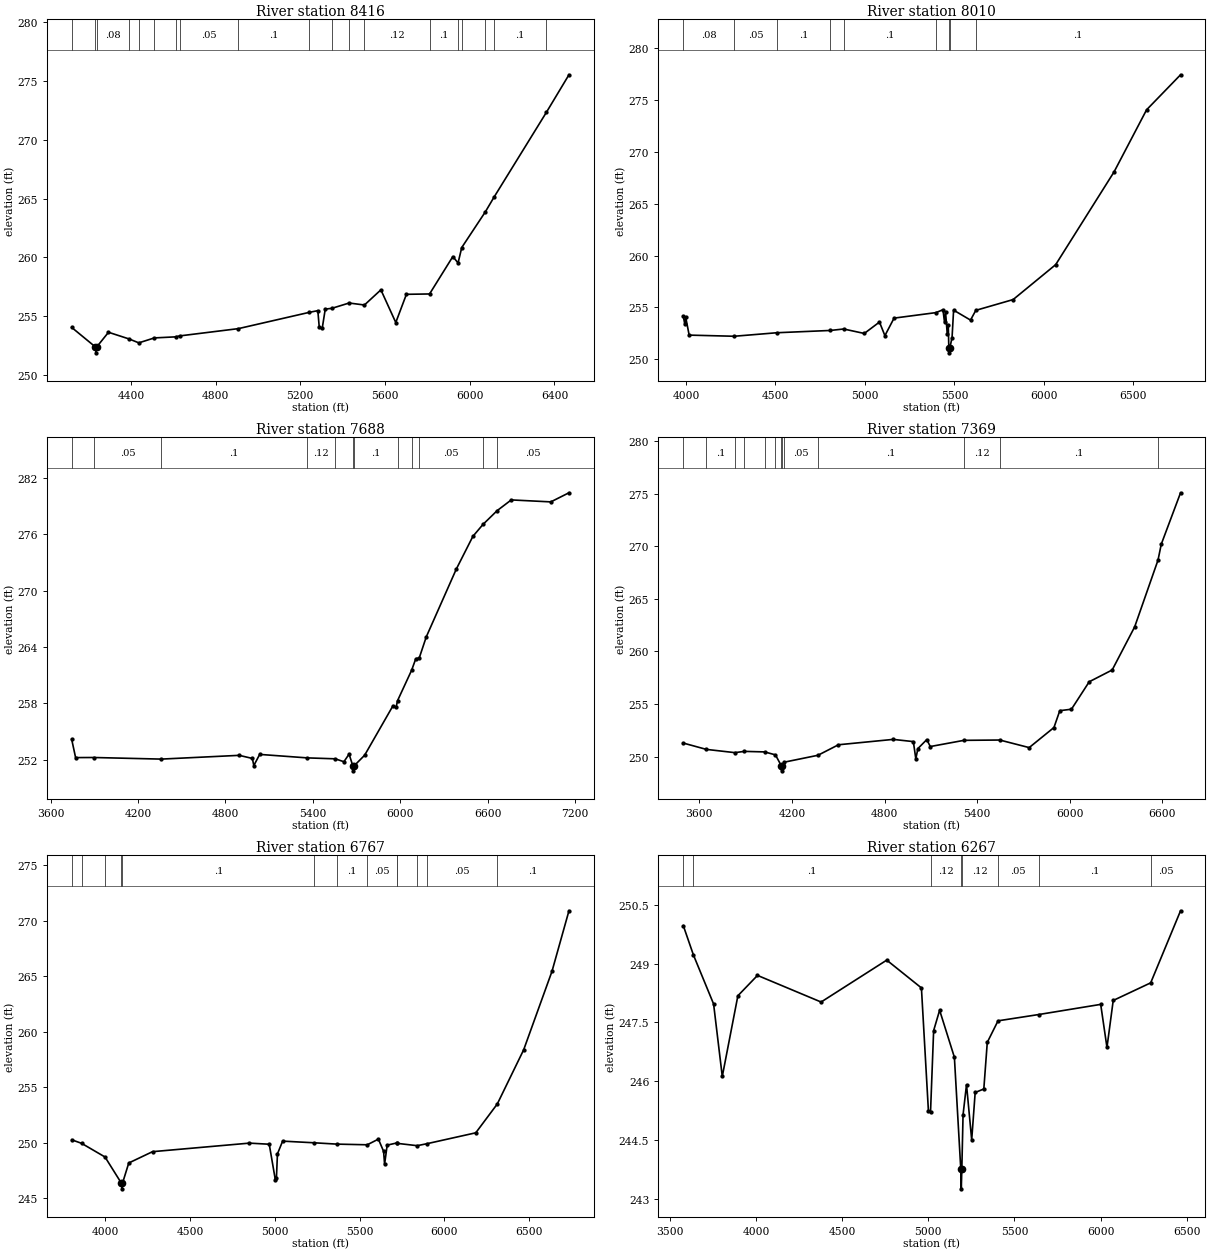
Type RM Length L Ch R = 1,8416,406,406,406
BEGIN DESCRIPTION:
Mapping XS 4cefc5b7
END DESCRIPTION:
XS GIS Cut Line= 4
      2244391.88     13198711.47      2244469.83     13198661.10
      2244956.13     13198346.88      2246067.25     13197092.53
#Sta/Elev= 30
  4120.8  254.03  4232.8  252.37  4235.5  251.87  4238.8  252.37  4294.4  253.62
  4391.9  253.05  4437.5  252.72  4511.0  253.14  4611.5  253.23  4630.2  253.31
  4907.6  253.93  5241.0  255.31  5282.7  255.46  5289.4  254.05  5303.6  253.98
  5317.8  255.59  5349.5  255.66  5430.4  256.11  5502.7  255.94  5580.4  257.23
  5650.7  254.45  5700.9  256.85  5810.2  256.88  5920.0  260.06  5944.8  259.52
  5962.1  260.83  6073.3  263.86  6115.3  265.14  6361.6  272.33  6468.3  275.53
#Mann=19,-1,0
  4120.8    0.08       0  4232.8    0.07       0  4238.8    0.08       0
  4391.9    0.05       0  4437.5    0.08       0  4511.0    0.05       0
  4611.5    0.08       0  4630.2    0.05       0  4907.6     0.1       0
  5241.0    0.08       0  5349.5     0.1       0  5430.4    0.08       0
  5502.7    0.12       0  5810.2     0.1       0  5944.8    0.08       0
  5962.1     0.1       0  6073.3    0.08       0  6115.3     0.1       0
  6361.6    0.08       0
Bank Sta=4232.8,4238.8
Exp/Cntr=0.3,0.1

Type RM Length L Ch R = 1,8010,322,322,322
BEGIN DESCRIPTION:
UNT 054 IN LACR 7.0
END DESCRIPTION:
XS GIS Cut Line= 3
      2244335.50     13198763.54      2245173.14     13198611.64
      2246794.93     13197570.92
#Sta/Elev= 30
  3985.2  254.13  3993.6  253.37  3998.7  254.03  4017.9  252.32  4269.4  252.21
  4508.5  252.55  4806.9  252.77  4881.2  252.91  4996.4  252.48  5081.2  253.58
  5111.6  252.27  5162.8  253.96  5396.6  254.49  5436.0  254.77  5444.6  253.58
  5450.5  254.54  5459.8  252.45  5465.7  253.26  5468.7  251.11  5471.4  250.61
  5474.7  251.11  5486.8  252.08  5495.4  254.73  5589.9  253.77  5619.6  254.71
  5828.1  255.75  6065.8  259.12  6392.0  268.07  6573.7  274.06  6763.5  277.44
#Mann=9,-1,0
  3985.2    0.08       0  4269.4    0.05       0  4508.5     0.1       0
  4806.9    0.05       0  4881.2     0.1       0  5396.6    0.12       0
  5468.7    0.07       0  5474.7    0.12       0  5619.6     0.1       0
Bank Sta=5468.7,5474.7
Exp/Cntr=0.3,0.1

Type RM Length L Ch R = 1,7688,319,319,319
BEGIN DESCRIPTION:
UNT 054 IN LACR 6.0
END DESCRIPTION:
XS GIS Cut Line= 4
      2244261.18     13198846.15      2245903.27     13198731.85
      2246406.75     13198367.27      2247109.89     13197464.46
#Sta/Elev= 30
  3744.8  254.15  3771.4  252.22  3896.9  252.23  4359.2  252.06  4894.1  252.46
  4984.3  252.13  4994.4  251.37  5034.5  252.56  5360.3  252.19  5552.8  252.09
  5612.5  251.78  5648.0  252.59  5674.4  251.31  5677.2  250.81  5680.4  251.31
  5754.7  252.47  5949.6  257.75  5970.5  257.56  5980.5  258.28  6077.1  261.52
  6105.8  262.75  6129.4  262.83  6177.8  265.08  6383.6  272.29  6497.6  275.78
  6567.5  277.06  6664.2  278.52  6760.9  279.66  7032.3  279.45  7156.8  280.42
#Mann=12,-1,0
  3744.8    0.08       0  3896.9    0.05       0  4359.2     0.1       0
  5360.3    0.12       0  5552.8     0.1       0  5674.4    0.07       0
  5680.4     0.1       0  5980.5    0.05       0  6077.1     0.1       0
  6129.4    0.05       0  6567.5     0.1       0  6664.2    0.05       0
Bank Sta=5674.4,5680.4
Exp/Cntr=0.3,0.1

Type RM Length L Ch R = 1,7369,602,602,602
BEGIN DESCRIPTION:
UNT 054 IN LACR 5.0
END DESCRIPTION:
XS GIS Cut Line= 4
      2244280.78     13199391.15      2245065.50     13199363.38
      2246829.39     13198384.21      2246912.73     13197974.45
#Sta/Elev= 30
  3496.4  251.29  3645.5  250.69  3830.7  250.38  3891.4  250.50  4022.5  250.45
  4093.1  250.17  4130.7  249.15  4133.5  248.65  4136.7  249.15  4148.8  249.47
  4368.5  250.13  4501.5  251.13  4856.0  251.64  4986.4  251.43  5002.4  249.80
  5016.1  250.77  5073.4  251.62  5096.2  250.96  5314.2  251.55  5546.0  251.58
  5736.7  250.86  5897.2  252.77  5935.0  254.37  6010.5  254.51  6125.6  257.12
  6274.3  258.24  6420.0  262.34  6571.2  268.69  6592.3  270.20  6717.2  275.09
#Mann=13,-1,0
  3496.4    0.05       0  3645.5     0.1       0  3830.7    0.05       0
  3891.4     0.1       0  4022.5    0.05       0  4093.1     0.1       0
  4130.7    0.07       0  4136.7     0.1       0  4148.8    0.05       0
  4368.5     0.1       0  5314.2    0.12       0  5546.0     0.1       0
  6571.2    0.05       0
Bank Sta=4130.7,4136.7
Exp/Cntr=0.3,0.1

Type RM Length L Ch R = 1,6767,500,500,500
BEGIN DESCRIPTION:
UNT 054 IN LACR 4.0
END DESCRIPTION:
XS GIS Cut Line= 3
      2244891.88     13199655.04      2245871.06     13199592.54
      2247522.47     13198551.74
#Sta/Elev= 30
  3802.2  250.27  3860.6  249.95  3998.6  248.72  4095.6  246.35  4098.4  245.85
  4101.6  246.35  4138.7  248.18  4279.0  249.20  4850.3  249.97  4967.4  249.87
  5003.9  246.61  5009.8  246.84  5015.8  249.00  5046.3  250.15  5232.7  250.00
  5366.8  249.88  5545.6  249.82  5611.3  250.33  5641.9  249.23  5647.8  248.07
  5663.1  249.79  5718.6  249.98  5721.6  249.95  5839.9  249.74  5895.5  249.91
  6185.7  250.90  6312.7  253.50  6468.2  258.38  6635.2  265.45  6735.4  270.91
#Mann=13,-1,0
  3802.2     0.1       0  3860.6    0.05       0  3998.6     0.1       0
  4095.6    0.07       0  4101.6     0.1       0  5232.7    0.12       0
  5366.8     0.1       0  5545.6    0.05       0  5718.6    0.12       0
  5721.6    0.05       0  5839.9    0.12       0  5895.5    0.05       0
  6312.7     0.1       0
Bank Sta=4095.6,4101.6
Exp/Cntr=0.3,0.1

Type RM Length L Ch R = 1,6267,959,959,959
BEGIN DESCRIPTION:
Mapping XS 420270de
END DESCRIPTION:
XS GIS Cut Line= 4
      2245002.96     13199752.26      2245914.48     13199858.39
      2247221.77     13199728.18      2247575.96     13199176.06
#Sta/Elev= 30
  3577.4  249.97  3636.3  249.22  3753.3  247.97  3803.7  246.12  3894.3  248.18
  4008.2  248.70  4377.5  248.02  4758.7  249.09  4960.1  248.38  5000.8  245.23
  5013.0  245.22  5031.0  247.29  5065.8  247.81  5151.5  246.61  5188.7  243.75
  5191.5  243.25  5194.7  243.75  5201.8  245.14  5221.9  245.91  5252.0  244.50
  5272.2  245.71  5322.4  245.80  5342.5  246.99  5404.9  247.54  5640.2  247.70
  6001.1  247.96  6037.5  246.86  6073.8  248.06  6291.4  248.51  6464.8  250.35
#Mann=8,-1,0
  3577.4    0.05       0  3636.3     0.1       0  5013.0    0.12       0
  5188.7    0.07       0  5194.7    0.12       0  5404.9    0.05       0
  5640.2     0.1       0  6291.4    0.05       0
Bank Sta=5188.7,5194.7
Exp/Cntr=0.3,0.1

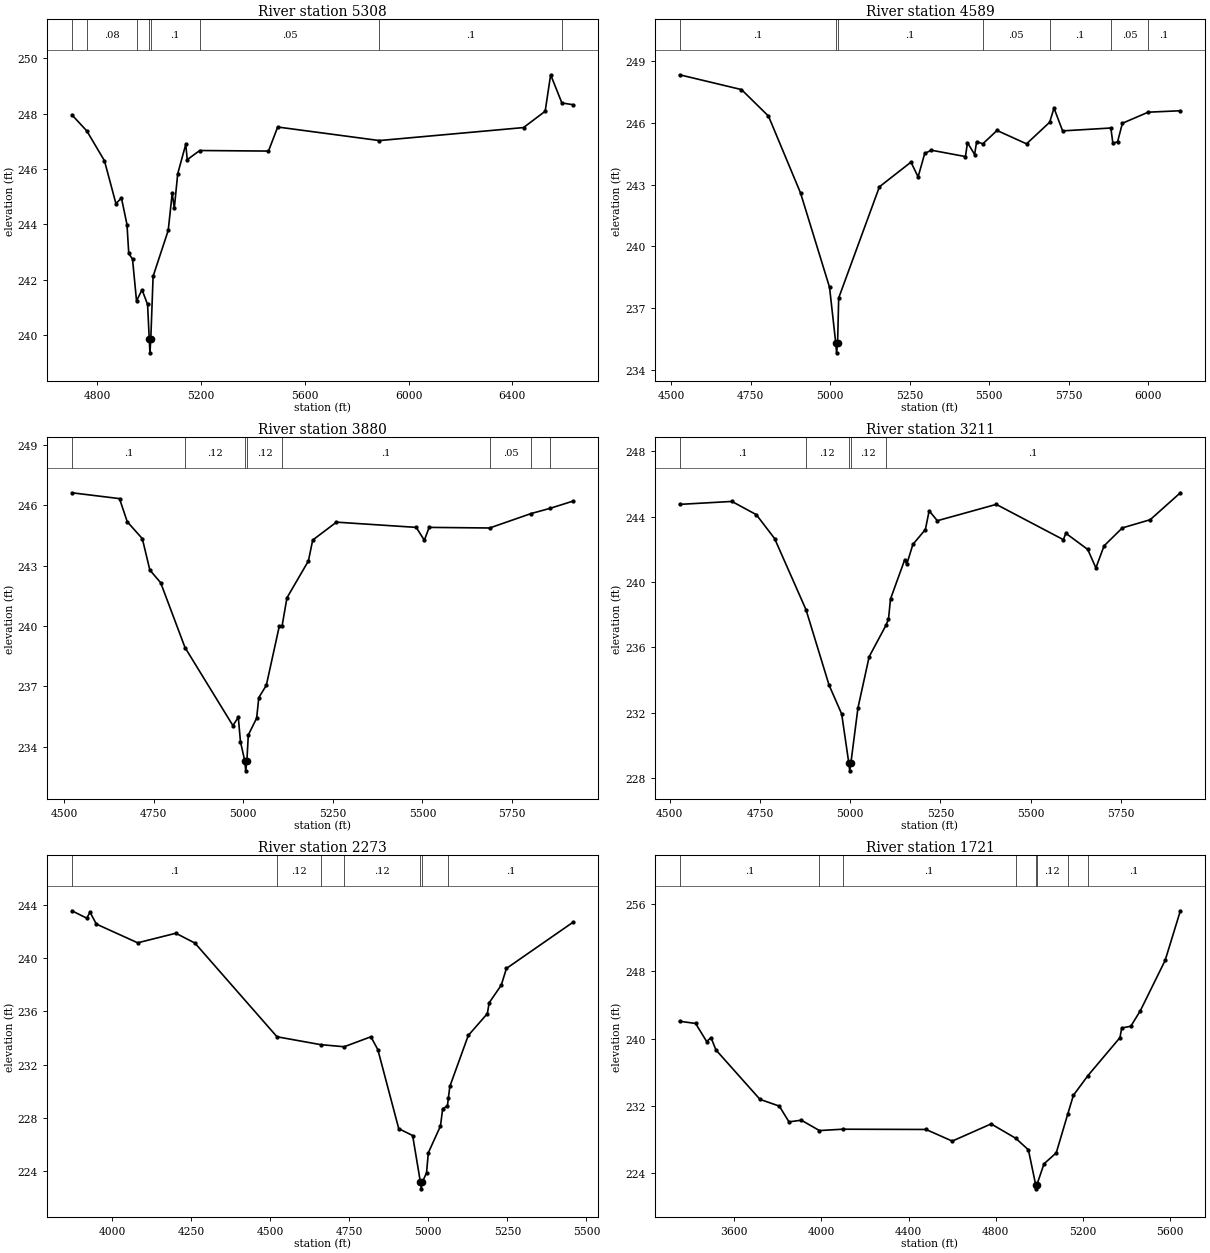
Type RM Length L Ch R = 1,5308,719,719,719
BEGIN DESCRIPTION:
Mapping XS 420270de1
END DESCRIPTION:
XS GIS Cut Line= 3
      2246140.55     13200591.88      2247473.91     13199779.36
      2247578.08     13199425.18
#Sta/Elev= 30
  4701.6  247.96  4759.0  247.38  4827.1  246.30  4871.3  244.75  4892.7  244.95
  4914.0  243.99  4920.8  242.95  4935.3  242.74  4950.8  241.23  4972.1  241.63
  4993.4  241.10  4999.8  239.85  5002.5  239.35  5005.8  239.85  5014.7  242.12
  5073.0  243.78  5088.3  245.13  5096.4  244.58  5109.6  245.83  5140.5  246.89
  5146.4  246.34  5194.4  246.67  5459.5  246.65  5495.0  247.52  5887.0  247.03
  6442.8  247.50  6526.2  248.09  6547.3  249.41  6590.7  248.39  6632.2  248.33
#Mann=8,-1,0
  4701.6     0.1       0  4759.0    0.08       0  4950.8     0.1       0
  4999.8    0.07       0  5005.8     0.1       0  5194.4    0.05       0
  5887.0     0.1       0  6590.7    0.05       0
Bank Sta=4999.8,5005.8
Exp/Cntr=0.3,0.1

Type RM Length L Ch R = 1,4589,709,709,709
BEGIN DESCRIPTION:
Mapping XS 0c526745
END DESCRIPTION:
XS GIS Cut Line= 3
      2246598.90     13201091.87      2247515.57     13200362.69
      2247744.72     13200029.39
#Sta/Elev= 30
  4526.1  248.35  4720.8  247.63  4805.7  246.34  4906.6  242.60  4997.9  238.01
  5017.3  235.32  5020.1  234.82  5023.3  235.32  5026.7  237.49  5154.9  242.90
  5254.2  244.10  5276.6  243.38  5297.4  244.52  5318.2  244.68  5425.6  244.37
  5432.0  245.05  5454.4  244.47  5460.8  245.10  5480.2  244.99  5524.9  245.64
  5617.8  244.99  5690.6  246.04  5704.2  246.73  5731.3  245.62  5883.1  245.76
  5889.6  245.01  5904.5  245.10  5919.4  245.99  6000.6  246.53  6101.9  246.60
#Mann=7,-1,0
  4526.1     0.1       0  5017.3    0.07       0  5023.3     0.1       0
  5480.2    0.05       0  5690.6     0.1       0  5883.1    0.05       0
  6000.6     0.1       0
Bank Sta=5017.3,5023.3
Exp/Cntr=0.3,0.1

Type RM Length L Ch R = 1,3880,669,669,669
BEGIN DESCRIPTION:
Mapping XS e0b94a53
END DESCRIPTION:
XS GIS Cut Line= 2
      2247265.56     13201487.71      2248036.11     13200321.47
#Sta/Elev= 30
  4521.5  246.62  4654.4  246.33  4676.0  245.18  4718.1  244.34  4739.1  242.78
  4769.3  242.15  4837.2  238.93  4970.9  235.05  4986.0  235.46  4992.0  234.25
  5004.0  233.30  5006.8  232.80  5010.0  233.30  5013.9  234.58  5037.2  235.42
  5043.2  236.44  5064.2  237.05  5100.3  239.98  5108.0  239.98  5121.8  241.40
  5181.6  243.23  5193.7  244.27  5259.9  245.16  5482.6  244.90  5505.3  244.26
  5518.7  244.90  5687.6  244.87  5803.7  245.59  5855.0  245.84  5919.3  246.20
#Mann=8,-1,0
  4521.5     0.1       0  4837.2    0.12       0  5004.0    0.07       0
  5010.0    0.12       0  5108.0     0.1       0  5687.6    0.05       0
  5803.7     0.1       0  5855.0    0.05       0
Bank Sta=5004,5010
Exp/Cntr=0.3,0.1

Type RM Length L Ch R = 1,3211,938,938,938
BEGIN DESCRIPTION:
UNT 054 IN LACR 3.0
END DESCRIPTION:
XS GIS Cut Line= 2
      2247797.81     13201839.16      2248405.31     13200591.61
#Sta/Elev= 30
  4527.1  244.75  4672.0  244.93  4739.7  244.12  4790.3  242.66  4877.4  238.30
  4941.2  233.69  4976.2  231.92  4995.8  228.94  4998.5  228.44  5001.8  228.94
  5021.3  232.29  5052.4  235.43  5098.7  237.34  5105.9  237.72  5111.5  238.96
  5151.0  241.37  5156.6  241.09  5173.5  242.30  5208.1  243.21  5218.6  244.36
  5241.2  243.75  5404.5  244.75  5590.4  242.59  5597.4  242.98  5658.1  241.99
  5680.6  240.86  5703.2  242.21  5753.8  243.31  5831.0  243.81  5914.7  245.46
#Mann=5,-1,0
  4527.1     0.1       0  4877.4    0.12       0  4995.8    0.07       0
  5001.8    0.12       0  5098.7     0.1       0
Bank Sta=4995.8,5001.8
Exp/Cntr=0.3,0.1

Type RM Length L Ch R = 1,2273,552,552,552
BEGIN DESCRIPTION:
UNT 054 IN LACR 2.0
END DESCRIPTION:
XS GIS Cut Line= 4
      2247830.85     13201922.65      2248497.51     13201849.73
      2248716.26     13201802.86      2249039.18     13201193.49
#Sta/Elev= 30
  3872.5  243.57  3919.7  243.01  3929.7  243.47  3949.8  242.57  4080.6  241.16
  4201.3  241.88  4261.7  241.14  4521.3  234.09  4659.0  233.50  4733.7  233.34
  4818.3  234.09  4840.3  233.12  4906.3  227.18  4950.3  226.66  4974.9  223.15
  4977.7  222.65  4980.9  223.15  4994.3  223.86  5000.0  225.37  5038.3  227.37
  5045.3  228.67  5060.3  228.89  5063.5  229.50  5067.9  230.35  5126.3  234.19
  5186.6  235.83  5192.4  236.65  5230.6  237.97  5246.9  239.23  5456.5  242.69
#Mann=7,-1,0
  3872.5     0.1       0  4521.3    0.12       0  4659.0     0.1       0
  4733.7    0.12       0  4974.9    0.07       0  4980.9    0.12       0
  5063.5     0.1       0
Bank Sta=4974.9,4980.9
Exp/Cntr=0.3,0.1

Type RM Length L Ch R = 1,1721,346,346,346
BEGIN DESCRIPTION:
Mapping XS f6a0962f
END DESCRIPTION:
XS GIS Cut Line= 3
      2247685.04     13202047.65      2248763.14     13202209.11
      2249720.00     13201470.66
#Sta/Elev= 30
  3348.9  242.05  3422.4  241.79  3473.0  239.65  3493.2  240.11  3515.4  238.66
  3717.8  232.79  3806.6  231.99  3851.0  230.12  3907.7  230.32  3990.7  229.09
  4097.4  229.25  4480.0  229.22  4600.5  227.84  4778.9  229.88  4892.2  228.17
  4950.1  226.80  4983.3  222.68  4986.1  222.18  4989.3  222.68  5021.7  225.15
  5077.8  226.44  5130.7  231.04  5156.6  233.27  5223.4  235.61  5370.4  240.11
  5378.5  241.25  5420.2  241.46  5463.7  243.29  5577.8  249.27  5647.7  255.15
#Mann=8,-1,0
  3348.9     0.1       0  3990.7    0.12       0  4097.4     0.1       0
  4892.2    0.12       0  4983.3    0.07       0  4989.3    0.12       0
  5130.7    0.08       0  5223.4     0.1       0
Bank Sta=4983.3,4989.3
Exp/Cntr=0.3,0.1

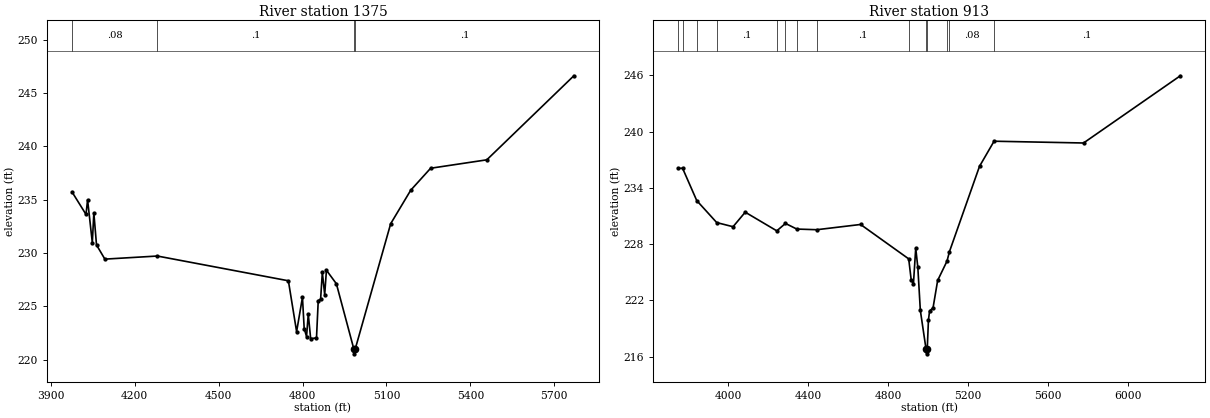
Type RM Length L Ch R = 1,1375,462,462,462
BEGIN DESCRIPTION:
Mapping XS 3db3f597
END DESCRIPTION:
XS GIS Cut Line= 3
      2248408.93     13202724.75      2248789.18     13202537.23
      2249897.27     13201730.88
#Sta/Elev= 30
  3975.5  235.75  4025.8  233.63  4031.4  235.00  4048.3  230.99  4053.8  233.77
  4063.3  230.77  4093.2  229.44  4280.8  229.73  4749.3  227.41  4778.7  222.64
  4799.6  225.86  4805.8  222.93  4814.2  222.18  4820.4  224.29  4828.9  221.99
  4849.8  222.05  4856.0  225.54  4864.5  225.69  4870.7  228.19  4879.1  226.11
  4885.3  228.40  4920.9  227.13  4982.8  221.06  4985.5  220.56  4988.8  221.06
  5115.0  232.76  5186.7  235.90  5257.8  237.96  5458.7  238.75  5769.9  246.63
#Mann=4,-1,0
  3975.5    0.08       0  4280.8     0.1       0  4982.8    0.07       0
  4988.8     0.1       0
Bank Sta=4982.8,4988.8
Exp/Cntr=0.3,0.1

Type RM Length L Ch R = 1,913,0,0,0
BEGIN DESCRIPTION:
UNT 054 IN LACR 1.0
END DESCRIPTION:
XS GIS Cut Line= 4
      2248228.42     13202900.08      2249018.35     13202769.87
      2249738.83     13202440.01      2250215.34     13201660.28
#Sta/Elev= 30
  3752.5  236.09  3773.2  236.11  3844.0  232.66  3943.9  230.31  4025.4  229.87
  4086.2  231.42  4243.8  229.43  4287.2  230.22  4343.7  229.62  4443.7  229.55
  4662.4  230.11  4902.7  226.44  4915.3  224.17  4926.3  223.78  4937.8  227.58
  4948.3  225.53  4960.8  220.94  4989.3  216.81  4992.1  216.31  4995.3  216.81
  5001.3  219.91  5006.8  220.86  5024.3  221.22  5047.3  224.14  5094.0  226.20
  5106.2  227.21  5256.3  236.31  5329.0  238.99  5775.9  238.80  6259.3  245.97
#Mann=14,-1,0
  3752.5    0.05       0  3773.2    0.08       0  3844.0    0.05       0
  3943.9     0.1       0  4243.8    0.05       0  4287.2     0.1       0
  4343.7    0.05       0  4443.7     0.1       0  4902.7    0.12       0
  4989.3    0.07       0  4995.3    0.12       0  5094.0     0.1       0
  5106.2    0.08       0  5329.0     0.1       0
Bank Sta=4989.3,4995.3
Exp/Cntr=0.3,0.1

Chan Stop Cuts=-1