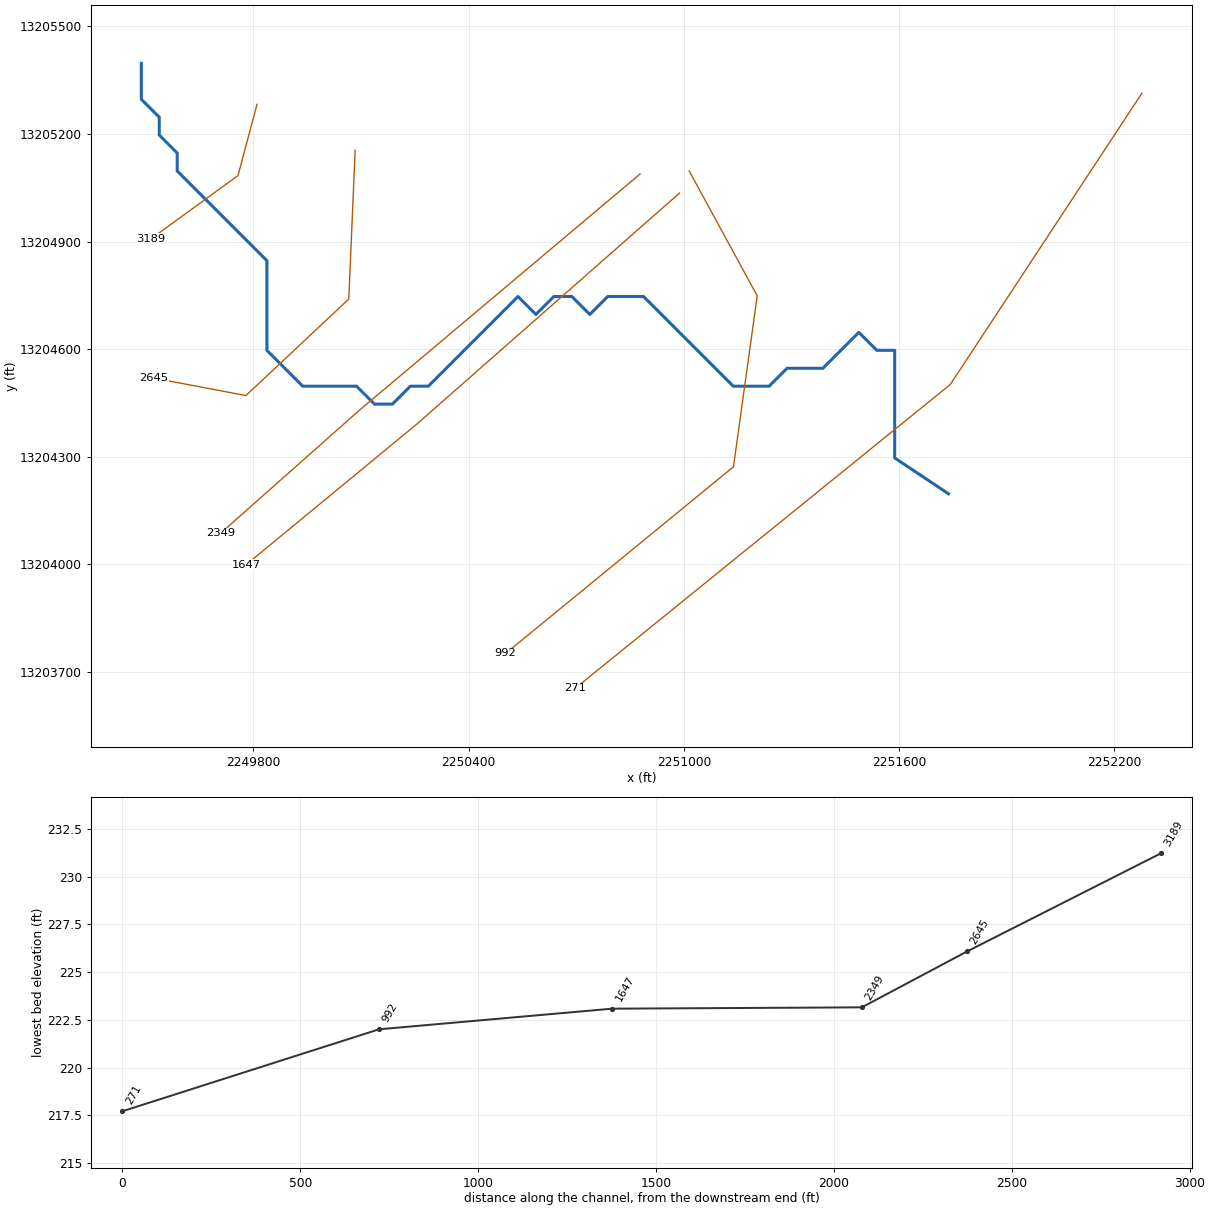
--- UNT 055 IN LACR.prj (project) ---

Proj Title=UNT 055 IN LACR Base Level Engineering
Current Plan=p01
Default Exp/Contr=0.3,0.1
English Units
Geom File=g01
Flow File=f01
Plan File=p01
BEGIN DESCRIPTION:
UNT 055 IN LACR
END DESCRIPTION:

--- UNT 055 IN LACR.p01 (plan) ---

Plan Title=Multiple Run
Short Identifier=Multiple
Geom File=g01
Flow File=f01
Subcritical Flow
K Sum by GR= 0
Std Step Tol= 0.01
Critical Tol= 0.01
Num of Std Step Trials= 20
Max Error Tol= 0.3
Flow Tol Ratio= 0.001
Split Flow NTrial= 30
Split Flow Tol= 0.02
Split Flow Ratio= 0.02
Log Output Level= 0
Friction Slope Method= 1
Unsteady Friction Slope Method= 2
Unsteady Bridges Friction Slope Method= 1
Parabolic Critical Depth
Global Vel Dist=  1 , 1 , 1
Global Log Level= 0
CheckData=True
Encroach Param= -1, 0, 0, 0
BEGIN DESCRIPTION:
Multiple Run
END DESCRIPTION:

--- UNT 055 IN LACR.f01 (steady flow) ---

Flow Title=Multiple
Number of Profiles=7
Profile Names=10-year,25-year,50-year,1pct_min,100-year,1pct_plu,500-year
River Rch & RM= UNT 055 IN LACR,Reach-1,3189
     160     214     257     227     308     416     446
River Rch & RM= UNT 055 IN LACR,Reach-1,271
     191     259     313     279     377     510     555
Boundary for River Rch & Prof#=UNT 055 IN LACR,Reach-1,1
Up Type=0
Dn Type=3
Dn Slope=0.005
Boundary for River Rch & Prof#=UNT 055 IN LACR,Reach-1,2
Up Type=0
Dn Type=3
Dn Slope=0.005
Boundary for River Rch & Prof#=UNT 055 IN LACR,Reach-1,3
Up Type=0
Dn Type=3
Dn Slope=0.005
Boundary for River Rch & Prof#=UNT 055 IN LACR,Reach-1,4
Up Type=0
Dn Type=3
Dn Slope=0.005
Boundary for River Rch & Prof#=UNT 055 IN LACR,Reach-1,5
Up Type=0
Dn Type=3
Dn Slope=0.005
Boundary for River Rch & Prof#=UNT 055 IN LACR,Reach-1,6
Up Type=0
Dn Type=3
Dn Slope=0.005
Boundary for River Rch & Prof#=UNT 055 IN LACR,Reach-1,7
Up Type=0
Dn Type=3
Dn Slope=0.005

--- UNT 055 IN LACR.g01 (geometry) ---

Geom Title=Existing Conditions

River Reach=UNT 055 IN LACR,Reach-1
Reach XY= 30
      2249487.72     13205396.85      2249487.72     13205296.85
      2249537.72     13205246.85      2249537.72     13205196.85
      2249587.72     13205146.85      2249587.72     13205096.86
      2249837.72     13204846.85      2249837.72     13204596.85
      2249937.72     13204496.85      2250087.72     13204496.85
      2250137.72     13204446.86      2250187.72     13204446.86
      2250237.72     13204496.85      2250287.72     13204496.85
      2250537.72     13204746.85      2250587.72     13204696.85
      2250637.72     13204746.85      2250687.72     13204746.85
      2250737.72     13204696.85      2250787.72     13204746.85
      2250887.72     13204746.85      2251137.72     13204496.85
      2251237.72     13204496.85      2251287.72     13204546.85
      2251387.72     13204546.85      2251487.72     13204646.85
      2251537.72     13204596.85      2251587.72     13204596.85
      2251587.72     13204296.86      2251737.72     13204196.85

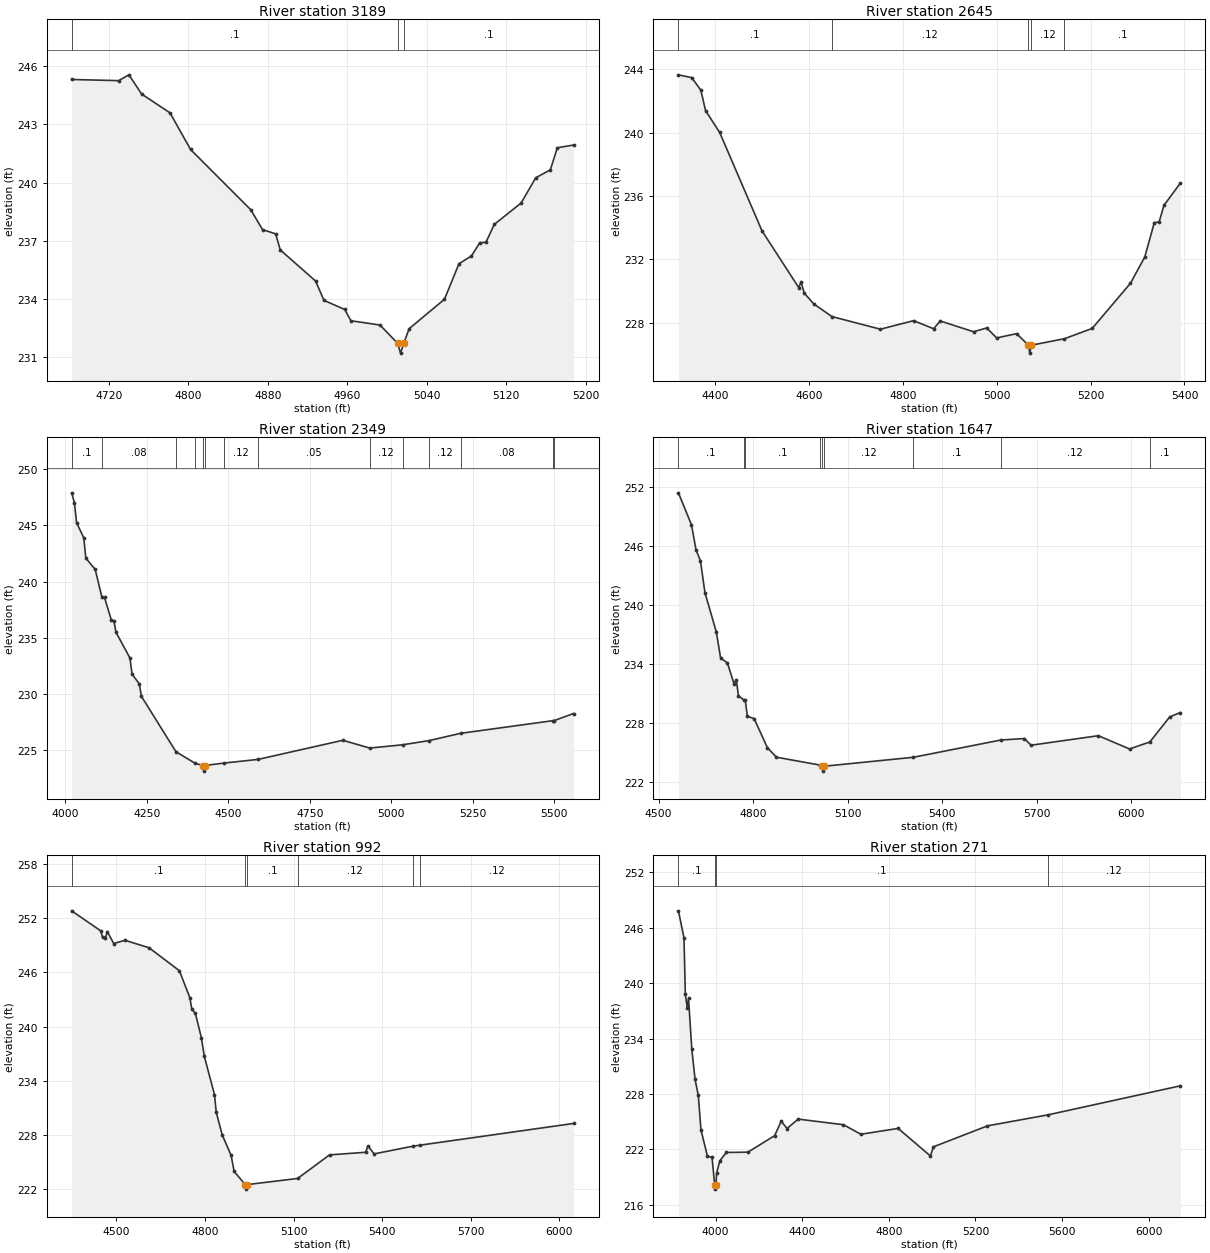
Type RM Length L Ch R = 1,3189,544,544,544
BEGIN DESCRIPTION:
UNT 055 IN LACR 3.0
END DESCRIPTION:
XS GIS Cut Line= 3
      2249810.19     13205282.62      2249757.23     13205084.03
      2249514.56     13204907.54
#Sta/Elev= 30
  4682.3  245.32  4729.7  245.26  4740.0  245.56  4752.8  244.57  4781.4  243.60
  4802.1  241.71  4862.8  238.60  4874.6  237.58  4887.8  237.36  4892.5  236.53
  4928.0  234.93  4936.5  233.93  4957.4  233.46  4963.6  232.88  4992.9  232.66
  5010.8  231.71  5013.6  231.21  5016.8  231.71  5022.3  232.47  5057.9  233.99
  5072.5  235.82  5085.1  236.22  5093.4  236.90  5099.6  236.92  5108.1  237.85
  5135.1  238.95  5149.8  240.25  5164.5  240.66  5171.6  241.80  5187.9  241.94
#Mann=3,-1,0
  4682.3     0.1       0  5010.8    0.07       0  5016.8     0.1       0
Bank Sta=5010.8,5016.8
Exp/Cntr=0.3,0.1

Type RM Length L Ch R = 1,2645,296,296,296
BEGIN DESCRIPTION:
Mapping XS 4241edf1
END DESCRIPTION:
XS GIS Cut Line= 4
      2250083.75     13205154.65      2250066.10     13204739.86
      2249779.29     13204470.70      2249523.34     13204519.25
#Sta/Elev= 30
  4322.1  243.65  4350.6  243.47  4369.9  242.68  4379.9  241.39  4410.0  240.01
  4500.1  233.80  4578.3  230.22  4583.3  230.57  4590.1  229.87  4610.2  229.19
  4648.9  228.39  4752.3  227.59  4823.1  228.13  4865.6  227.62  4879.8  228.11
  4950.6  227.43  4978.9  227.67  4999.9  227.04  5042.4  227.31  5067.7  226.58
  5070.5  226.08  5073.7  226.58  5144.3  226.99  5203.4  227.64  5284.9  230.49
  5315.4  232.15  5335.7  234.32  5345.9  234.36  5356.3  235.41  5391.1  236.81
#Mann=5,-1,0
  4322.1     0.1       0  4648.9    0.12       0  5067.7    0.07       0
  5073.7    0.12       0  5144.3     0.1       0
Bank Sta=5067.7,5073.7
Exp/Cntr=0.3,0.1

Type RM Length L Ch R = 1,2349,702,702,702
BEGIN DESCRIPTION:
Mapping XS 14d0c6bc
END DESCRIPTION:
XS GIS Cut Line= 3
      2250877.97     13205088.44      2250096.98     13204430.99
      2249708.72     13204086.85
#Sta/Elev= 30
  4019.3  247.88  4027.8  247.02  4034.4  245.23  4056.4  243.89  4063.0  242.07
  4091.6  241.07  4111.9  238.64  4120.2  238.58  4141.0  236.58  4148.8  236.51
  4155.3  235.49  4198.2  233.20  4204.7  231.76  4226.8  230.91  4233.3  229.80
  4339.4  224.87  4398.1  223.85  4421.8  223.65  4424.6  223.15  4427.8  223.65
  4487.9  223.87  4590.8  224.19  4851.1  225.89  4933.9  225.20  5034.6  225.49
  5115.3  225.86  5212.7  226.51  5497.4  227.64  5499.5  227.64  5559.0  228.27
#Mann=14,-1,0
  4019.3     0.1       0  4111.9    0.08       0  4339.4     0.1       0
  4398.1    0.05       0  4421.8    0.07       0  4427.8    0.05       0
  4487.9    0.12       0  4590.8    0.05       0  4933.9    0.12       0
  5034.6    0.05       0  5115.3    0.12       0  5212.7    0.08       0
  5497.4     0.1       0  5499.5    0.08       0
Bank Sta=4421.8,4427.8
Exp/Cntr=0.3,0.1

Type RM Length L Ch R = 1,1647,655,655,655
BEGIN DESCRIPTION:
UNT 055 IN LACR 2.0
END DESCRIPTION:
XS GIS Cut Line= 3
      2250988.25     13205035.46      2250255.83     13204391.28
      2249779.29     13203998.58
#Sta/Elev= 30
  4563.0  251.44  4604.5  248.18  4618.8  245.64  4633.0  244.49  4647.2  241.26
  4683.2  237.27  4696.9  234.61  4718.4  234.11  4739.3  232.00  4746.8  232.37
  4753.5  230.75  4769.6  230.35  4775.2  230.29  4781.9  228.67  4803.4  228.43
  4845.5  225.46  4874.0  224.50  5011.6  223.70  5019.9  223.58  5022.7  223.08
  5025.9  223.58  5308.4  224.49  5586.4  226.25  5661.2  226.40  5682.0  225.72
  5895.7  226.69  5994.7  225.34  6059.1  226.05  6122.4  228.61  6155.9  229.05
#Mann=9,-1,0
  4563.0     0.1       0  4769.6    0.08       0  4775.2     0.1       0
  5011.6    0.12       0  5019.9    0.07       0  5025.9    0.12       0
  5308.4     0.1       0  5586.4    0.12       0  6059.1     0.1       0
Bank Sta=5019.9,5025.9
Exp/Cntr=0.3,0.1

Type RM Length L Ch R = 1,992,721,721,721
BEGIN DESCRIPTION:
Mapping XS 56fbb716
END DESCRIPTION:
XS GIS Cut Line= 4
      2251014.77     13205097.25      2251204.49     13204748.68
      2251138.31     13204272.15      2250503.17     13203751.69
#Sta/Elev= 30
  4348.9  252.81  4447.7  250.59  4453.4  249.88  4463.2  249.79  4469.5  250.52
  4491.4  249.19  4529.3  249.55  4611.0  248.72  4713.7  246.18  4749.2  243.18
  4755.6  241.94  4767.8  241.46  4788.0  238.77  4798.1  236.70  4832.4  232.47
  4838.5  230.49  4858.7  228.00  4888.9  225.73  4899.0  223.96  4936.4  222.50
  4939.2  222.00  4942.4  222.50  5113.9  223.18  5222.0  225.79  5344.1  226.08
  5352.0  226.79  5372.8  225.90  5503.7  226.75  5526.8  226.86  6048.0  229.27
#Mann=6,-1,0
  4348.9     0.1       0  4936.4    0.07       0  4942.4     0.1       0
  5113.9    0.12       0  5503.7     0.1       0  5526.8    0.12       0
Bank Sta=4936.4,4942.4
Exp/Cntr=0.3,0.1

Type RM Length L Ch R = 1,271,0,0,0
BEGIN DESCRIPTION:
UNT 055 IN LACR 1.0
END DESCRIPTION:
XS GIS Cut Line= 3
      2252276.71     13205313.48      2251742.80     13204501.59
      2250697.10     13203654.44
#Sta/Elev= 30
  3828.7  247.83  3854.4  244.91  3860.6  238.80  3869.5  237.34  3875.4  238.35
  3890.5  232.84  3905.6  229.59  3920.4  227.86  3932.7  224.13  3962.8  221.27
  3983.9  221.15  3996.0  218.21  3998.7  217.71  4002.0  218.21  4005.0  219.43
  4020.1  220.79  4050.2  221.68  4149.6  221.71  4273.1  223.50  4303.3  225.06
  4330.3  224.27  4381.6  225.29  4590.7  224.68  4670.8  223.65  4843.4  224.28
  4992.1  221.30  5006.5  222.29  5255.8  224.56  5533.3  225.74  6146.2  228.89
#Mann=4,-1,0
  3828.7     0.1       0  3996.0    0.07       0  4002.0     0.1       0
  5533.3    0.12       0
Bank Sta=3996,4002
Exp/Cntr=0.3,0.1

Chan Stop Cuts=-1