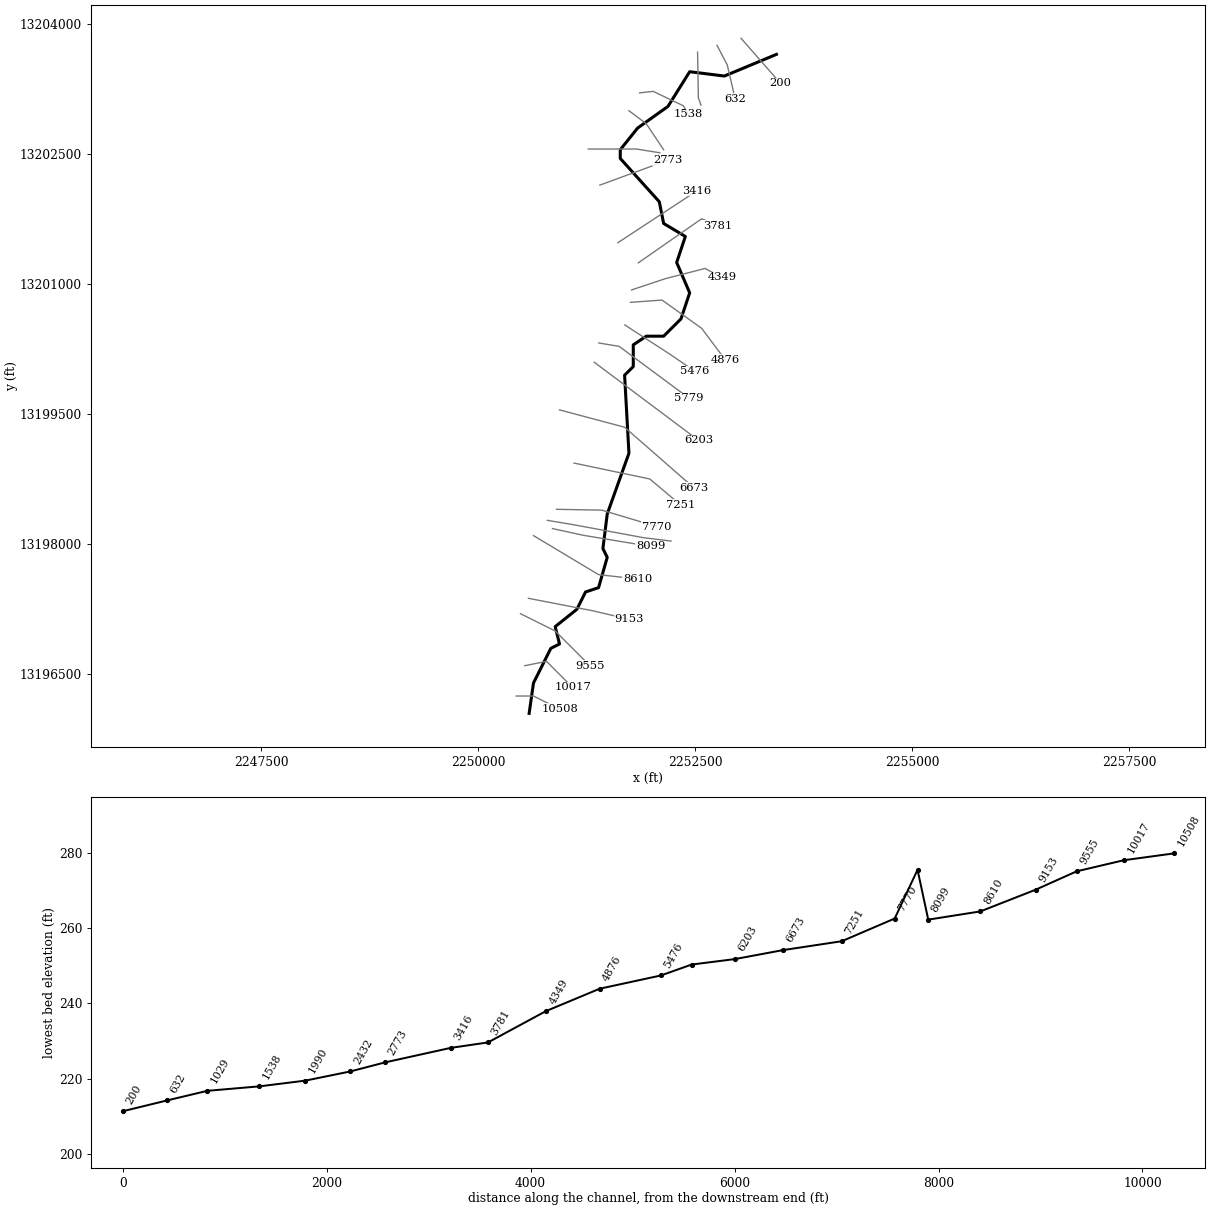
--- UNT 056 IN LACR.prj (project) ---

Proj Title=UNT 056 IN LACR Base Level Engineering
Current Plan=p01
Default Exp/Contr=0.3,0.1
English Units
Geom File=g01
Flow File=f01
Plan File=p01
BEGIN DESCRIPTION:
UNT 056 IN LACR
END DESCRIPTION:

--- UNT 056 IN LACR.p01 (plan) ---

Plan Title=Multiple Run
Short Identifier=Multiple
Geom File=g01
Flow File=f01
Subcritical Flow
K Sum by GR= 0
Std Step Tol= 0.01
Critical Tol= 0.01
Num of Std Step Trials= 20
Max Error Tol= 0.3
Flow Tol Ratio= 0.001
Split Flow NTrial= 30
Split Flow Tol= 0.02
Split Flow Ratio= 0.02
Log Output Level= 0
Friction Slope Method= 1
Unsteady Friction Slope Method= 2
Unsteady Bridges Friction Slope Method= 1
Parabolic Critical Depth
Global Vel Dist=  1 , 1 , 1
Global Log Level= 0
CheckData=True
Encroach Param= -1, 0, 0, 0
BEGIN DESCRIPTION:
Multiple Run
END DESCRIPTION:

--- UNT 056 IN LACR.f01 (steady flow) ---

Flow Title=Multiple
Number of Profiles=7
Profile Names=10-year,25-year,50-year,1pct_min,100-year,1pct_plu,500-year
River Rch & RM= UNT 056 IN LACR,Reach-1,10508
     167     225     272     243     328     444     483
River Rch & RM= UNT 056 IN LACR,Reach-1,9153
     228     314     384     346     468     633     706
River Rch & RM= UNT 056 IN LACR,Reach-1,5476
     285     397     491     446     603     815     923
Boundary for River Rch & Prof#=UNT 056 IN LACR,Reach-1,1
Up Type=0
Dn Type=3
Dn Slope=0.005
Boundary for River Rch & Prof#=UNT 056 IN LACR,Reach-1,2
Up Type=0
Dn Type=3
Dn Slope=0.005
Boundary for River Rch & Prof#=UNT 056 IN LACR,Reach-1,3
Up Type=0
Dn Type=3
Dn Slope=0.005
Boundary for River Rch & Prof#=UNT 056 IN LACR,Reach-1,4
Up Type=0
Dn Type=3
Dn Slope=0.005
Boundary for River Rch & Prof#=UNT 056 IN LACR,Reach-1,5
Up Type=0
Dn Type=3
Dn Slope=0.005
Boundary for River Rch & Prof#=UNT 056 IN LACR,Reach-1,6
Up Type=0
Dn Type=3
Dn Slope=0.005
Boundary for River Rch & Prof#=UNT 056 IN LACR,Reach-1,7
Up Type=0
Dn Type=3
Dn Slope=0.005

--- UNT 056 IN LACR.g01 (geometry) ---

Geom Title=Existing Conditions

River Reach=UNT 056 IN LACR,Reach-1
Reach XY= 30
      2250587.72     13196046.85      2250637.72     13196396.86
      2250837.72     13196796.85      2250937.72     13196846.85
      2250887.72     13197046.85      2251137.72     13197246.86
      2251237.72     13197446.85      2251387.72     13197496.85
      2251487.72     13197846.85      2251437.72     13197946.85
      2251487.72     13198346.85      2251737.72     13199046.86
      2251687.72     13199946.85      2251787.72     13200046.85
      2251787.72     13200296.85      2251937.72     13200396.85
      2252137.72     13200396.85      2252337.72     13200596.85
      2252437.72     13200896.85      2252287.72     13201246.85
      2252387.72     13201546.85      2252137.72     13201696.85
      2252087.72     13201946.85      2251637.72     13202446.85
      2251637.72     13202546.85      2251837.72     13202796.86
      2252187.72     13203046.85      2252437.72     13203446.85
      2252837.72     13203396.85      2253437.72     13203646.86

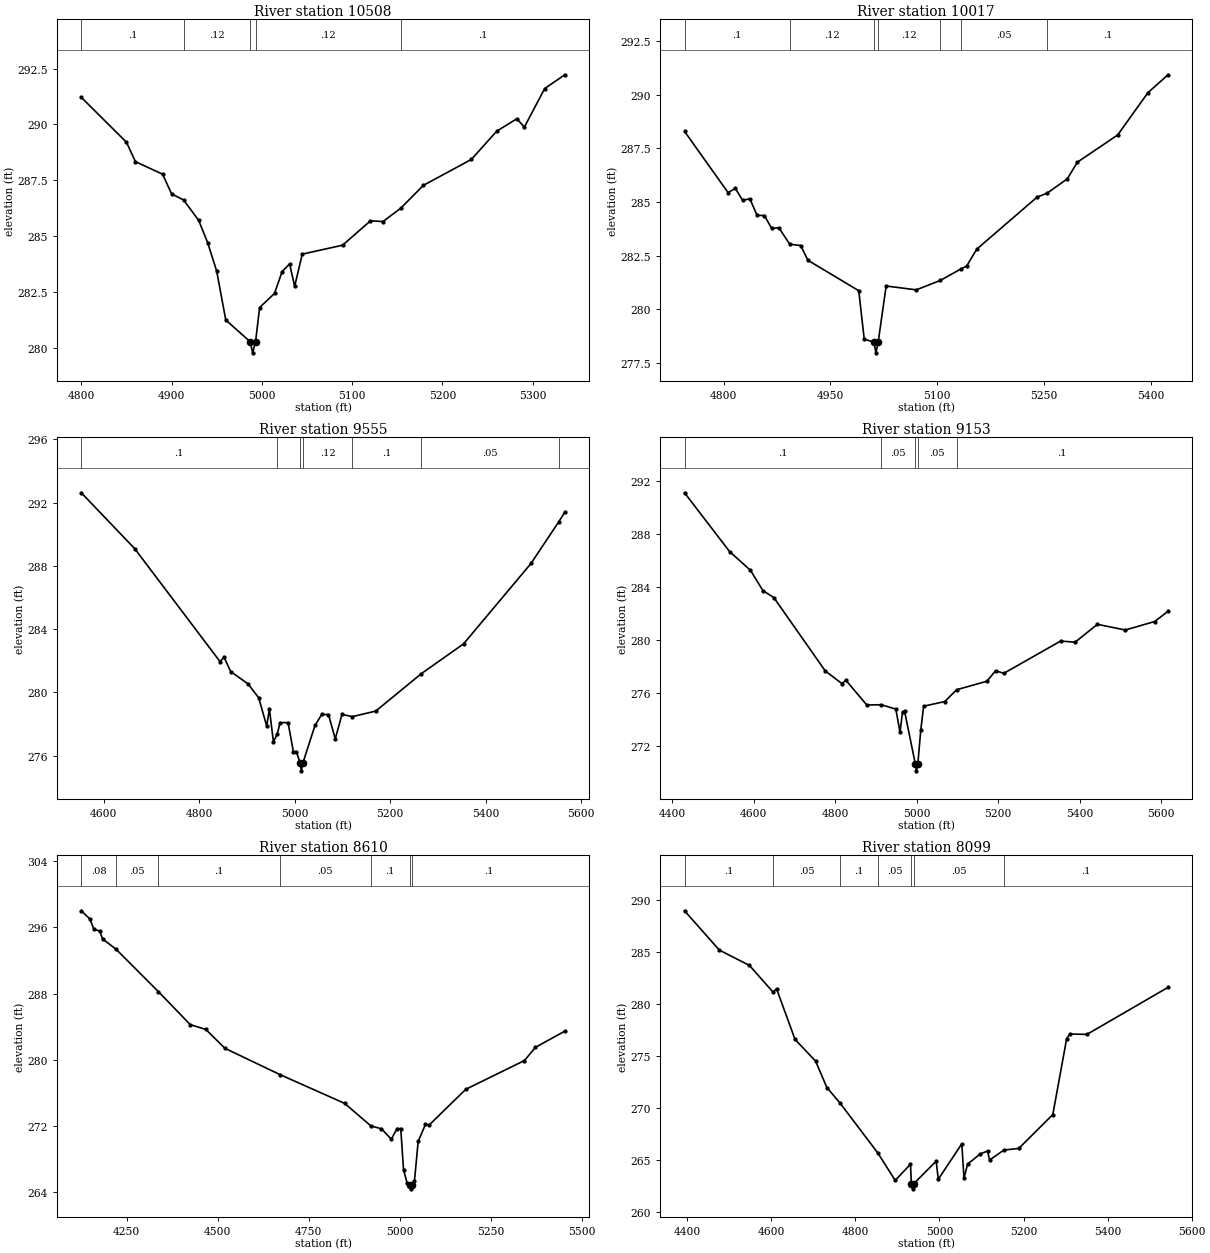
Type RM Length L Ch R = 1,10508,491,491,491
BEGIN DESCRIPTION:
UNT 056 IN LACR 17.0
END DESCRIPTION:
XS GIS Cut Line= 3
      2250437.72     13196246.85      2250637.72     13196246.86
      2250937.71     13196096.86
#Sta/Elev= 30
  4800.0  291.21  4850.0  289.20  4860.0  288.33  4890.0  287.77  4900.0  286.89
  4913.4  286.61  4930.0  285.70  4940.0  284.70  4950.0  283.42  4960.0  281.24
  4987.0  280.27  4989.8  279.77  4993.0  280.27  4997.5  281.80  5014.0  282.43
  5022.4  283.41  5030.7  283.75  5036.3  282.75  5044.7  284.19  5089.4  284.59
  5120.2  285.68  5134.2  285.65  5153.6  286.24  5178.9  287.27  5232.0  288.43
  5259.9  289.69  5282.3  290.25  5290.7  289.88  5313.1  291.60  5335.4  292.22
#Mann=5,-1,0
  4800.0     0.1       0  4913.4    0.12       0  4987.0    0.07       0
  4993.0    0.12       0  5153.6     0.1       0
Bank Sta=4987,4993
Exp/Cntr=0.3,0.1

Type RM Length L Ch R = 1,10017,462,462,462
BEGIN DESCRIPTION:
UNT 056 IN LACR 16.0
END DESCRIPTION:
XS GIS Cut Line= 3
      2250537.67     13196596.85      2250787.72     13196646.85
      2251087.75     13196346.83
#Sta/Elev= 30
  4745.0  288.30  4806.2  285.44  4816.4  285.64  4826.6  285.08  4836.8  285.15
  4847.0  284.38  4857.2  284.37  4867.4  283.77  4877.6  283.80  4892.8  283.03
  4908.2  282.97  4918.4  282.28  4989.8  280.86  4997.5  278.60  5011.1  278.46
  5013.9  277.96  5017.1  278.46  5028.3  281.08  5070.7  280.90  5104.4  281.34
  5133.6  281.88  5141.4  282.01  5155.6  282.80  5240.4  285.23  5254.3  285.41
  5282.8  286.08  5297.0  286.86  5353.6  288.13  5396.0  290.10  5424.3  290.94
#Mann=7,-1,0
  4745.0     0.1       0  4892.8    0.12       0  5011.1    0.07       0
  5017.1    0.12       0  5104.4     0.1       0  5133.6    0.05       0
  5254.3     0.1       0
Bank Sta=5011.1,5017.1
Exp/Cntr=0.3,0.1

Type RM Length L Ch R = 1,9555,402,402,402
BEGIN DESCRIPTION:
UNT 056 IN LACR 15.0
END DESCRIPTION:
XS GIS Cut Line= 3
      2250487.73     13197196.85      2250887.72     13196996.85
      2251287.73     13196596.84
#Sta/Elev= 30
  4552.8  292.62  4664.6  289.09  4843.5  281.94  4851.9  282.22  4865.8  281.31
  4902.2  280.53  4924.5  279.65  4941.3  277.86  4946.9  278.95  4955.3  276.87
  4963.4  277.35  4969.3  278.08  4986.0  278.08  4997.2  276.24  5003.5  276.24
  5011.1  275.53  5013.9  275.03  5017.1  275.53  5042.4  277.90  5056.6  278.60
  5070.7  278.59  5084.9  277.05  5099.0  278.60  5120.7  278.46  5169.7  278.81
  5265.3  281.18  5353.6  283.06  5495.0  288.15  5552.8  290.77  5565.7  291.39
#Mann=7,-1,0
  4552.8     0.1       0  4963.4    0.12       0  5011.1    0.07       0
  5017.1    0.12       0  5120.7     0.1       0  5265.3    0.05       0
  5552.8     0.1       0
Bank Sta=5011.1,5017.1
Exp/Cntr=0.3,0.1

Type RM Length L Ch R = 1,9153,543,543,543
BEGIN DESCRIPTION:
UNT 056 IN LACR 14.0
END DESCRIPTION:
XS GIS Cut Line= 3
      2250578.92     13197373.84      2251321.06     13197229.99
      2251739.57     13197131.90
#Sta/Elev= 30
  4430.8  291.11  4541.4  286.68  4592.6  285.27  4623.1  283.74  4650.0  283.21
  4775.9  277.69  4816.6  276.74  4826.8  276.98  4877.8  275.12  4913.6  275.14
  4949.1  274.81  4959.3  273.07  4965.5  274.59  4970.6  274.64  4997.0  270.66
  4999.7  270.16  5003.0  270.66  5010.2  273.22  5017.3  275.03  5069.0  275.38
  5098.1  276.27  5172.5  276.91  5193.6  277.70  5214.1  277.51  5353.3  279.94
  5388.7  279.85  5443.4  281.20  5512.0  280.77  5583.9  281.41  5616.6  282.18
#Mann=5,-1,0
  4430.8     0.1       0  4913.6    0.05       0  4997.0   0.035       0
  5003.0    0.05       0  5098.1     0.1       0
Bank Sta=4997,5003
Exp/Cntr=0.3,0.1

Type RM Length L Ch R = 1,8610,511,511,511
BEGIN DESCRIPTION:
UNT 056 IN LACR 13.0
END DESCRIPTION:
XS GIS Cut Line= 3
      2250637.76     13198096.83      2251387.72     13197646.85
      2251837.75     13197596.85
#Sta/Elev= 30
  4125.4  298.00  4148.7  297.03  4160.3  295.75  4175.9  295.56  4183.7  294.60
  4220.8  293.36  4337.4  288.22  4424.7  284.24  4467.4  283.66  4519.9  281.38
  4670.6  278.21  4848.4  274.73  4920.0  272.02  4949.5  271.65  4976.7  270.40
  4992.2  271.68  5002.5  271.68  5010.1  266.73  5020.1  265.08  5027.2  264.90
  5029.9  264.40  5033.2  264.90  5040.2  265.38  5050.3  270.13  5070.4  272.19
  5080.5  272.11  5181.1  276.43  5342.1  279.90  5372.3  281.50  5452.8  283.45
#Mann=7,-1,0
  4125.4    0.08       0  4220.8    0.05       0  4337.4     0.1       0
  4670.6    0.05       0  4920.0     0.1       0  5027.2    0.07       0
  5033.2     0.1       0
Bank Sta=5027.2,5033.2
Exp/Cntr=0.3,0.1

Type RM Length L Ch R = 1,8099,105,105,105
BEGIN DESCRIPTION:
UNT 056 IN LACR 12.0
END DESCRIPTION:
XS GIS Cut Line= 3
      2250856.77     13198178.10      2251216.45     13198099.62
      2251988.05     13197972.11
#Sta/Elev= 30
  4393.5  288.94  4476.4  285.16  4548.0  283.69  4604.2  281.12  4612.5  281.44
  4656.4  276.58  4705.4  274.49  4732.2  271.95  4763.6  270.46  4853.8  265.64
  4894.7  263.03  4931.1  264.59  4933.1  262.72  4935.9  262.22  4939.1  262.72
  4992.1  264.88  4997.2  263.14  5053.2  266.55  5058.3  263.24  5067.0  264.60
  5097.4  265.58  5114.3  265.85  5119.3  264.99  5153.6  265.95  5188.6  266.10
  5269.7  269.36  5302.6  276.65  5310.2  277.10  5350.8  277.06  5543.7  281.58
#Mann=7,-1,0
  4393.5     0.1       0  4604.2    0.05       0  4763.6     0.1       0
  4853.8    0.05       0  4933.1   0.033       0  4939.1    0.05       0
  5153.6     0.1       0
Bank Sta=4933.1,4939.1
Exp/Cntr=0.3,0.1

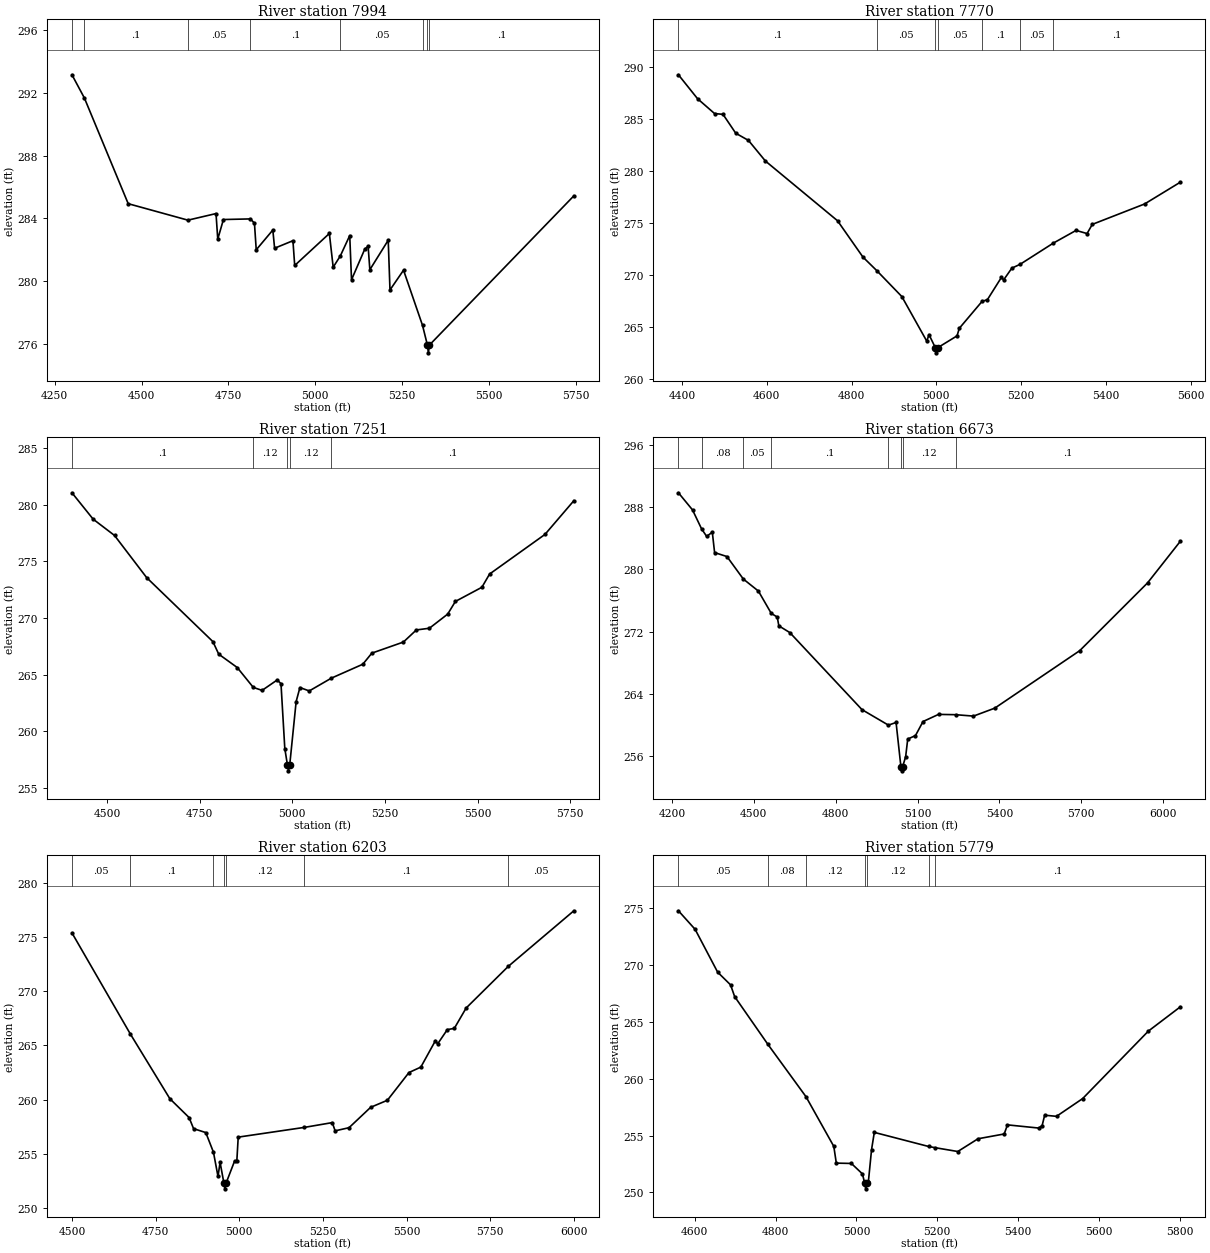
Type RM Length L Ch R = 1,7994,224,224,224
BEGIN DESCRIPTION:
Mapping XS c3ccdf48
END DESCRIPTION:
XS GIS Cut Line= 4
      2250797.93     13198272.90      2251092.21     13198223.86
      2251903.00     13198073.47      2252223.05     13198034.28
#Sta/Elev= 30
  4299.4  293.16  4335.2  291.68  4461.4  284.94  4633.4  283.89  4714.3  284.31
  4719.3  282.68  4735.6  283.93  4813.5  283.97  4825.0  283.69  4830.1  282.00
  4877.9  283.26  4883.0  282.10  4935.8  282.58  4940.9  281.00  5040.7  283.04
  5051.7  280.89  5072.3  281.61  5099.4  282.91  5104.5  280.09  5142.4  282.03
  5152.3  282.23  5157.3  280.73  5210.2  282.61  5215.3  279.44  5254.3  280.70
  5309.0  277.18  5323.0  275.93  5325.8  275.43  5329.0  275.93  5744.8  285.44
#Mann=8,-1,0
  4299.4    0.08       0  4335.2     0.1       0  4633.4    0.05       0
  4813.5     0.1       0  5072.3    0.05       0  5309.0     0.1       0
  5323.0    0.07       0  5329.0     0.1       0
Bank Sta=5323,5329
Exp/Cntr=0.3,0.1

Type RM Length L Ch R = 1,7770,519,519,519
BEGIN DESCRIPTION:
UNT 056 IN LACR 11.0
END DESCRIPTION:
XS GIS Cut Line= 3
      2250902.56     13198400.40      2251425.68     13198390.59
      2252058.40     13198201.43
#Sta/Elev= 30
  4391.8  289.21  4437.0  286.91  4477.0  285.49  4497.0  285.41  4527.0  283.60
  4557.0  282.91  4597.0  280.93  4767.0  275.20  4827.0  271.71  4859.6  270.41
  4918.7  267.92  4977.5  263.64  4982.7  264.27  4997.6  263.02  5000.4  262.52
  5003.6  263.02  5048.9  264.15  5054.1  264.87  5107.9  267.46  5120.4  267.62
  5153.5  269.76  5158.7  269.52  5178.1  270.65  5197.7  271.02  5275.8  273.05
  5329.5  274.27  5355.5  273.97  5367.8  274.85  5491.2  276.81  5575.4  278.90
#Mann=7,-1,0
  4391.8     0.1       0  4859.6    0.05       0  4997.6    0.03       0
  5003.6    0.05       0  5107.9     0.1       0  5197.7    0.05       0
  5275.8     0.1       0
Bank Sta=4997.6,5003.6
Exp/Cntr=0.3,0.1

Type RM Length L Ch R = 1,7251,578,578,578
BEGIN DESCRIPTION:
UNT 056 IN LACR 10.0
END DESCRIPTION:
XS GIS Cut Line= 3
      2251105.29     13198933.29      2251978.19     13198750.21
      2252332.17     13198451.44
#Sta/Elev= 30
  4404.9  281.07  4462.1  278.74  4519.8  277.30  4606.7  273.57  4785.4  267.92
  4801.2  266.81  4851.1  265.63  4894.6  263.87  4918.3  263.61  4959.1  264.53
  4969.3  264.20  4979.6  258.47  4986.8  257.00  4989.5  256.50  4992.8  257.00
  5010.2  262.62  5020.4  263.86  5045.6  263.56  5105.3  264.69  5190.2  265.92
  5214.6  266.90  5299.8  267.88  5334.8  268.95  5370.0  269.10  5419.4  270.35
  5440.2  271.47  5511.7  272.72  5532.5  273.89  5682.0  277.39  5760.0  280.37
#Mann=5,-1,0
  4404.9     0.1       0  4894.6    0.12       0  4986.8    0.07       0
  4992.8    0.12       0  5105.3     0.1       0
Bank Sta=4986.8,4992.8
Exp/Cntr=0.3,0.1

Type RM Length L Ch R = 1,6673,470,470,470
BEGIN DESCRIPTION:
UNT 056 IN LACR 9.0
END DESCRIPTION:
XS GIS Cut Line= 3
      2250937.73     13199546.85      2251687.72     13199346.85
      2252487.71     13198646.86
#Sta/Elev= 30
  4223.8  289.85  4275.5  287.65  4308.6  285.22  4327.3  284.25  4348.0  284.79
  4356.4  282.17  4401.7  281.66  4461.7  278.77  4516.8  277.23  4564.1  274.36
  4586.0  273.89  4591.8  272.76  4631.9  271.90  4896.5  262.00  4993.3  260.01
  5021.4  260.35  5039.2  254.64  5042.0  254.14  5045.2  254.64  5056.5  255.96
  5064.1  258.22  5092.5  258.67  5120.1  260.47  5177.0  261.39  5239.9  261.35
  5305.1  261.17  5383.0  262.19  5694.3  269.57  5943.0  278.28  6063.0  283.62
#Mann=8,-1,0
  4223.8     0.1       0  4308.6    0.08       0  4461.7    0.05       0
  4564.1     0.1       0  4993.3    0.12       0  5039.2    0.07       0
  5045.2    0.12       0  5239.9     0.1       0
Bank Sta=5039.2,5045.2
Exp/Cntr=0.3,0.1

Type RM Length L Ch R = 1,6203,424,424,424
BEGIN DESCRIPTION:
UNT 056 IN LACR 8.0
END DESCRIPTION:
XS GIS Cut Line= 3
      2251337.72     13200096.85      2251737.72     13199796.85
      2252537.72     13199196.85
#Sta/Elev= 30
  4500.0  275.38  4674.2  266.07  4792.7  260.08  4850.0  258.35  4863.5  257.32
  4900.0  256.96  4922.9  255.15  4936.5  252.91  4942.7  254.22  4954.3  252.27
  4957.0  251.77  4960.3  252.27  4986.5  254.37  4992.7  254.30  4996.9  256.54
  5195.0  257.44  5278.1  257.88  5286.5  257.12  5328.1  257.41  5392.7  259.29
  5442.7  259.94  5507.3  262.50  5542.7  263.00  5586.5  265.45  5592.7  265.13
  5621.9  266.46  5642.7  266.57  5678.1  268.45  5804.3  272.30  6000.0  277.42
#Mann=7,-1,0
  4500.0    0.05       0  4674.2     0.1       0  4922.9    0.12       0
  4954.3    0.07       0  4960.3    0.12       0  5195.0     0.1       0
  5804.3    0.05       0
Bank Sta=4954.3,4960.3
Exp/Cntr=0.3,0.1

Type RM Length L Ch R = 1,5779,303,303,303
BEGIN DESCRIPTION:
UNT 056 IN LACR 7.0
END DESCRIPTION:
XS GIS Cut Line= 3
      2251390.48     13200318.38      2251624.89     13200279.32
      2252431.16     13199681.11
#Sta/Elev= 30
  4559.6  274.75  4600.9  273.12  4656.6  269.36  4688.6  268.24  4698.7  267.21
  4781.0  263.01  4875.1  258.42  4944.0  254.05  4950.2  252.58  4987.5  252.55
  5014.9  251.63  5020.3  250.82  5023.1  250.32  5026.3  250.82  5029.5  250.93
  5037.4  253.77  5044.2  255.28  5178.7  254.04  5193.9  253.94  5250.7  253.60
  5300.8  254.72  5365.5  255.14  5373.6  255.94  5451.0  255.66  5459.4  255.88
  5465.6  256.79  5494.9  256.69  5559.6  258.25  5722.2  264.18  5801.2  266.31
#Mann=7,-1,0
  4559.6    0.05       0  4781.0    0.08       0  4875.1    0.12       0
  5020.3    0.07       0  5026.3    0.12       0  5178.7    0.05       0
  5193.9     0.1       0
Bank Sta=5020.3,5026.3
Exp/Cntr=0.3,0.1

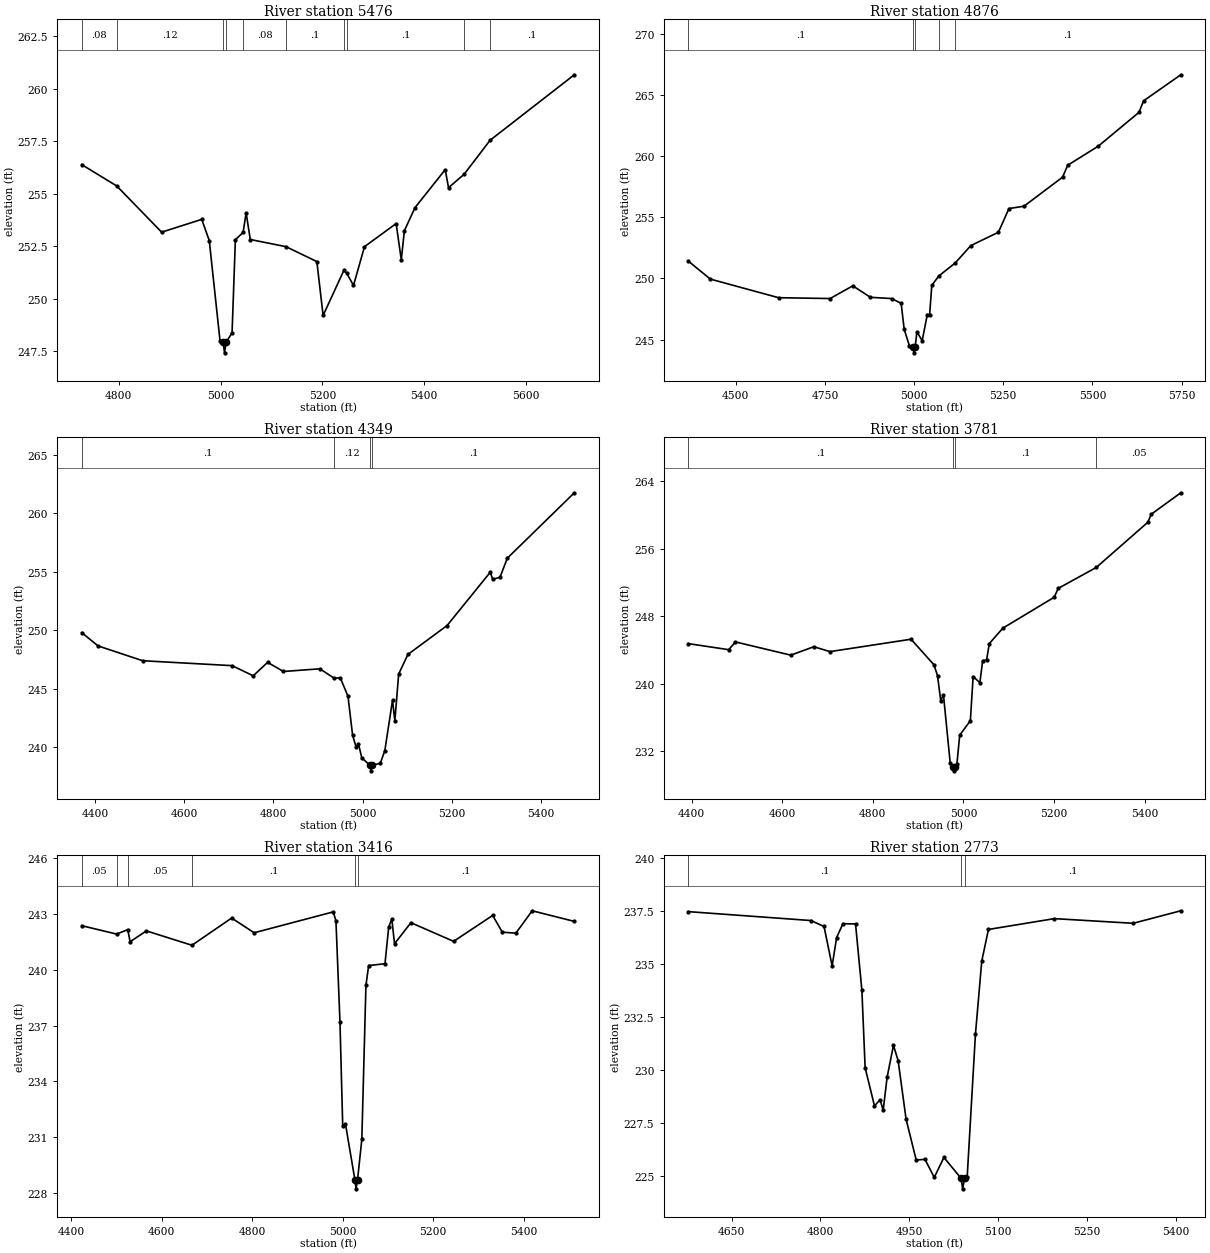
Type RM Length L Ch R = 1,5476,600,600,600
BEGIN DESCRIPTION:
Mapping XS d8a2fbad
END DESCRIPTION:
XS GIS Cut Line= 3
      2251690.02     13200526.69      2252210.83     13200188.17
      2252497.31     13199992.84
#Sta/Elev= 30
  4727.1  256.39  4796.0  255.37  4884.1  253.17  4962.9  253.78  4977.7  252.77
  4998.8  248.00  5004.9  247.92  5007.7  247.42  5010.9  247.92  5022.5  248.38
  5029.0  252.81  5044.2  253.16  5050.1  254.09  5058.3  252.82  5128.3  252.48
  5189.1  251.77  5201.4  249.20  5242.2  251.35  5247.7  251.22  5261.1  250.63
  5282.7  252.48  5344.9  253.58  5355.0  251.85  5361.1  253.24  5382.0  254.34
  5441.3  256.15  5447.8  255.29  5478.5  255.93  5529.5  257.55  5695.0  260.67
#Mann=10,-1,0
  4727.1    0.08       0  4796.0    0.12       0  5004.9    0.07       0
  5010.9    0.12       0  5044.2    0.08       0  5128.3     0.1       0
  5242.2    0.05       0  5247.7     0.1       0  5478.5    0.08       0
  5529.5     0.1       0
Bank Sta=5004.9,5010.9
Exp/Cntr=0.3,0.1

Type RM Length L Ch R = 1,4876,527,527,527
BEGIN DESCRIPTION:
UNT 056 IN LACR 6.0
END DESCRIPTION:
XS GIS Cut Line= 4
      2251755.06     13200787.12      2252119.68     13200813.17
      2252575.41     13200487.65      2252848.83     13200123.09
#Sta/Elev= 30
  4366.5  251.42  4428.6  249.94  4619.8  248.42  4764.5  248.35  4828.0  249.39
  4877.6  248.45  4936.6  248.35  4963.6  247.96  4972.2  245.83  4987.0  244.47
  4997.0  244.41  4999.7  243.91  5003.0  244.41  5007.9  245.64  5022.6  244.90
  5036.9  247.03  5043.5  247.02  5049.6  249.43  5069.4  250.20  5115.3  251.26
  5159.0  252.68  5236.4  253.77  5265.9  255.71  5308.1  255.90  5416.4  258.28
  5430.6  259.25  5516.4  260.81  5630.6  263.58  5643.5  264.52  5747.8  266.65
#Mann=5,-1,0
  4366.5     0.1       0  4997.0    0.07       0  5003.0     0.1       0
  5069.4    0.12       0  5115.3     0.1       0
Bank Sta=4997,5003
Exp/Cntr=0.3,0.1

Type RM Length L Ch R = 1,4349,568,568,568
BEGIN DESCRIPTION:
Mapping XS 71f12264
END DESCRIPTION:
XS GIS Cut Line= 4
      2251768.14     13200930.36      2252158.75     13201060.57
      2252614.47     13201177.75      2252809.75     13201073.60
#Sta/Elev= 30
  4370.4  249.80  4406.8  248.66  4507.0  247.39  4707.3  246.97  4754.6  246.10
  4786.8  247.25  4822.3  246.47  4903.8  246.70  4935.8  245.90  4949.7  245.93
  4966.9  244.35  4977.3  241.01  4985.2  240.00  4990.4  240.28  4997.9  239.07
  5015.6  238.47  5018.3  237.97  5021.6  238.47  5039.2  238.60  5049.5  239.71
  5066.7  244.01  5071.9  242.25  5080.5  246.25  5101.2  247.93  5188.9  250.40
  5285.6  254.96  5291.2  254.36  5307.5  254.53  5323.8  256.16  5474.0  261.76
#Mann=4,-1,0
  4370.4     0.1       0  4935.8    0.12       0  5015.6    0.07       0
  5021.6     0.1       0
Bank Sta=5015.6,5021.6
Exp/Cntr=0.3,0.1

Type RM Length L Ch R = 1,3781,365,365,365
BEGIN DESCRIPTION:
UNT 056 IN LACR 5.0
END DESCRIPTION:
XS GIS Cut Line= 3
      2251846.28     13201242.88      2252575.41     13201750.67
      2252757.74     13201672.53
#Sta/Elev= 30
  4392.7  244.77  4482.1  244.05  4497.0  244.97  4619.1  243.40  4669.8  244.40
  4705.5  243.82  4884.4  245.29  4935.0  242.26  4942.8  240.97  4949.9  238.01
  4956.0  238.66  4970.8  230.62  4976.4  230.18  4979.1  229.68  4982.4  230.18
  4985.7  230.54  4991.8  233.91  5015.3  235.63  5021.4  240.86  5036.3  240.14
  5042.4  242.75  5051.1  242.83  5057.2  244.78  5086.9  246.60  5200.3  250.27
  5209.1  251.32  5293.1  253.80  5407.0  259.17  5414.3  260.11  5479.6  262.66
#Mann=4,-1,0
  4392.7     0.1       0  4976.4    0.07       0  4982.4     0.1       0
  5293.1    0.05       0
Bank Sta=4976.4,4982.4
Exp/Cntr=0.3,0.1

Type RM Length L Ch R = 1,3416,643,643,643
BEGIN DESCRIPTION:
Mapping XS 31c89d75
END DESCRIPTION:
XS GIS Cut Line= 2
      2251610.73     13201474.90      2252520.65     13202072.85
#Sta/Elev= 30
  4423.1  242.36  4500.2  241.91  4524.8  242.15  4530.0  241.50  4566.1  242.08
  4666.7  241.31  4754.5  242.77  4804.2  241.98  4979.0  243.10  4985.0  242.62
  4993.9  237.19  5000.0  231.59  5006.0  231.73  5026.8  228.74  5029.5  228.24
  5032.8  228.74  5042.2  230.89  5051.3  239.16  5057.3  240.22  5093.4  240.32
  5101.6  242.29  5108.5  242.72  5114.5  241.39  5150.7  242.52  5245.1  241.52
  5331.4  242.91  5352.8  242.01  5382.7  241.96  5418.8  243.16  5511.9  242.59
#Mann=6,-1,0
  4423.1    0.05       0  4500.2     0.1       0  4524.8    0.05       0
  4666.7     0.1       0  5026.8    0.07       0  5032.8     0.1       0
Bank Sta=5026.8,5032.8
Exp/Cntr=0.3,0.1

Type RM Length L Ch R = 1,2773,341,341,341
BEGIN DESCRIPTION:
Mapping XS cc0e8f80
END DESCRIPTION:
XS GIS Cut Line= 2
      2251402.44     13202138.98      2252183.21     13202425.26
#Sta/Elev= 30
  4576.7  237.47  4783.9  237.05  4806.0  236.77  4819.7  234.91  4827.3  236.25
  4837.9  236.90  4859.2  236.89  4869.9  233.77  4875.4  230.11  4891.2  228.31
  4900.6  228.60  4905.9  228.11  4912.5  229.66  4923.2  231.16  4931.1  230.45
  4944.5  227.69  4961.6  225.76  4976.4  225.79  4992.1  224.94  5008.4  225.88
  5037.3  224.90  5040.1  224.40  5043.3  224.90  5047.7  224.96  5061.6  231.68
  5072.3  235.14  5083.6  236.63  5194.9  237.14  5327.9  236.92  5408.3  237.51
#Mann=3,-1,0
  4576.7     0.1       0  5037.3    0.07       0  5043.3     0.1       0
Bank Sta=5037.3,5043.3
Exp/Cntr=0.3,0.1

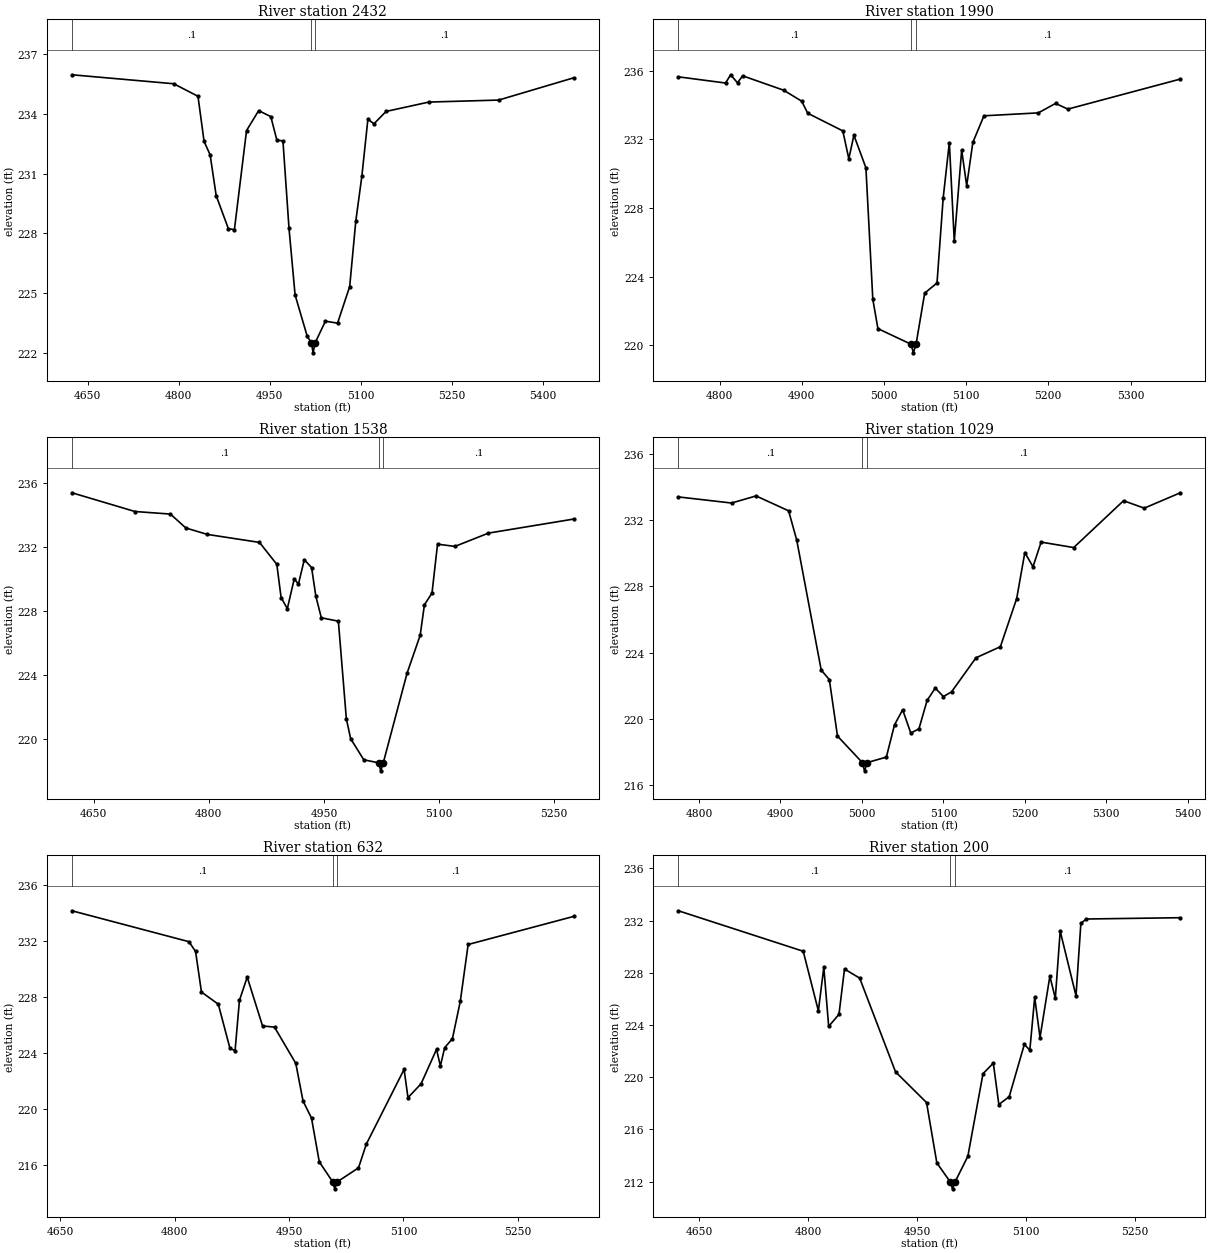
Type RM Length L Ch R = 1,2432,442,442,442
BEGIN DESCRIPTION:
Mapping XS a0fab34a
END DESCRIPTION:
XS GIS Cut Line= 3
      2251270.02     13202555.26      2251823.44     13202555.26
      2252093.69     13202512.02
#Sta/Elev= 30
  4623.9  235.96  4791.6  235.51  4831.6  234.88  4841.6  232.62  4851.6  231.94
  4861.6  229.89  4881.6  228.24  4891.6  228.18  4911.6  233.16  4931.6  234.16
  4951.6  233.86  4961.6  232.68  4971.6  232.64  4981.6  228.25  4991.6  224.91
  5011.6  222.83  5018.6  222.50  5021.3  222.00  5024.6  222.50  5041.6  223.59
  5061.6  223.49  5081.6  225.33  5091.6  228.60  5101.6  230.86  5111.6  233.73
  5121.6  233.50  5141.6  234.12  5212.0  234.59  5327.0  234.69  5451.0  235.81
#Mann=3,-1,0
  4623.9     0.1       0  5018.6    0.07       0  5024.6     0.1       0
Bank Sta=5018.6,5024.6
Exp/Cntr=0.3,0.1

Type RM Length L Ch R = 1,1990,452,452,452
BEGIN DESCRIPTION:
UNT 056 IN LACR 4.0
END DESCRIPTION:
XS GIS Cut Line= 3
      2251737.72     13202996.85      2251937.72     13202846.85
      2252137.75     13202546.82
#Sta/Elev= 30
  4750.0  235.64  4807.3  235.28  4813.5  235.76  4821.9  235.29  4828.1  235.70
  4878.1  234.86  4900.0  234.22  4907.3  233.52  4950.0  232.49  4957.3  230.87
  4963.5  232.24  4978.1  230.34  4986.5  222.68  4992.7  220.97  5033.1  220.06
  5035.8  219.56  5039.1  220.06  5049.6  223.04  5064.6  223.63  5072.1  228.58
  5079.6  231.81  5085.6  226.07  5094.6  231.37  5100.7  229.30  5108.2  231.82
  5121.7  233.37  5187.8  233.54  5208.8  234.09  5223.8  233.76  5360.6  235.51
#Mann=3,-1,0
  4750.0     0.1       0  5033.1    0.07       0  5039.1     0.1       0
Bank Sta=5033.1,5039.1
Exp/Cntr=0.3,0.1

Type RM Length L Ch R = 1,1538,509,509,509
BEGIN DESCRIPTION:
UNT 056 IN LACR 3.0
END DESCRIPTION:
XS GIS Cut Line= 4
      2251860.27     13203202.68      2252016.77     13203220.46
      2252365.31     13203053.30      2252418.65     13202957.29
#Sta/Elev= 30
  4621.7  235.41  4703.8  234.24  4750.0  234.08  4770.1  233.21  4798.0  232.81
  4866.0  232.31  4888.6  230.94  4894.2  228.86  4902.3  228.17  4911.3  230.03
  4916.8  229.71  4924.4  231.23  4933.9  230.74  4939.5  228.94  4946.6  227.60
  4968.8  227.39  4979.2  221.29  4984.8  220.05  5001.9  218.73  5021.3  218.54
  5024.0  218.04  5027.3  218.54  5058.3  224.14  5075.4  226.51  5080.9  228.41
  5090.8  229.15  5098.0  232.20  5120.7  232.06  5164.3  232.89  5275.6  233.77
#Mann=3,-1,0
  4621.7     0.1       0  5021.3    0.07       0  5027.3     0.1       0
Bank Sta=5021.3,5027.3
Exp/Cntr=0.3,0.1

Type RM Length L Ch R = 1,1029,397,397,397
BEGIN DESCRIPTION:
UNT 056 IN LACR 2.0
END DESCRIPTION:
XS GIS Cut Line= 3
      2252528.91     13203672.12      2252537.72     13203146.85
      2252567.79     13203061.12
#Sta/Elev= 30
  4774.7  233.41  4840.0  233.04  4870.0  233.47  4910.0  232.57  4920.0  230.79
  4950.0  222.95  4960.0  222.37  4970.0  218.96  5000.5  217.36  5003.2  216.86
  5006.5  217.36  5030.0  217.69  5040.0  219.64  5050.0  220.55  5060.0  219.14
  5070.0  219.40  5080.0  221.11  5090.0  221.86  5100.0  221.35  5110.0  221.63
  5140.0  223.69  5170.0  224.36  5190.0  227.27  5200.0  230.05  5210.0  229.19
  5220.0  230.68  5260.0  230.35  5321.2  233.18  5346.6  232.73  5390.9  233.66
#Mann=3,-1,0
  4774.7     0.1       0  5000.5    0.07       0  5006.5     0.1       0
Bank Sta=5000.5,5006.5
Exp/Cntr=0.3,0.1

Type RM Length L Ch R = 1,632,432,432,432
BEGIN DESCRIPTION:
Mapping XS d4e27974
END DESCRIPTION:
XS GIS Cut Line= 3
      2252752.95     13203750.42      2252870.34     13203526.32
      2252962.73     13203131.88
#Sta/Elev= 30
  4665.4  234.18  4818.8  231.97  4827.5  231.27  4835.2  228.37  4857.3  227.50
  4872.6  224.34  4879.3  224.18  4885.0  227.77  4895.2  229.44  4915.3  225.95
  4931.0  225.86  4958.9  223.27  4968.4  220.58  4979.5  219.36  4989.7  216.23
  5007.3  214.80  5010.0  214.30  5013.3  214.80  5041.1  215.80  5051.4  217.50
  5100.9  222.84  5106.0  220.82  5123.2  221.81  5143.4  224.27  5148.5  223.09
  5154.1  224.39  5164.3  225.04  5174.6  227.71  5184.9  231.77  5323.5  233.78
#Mann=3,-1,0
  4665.4     0.1       0  5007.3    0.07       0  5013.3     0.1       0
Bank Sta=5007.3,5013.3
Exp/Cntr=0.3,0.1

Type RM Length L Ch R = 1,200,0,0,0
BEGIN DESCRIPTION:
UNT 056 IN LACR 1.0
END DESCRIPTION:
XS GIS Cut Line= 2
      2253029.98     13203831.71      2253485.27     13203311.37
#Sta/Elev= 30
  4621.5  232.75  4793.4  229.65  4814.3  225.09  4821.8  228.42  4828.5  223.89
  4842.7  224.82  4850.3  228.29  4871.2  227.59  4920.6  220.41  4963.3  218.06
  4977.5  213.44  4996.3  211.95  4999.1  211.45  5002.3  211.95  5020.2  213.94
  5041.1  220.27  5055.3  221.08  5062.9  217.91  5077.2  218.51  5098.0  222.51
  5105.6  222.08  5112.3  226.12  5119.6  223.04  5133.2  227.74  5140.7  226.04
  5147.4  231.19  5169.2  226.24  5175.9  231.79  5183.5  232.12  5312.9  232.22
#Mann=3,-1,0
  4621.5     0.1       0  4996.3    0.07       0  5002.3     0.1       0
Bank Sta=4996.3,5002.3
Exp/Cntr=0.3,0.1

Chan Stop Cuts=-1