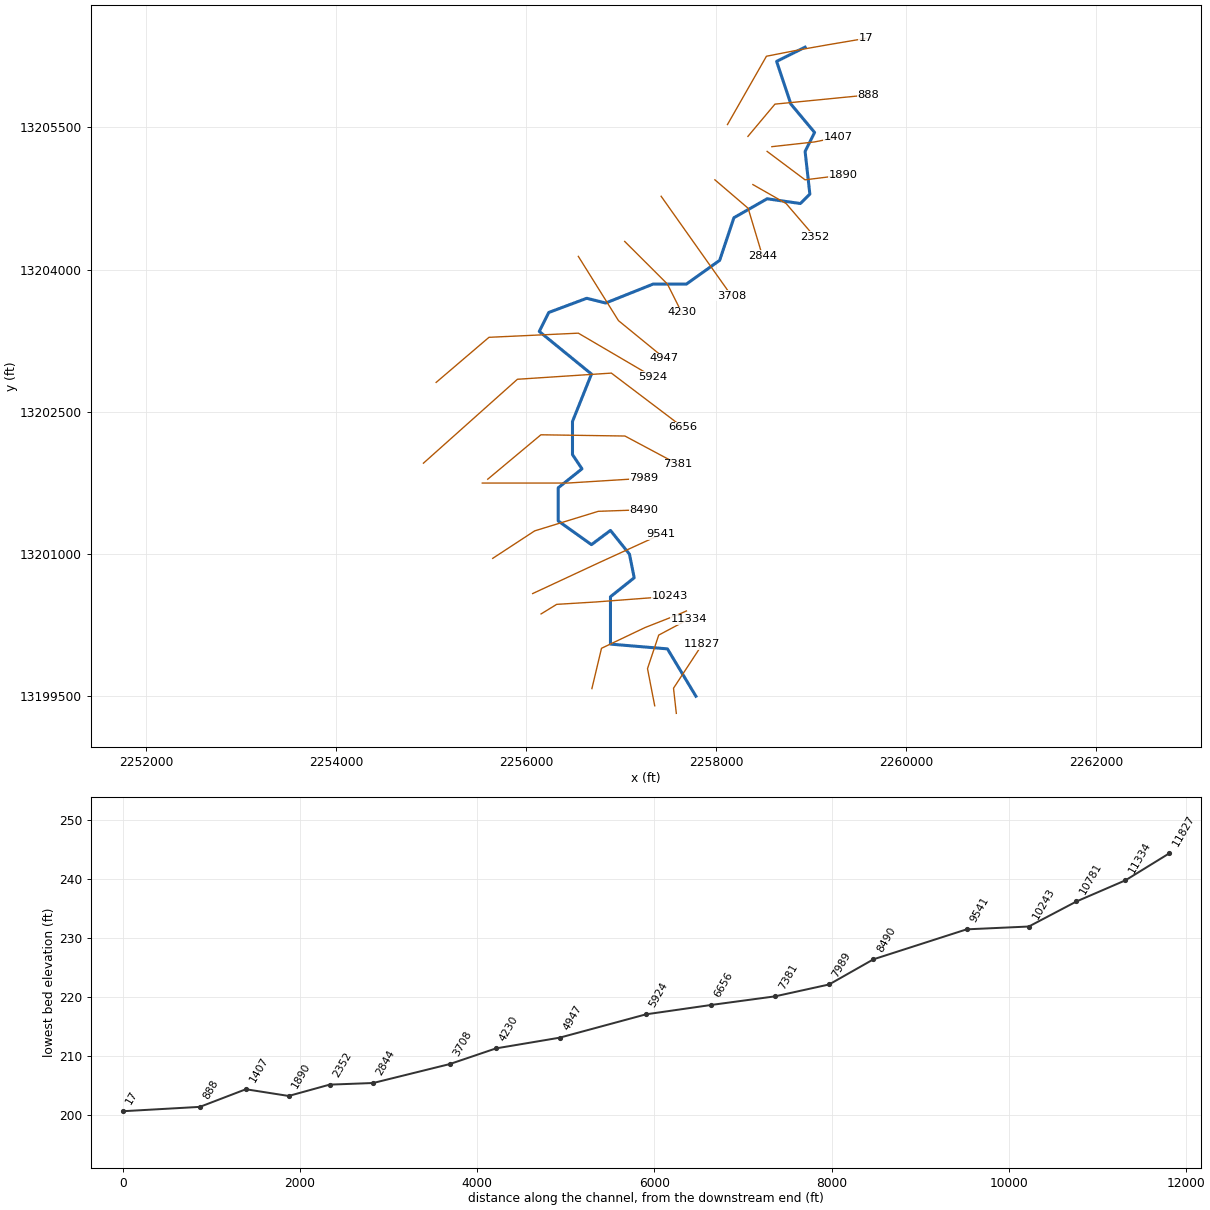
--- UNT 057 IN LACR.prj (project) ---

Proj Title=UNT 057 IN LACR Base Level Engineering
Current Plan=p01
Default Exp/Contr=0.3,0.1
English Units
Geom File=g01
Flow File=f01
Plan File=p01
Y Axis Title=Elevation
X Axis Title(PF)=Main Channel Distance
X Axis Title(XS)=Station
BEGIN DESCRIPTION:
UNT 057 IN LACR
END DESCRIPTION:
DSS Export Rating Curves= 0
DSS Export Rating Curve Sorted= 0
DSS Export Volume Flow Curves= 0
DXF OffsetX= 0
DXF OffsetY= 0
DXF ScaleX= 1
DXF ScaleY= 10

--- UNT 057 IN LACR.p01 (plan) ---

Plan Title=Multiple Run
Short Identifier=Multiple
Geom File=g01
Flow File=f01
Subcritical Flow
K Sum by GR= 0
Std Step Tol= 0.01
Critical Tol= 0.01
Num of Std Step Trials= 20
Max Error Tol= 0.3
Flow Tol Ratio= 0.001
Split Flow NTrial= 30
Split Flow Tol= 0.02
Split Flow Ratio= 0.02
Log Output Level= 0
Friction Slope Method= 1
Unsteady Friction Slope Method= 2
Unsteady Bridges Friction Slope Method= 1
Parabolic Critical Depth
Global Vel Dist=  1 , 1 , 1
Global Log Level= 0
CheckData=True
Encroach Param= -1, 0, 0, 0
BEGIN DESCRIPTION:
Multiple Run
END DESCRIPTION:

--- UNT 057 IN LACR.f01 (steady flow) ---

Flow Title=Multiple
Program Version=4.10
Number of Profiles= 7
Profile Names=10-year,25-year,50-year,1pct_min,100-year,1pct_plu,500-year
River Rch & RM=UNT 057 IN LACR,Reach-1         ,11827
     195     266     323     289     391     529     582
River Rch & RM=UNT 057 IN LACR,Reach-1         ,10243
     367     516     641     585     792    1071    1225
River Rch & RM=UNT 057 IN LACR,Reach-1         ,9541
     367     516     641     585     792    1071    1225
River Rch & RM=UNT 057 IN LACR,Reach-1         ,1890
     386     543     675     616     832    1126    1287
River Rch & RM=UNT 057 IN LACR,Reach-1         ,17
    4301    6462    8401    7970   10779   14577   18006
Boundary for River Rch & Prof#=UNT 057 IN LACR,Reach-1         , 1
Up Type= 0
Dn Type= 3
Dn Slope=0.0014
Boundary for River Rch & Prof#=UNT 057 IN LACR,Reach-1         , 2
Up Type= 0
Dn Type= 3
Dn Slope=0.0014
Boundary for River Rch & Prof#=UNT 057 IN LACR,Reach-1         , 3
Up Type= 0
Dn Type= 3
Dn Slope=0.0014
Boundary for River Rch & Prof#=UNT 057 IN LACR,Reach-1         , 4
Up Type= 0
Dn Type= 3
Dn Slope=0.0014
Boundary for River Rch & Prof#=UNT 057 IN LACR,Reach-1         , 5
Up Type= 0
Dn Type= 3
Dn Slope=0.0014
Boundary for River Rch & Prof#=UNT 057 IN LACR,Reach-1         , 6
Up Type= 0
Dn Type= 3
Dn Slope=0.0014
Boundary for River Rch & Prof#=UNT 057 IN LACR,Reach-1         , 7
Up Type= 0
Dn Type= 3
Dn Slope=0.0014
DSS Import GetInterval= 0
DSS Import GetPeak= 0
DSS Import FillOption= 0

--- UNT 057 IN LACR.g01 (geometry) ---

Geom Title=Existing Conditions
Program Version=4.10

River Reach=UNT 057 IN LACR ,Reach-1
Reach XY= 30
      2257787.72     13199496.85      2257487.72     13199996.85
      2256887.72     13200046.85      2256887.72     13200546.85
      2257137.72     13200746.85      2257087.72     13200996.86
      2256887.72     13201246.85      2256687.72     13201096.85
      2256337.72     13201346.86      2256337.72     13201696.85
      2256587.72     13201896.85      2256487.72     13202046.85
      2256487.72     13202396.85      2256687.72     13202896.85
      2256137.72     13203346.85      2256237.72     13203546.85
      2256637.72     13203696.85      2256837.72     13203646.86
      2257337.72     13203846.85      2257687.72     13203846.85
      2258037.72     13204096.85      2258187.72     13204546.85
      2258537.72     13204746.85      2258887.72     13204696.85
      2258987.72     13204796.86      2258937.72     13205246.85
      2259037.72     13205446.86      2258787.72     13205746.86
      2258637.72     13206196.85      2258937.72     13206346.85

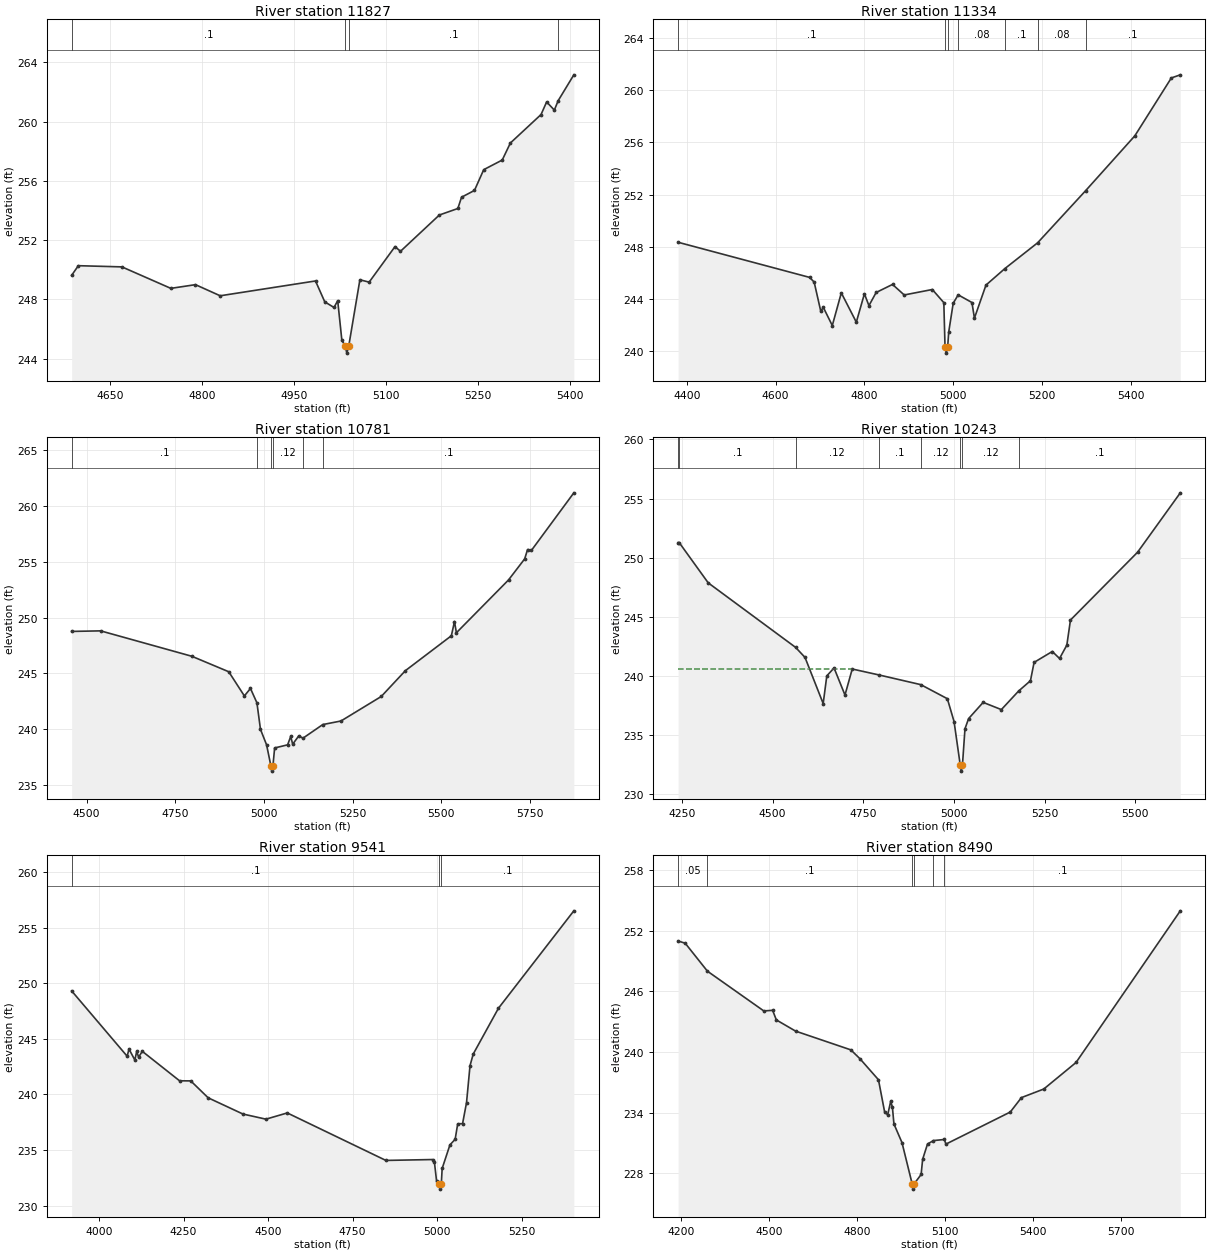
Type RM Length L Ch R = 1 ,11827   ,493,493,493
BEGIN DESCRIPTION:
UNT 057 IN LACR 16.0
END DESCRIPTION:
XS GIS Cut Line= 3
      2257581.29     13199316.05      2257551.79     13199581.56
      2257854.13     13200043.47
#Sta/Elev= 30
  4587.5  249.62  4598.4  250.27  4669.5  250.19  4749.3  248.74  4789.5  248.99
  4829.8  248.24  4985.3  249.24  5000.4  247.83  5015.5  247.45  5021.5  247.91
  5028.3  245.23  5033.6  244.87  5036.4  244.37  5039.6  244.87  5057.7  249.32
  5072.8  249.16    5115  251.56  5123.9  251.24  5187.3  253.69  5217.5  254.13
  5223.5  254.89  5244.6  255.35  5259.7  256.75  5289.9   257.4  5303.2  258.55
  5353.2  260.47  5362.3  261.32  5374.9  260.77  5381.2  261.41  5406.7  263.15
#Mann= 4 ,-1 , 0
  4587.5      .1       0  5033.6     .07       0  5039.6      .1       0
  5381.2     .08       0
Bank Sta=5033.6,5039.6
XS Rating Curve= 0 ,0
Exp/Cntr=0.3,0.1

Type RM Length L Ch R = 1 ,11334   ,553,553,553
BEGIN DESCRIPTION:
UNT 057 IN LACR 15.0
END DESCRIPTION:
XS GIS Cut Line= 4
      2257353.72     13199396.12      2257277.86     13199788.06
      2257395.86     13200142.06      2257711.96     13200310.64
#Sta/Elev= 30
  4380.7  248.33  4676.8  245.63    4687  245.27    4702  243.01  4707.4  243.34
  4727.8  241.93  4748.1  244.44  4781.9  242.19  4800.1  244.37  4810.3  243.46
  4826.5  244.47  4863.4  245.09  4889.7  244.28    4953   244.7  4978.9  243.69
  4981.6  240.31  4984.4  239.81  4987.6  240.31  4989.9  241.43    5000  243.64
  5011.2  244.29  5042.2   243.7  5047.8   242.5  5073.8  245.04  5116.4  246.31
  5190.1  248.29    5298  252.29  5408.9  256.51  5491.1  260.96  5511.3   261.2
#Mann= 7 ,-1 , 0
  4380.7      .1       0  4981.6     .07       0  4987.6      .1       0
  5011.2     .08       0  5116.4      .1       0  5190.1     .08       0
    5298      .1       0
Bank Sta=4981.6,4987.6
XS Rating Curve= 0 ,0
Exp/Cntr=0.3,0.1

Type RM Length L Ch R = 1 ,10781   ,538,538,538
BEGIN DESCRIPTION:
UNT 057 IN LACR 14.0
END DESCRIPTION:
XS GIS Cut Line= 5
      2256692.07     13199577.34      2256793.22     13200002.99
      2257252.57     13200222.13      2257606.57      13200361.2
       2257687.7     13200396.85
#Sta/Elev= 30
  4457.8  248.76  4539.5  248.81  4796.5  246.53  4900.6  245.14  4944.6  242.97
  4961.8  243.64    4980  242.35    4990  239.97  5007.2  238.58  5019.2  236.72
  5021.9  236.22  5025.2  236.72  5029.9   238.3  5066.5  238.58  5075.2  239.33
  5080.8  238.64  5097.9  239.38  5109.9  239.18  5165.6   240.4  5216.9  240.72
  5330.4  242.92  5398.5  245.24    5528  248.37  5536.8  249.65  5542.2  248.64
  5689.1  253.38  5734.6  255.27  5742.8  256.11  5753.6  256.03  5873.2   261.2
#Mann= 6 ,-1 , 0
  4457.8      .1       0    4980     .12       0  5019.2     .07       0
  5025.2     .12       0  5109.9     .05       0  5165.6      .1       0
Bank Sta=5019.2,5025.2
XS Rating Curve= 0 ,0
Exp/Cntr=0.3,0.1

Type RM Length L Ch R = 1 ,10243   ,702,702,702
BEGIN DESCRIPTION:
UNT 057 IN LACR 13.0
END DESCRIPTION:
XS GIS Cut Line= 4
      2256156.86     13200365.42      2256321.22     13200466.56
      2256734.22     13200491.84      2257509.62     13200550.84
#Sta/Elev= 30
  4239.3  251.28  4242.4  251.28  4322.3  247.88  4563.1  242.43  4589.1  241.58
  4639.2  237.68  4649.2  240.02  4669.2  240.69  4699.3   238.4  4719.3   240.6
  4792.8   240.1  4908.2  239.28  4981.5  238.09    5000  236.16  5017.1  232.47
  5019.8  231.97  5023.1  232.47  5030.1  235.55  5040.1  236.41  5080.2  237.78
  5130.4  237.17    5178  238.74  5210.6  239.61  5220.6  241.16  5270.8  242.08
  5290.8  241.49  5310.9  242.62  5320.9  244.74  5505.9  250.47  5623.7  255.49
#Mann= 8 ,-1 , 0
  4239.3     .05       0  4242.4      .1       0  4563.1     .12       0
  4792.8      .1       0  4908.2     .12       0  5017.1     .07       0
  5023.1     .12       0    5178      .1       0
#XS Ineff= 2 , 0
         4719.33  240.62
Permanent Ineff=
       F       F
Bank Sta=5017.1,5023.1
XS Rating Curve= 0 ,0
Exp/Cntr=0.3,0.1

Type RM Length L Ch R = 1 ,9541    ,1051,1051,1051
BEGIN DESCRIPTION:
UNT 057 IN LACR 12.0
END DESCRIPTION:
XS GIS Cut Line= 3
      2256068.34     13200580.33      2256763.72     13200904.84
      2257416.97     13201204.08
#Sta/Elev= 30
  3918.8  249.31    4083  243.44  4088.5  244.08  4105.7   243.1  4111.4  243.88
  4116.9  243.35  4127.8  243.88  4238.1  241.23  4271.2  241.22  4322.7   239.7
  4425.7  238.24  4493.7  237.78  4556.8  238.34  4848.6  234.07  4986.6  234.15
  4992.1  233.93  4998.6  232.21  5006.6  231.99  5009.3  231.49  5012.6  231.99
  5015.1  233.35  5038.1  235.47  5053.5  235.97  5061.1  237.36  5075.5  237.38
  5087.2  239.27  5097.5  242.59  5107.1  243.64  5181.6  247.75  5404.7  256.51
#Mann= 3 ,-1 , 0
  3918.8      .1       0  5006.6     .07       0  5012.6      .1       0
Bank Sta=5006.6,5012.6
XS Rating Curve= 0 ,0
Exp/Cntr=0.3,0.1

Type RM Length L Ch R = 1 ,8490    ,501,501,501
BEGIN DESCRIPTION:
UNT 057 IN LACR 11.0
END DESCRIPTION:
XS GIS Cut Line= 4
      2255647.47     13200951.99      2256089.43     13201241.99
       2256759.5     13201448.49      2257243.43     13201465.32
#Sta/Elev= 30
  4188.9     251  4213.1  250.78  4288.9  248.01  4481.3  244.07  4511.5  244.13
  4524.1  243.18  4589.8  242.07  4778.5  240.21  4809.9  239.32  4872.7  237.25
  4893.6  234.08  4904.1  233.77  4914.5  235.11  4920.3  234.53  4925.5  232.87
    4953  231.02  4987.9  226.91  4990.6  226.41  4993.9  226.91  5018.3  227.86
  5023.5  229.37  5040.1  230.88  5060.4  231.22  5097.6  231.33  5102.9  230.87
  5322.6  234.05  5360.7  235.48  5436.9  236.33    5547  238.96  5902.9  253.99
#Mann= 6 ,-1 , 0
  4188.9     .05       0  4288.9      .1       0  4987.9     .07       0
  4993.9      .1       0  5060.4     .12       0  5097.6      .1       0
Bank Sta=4987.9,4993.9
XS Rating Curve= 0 ,0
Exp/Cntr=0.3,0.1

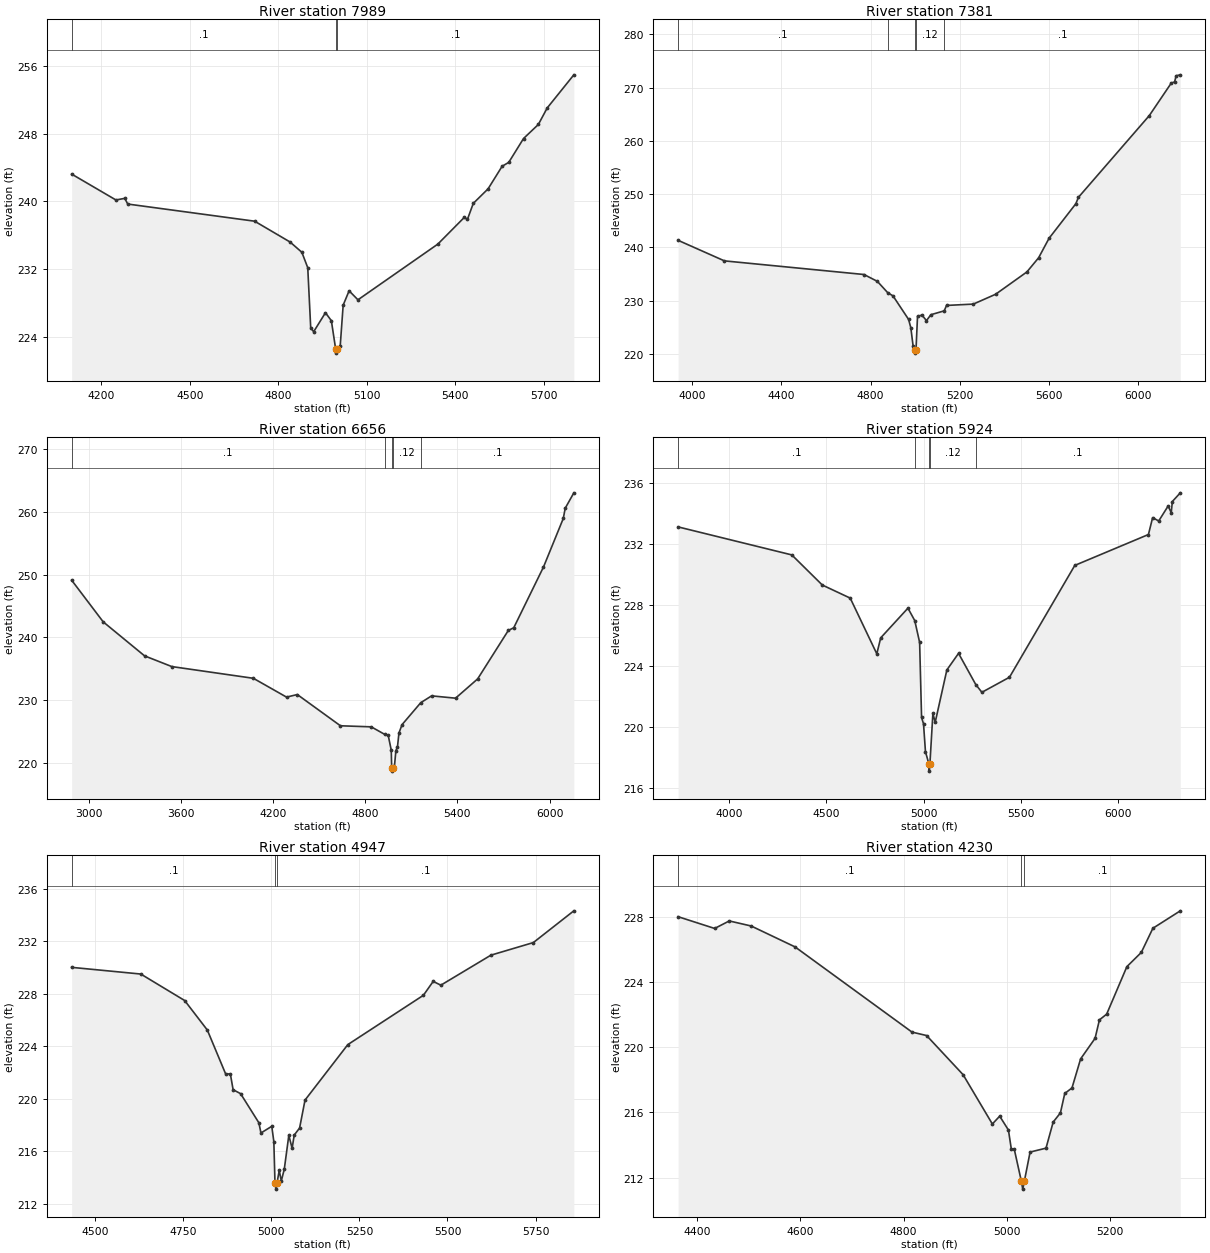
Type RM Length L Ch R = 1 ,7989    ,608,608,608
BEGIN DESCRIPTION:
UNT 057 IN LACR 10.0
END DESCRIPTION:
XS GIS Cut Line= 3
      2255537.72     13201746.85      2256437.72     13201746.85
      2257237.76     13201796.86
#Sta/Elev= 30
    4100  243.23    4250  240.18    4280  240.37    4290   239.7    4720  237.68
    4840  235.23    4880  234.02    4900   232.2    4910  225.13    4920  224.66
    4960   226.9    4980  225.96  4994.5  222.64  4997.2  222.14  5000.5  222.64
    5010  222.99    5020  227.79  5040.1  229.48  5070.1  228.42  5340.7  234.98
  5430.8  238.14  5440.9  237.88  5460.9  239.78    5511  241.49  5558.6  244.15
  5581.1  244.61  5631.2  247.42  5681.3  249.07  5711.4  251.02  5801.6  254.92
#Mann= 3 ,-1 , 0
    4100      .1       0  4994.5     .07       0  5000.5      .1       0
Bank Sta=4994.5,5000.5
XS Rating Curve= 0 ,0
Exp/Cntr=0.3,0.1

Type RM Length L Ch R = 1 ,7381    ,725,725,725
BEGIN DESCRIPTION:
UNT 057 IN LACR 8.0
END DESCRIPTION:
XS GIS Cut Line= 4
      2255595.08     13201787.38      2256155.01     13202256.16
      2257040.43     13202243.13       2257600.3     13201943.67
#Sta/Elev= 30
    3937  241.32  4144.5  237.46    4770   234.9    4830  233.61  4876.9  231.46
    4900  230.89    4970  226.46    4980  224.88    4990  221.52    4997  220.63
  4999.8  220.13    5003  220.63    5010  227.05    5030  227.27    5050  226.24
    5070  227.35  5129.6  228.07    5140  229.09    5260  229.34    5360  231.19
  5500.1  235.38  5552.8  238.05  5599.3  241.69  5719.6   248.2  5731.1   249.4
  6048.7  264.75  6147.1  270.85  6162.1  271.08    6169  272.23  6187.7  272.41
#Mann= 5 ,-1 , 0
    3937      .1       0  4876.9     .12       0    4997     .07       0
    5003     .12       0  5129.6      .1       0
Bank Sta=4997,5003
XS Rating Curve= 0 ,0
Exp/Cntr=0.3,0.1

Type RM Length L Ch R = 1 ,6656    ,732,732,732
BEGIN DESCRIPTION:
UNT 057 IN LACR 7.0
END DESCRIPTION:
XS GIS Cut Line= 4
        2254918.     13201956.65      2255907.61     13202842.09
       2256897.2      13202907.2      2257652.44     13202334.26
#Sta/Elev= 30
  2890.3   249.1  3095.5  242.46  3364.6  237.04  3541.8  235.33  4072.7  233.46
  4288.5  230.46  4358.6  230.87  4639.2  225.89  4839.7  225.72  4927.3  224.52
  4949.9  224.38  4969.9     222  4972.6  219.16  4975.3  218.66  4978.6  219.16
    4990  219.26    5000  221.93    5010  222.46    5020  224.74  5040.1  226.07
  5161.8  229.57  5232.4  230.66  5388.4  230.29  5531.9  233.36  5731.6  241.09
    5767  241.52  5960.4   251.2  6089.2  258.94  6101.9  260.58  6157.9  263.03
#Mann= 5 ,-1 , 0
  2890.3      .1       0  4927.3     .12       0  4972.6     .07       0
  4978.6     .12       0  5161.8      .1       0
Bank Sta=4972.6,4978.6
XS Rating Curve= 0 ,0
Exp/Cntr=0.3,0.1

Type RM Length L Ch R = 1 ,5924    ,977,977,977
BEGIN DESCRIPTION:
Mapping XS 47c3176d
END DESCRIPTION:
XS GIS Cut Line= 4
      2255051.66     13202808.87      2255608.13      13203284.8
      2256549.29     13203328.63       2257333.1     13202868.31
#Sta/Elev= 30
  3737.6  233.13  4322.4  231.29  4479.4  229.31    4623  228.45  4759.7  224.79
  4779.8  225.84  4919.9  227.79    4955  226.97    4980  225.54    4990  220.61
    5000  220.19    5010  218.36    5027  217.58  5029.8  217.08    5033  217.58
  5048.2  220.87  5060.1  220.29  5120.1  223.73  5180.2  224.82  5268.8  222.77
  5300.3  222.26  5442.2  223.25  5778.2   230.6  6157.1  232.63  6178.6  233.74
  6209.9  233.52  6258.7  234.51  6274.3  234.06  6280.1   234.8    6321  235.37
#Mann= 5 ,-1 , 0
  3737.6      .1       0    4955     .12       0    5027     .07       0
    5033     .12       0  5268.8      .1       0
Bank Sta=5027,5033
XS Rating Curve= 0 ,0
Exp/Cntr=0.3,0.1

Type RM Length L Ch R = 1 ,4947    ,717,717,717
BEGIN DESCRIPTION:
Mapping XS 511745aa
END DESCRIPTION:
XS GIS Cut Line= 3
      2256549.28     13204139.12      2256972.15     13203460.78
      2257456.68     13203064.34
#Sta/Elev= 30
  4433.3  230.02  4629.6  229.51  4754.1  227.49  4818.4  225.24  4870.3   221.9
  4883.8  221.89  4891.6  220.69  4912.8  220.39  4964.7  218.17  4970.6  217.39
  5001.3   217.9  5007.2  216.73  5010.4  213.61  5013.1  213.11  5016.4  213.61
  5022.5  214.54  5028.4  213.73  5036.9  214.64  5049.7  217.21  5059.1  216.22
    5065  217.23  5080.3  217.77  5095.7   219.9  5217.2  224.13  5431.7  227.89
  5459.5  228.95  5481.2  228.66  5623.4  230.95  5743.8  231.91  5858.7  234.33
#Mann= 3 ,-1 , 0
  4433.3      .1       0  5010.4     .07       0  5016.4      .1       0
Bank Sta=5010.4,5016.4
XS Rating Curve= 0 ,0
Exp/Cntr=0.3,0.1

Type RM Length L Ch R = 1 ,4230    ,522,522,522
BEGIN DESCRIPTION:
UNT 057 IN LACR 6.0
END DESCRIPTION:
XS GIS Cut Line= 3
      2257037.72     13204296.86      2257487.72     13203846.85
      2257637.72     13203546.86
#Sta/Elev= 30
  4363.6  227.99  4434.3  227.27  4462.6  227.73    4505  227.42  4589.9  226.14
  4816.2  220.92  4844.4  220.71  4915.1  218.31  4971.7  215.29  4985.9  215.77
  5002.8  214.92  5008.4  213.75    5014  213.76  5027.7   211.8  5030.5   211.3
  5033.7   211.8  5044.7  213.57  5075.5  213.81  5089.4  215.41  5103.4  215.97
  5111.8  217.16  5125.8   217.5  5142.5  219.28  5170.5  220.54  5178.9  221.67
  5192.9  222.02    5232  224.93  5259.9   225.8  5282.3  227.28  5335.4  228.35
#Mann= 3 ,-1 , 0
  4363.6      .1       0  5027.7     .07       0  5033.7      .1       0
Bank Sta=5027.7,5033.7
XS Rating Curve= 0 ,0
Exp/Cntr=0.3,0.1

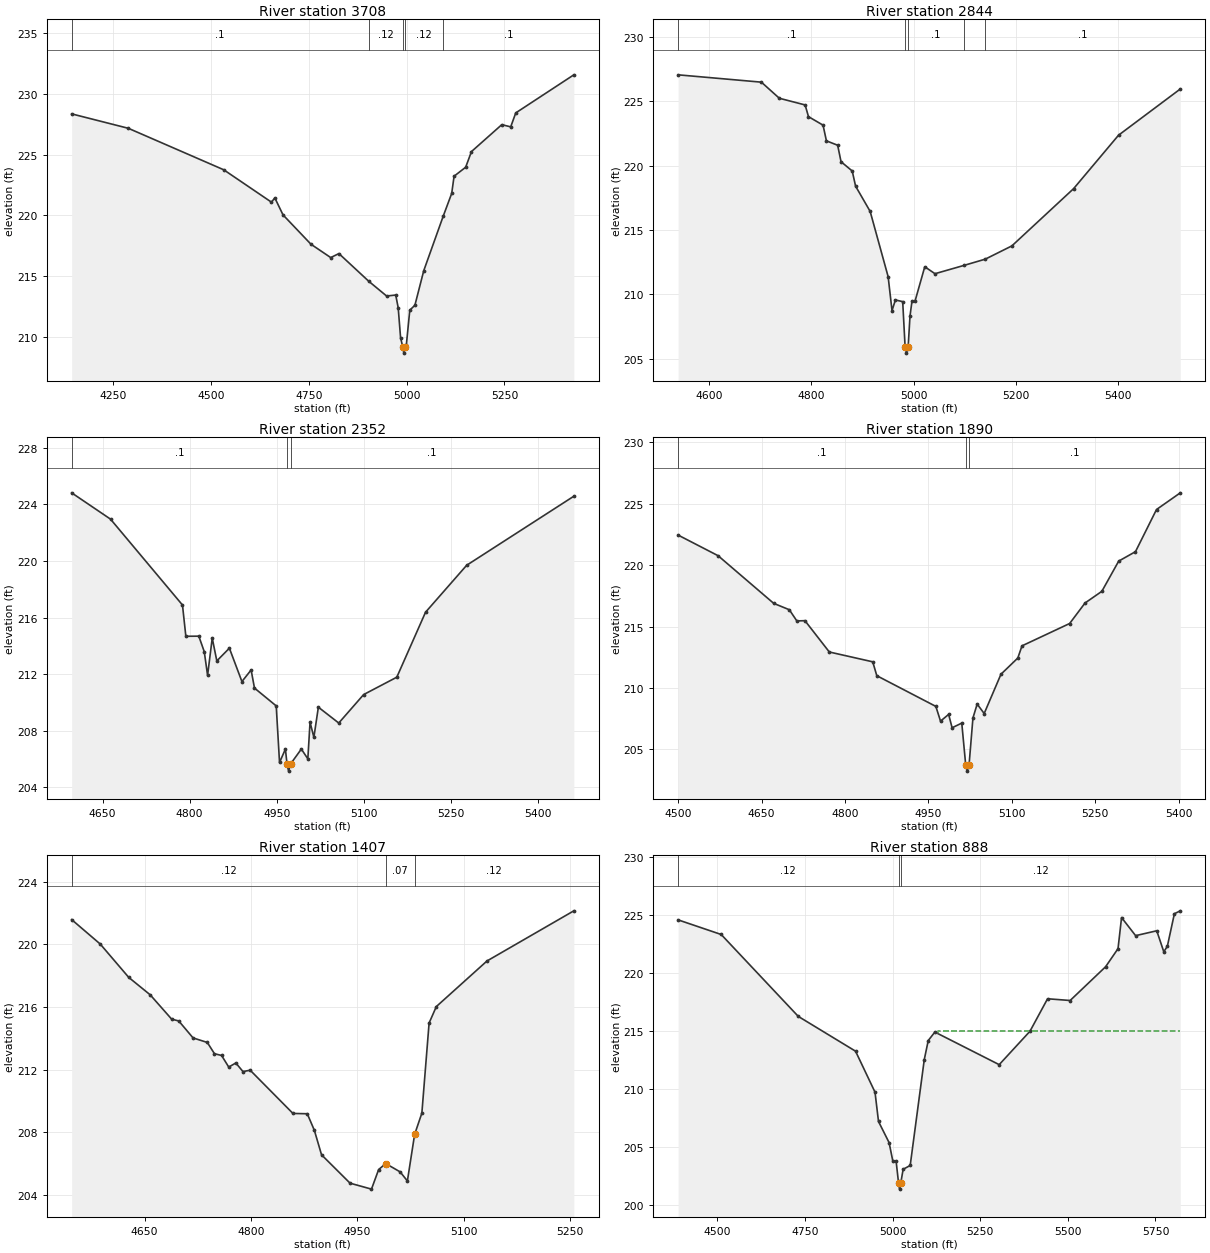
Type RM Length L Ch R = 1 ,3708    ,864,864,864
BEGIN DESCRIPTION:
Mapping XS 14898e24
END DESCRIPTION:
XS GIS Cut Line= 2
      2257421.43     13204773.39      2258161.43     13203725.06
#Sta/Elev= 30
  4144.1  228.37    4289  227.18  4532.7  223.76  4654.6  221.09  4663.3  221.44
  4684.2  220.04  4755.6  217.62  4806.1  216.52    4827  216.85  4903.5  214.56
  4948.9  213.35  4972.2  213.43  4978.5  212.38  4984.6   209.9  4990.3  209.14
    4993  208.64  4996.3  209.14  4999.4  209.34  5008.1  212.18  5021.2  212.59
  5043.8  215.44  5093.6  219.94  5115.2  221.81  5121.3  223.23  5150.9  223.97
  5165.7  225.26  5243.2  227.48    5266   227.3  5278.9  228.45  5427.3  231.59
#Mann= 5 ,-1 , 0
  4144.1      .1       0  4903.5     .12       0  4990.3     .07       0
  4996.3     .12       0  5093.6      .1       0
Bank Sta=4990.3,4996.3
XS Rating Curve= 0 ,0
Exp/Cntr=0.3,0.1

Type RM Length L Ch R = 1 ,2844    ,492,492,492
BEGIN DESCRIPTION:
UNT 057 IN LACR 5.0
END DESCRIPTION:
XS GIS Cut Line= 3
       2257987.7     13204946.87      2258337.72     13204646.85
      2258487.72     13204146.87
#Sta/Elev= 30
    4539  227.05    4702  226.48  4737.1  225.23  4787.6  224.71  4794.2   223.8
  4822.7  223.14  4829.3  221.92  4851.3  221.58  4857.9   220.3  4879.8  219.58
  4886.4   218.4  4914.9  216.44  4950.1  211.37  4957.7  208.73  4964.3  209.56
  4978.6  209.43  4983.3  205.93    4986  205.43  4989.3  205.93  4992.9  208.31
  4996.7  209.45  5002.6  209.45  5021.8  212.14  5041.8   211.6    5099  212.25
  5140.2  212.73  5192.3  213.76  5313.2  218.21  5401.1  222.36    5522  225.95
#Mann= 5 ,-1 , 0
    4539      .1       0  4983.3     .07       0  4989.3      .1       0
    5099     .12       0  5140.2      .1       0
Bank Sta=4983.3,4989.3
XS Rating Curve= 0 ,0
Exp/Cntr=0.3,0.1

Type RM Length L Ch R = 1 ,2352    ,462,462,462
BEGIN DESCRIPTION:
UNT 057 IN LACR 4.0
END DESCRIPTION:
XS GIS Cut Line= 3
      2258387.73     13204896.85      2258737.72     13204696.85
      2259037.74     13204346.84
#Sta/Elev= 30
  4596.9  224.82  4663.8  222.96  4787.6  216.89  4793.4  214.68  4815.7  214.69
  4825.1  213.59  4830.8  211.92  4838.8  214.55  4846.7  212.94  4868.3  213.84
  4889.9  211.48  4905.7   212.3  4911.5  211.02  4948.9  209.76  4954.6  205.76
  4964.7  206.71  4967.5  205.65  4970.2  205.15  4973.5  205.65  4992.1  206.71
  5003.3  206.02  5007.1  208.61  5013.7  207.54  5021.4  209.67  5056.5  208.55
  5099.3  210.56  5156.4  211.79  5205.8  216.38  5276.6   219.7    5461  224.58
#Mann= 3 ,-1 , 0
  4596.9      .1       0  4967.5     .07       0  4973.5      .1       0
Bank Sta=4967.5,4973.5
XS Rating Curve= 0 ,0
Exp/Cntr=0.3,0.1

Type RM Length L Ch R = 1 ,1890    ,483,483,483
BEGIN DESCRIPTION:
UNT 057 IN LACR 3.0
END DESCRIPTION:
XS GIS Cut Line= 3
      2258537.72     13205246.85      2258937.72     13204946.86
      2259337.71     13204996.85
#Sta/Elev= 30
    4500  222.45  4571.9  220.77  4671.9  216.89    4700  216.37  4713.5  215.46
  4728.1  215.48  4771.9  212.93    4850  212.13  4857.3     211  4963.5   208.5
  4971.9   207.3  4986.5  207.85  4992.7  206.76  5010.1  207.14  5017.2  203.73
  5019.9  203.23  5023.2  203.73  5030.2  207.56  5037.8  208.69  5050.4  207.92
  5080.6  211.12  5110.9  212.44  5118.4  213.43  5204.1  215.25  5231.8  216.92
    5262  217.87  5292.3  220.33  5322.5   221.1  5360.3  224.53  5403.1  225.89
#Mann= 3 ,-1 , 0
    4500      .1       0  5017.2     .07       0  5023.2      .1       0
Bank Sta=5017.2,5023.2
XS Rating Curve= 0 ,0
Exp/Cntr=0.3,0.1

Type RM Length L Ch R = 1 ,1407    ,519,519,519
BEGIN DESCRIPTION:
UNT 057 IN LACR 2.0
END DESCRIPTION:
XS GIS Cut Line= 3
      2258587.69     13205296.85      2259037.72     13205346.85
      2259287.77     13205396.86
#Sta/Elev= 30
  4547.2  221.57  4587.5  220.01  4627.7  217.88  4657.9  216.77  4688.1  215.22
  4698.2   215.1  4718.3  214.02  4738.4  213.73  4748.5  213.01  4758.5   212.9
  4768.6  212.16  4778.6  212.42  4788.7  211.87  4798.8  211.96  4859.1   209.2
  4879.3  209.18  4889.3  208.12  4899.4  206.56  4939.6  204.75  4969.8  204.37
  4979.9  205.62  4989.9     206  5010.2  205.47  5020.4  204.89  5030.6  207.86
  5040.8  209.22    5051  214.97  5061.2  216.02  5132.6  218.93    5255  222.13
#Mann= 3 , 0 , 0
  4547.2     .12       0  4989.9     .07       0  5030.6     .12       0
Bank Sta=4989.9,5030.6
XS Rating Curve= 0 ,0
Exp/Cntr=0.3,0.1

Type RM Length L Ch R = 1 ,888     ,871,871,871
BEGIN DESCRIPTION:
Mapping XS e66bb53b
END DESCRIPTION:
XS GIS Cut Line= 3
      2258335.58     13205405.48      2258620.29     13205745.74
      2259604.56     13205842.78
#Sta/Elev= 30
  4388.1  224.59    4511  223.33  4730.9  216.27  4894.3  213.27  4949.8  209.74
  4959.8  207.21    4990  205.39  5000.5  203.82    5010   203.8  5017.1  201.88
  5019.8  201.38  5023.1  201.88  5030.1  203.09  5050.2  203.42  5090.4  212.55
  5101.7  214.19  5120.6  214.92  5304.1  212.11  5391.9  214.99  5442.1  217.79
  5506.5  217.64  5607.7  220.55  5643.1  222.11  5653.2  224.79  5693.3  223.23
  5753.6  223.65  5773.7  221.84  5783.8  222.31  5803.9  225.12  5820.8  225.37
#Mann= 3 ,-1 , 0
  4388.1     .12       0  5017.1     .07       0  5023.1     .12       0
#XS Ineff= 2 , 0
                         5129.66          215.02
Permanent Ineff=
       F       F
Bank Sta=5017.1,5023.1
XS Rating Curve= 0 ,0
Exp/Cntr=0.3,0.1

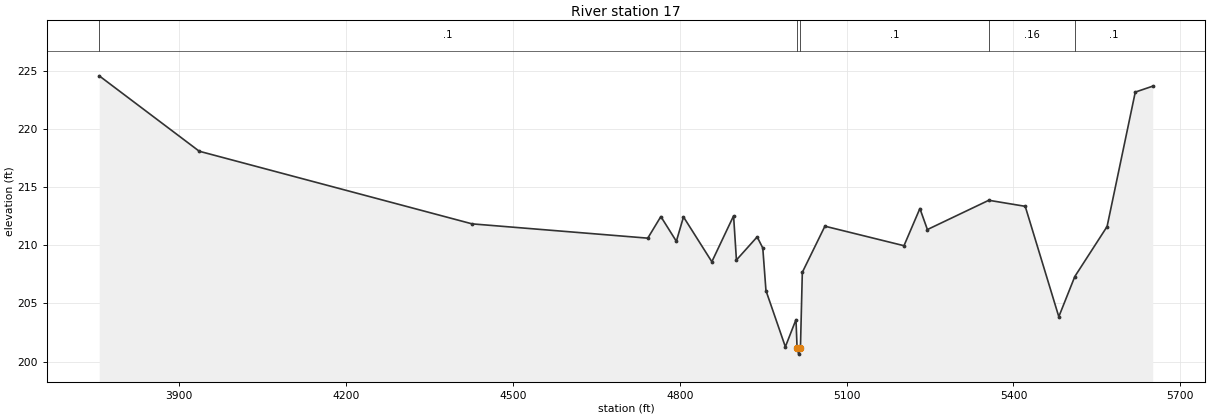
Type RM Length L Ch R = 1 ,17      ,0,0,0
BEGIN DESCRIPTION:
UNT 057 IN LACR 1.0
END DESCRIPTION:
XS GIS Cut Line= 5
      2258120.29     13205530.47       2258530.5     13206251.19
       2258856.4     13206315.18       2259168.9     13206370.74
      2259578.65     13206440.19
#Sta/Elev= 30
    3756  224.59  3935.9   218.1  4426.5  211.85  4742.4  210.62  4765.9  212.48
  4793.8  210.35  4806.6  212.45  4857.6  208.59  4896.7  212.54  4901.8  208.74
  4939.1  210.73  4949.2  209.77  4954.9  206.11  4989.8  201.27  5008.9  203.61
  5010.9  201.14  5013.7  200.64  5016.9  201.14  5020.3  207.68  5060.9  211.65
  5203.1  209.97  5231.7  213.17  5245.2  211.36  5355.6  213.88  5421.1  213.36
  5481.5  203.86  5510.3  207.32  5568.3  211.62    5619  223.19  5650.4   223.7
#Mann= 5 ,-1 , 0
    3756      .1       0  5010.9     .07       0  5016.9      .1       0
  5355.6     .16       0  5510.3      .1       0
Bank Sta=5010.9,5016.9
XS Rating Curve= 0 ,0
Exp/Cntr=0.3,0.1

Chan Stop Cuts=-1
Use User Specified Reach Order=0
Composite Channel Slope=5