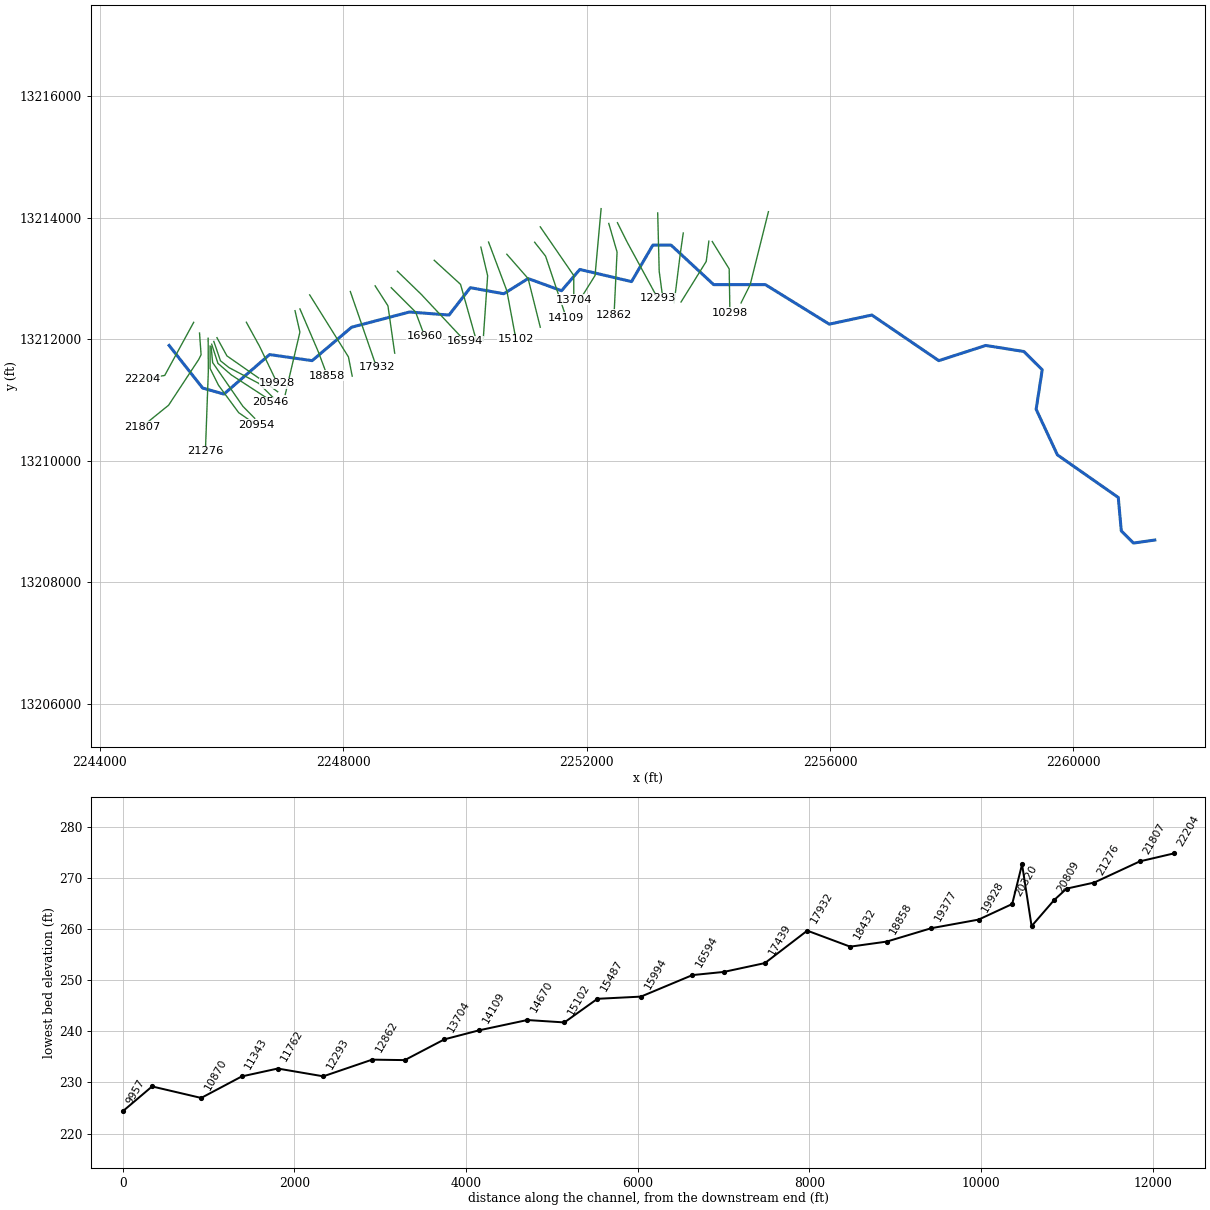
--- UNT 058 IN LACR.prj (project) ---

Proj Title=UNT 058 IN LACR Base Level Engineering
Current Plan=p01
Default Exp/Contr=0.3,0.1
English Units
Geom File=g01
Flow File=f01
Plan File=p01
Y Axis Title=Elevation
X Axis Title(PF)=Main Channel Distance
X Axis Title(XS)=Station
BEGIN DESCRIPTION:
UNT 058 IN LACR
END DESCRIPTION:
DSS Export Rating Curves= 0
DSS Export Rating Curve Sorted= 0
DSS Export Volume Flow Curves= 0
DXF OffsetX= 0
DXF OffsetY= 0
DXF ScaleX= 1
DXF ScaleY= 10

--- UNT 058 IN LACR.p01 (plan) ---

Plan Title=Multiple Run
Short Identifier=Multiple
Geom File=g01
Flow File=f01
Subcritical Flow
K Sum by GR= 0
Std Step Tol= 0.01
Critical Tol= 0.01
Num of Std Step Trials= 20
Max Error Tol= 0.3
Flow Tol Ratio= 0.001
Split Flow NTrial= 30
Split Flow Tol= 0.02
Split Flow Ratio= 0.02
Log Output Level= 0
Friction Slope Method= 1
Unsteady Friction Slope Method= 2
Unsteady Bridges Friction Slope Method= 1
Parabolic Critical Depth
Global Vel Dist=  1 , 1 , 1
Global Log Level= 0
CheckData=True
Encroach Param= -1, 0, 0, 0
BEGIN DESCRIPTION:
Multiple Run
END DESCRIPTION:

--- UNT 058 IN LACR.f01 (steady flow) ---

Flow Title=Multiple
Program Version=4.10
Number of Profiles= 7
Profile Names=10-year,25-year,50-year,1pct_min,100-year,1pct_plu,500-year
River Rch & RM=UNT 058 IN LACR,Reach-1         ,22204
     197     271     331     299     404     547     611
River Rch & RM=UNT 058 IN LACR,Reach-1         ,21276
     316     446     555     509     688     930    1072
River Rch & RM=UNT 058 IN LACR,Reach-1         ,19377
     397     565     708     652     882    1193    1389
River Rch & RM=UNT 058 IN LACR,Reach-1         ,15487
     461     661     831     768    1038    1404    1647
River Rch & RM=UNT 058 IN LACR,Reach-1         ,13242
     636     922    1170    1089    1473    1992    2372
River Rch & RM=UNT 058 IN LACR,Reach-1         ,8103
     646     937    1189    1107    1497    2025    2411
River Rch & RM=UNT 058 IN LACR,Reach-1         ,5829
     764    1115    1422    1329    1797    2430    2917
River Rch & RM=UNT 058 IN LACR,Reach-1         ,5451
     764    1115    1422    1329    1797    2430    2917
River Rch & RM=UNT 058 IN LACR,Reach-1         ,4518
     756    1103    1404    1311    1773    2397    2870
River Rch & RM=UNT 058 IN LACR,Reach-1         ,884
     813    1188    1515    1416    1915    2589    3108
Boundary for River Rch & Prof#=UNT 058 IN LACR,Reach-1         , 1
Up Type= 0
Dn Type= 3
Dn Slope=0.0036
Boundary for River Rch & Prof#=UNT 058 IN LACR,Reach-1         , 2
Up Type= 0
Dn Type= 3
Dn Slope=0.0036
Boundary for River Rch & Prof#=UNT 058 IN LACR,Reach-1         , 3
Up Type= 0
Dn Type= 3
Dn Slope=0.0036
Boundary for River Rch & Prof#=UNT 058 IN LACR,Reach-1         , 4
Up Type= 0
Dn Type= 3
Dn Slope=0.0036
Boundary for River Rch & Prof#=UNT 058 IN LACR,Reach-1         , 5
Up Type= 0
Dn Type= 3
Dn Slope=0.0036
Boundary for River Rch & Prof#=UNT 058 IN LACR,Reach-1         , 6
Up Type= 0
Dn Type= 3
Dn Slope=0.0036
Boundary for River Rch & Prof#=UNT 058 IN LACR,Reach-1         , 7
Up Type= 0
Dn Type= 3
Dn Slope=0.0036
DSS Import GetInterval= 0
DSS Import GetPeak= 0
DSS Import FillOption= 0

--- UNT 058 IN LACR.g01 (geometry) ---

Geom Title=Existing Conditions
Program Version=4.10

River Reach=UNT 058 IN LACR ,Reach-1
Reach XY= 30
      2245137.72     13211896.85      2245687.72     13211196.86
      2246037.72     13211096.85      2246787.72     13211746.85
      2247487.72     13211646.85      2248137.72     13212196.85
      2249087.72     13212446.85      2249737.72     13212396.85
      2250087.72     13212846.85      2250637.72     13212746.85
      2251037.72     13212996.86      2251587.72     13212796.85
      2251887.72     13213146.86      2252737.72     13212946.85
      2253087.72     13213546.85      2253387.72     13213546.85
      2254087.72     13212896.85      2254937.72     13212896.85
      2255987.72     13212246.85      2256687.72     13212396.85
      2257787.72     13211646.85       2258559.5     13211896.85
      2259187.72     13211796.85      2259487.72     13211496.86
      2259387.72     13210846.86      2259737.72     13210096.85
      2260737.72     13209396.86      2260787.72     13208846.85
      2260987.72     13208646.85      2261337.72     13208696.85

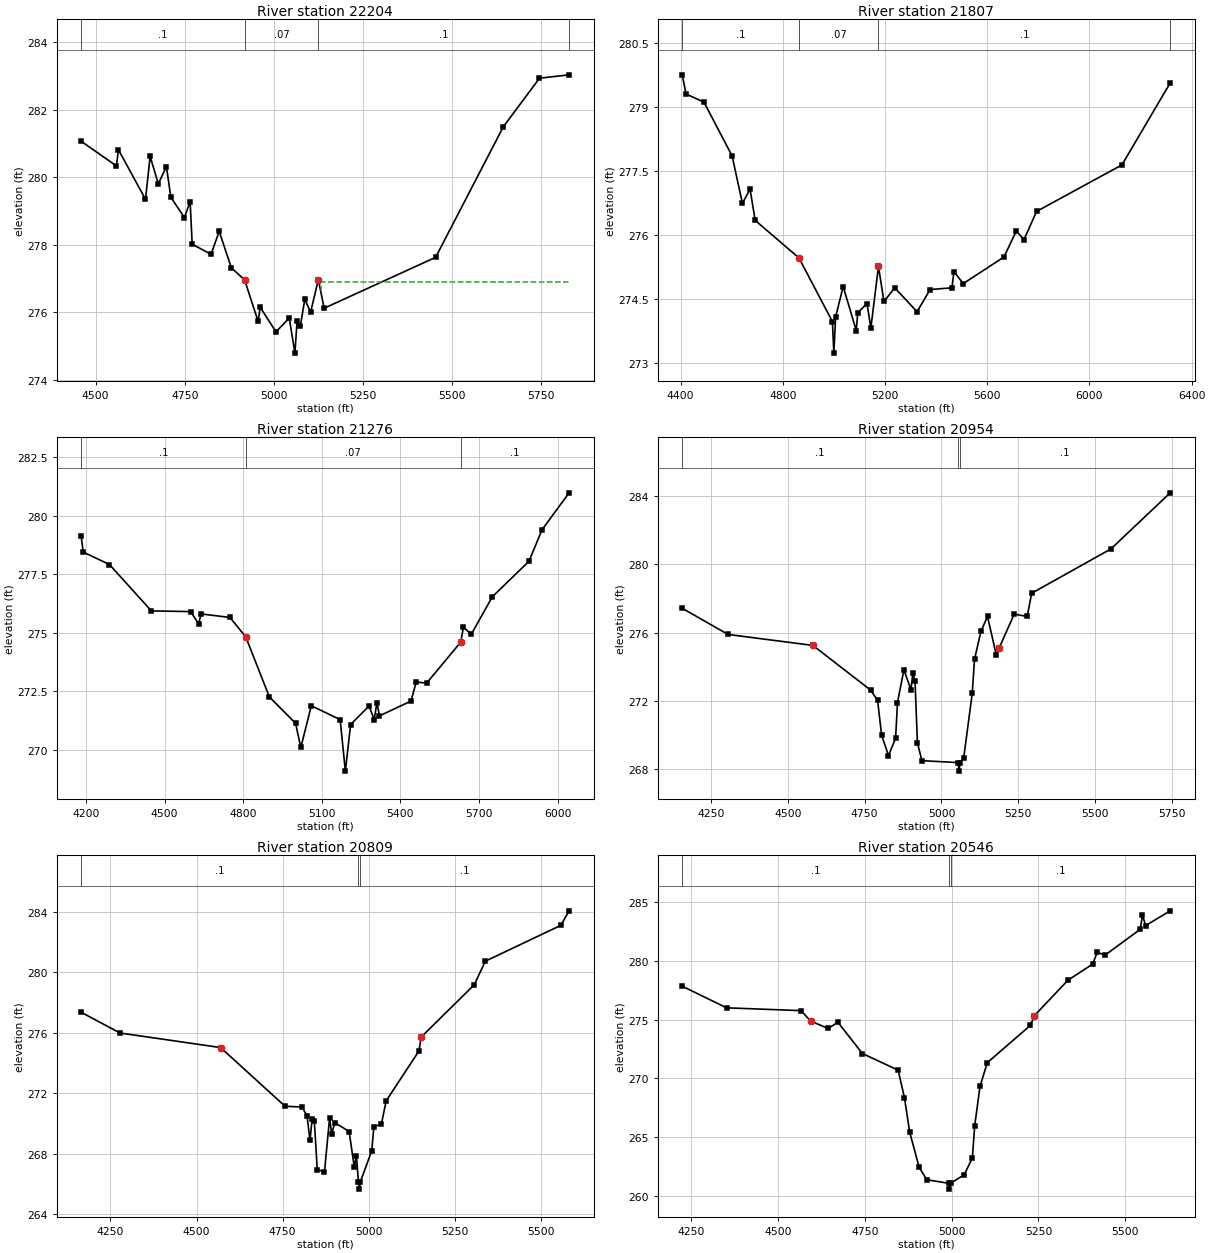
Type RM Length L Ch R = 1 ,22204   ,397,397,397
BEGIN DESCRIPTION:
UNT 058 IN LACR 40.0
END DESCRIPTION:
XS GIS Cut Line= 3
      2245541.09     13212276.71      2245064.73     13211403.72
      2244695.83     13211338.62
#Sta/Elev= 30
  4459.6  281.07  4558.4  280.34  4564.1  280.82    4640  279.35  4653.1  280.62
  4675.9  279.81  4698.7  280.32  4711.2  279.41  4749.2  278.81  4765.3  279.28
    4771  278.02    4824  277.72  4846.8   278.4  4880.9  277.32  4918.1  276.96
  4956.1  275.73  4961.8  276.15  5006.2  275.42  5043.4  275.83  5059.3  274.79
  5065.3  275.73  5074.6   275.6  5087.1  276.39  5103.2     276  5125.1  276.97
  5141.2  276.12  5454.1  277.63    5644   281.5  5745.5  282.94  5828.7  283.04
#Mann= 4 ,-1 , 0
  4459.6      .1       0  4918.1     .07       0  5125.1      .1       0
  5828.7     .05       0
#XS Ineff= 2 , 0
       0                 5131.53       0   276.9
Permanent Ineff=
       F       T
Bank Sta=4918.1,5125.1
XS Rating Curve= 0 ,0
Exp/Cntr=0.3,0.1

Type RM Length L Ch R = 1 ,21807   ,531,531,531
BEGIN DESCRIPTION:
Mapping XS e0dc8c56
END DESCRIPTION:
XS GIS Cut Line= 5
      2245637.01      13212101.6      2245662.77     13211744.19
      2245624.14     13211666.92      2245128.32     13210913.54
      2244690.44     13210559.37
#Sta/Elev= 30
  4406.2  279.75    4421   279.3  4491.2  279.11  4601.4  277.85  4641.6  276.74
  4671.6  277.07  4691.7  276.34    4863  275.46  4993.8  273.97  4999.6  273.23
  5006.6  274.08    5036  274.79  5087.2  273.76  5093.2  274.18  5129.3  274.39
  5144.4  273.82  5174.2  275.26  5195.6  274.44  5237.8  274.76  5325.2   274.2
  5376.4  274.72  5461.5  274.76  5469.7  275.14  5505.9  274.86  5665.1  275.48
  5713.7  276.09  5743.8  275.89    5793  276.55  6127.1  277.64    6316  279.56
#Mann= 4 ,-1 , 0
  4406.2      .1       0    4863     .07       0  5174.2      .1       0
    6316     .05       0
#XS Ineff= 2 , 0
       0                  5174.2       0   275.2
Permanent Ineff=
       F       T
Bank Sta=4863,5174.2
XS Rating Curve= 0 ,0
Exp/Cntr=0.3,0.1

Type RM Length L Ch R = 1 ,21276   ,322,322,322
BEGIN DESCRIPTION:
Mapping XS 87b9310d
END DESCRIPTION:
XS GIS Cut Line= 3
      2245778.68     13212014.66       2245781.9     13211473.75
       2245733.6     13210153.75
#Sta/Elev= 30
    4182  279.11  4189.8  278.44  4289.8  277.91  4449.8  275.93  4599.8   275.9
  4629.8  275.38  4639.8   275.8  4749.8  275.65  4809.9  274.82  4899.9  272.26
    5000  271.13    5020   270.1    5060  271.88  5170.1  271.29  5189.9  269.09
  5210.1  271.08  5280.2  271.87  5300.2  271.29  5310.2  272.01  5320.2  271.45
  5440.3  272.08  5460.3  272.89  5500.3  272.85  5630.4   274.6  5640.4  275.24
  5670.4  274.93  5750.5  276.53  5890.6  278.05  5940.6   279.4  6043.8  280.97
#Mann= 3 , 0 , 0
    4182      .1       0  4809.9     .07       0  5630.4      .1       0
Bank Sta=4809.9,5630.4
XS Rating Curve= 0 ,0
Exp/Cntr=0.3,0.1

Type RM Length L Ch R = 1 ,20954   ,145,145,145
BEGIN DESCRIPTION:
Mapping XS c73ca792
END DESCRIPTION:
XS GIS Cut Line= 5
      2245810.87     13211885.85      2245810.87     13211518.82
      2245949.32     13211241.94      2246280.94     13210791.19
      2246570.49     13210591.72
#Sta/Elev= 30
  4156.4  277.42  4305.4  275.89  4581.5  275.25  4769.8  272.63  4792.1  272.03
  4805.1     270  4827.5  268.81  4850.6  269.81  4856.8  271.91  4877.6  273.82
  4900.7  272.66  4906.9  273.66  4913.8  273.19  4921.6  269.56  4936.2  268.51
  5054.3   268.4  5057.1   267.9  5060.3   268.4    5072  268.64    5100  272.44
  5107.5  274.44  5128.3  276.07  5149.7  276.94  5178.5  274.68  5186.9  275.07
  5236.6  277.08  5278.8  276.94  5293.4   278.3  5551.3  280.89  5744.2  284.17
#Mann= 3 ,-1 , 0
  4156.4      .1       0  5054.3     .07       0  5060.3      .1       0
Bank Sta=4581.5,5186.9
XS Rating Curve= 0 ,0
Exp/Cntr=0.3,0.1

Type RM Length L Ch R = 1 ,20809   ,263,263,263
BEGIN DESCRIPTION:
Mapping XS 86a1fa35
END DESCRIPTION:
XS GIS Cut Line= 4
      2245826.97     13211879.43      2245852.73     13211615.41
      2246348.55     13210897.44      2246543.86     13210698.92
#Sta/Elev= 30
  4165.3  277.36  4278.4  275.99    4570  275.03  4756.9  271.15  4805.9   271.1
  4820.7  270.53  4829.5   268.9  4835.6  270.31    4842  270.16  4850.5  266.96
  4871.5  266.82  4886.3  270.37  4892.4  269.31  4901.2  270.07  4943.1  269.48
    4958  267.12  4964.1  267.89  4969.9  266.17  4972.6  265.67  4975.9  266.17
  5008.7  268.21  5014.8   269.8  5036.5  269.96  5050.6  271.51  5145.8  274.81
    5152  275.72  5306.1  279.18  5338.3  280.74  5557.5  283.11  5581.6  284.07
#Mann= 3 ,-1 , 0
  4165.3      .1       0  4969.9     .07       0  4975.9      .1       0
Bank Sta=4570,5152
XS Rating Curve= 0 ,0
Exp/Cntr=0.3,0.1

Type RM Length L Ch R = 1 ,20546   ,111,111,111
BEGIN DESCRIPTION:
Mapping XS 6e7c5dcc
END DESCRIPTION:
XS GIS Cut Line= 5
      2245836.64     13211918.02      2245939.66     13211602.53
      2246158.59     13211412.58       2246767.1     13211016.56
      2246792.79     13210965.18
#Sta/Elev= 30
  4224.2  277.85  4351.7  276.01  4566.3  275.77  4593.7  274.89  4644.1  274.25
  4672.6  274.78  4742.9  272.12  4845.9   270.7  4864.2  268.34  4879.3   265.4
  4906.4  262.43  4928.4  261.37    4991  261.07  4993.7  260.57    4997  261.07
  5036.2   261.8  5059.7  263.22  5066.4  265.96  5081.6  269.31  5102.7  271.34
  5226.5  274.51  5238.6  275.35  5334.1  278.34  5405.7  279.73  5419.6  280.74
  5441.5  280.49  5543.4   282.7  5549.4  283.93  5558.5  283.01  5629.4  284.27
#Mann= 3 ,-1 , 0
  4224.2      .1       0    4991     .07       0    4997      .1       0
Bank Sta=4593.7,5238.6
XS Rating Curve= 0 ,0
Exp/Cntr=0.3,0.1

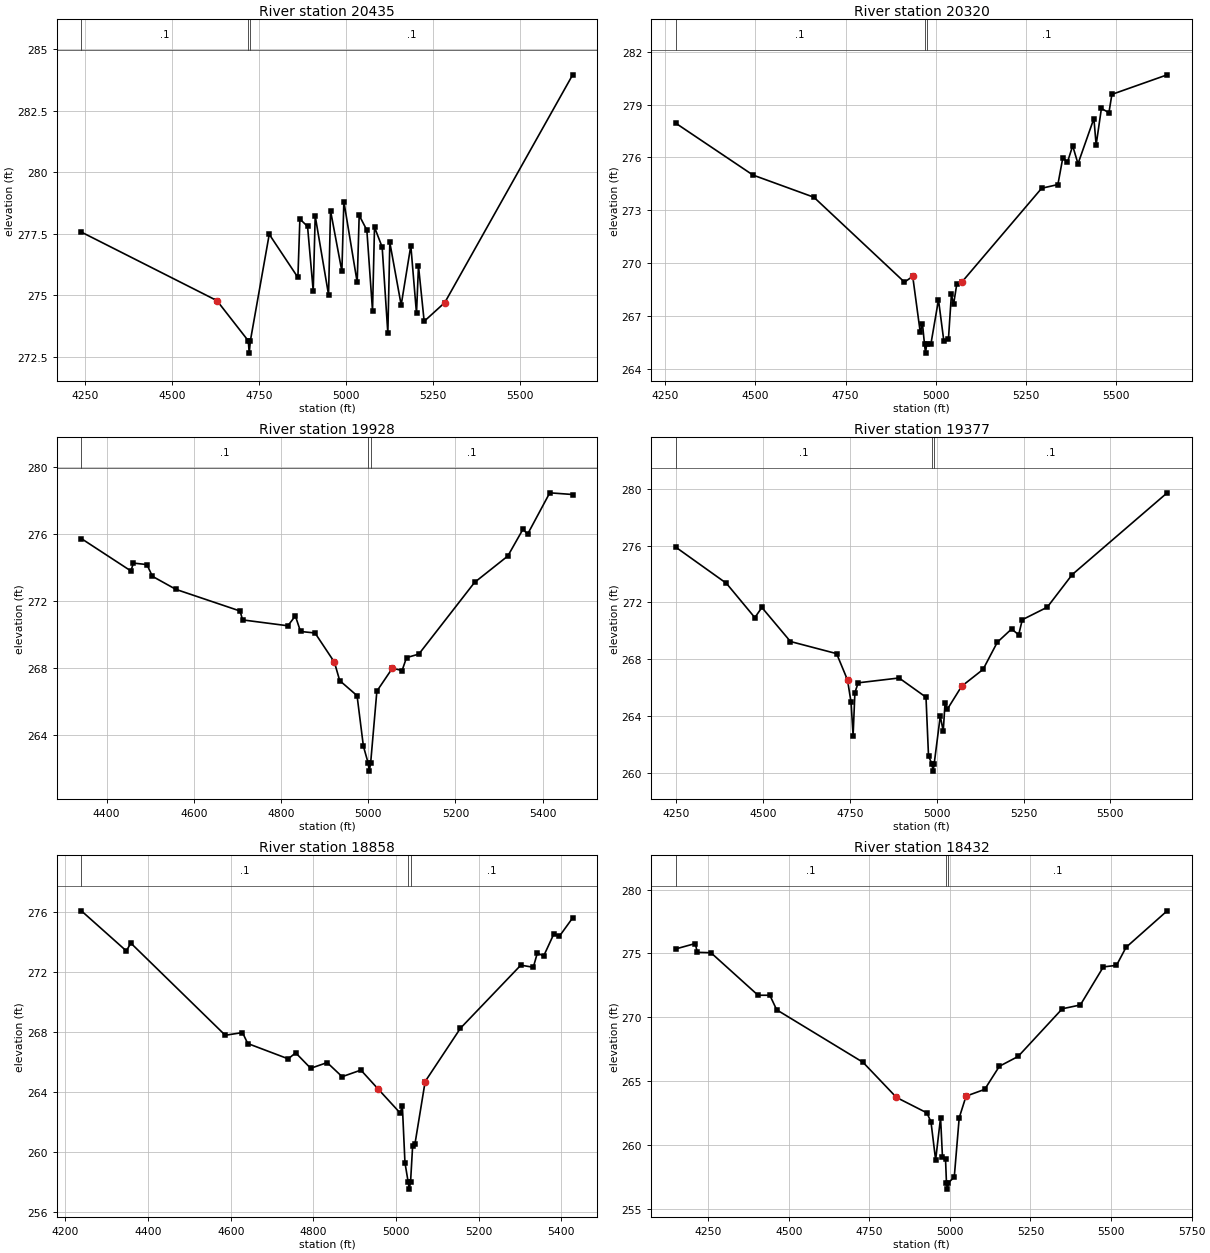
Type RM Length L Ch R = 1 ,20435   ,115,115,115
BEGIN DESCRIPTION:
Mapping XS 68672fd6
END DESCRIPTION:
XS GIS Cut Line= 5
      2245872.05      13211963.1      2245981.51     13211644.39
      2246123.18      13211531.7      2246609.34     13211274.13
      2246853.35     13211033.33
#Sta/Elev= 30
  4239.2  277.57  4628.6  274.79  4718.6  273.16  4721.3  272.66  4724.6  273.16
  4778.8  277.48  4861.1  275.73  4866.8   278.1  4888.8   277.8  4905.1  275.18
  4910.8  278.22  4949.1  275.03  4954.8  278.44  4987.4  275.98  4993.1  278.81
  5031.4  275.53  5037.1  278.25  5059.1  277.65  5075.4  274.38  5081.1  277.77
  5103.1  276.96  5119.4  273.47  5125.1  277.15  5157.7  274.61  5185.4  277.02
  5201.7  274.27  5207.4   276.2  5223.7  273.95  5282.9  274.71  5650.2  283.95
#Mann= 3 ,-1 , 0
  4239.2      .1       0  4718.6     .07       0  4724.6      .1       0
Bank Sta=4628.6,5282.9
XS Rating Curve= 0 ,0
Exp/Cntr=0.3,0.1

Type RM Length L Ch R = 1 ,20320   ,392,392,392
BEGIN DESCRIPTION:
UNT 058 IN LACR 39.0
END DESCRIPTION:
XS GIS Cut Line= 4
      2245923.56      13212024.3      2246087.76     13211724.88
      2246673.73     13211315.99      2246921.67     13211135.67
#Sta/Elev= 30
  4279.3  277.94  4493.1     275  4662.2  273.74  4913.4  268.92  4936.2  269.25
  4957.1  266.07  4963.2  266.57  4968.9  265.39  4971.7  264.89  4974.9  265.39
  4986.6   265.4  5007.7  267.92  5022.5  265.58  5035.3  265.69  5043.5  268.23
  5049.5  267.66  5058.3  268.79  5071.9  268.91  5293.8  274.25  5338.8  274.46
  5352.6  275.99  5365.3  275.73  5379.9  276.66  5394.6  275.64  5438.7  278.21
  5444.9  276.71  5459.5  278.78  5480.4  278.54  5488.6  279.58  5641.9  280.69
#Mann= 3 ,-1 , 0
  4279.3      .1       0  4968.9     .07       0  4974.9      .1       0
Bank Sta=4936.2,5071.9
XS Rating Curve= 0 ,0
Exp/Cntr=0.3,0.1

Type RM Length L Ch R = 1 ,19928   ,551,551,551
BEGIN DESCRIPTION:
UNT 058 IN LACR 38.0
END DESCRIPTION:
XS GIS Cut Line= 3
      2246406.51     13212278.63      2246625.43     13211879.42
      2246915.21      13211274.1
#Sta/Elev= 30
  4342.3  275.71  4455.9  273.78  4461.6  274.25  4492.6  274.16  4505.2  273.46
  4559.2  272.68  4706.2  271.39  4711.9  270.86  4815.8  270.51  4832.9   271.1
  4844.8  270.17    4878  270.08  4922.4  268.34  4934.6  267.24  4974.4  266.34
  4988.9  263.33  4999.6  262.34  5002.4  261.84  5005.6  262.34  5019.8  266.61
  5055.4  267.98  5077.6  267.84  5087.8  268.61    5116  268.82  5243.9   273.1
    5320  274.67  5354.8  276.27  5365.3  275.97  5416.2  278.44  5468.7  278.34
#Mann= 3 ,-1 , 0
  4342.3      .1       0  4999.6     .07       0  5005.6      .1       0
Bank Sta=4922.4,5055.4
XS Rating Curve= 0 ,0
Exp/Cntr=0.3,0.1

Type RM Length L Ch R = 1 ,19377   ,519,519,519
BEGIN DESCRIPTION:
UNT 058 IN LACR 37.0
END DESCRIPTION:
XS GIS Cut Line= 3
      2247206.54     13212468.58      2247286.94     13212116.09
      2247046.04     13211090.75
#Sta/Elev= 30
  4248.8  275.88  4394.2  273.35  4476.2  270.94  4496.5  271.65  4578.8  269.26
  4711.7  268.41  4743.1  266.56  4753.4  264.98  4759.2  262.66  4764.4  265.68
  4773.9  266.36  4891.6   266.7  4969.1  265.35  4976.4  261.21  4986.6  260.66
  4989.4  260.16  4992.6  260.66  5010.2  264.02  5018.8  262.97  5023.9  264.92
  5030.7  264.51  5071.8  266.12  5133.4   267.3  5174.5  269.21  5215.6  270.14
    5236  269.73  5246.4  270.79  5318.3  271.67  5390.2  273.96  5663.6   279.7
#Mann= 3 ,-1 , 0
  4248.8      .1       0  4986.6     .07       0  4992.6      .1       0
Bank Sta=4743.1,5071.8
XS Rating Curve= 0 ,0
Exp/Cntr=0.3,0.1

Type RM Length L Ch R = 1 ,18858   ,426,426,426
BEGIN DESCRIPTION:
UNT 058 IN LACR 36.0
END DESCRIPTION:
XS GIS Cut Line= 3
      2247287.71     13212496.88      2247587.72     13211796.85
      2247737.72     13211396.85
#Sta/Elev= 30
  4238.4  276.08  4347.2  273.41  4358.1  273.93  4586.6  267.79  4628.3  267.97
    4641  267.24  4738.9  266.22    4757  266.62  4793.3  265.59  4833.2  265.97
  4869.4  265.03  4914.8  265.47  4956.5  264.21  5009.8  262.61  5015.1   263.1
  5021.4   259.3    5029  258.04  5031.8  257.54    5035  258.04    5040  260.43
  5045.4  260.52  5070.3  264.71  5155.7  268.26  5301.7  272.46    5332  272.32
  5341.8  273.28  5356.9  273.06  5381.8  274.55  5395.2  274.39  5427.2  275.61
#Mann= 3 ,-1 , 0
  4238.4      .1       0    5029     .07       0    5035      .1       0
Bank Sta=4956.5,5070.3
XS Rating Curve= 0 ,0
Exp/Cntr=0.3,0.1

Type RM Length L Ch R = 1 ,18432   ,500,500,500
BEGIN DESCRIPTION:
UNT 058 IN LACR 35.0
END DESCRIPTION:
XS GIS Cut Line= 3
      2247447.71     13212728.27      2248084.63     13211707.96
      2248146.48     13211392.56
#Sta/Elev= 30
  4149.8  275.36  4210.2  275.78  4216.1  275.09  4258.6  275.06  4404.8  271.73
  4441.4  271.73  4462.6  270.59  4730.4  266.48  4834.2  263.73  4928.6  262.52
  4941.3  261.81  4955.7  258.83    4971  262.15  4976.9  259.07  4986.4  258.89
  4989.3  257.05    4992  256.55  4995.3  257.05  5013.5  257.49  5028.8  262.13
  5050.1  263.83  5107.9  264.36  5153.5  266.17  5211.7  266.94  5348.5  270.67
  5404.7  270.97    5476  273.95  5516.8  274.07  5546.4  275.48    5674  278.34
#Mann= 3 ,-1 , 0
  4149.8      .1       0  4989.3     .07       0  4995.3      .1       0
Bank Sta=4834.2,5050.1
XS Rating Curve= 0 ,0
Exp/Cntr=0.3,0.1

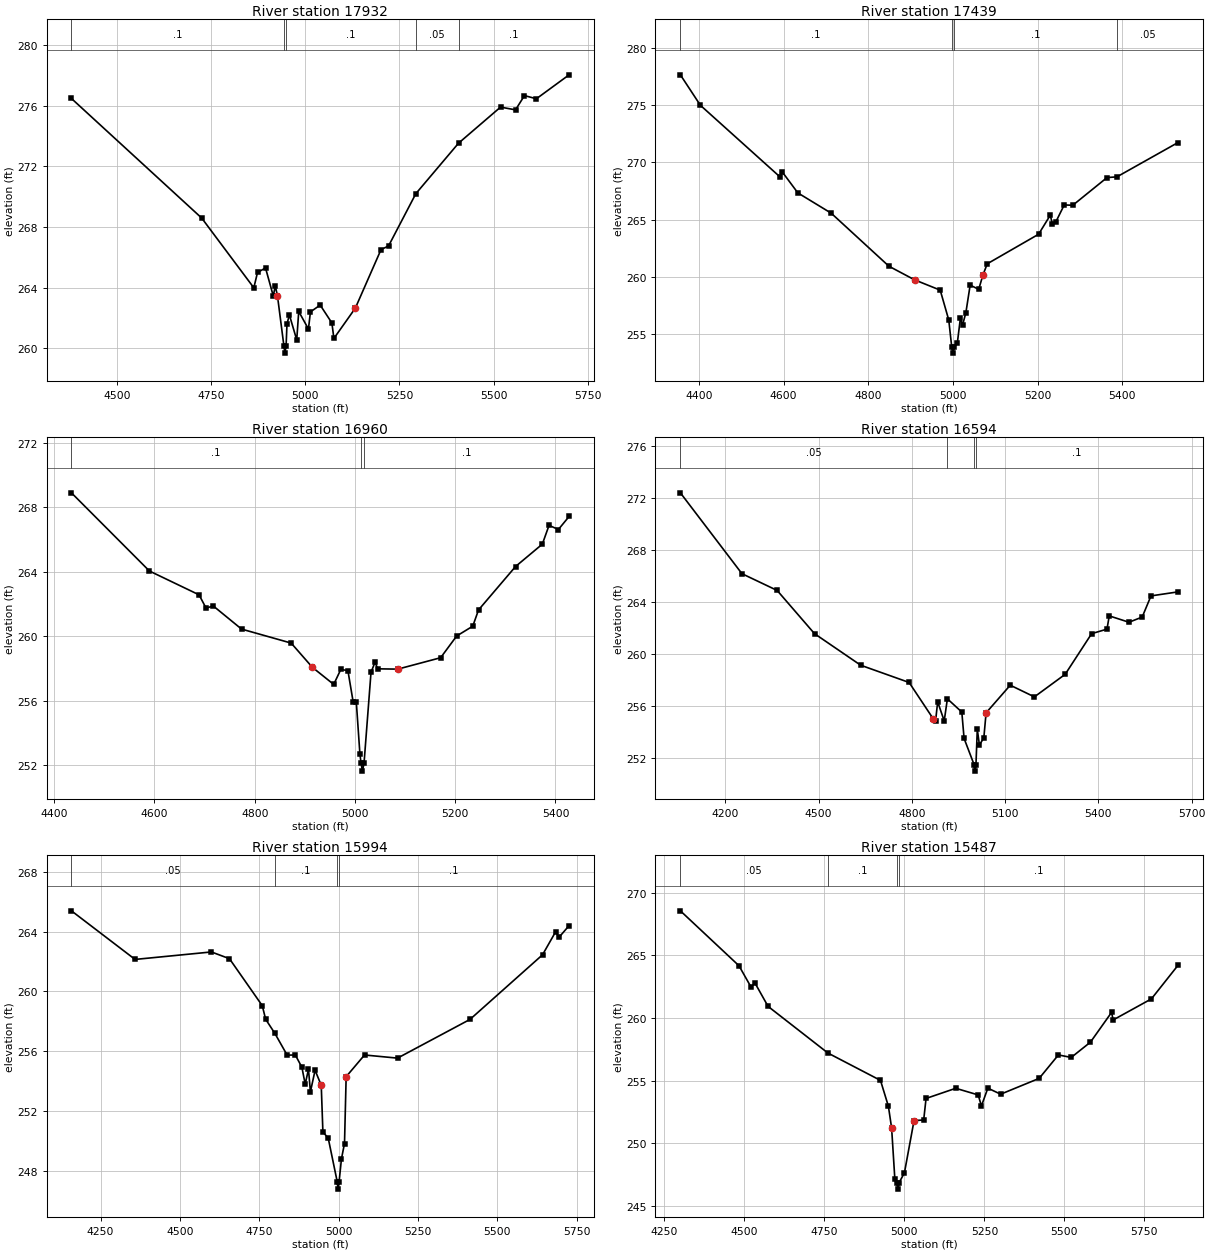
Type RM Length L Ch R = 1 ,17932   ,493,493,493
BEGIN DESCRIPTION:
UNT 058 IN LACR 34.0
END DESCRIPTION:
XS GIS Cut Line= 2
      2248115.56     13212783.91      2248548.42     13211534.78
#Sta/Elev= 30
  4378.7  276.48  4724.8  268.59  4863.2  263.99    4873     265  4894.3   265.3
  4914.9  263.45  4920.2  264.11  4925.9  263.48    4943  260.18  4945.8  259.68
    4949  260.18  4951.3  261.61  4957.7   262.2  4977.2  260.55  4982.5  262.43
  5008.3  261.27  5013.6   262.4  5039.5  262.85  5070.6  261.67  5075.9  260.65
  5132.9  262.65  5201.1  266.51  5221.1  266.75  5293.6   270.2    5407  273.53
  5518.6  275.91  5558.4  275.73  5582.1  276.67  5613.8  276.46  5700.7  278.04
#Mann= 5 ,-1 , 0
  4378.7      .1       0    4943     .07       0    4949      .1       0
  5293.6     .05       0    5407      .1       0
Bank Sta=4925.9,5132.9
XS Rating Curve= 0 ,0
Exp/Cntr=0.3,0.1

Type RM Length L Ch R = 1 ,17439   ,479,479,479
BEGIN DESCRIPTION:
UNT 058 IN LACR 33.0
END DESCRIPTION:
XS GIS Cut Line= 3
      2248523.69     13212876.66      2248733.92     13212548.94
      2248845.09      13211770.8
#Sta/Elev= 30
    4356  277.64  4403.3  274.98  4591.2  268.73  4597.1  269.14  4633.5  267.33
  4712.2  265.56  4848.5  260.93  4909.1  259.74  4969.7  258.84  4989.9  256.23
    4997  253.84  4999.7  253.34    5003  253.84  5010.1  254.22  5017.4   256.4
  5022.5   255.8  5030.3  256.87  5040.4  259.28  5060.6  258.91  5070.7  260.17
  5080.8  261.14    5202  263.72  5229.6  265.38  5234.6  264.64  5242.4  264.77
  5262.6  266.28  5282.8  266.25  5363.7  268.67    5387  268.73  5531.4  271.73
#Mann= 4 ,-1 , 0
    4356      .1       0    4997     .07       0    5003      .1       0
    5387     .05       0
Bank Sta=4909.1,5070.7
XS Rating Curve= 0 ,0
Exp/Cntr=0.3,0.1

Type RM Length L Ch R = 1 ,16960   ,366,366,366
BEGIN DESCRIPTION:
UNT 058 IN LACR 32.0
END DESCRIPTION:
XS GIS Cut Line= 3
      2248787.71     13212846.87      2249187.72     13212446.85
      2249337.72     13212046.85
#Sta/Elev= 30
  4434.3  268.91  4589.9  264.05  4688.9  262.57    4703  261.74  4717.2  261.88
  4773.7  260.44  4872.7  259.57  4915.1  258.06  4957.6     257  4971.7  257.93
  4985.9  257.86  4996.5  255.89  5002.7  255.89  5009.8   252.7  5012.1  252.11
  5014.9  251.61  5018.1  252.11    5032  257.75    5040  258.38  5045.4  257.97
  5085.4  257.95  5170.9  258.66  5202.9  260.01    5235  260.62  5246.5  261.63
  5320.4  264.33  5373.8  265.72  5387.2  266.89  5405.8  266.63  5427.2  267.44
#Mann= 3 ,-1 , 0
  4434.3      .1       0  5012.1     .07       0  5018.1      .1       0
Bank Sta=4915.1,5085.4
XS Rating Curve= 0 ,0
Exp/Cntr=0.3,0.1

Type RM Length L Ch R = 1 ,16594   ,600,600,600
BEGIN DESCRIPTION:
UNT 058 IN LACR 31.0
END DESCRIPTION:
XS GIS Cut Line= 3
      2248888.49     13213117.87      2249278.09     13212740.64
      2250001.56      13211967.7
#Sta/Elev= 30
  4055.3  272.43  4253.4   266.2  4366.6  264.91  4486.8  261.58  4635.3  259.15
  4791.2  257.82  4868.8  255.02  4876.2  254.83    4883  256.33  4904.1  254.86
  4914.3  256.56  4960.7  255.54    4968  253.51  5000.2  251.49  5002.9  250.99
  5006.2  251.49  5010.5  254.21  5017.3  253.01  5031.5  253.55  5038.8  255.48
  5116.5  257.61  5194.2  256.71  5293.3  258.45  5378.3  261.58  5427.7  261.93
    5435  262.95  5498.5  262.46    5541  262.86  5569.3  264.49  5656.3   264.8
#Mann= 4 ,-1 , 0
  4055.3     .05       0  4914.3      .1       0  5000.2     .07       0
  5006.2      .1       0
Bank Sta=4868.8,5038.8
XS Rating Curve= 0 ,0
Exp/Cntr=0.3,0.1

Type RM Length L Ch R = 1 ,15994   ,507,507,507
BEGIN DESCRIPTION:
UNT 058 IN LACR 30.0
END DESCRIPTION:
XS GIS Cut Line= 3
      2249494.55     13213297.14      2249927.37     13212901.41
        2250193.     13211956.29
#Sta/Elev= 30
  4158.2  265.39  4358.8  262.14  4599.3  262.64  4656.1  262.19  4759.5  259.05
  4770.2  258.14  4799.4  257.19    4838  255.74  4863.7  255.75  4884.4  254.93
  4894.8   253.8  4905.2  254.79  4911.3  253.29    4926  254.73  4945.4  253.72
  4950.6  250.61  4967.5  250.18  4995.7  247.28  4998.4  246.78  5001.7  247.28
  5009.1  248.81  5018.7  249.83  5023.9   254.3  5081.8  255.75  5185.7  255.54
  5414.2  258.13  5642.7  262.45  5683.7  263.98  5694.6  263.62  5726.4   264.4
#Mann= 4 ,-1 , 0
  4158.2     .05       0  4799.4      .1       0  4995.7     .07       0
  5001.7      .1       0
Bank Sta=4945.4,5023.9
XS Rating Curve= 0 ,0
Exp/Cntr=0.3,0.1

Type RM Length L Ch R = 1 ,15487   ,385,385,385
BEGIN DESCRIPTION:
UNT 058 IN LACR 29.0
END DESCRIPTION:
XS GIS Cut Line= 3
       2250261.3     13213513.58       2250372.6     13213043.64
       2250298.4     13211973.85
#Sta/Elev= 30
  4299.9  268.54  4483.1  264.16  4520.3  262.48  4532.9  262.79    4574  260.92
  4761.1   257.2  4925.3  255.02    4950  252.96  4960.1  251.22  4970.1  247.18
  4977.1  246.85  4979.8  246.35  4983.1  246.85  5000.1  247.65  5030.2  251.82
  5060.3  251.86  5067.7  253.58  5160.5  254.39  5230.7  253.86  5240.7  252.98
  5260.8   254.4  5300.9  253.92  5421.2  255.18  5481.3  257.05  5521.4  256.85
  5581.5  258.07  5647.4  260.44  5652.5  259.84    5772  261.52  5855.2   264.2
#Mann= 4 ,-1 , 0
  4299.9     .05       0  4761.1      .1       0  4977.1     .07       0
  4983.1      .1       0
Bank Sta=4960.1,5030.2
XS Rating Curve= 0 ,0
Exp/Cntr=0.3,0.1

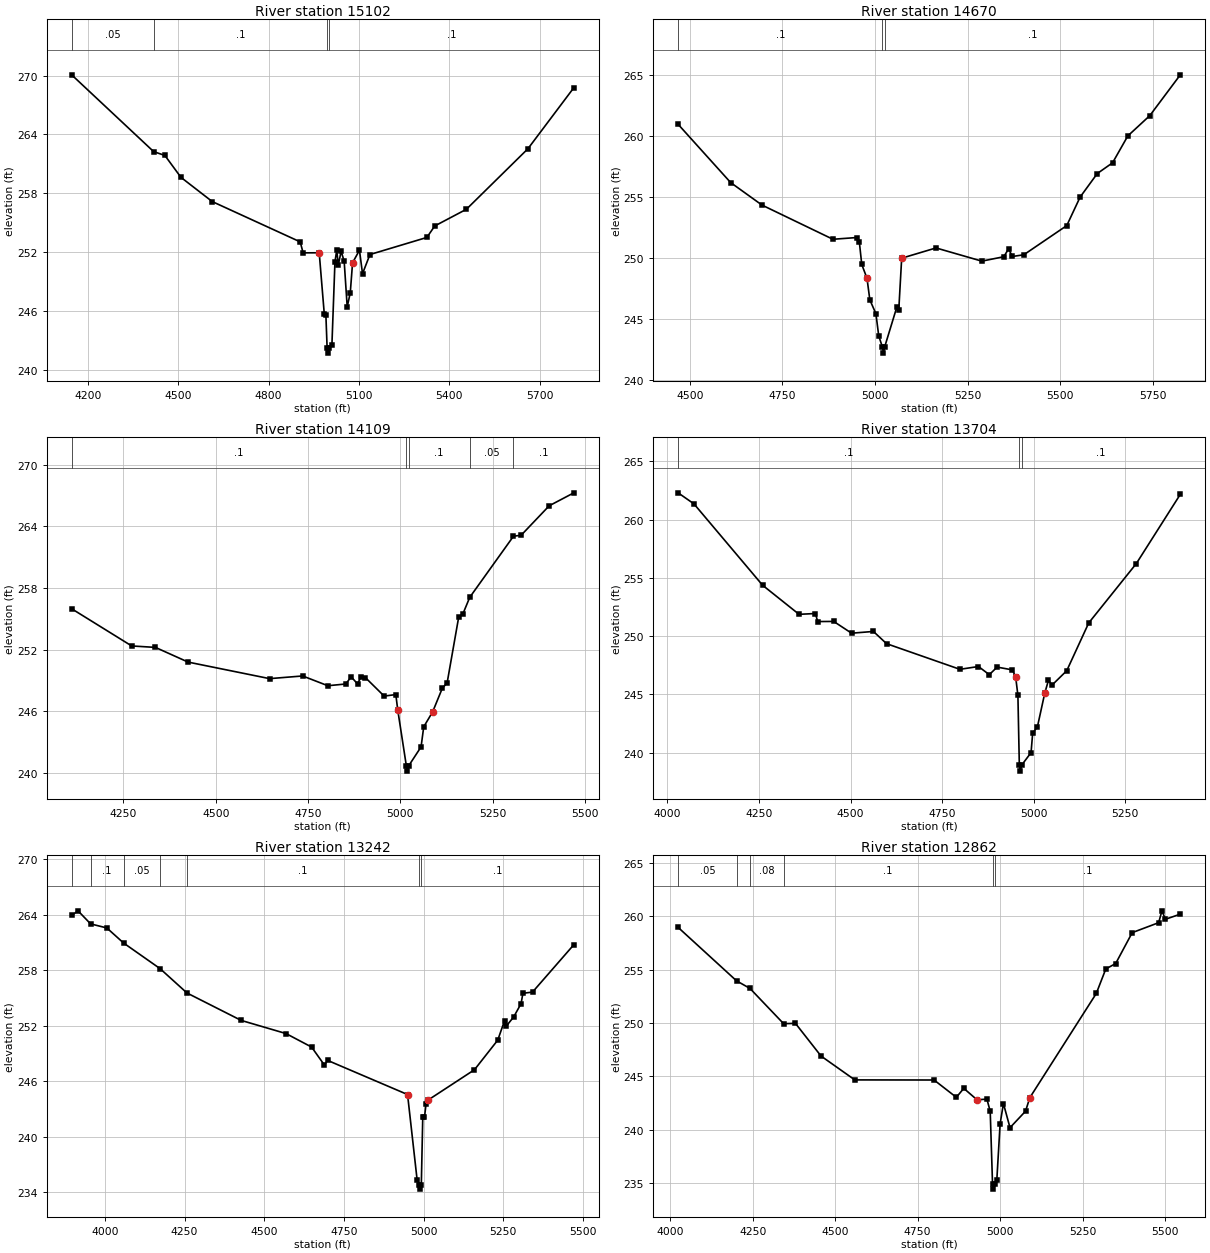
Type RM Length L Ch R = 1 ,15102   ,432,432,432
BEGIN DESCRIPTION:
UNT 058 IN LACR 28.0
END DESCRIPTION:
XS GIS Cut Line= 3
      2250387.72     13213596.85      2250687.72     13212796.85
      2250837.71      13211996.9
#Sta/Elev= 30
  4145.6  270.07    4418  262.25  4455.3  261.86  4508.7  259.63  4612.8  257.16
  4904.8  253.06  4914.6  251.94    4968  251.95  4984.9   245.7  4990.2   245.6
  4994.3  242.23  4997.1  241.73  5000.3  242.23  5010.2  242.56  5020.3  251.02
  5026.3  252.23  5031.4  250.69  5040.7   252.1  5050.9   251.1    5061  246.44
  5071.2  247.88  5078.8  250.93  5101.7  252.21  5111.9  249.82  5136.5  251.77
  5325.6  253.51  5351.9  254.68    5457  256.38  5661.3  262.54  5813.9  268.76
#Mann= 4 ,-1 , 0
  4145.6     .05       0    4418      .1       0  4994.3     .07       0
  5000.3      .1       0
Bank Sta=4968,5078.8
XS Rating Curve= 0 ,0
Exp/Cntr=0.3,0.1

Type RM Length L Ch R = 1 ,14670   ,561,561,561
BEGIN DESCRIPTION:
UNT 058 IN LACR 27.0
END DESCRIPTION:
XS GIS Cut Line= 3
      2250687.73     13213396.85      2251037.72     13212996.86
      2251237.72     13212196.88
#Sta/Elev= 30
  4468.5  260.93  4610.4  256.16  4694.9  254.32  4886.6  251.52  4950.2  251.66
  4957.8  251.32  4964.4  249.46  4978.6  248.32  4986.2  246.56  5002.6  245.43
  5010.3   243.6  5020.2   242.7  5022.9   242.2  5026.2   242.7  5059.3  245.99
  5064.4  245.76  5072.2  249.97  5164.9  250.81  5288.6  249.73  5347.9  250.09
  5360.8  250.73  5371.1  250.11    5402  250.25    5518  252.64    5554  254.97
  5600.4   256.9  5641.7  257.78  5682.9  259.98  5742.2  261.64  5824.6  264.98
#Mann= 3 ,-1 , 0
  4468.5      .1       0  5020.2     .07       0  5026.2      .1       0
Bank Sta=4978.6,5072.2
XS Rating Curve= 0 ,0
Exp/Cntr=0.3,0.1

Type RM Length L Ch R = 1 ,14109   ,405,405,405
BEGIN DESCRIPTION:
UNT 058 IN LACR 26.0
END DESCRIPTION:
XS GIS Cut Line= 3
      2251145.59     13213593.95      2251324.89     13213365.19
      2251664.87     13212351.44
#Sta/Elev= 30
  4109.9  255.99  4272.5  252.37  4336.7  252.23  4425.2   250.8    4646  249.19
  4735.4  249.45  4803.7   248.5  4852.3  248.67  4866.8  249.37    4884  248.68
  4893.1  249.34  4905.1   249.3  4956.2  247.49  4987.7  247.64    4993  246.13
  5016.3  240.69    5019  240.19  5022.3  240.69  5056.1  242.55  5063.3   244.5
  5087.6  245.97  5113.9  248.28  5126.6  248.76  5158.2  255.22  5168.8  255.44
  5187.9   257.1  5306.4  263.05    5327  263.14  5403.1  266.01  5469.8  267.27
#Mann= 5 ,-1 , 0
  4109.9      .1       0  5016.3     .07       0  5022.3      .1       0
  5187.9     .05       0  5306.4      .1       0
Bank Sta=4993,5087.6
XS Rating Curve= 0 ,0
Exp/Cntr=0.3,0.1

Type RM Length L Ch R = 1 ,13704   ,462,462,462
BEGIN DESCRIPTION:
UNT 058 IN LACR 25.0
END DESCRIPTION:
XS GIS Cut Line= 3
      2251237.73     13213846.83      2251787.72     13213046.85
      2251787.72     13212646.85
#Sta/Elev= 30
  4029.2  262.31  4072.5  261.36  4259.7  254.38  4359.3  251.88    4404  251.95
  4410.1  251.26  4453.9  251.27  4502.7  250.26  4562.3  250.41  4598.2  249.36
  4798.4  247.16  4849.1   247.4  4878.6   246.7  4899.9  247.35  4941.8  247.11
  4950.6  246.49  4956.7  244.93  4960.6  238.92  4963.3  238.42  4966.6  238.92
  4992.6  240.01    4997  241.68    5010  242.23    5030  245.11    5040  246.21
    5050  245.81    5090  247.04    5150  251.14    5280  256.24    5400  262.18
#Mann= 3 ,-1 , 0
  4029.2      .1       0  4960.6     .07       0  4966.6      .1       0
Bank Sta=4950.6,5030
XS Rating Curve= 0 ,0
Exp/Cntr=0.3,0.1

Type RM Length L Ch R = 1 ,13242   ,380,380,380
BEGIN DESCRIPTION:
UNT 058 IN LACR 24.0
END DESCRIPTION:
XS GIS Cut Line= 3
      2252237.72     13214146.82      2252137.72     13213046.85
      2251887.72     13212646.85
#Sta/Elev= 30
  3895.5  263.93  3915.5  264.43    3955  263.02  4005.9  262.58  4058.6  260.95
  4172.8  258.19  4257.6  255.55  4427.6  252.59  4568.2  251.17  4648.6  249.71
  4688.7  247.77  4698.8  248.27  4949.8  244.58  4979.9  235.33    4987  234.86
  4989.7  234.36    4993  234.86  4997.5  242.11  5002.9  242.11  5007.7  243.54
  5013.6  243.97  5159.8  247.26  5232.9  250.46  5254.1  252.55    5260  251.99
    5283  252.97    5306   254.4  5311.9  255.52    5342  255.65  5471.7  260.77
#Mann= 7 ,-1 , 0
  3895.5     .05       0    3955      .1       0  4058.6     .05       0
  4172.8     .08       0  4257.6      .1       0    4987     .07       0
    4993      .1       0
Bank Sta=4949.8,5013.6
XS Rating Curve= 0 ,0
Exp/Cntr=0.3,0.1

Type RM Length L Ch R = 1 ,12862   ,569,569,569
BEGIN DESCRIPTION:
UNT 058 IN LACR 23.0
END DESCRIPTION:
XS GIS Cut Line= 3
      2252363.74      13213903.2      2252499.79     13213433.21
      2252450.35     13212401.18
#Sta/Elev= 30
  4023.8  258.94  4200.9  253.94  4241.6  253.23  4343.6  249.93  4379.5  249.96
  4457.2   246.9  4559.5  244.67  4799.8  244.66  4867.3  243.04  4889.9  243.88
  4929.9  242.81    4960  242.87    4970  241.73    4977  234.95  4979.7  234.45
    4983  234.95    4990   235.3    5000  240.55    5010  242.46    5030   240.2
    5077  241.74  5090.1  243.01  5291.6  252.76  5320.4  255.05  5350.4  255.56
  5400.5  258.45  5480.6  259.38  5490.6  260.49  5501.2   259.7  5546.3  260.18
#Mann= 6 ,-1 , 0
  4023.8     .05       0  4200.9      .1       0  4241.6     .08       0
  4343.6      .1       0    4977     .07       0    4983      .1       0
Bank Sta=4929.9,5090.1
XS Rating Curve= 0 ,0
Exp/Cntr=0.3,0.1

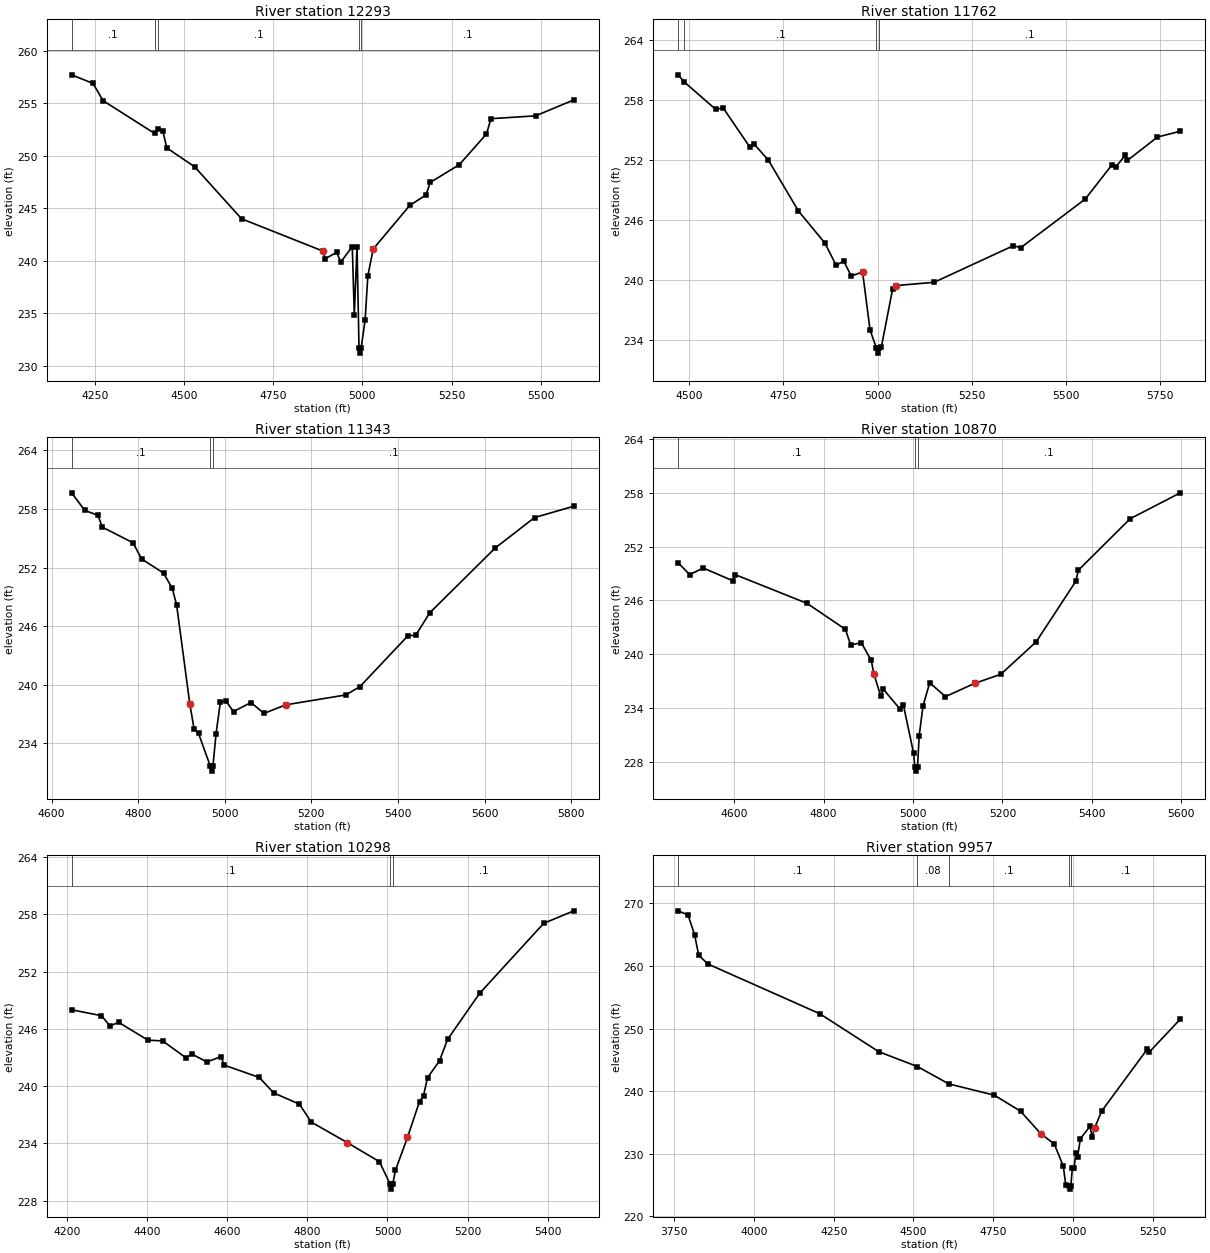
Type RM Length L Ch R = 1 ,12293   ,531,531,531
BEGIN DESCRIPTION:
UNT 058 IN LACR 22.0
END DESCRIPTION:
XS GIS Cut Line= 3
      2252505.96     13213915.56      2252666.75     13213593.99
      2253167.61     13212672.66
#Sta/Elev= 30
  4184.7  257.72  4244.6   256.9  4272.7  255.26  4417.4  252.13  4426.1   252.6
  4440.3  252.37  4451.6  250.75  4529.7  248.95    4661     244  4889.9  240.91
  4895.6  240.19  4927.9  240.79  4939.3  239.87  4971.6  241.34  4977.3  234.87
  4984.9  241.34  4990.5  231.69  4993.2  231.19  4996.5  231.69  5007.6  234.34
  5015.3  238.57  5030.4  241.12  5132.8  245.27  5178.4  246.27  5190.1  247.46
  5271.9  249.16  5347.9  252.08  5360.5  253.54  5485.7  253.81  5592.9  255.33
#Mann= 5 ,-1 , 0
  4184.7      .1       0  4417.4     .08       0  4426.1      .1       0
  4990.5     .07       0  4996.5      .1       0
Bank Sta=4889.9,5030.4
XS Rating Curve= 0 ,0
Exp/Cntr=0.3,0.1

Type RM Length L Ch R = 1 ,11762   ,419,419,419
BEGIN DESCRIPTION:
UNT 058 IN LACR 21.0
END DESCRIPTION:
XS GIS Cut Line= 3
      2253167.63     13214076.28      2253192.37     13213117.84
      2253241.84     13212746.78
#Sta/Elev= 30
  4470.4  260.49  4486.9  259.77  4569.9  257.05  4589.9  257.19  4659.9  253.33
  4671.3  253.61  4709.9  251.98  4789.9  246.89    4860   243.7    4890  241.47
    4910   241.9    4930  240.41    4960  240.81    4980     235    4997  233.21
  4999.7  232.71    5003  233.21    5010  233.33    5040  239.16    5050  239.46
    5150  239.78  5360.1  243.43  5380.1  243.24  5551.2  248.09  5621.8  251.49
  5631.9  251.29    5658  252.48    5663  251.94  5742.9  254.28  5803.5  254.86
#Mann= 4 ,-1 , 0
  4470.4     .05       0  4486.9      .1       0    4997     .07       0
    5003      .1       0
Bank Sta=4960,5050
XS Rating Curve= 0 ,0
Exp/Cntr=0.3,0.1

Type RM Length L Ch R = 1 ,11343   ,473,473,473
BEGIN DESCRIPTION:
UNT 058 IN LACR 20.0
END DESCRIPTION:
XS GIS Cut Line= 3
      2253587.73      13213746.9      2253537.72     13213396.85
      2253437.72     13212596.88
#Sta/Elev= 30
  4646.4  259.66  4676.7  257.86  4707.1  257.36  4717.2  256.15  4787.9  254.55
  4808.1  252.89  4858.6  251.44  4878.8  249.88  4888.9  248.17  4919.2  238.07
  4929.3  235.44  4939.4  235.03  4966.7  231.67  4969.4  231.17  4972.7  231.67
  4979.8  234.95  4989.9  238.26  5002.5  238.35  5020.2  237.27  5060.5  238.19
  5090.7  237.08  5141.1  237.96  5279.7  238.97  5312.4  239.83  5423.3  245.04
  5440.9  245.07  5473.7  247.39  5624.8  254.02  5715.5  257.13  5806.2  258.29
#Mann= 3 ,-1 , 0
  4646.4      .1       0  4966.7     .07       0  4972.7      .1       0
Bank Sta=4919.2,5141.1
XS Rating Curve= 0 ,0
Exp/Cntr=0.3,0.1

Type RM Length L Ch R = 1 ,10870   ,572,572,572
BEGIN DESCRIPTION:
UNT 058 IN LACR 19.0
END DESCRIPTION:
XS GIS Cut Line= 3
      2254008.61     13213612.56      2253965.33     13213278.62
      2253551.04     13212610.82
#Sta/Elev= 30
  4474.9   250.2  4500.8  248.89  4531.1  249.62  4597.6  248.19  4602.6  248.88
    4763  245.68  4848.8  242.78  4860.8  241.02  4884.3  241.29  4906.7  239.31
  4912.6  237.78  4927.9  235.33  4933.8  236.09  4970.5  233.91  4978.5  234.33
  5001.2  228.98  5004.1  227.46  5006.8  226.96  5010.1  227.46  5013.8  230.92
  5022.4  234.25  5037.3  236.81  5072.6  235.28  5138.2  236.76  5196.1  237.76
  5275.2  241.38  5363.8  248.13  5369.7  249.38  5485.4  255.12  5597.5  258.01
#Mann= 3 ,-1 , 0
  4474.9      .1       0  5004.1     .07       0  5010.1      .1       0
Bank Sta=4912.6,5138.2
XS Rating Curve= 0 ,0
Exp/Cntr=0.3,0.1

Type RM Length L Ch R = 1 ,10298   ,341,341,341
BEGIN DESCRIPTION:
UNT 058 IN LACR 18.0
END DESCRIPTION:
XS GIS Cut Line= 3
      2254064.27     13213606.34      2254342.53     13213154.95
       2254354.9     13212431.62
#Sta/Elev= 30
  4211.6     248  4286.1  247.38  4307.4  246.31  4328.7  246.69    4402  244.82
  4438.7  244.74  4496.7  242.98  4512.1  243.36  4548.7  242.54  4585.4   243.1
  4591.3  242.22    4680  240.91  4716.1  239.29    4780  238.12    4810  236.23
    4900  234.08    4980  232.08    5007  229.71  5009.8  229.21    5013  229.71
    5020  231.19    5050  234.63    5080  238.39    5090  239.01    5100  240.88
    5130  242.66    5150  244.89    5230  249.72  5390.1  257.06  5465.3  258.37
#Mann= 3 ,-1 , 0
  4211.6      .1       0    5007     .07       0    5013      .1       0
Bank Sta=4900,5050
XS Rating Curve= 0 ,0
Exp/Cntr=0.3,0.1

Type RM Length L Ch R = 1 ,9957    ,462,462,462
BEGIN DESCRIPTION:
UNT 058 IN LACR 17.0
END DESCRIPTION:
XS GIS Cut Line= 3
      2254987.71     13214096.82      2254687.72     13212896.85
      2254537.72     13212596.86
#Sta/Elev= 30
  3763.1   268.8    3794  268.15  3814.6  264.99  3827.5  261.73  3855.8  260.32
  4206.3  252.38  4391.8  246.29  4512.1  243.94  4610.6  241.16  4752.6  239.37
  4835.1  236.81  4899.5  233.16  4940.7  231.58  4969.1  228.03  4976.8     225
  4986.7  224.86  4989.4  224.36  4992.7  224.86  4997.4   227.7  5002.8   227.7
  5008.4  230.19    5014  229.56  5022.4  232.41  5053.1  234.41  5058.7  232.64
  5067.1  234.13  5089.4  236.83    5232  246.71  5237.6  246.21  5335.4   251.5
#Mann= 5 ,-1 , 0
  3763.1      .1       0  4512.1     .08       0  4610.6      .1       0
  4986.7     .07       0  4992.7      .1       0
Bank Sta=4899.5,5067.1
XS Rating Curve= 0 ,0
Exp/Cntr=0.3,0.1