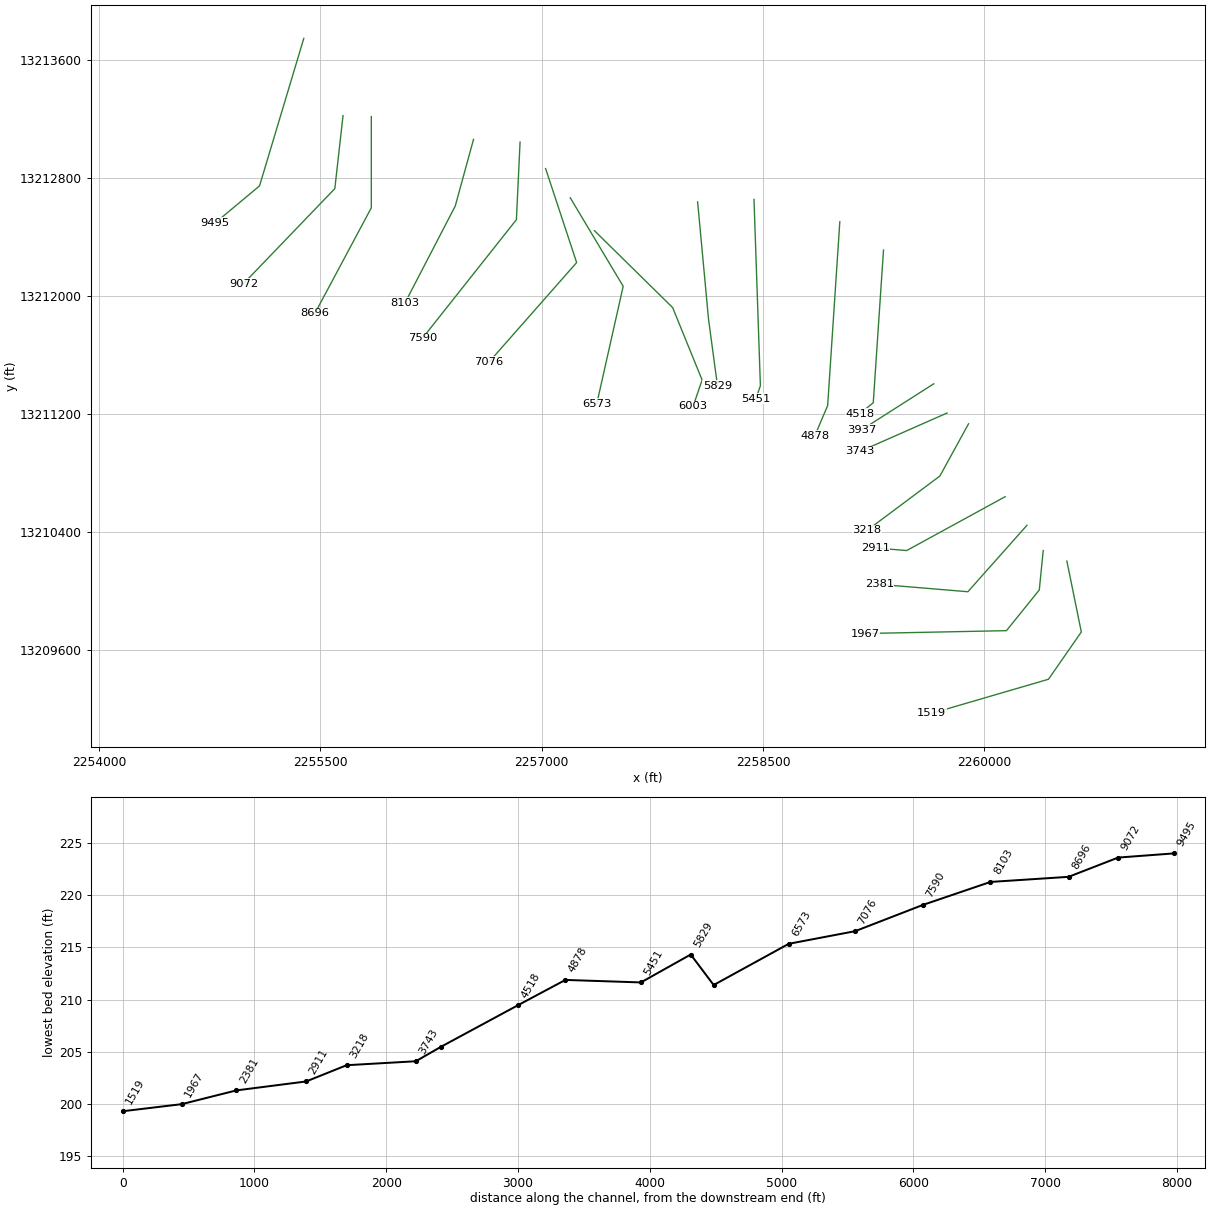
HEC-RAS study UNT 058 IN LACR.prj: UNT 058 IN LACR Base Level Engineering

--- UNT 058 IN LACR.g01 (geometry) --- (continued)

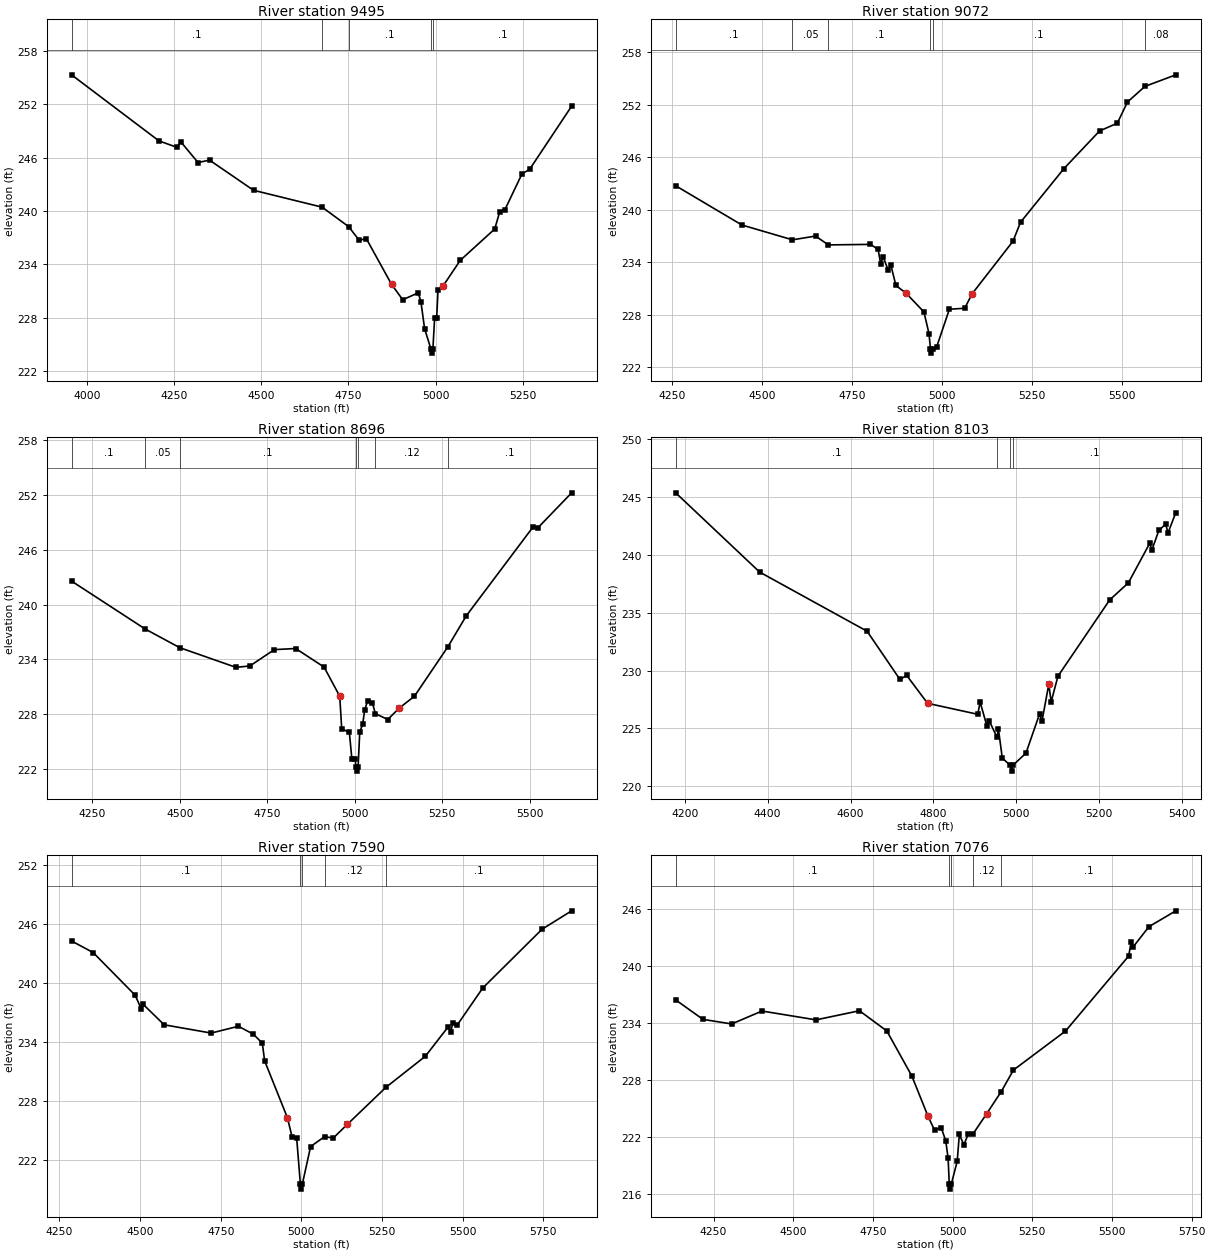
Type RM Length L Ch R = 1 ,9495    ,423,423,423
BEGIN DESCRIPTION:
UNT 058 IN LACR 16.0
END DESCRIPTION:
XS GIS Cut Line= 3
      2255387.71     13213746.83      2255087.72     13212746.85
      2254787.73     13212496.86
#Sta/Elev= 30
    3956  255.32  4206.5   247.9  4258.7  247.16  4269.2   247.8  4318.8  245.46
  4351.8  245.73    4478  242.34  4674.8  240.44  4750.9  238.25  4780.8  236.73
  4801.6   236.9  4873.8  231.77    4906  230.03  4950.4  230.81  4958.2  229.81
  4968.7  226.78  4986.6  224.53  4989.3  224.03  4992.6  224.53  4997.4  227.96
  5003.3  227.96  5007.2  231.12  5021.5  231.57  5070.9  234.46  5169.9  237.99
  5184.2  239.92  5198.5  240.11    5248  244.18  5270.1   244.7  5390.5   251.8
#Mann= 5 ,-1 , 0
    3956      .1       0  4674.8     .08       0  4750.9      .1       0
  4986.6     .07       0  4992.6      .1       0
Bank Sta=4873.8,5021.5
XS Rating Curve= 0 ,0
Exp/Cntr=0.3,0.1

Type RM Length L Ch R = 1 ,9072    ,376,376,376
BEGIN DESCRIPTION:
UNT 058 IN LACR 15.0
END DESCRIPTION:
XS GIS Cut Line= 3
      2255653.48     13213223.01      2255597.82     13212728.27
      2254979.48     13212085.19
#Sta/Elev= 30
  4260.6  242.73  4444.6  238.25  4585.2  236.56  4649.2  236.99    4685  235.98
    4802  236.04  4823.2  235.47  4830.1  233.84  4837.3   234.6  4851.5  233.07
  4858.4  233.72  4872.6  231.35  4900.9  230.47  4950.5  228.33  4964.7  225.84
  4968.6  224.13  4971.4  223.63  4974.6  224.13  4985.8  224.33  5021.3  228.64
  5063.8  228.75  5084.8  230.42    5198   236.4  5219.1  238.57  5339.5  244.68
  5438.6  248.98    5488  249.87  5516.3  252.29  5564.8  254.07  5650.6  255.39
#Mann= 6 ,-1 , 0
  4260.6      .1       0  4585.2     .05       0    4685      .1       0
  4968.6     .07       0  4974.6      .1       0  5564.8     .08       0
Bank Sta=4900.9,5084.8
XS Rating Curve= 0 ,0
Exp/Cntr=0.3,0.1

Type RM Length L Ch R = 1 ,8696    ,593,593,593
BEGIN DESCRIPTION:
UNT 058 IN LACR 14.0
END DESCRIPTION:
XS GIS Cut Line= 3
      2255845.17     13213216.82      2255845.17     13212598.41
      2255462.46     13211882.38
#Sta/Elev= 30
  4190.2  242.58    4401  237.33  4499.8  235.29  4660.2  233.14  4700.2  233.29
  4770.2  235.08  4831.2   235.2  4912.4  233.17  4957.2  229.98  4962.9  226.42
  4984.8  226.01  4991.8  223.16  5001.1  223.07  5003.8  222.28  5006.5  221.78
  5009.8  222.28  5014.5  226.05    5023  226.95  5028.7  228.51  5037.2  229.47
  5050.7  229.25  5059.2  228.07  5094.6  227.43  5127.1  228.67    5171  229.98
  5266.7   235.4    5319  238.77  5510.8  248.54  5524.7  248.44  5620.5  252.24
#Mann= 7 ,-1 , 0
  4190.2      .1       0    4401     .05       0  4499.8      .1       0
  5003.8     .07       0  5009.8      .1       0  5059.2     .12       0
  5266.7      .1       0
Bank Sta=4957.2,5127.1
XS Rating Curve= 0 ,0
Exp/Cntr=0.3,0.1

Type RM Length L Ch R = 1 ,8103    ,513,513,513
BEGIN DESCRIPTION:
UNT 058 IN LACR 13.0
END DESCRIPTION:
XS GIS Cut Line= 3
      2256537.74     13213062.18      2256414.07     13212610.78
      2256073.96      13211955.3
#Sta/Elev= 30
  4178.3  245.38  4380.8  238.52    4640   233.4  4719.2  229.23  4735.7  229.57
  4785.9  227.16    4907  226.21  4912.7  227.27  4929.1  225.19  4934.8  225.64
  4953.3  224.22  4956.9  224.93  4966.2  222.41  4985.7  221.79  4988.5  221.29
  4991.7  221.79  5023.3  222.85  5056.2  226.25  5061.9  225.61  5078.4  228.81
    5084  227.28  5100.5  229.51  5225.3  236.11  5270.4  237.59  5321.7     241
  5327.3  240.45  5343.8  242.12  5360.3  242.67    5366  241.91  5384.8  243.67
#Mann= 4 ,-1 , 0
  4178.3      .1       0  4953.3     .12       0  4985.7     .07       0
  4991.7      .1       0
Bank Sta=4785.9,5078.4
XS Rating Curve= 0 ,0
Exp/Cntr=0.3,0.1

Type RM Length L Ch R = 1 ,7590    ,514,514,514
BEGIN DESCRIPTION:
UNT 058 IN LACR 12.0
END DESCRIPTION:
XS GIS Cut Line= 3
      2256853.11     13213043.66      2256828.38     13212518.03
       2256192.1     13211714.96
#Sta/Elev= 30
  4287.4  244.25  4354.3  243.08  4484.4  238.76    4504  237.34    4509  237.84
  4574.5  235.75  4720.5  234.91  4804.8   235.6    4851   234.8  4878.9  233.89
  4886.2  232.09  4956.7  226.33  4971.1   224.4  4985.6  224.24    4997  219.58
  4999.7  219.08    5003  219.58  5028.8   223.4  5071.9   224.4  5099.3  224.27
  5142.6  225.65  5262.1   229.4  5384.6  232.56  5455.1  235.53  5463.1  234.98
  5469.5  235.91  5483.9  235.75  5562.5  239.48  5746.7  245.45  5838.2  247.31
#Mann= 5 ,-1 , 0
  4287.4      .1       0    4997     .07       0    5003      .1       0
  5071.9     .12       0  5262.1      .1       0
Bank Sta=4956.7,5142.6
XS Rating Curve= 0 ,0
Exp/Cntr=0.3,0.1

Type RM Length L Ch R = 1 ,7076    ,503,503,503
BEGIN DESCRIPTION:
UNT 058 IN LACR 11.0
END DESCRIPTION:
XS GIS Cut Line= 3
      2257026.26     13212864.29       2257236.5     13212227.39
      2256642.84     13211553.34
#Sta/Elev= 30
  4131.4  236.48    4217  234.43    4307  233.95  4402.2  235.31  4571.5  234.38
  4707.9  235.34  4793.7  233.21  4872.2  228.47  4922.5  224.27  4943.4  222.76
  4964.2  223.04  4978.5  221.65    4986   219.8  4989.7  217.06  4992.5  216.56
  4995.7  217.06  5014.5  219.49  5021.2  222.32  5035.4  221.23  5049.6  222.39
  5064.5  222.39  5106.5  224.48  5152.5  226.82    5191   229.1  5354.2   233.2
  5552.4   241.1    5560  242.55  5566.7  242.07    5616  244.19  5700.3  245.86
#Mann= 5 ,-1 , 0
  4131.4      .1       0  4989.7     .07       0  4995.7      .1       0
  5064.5     .12       0  5152.5      .1       0
Bank Sta=4922.5,5106.5
XS Rating Curve= 0 ,0
Exp/Cntr=0.3,0.1

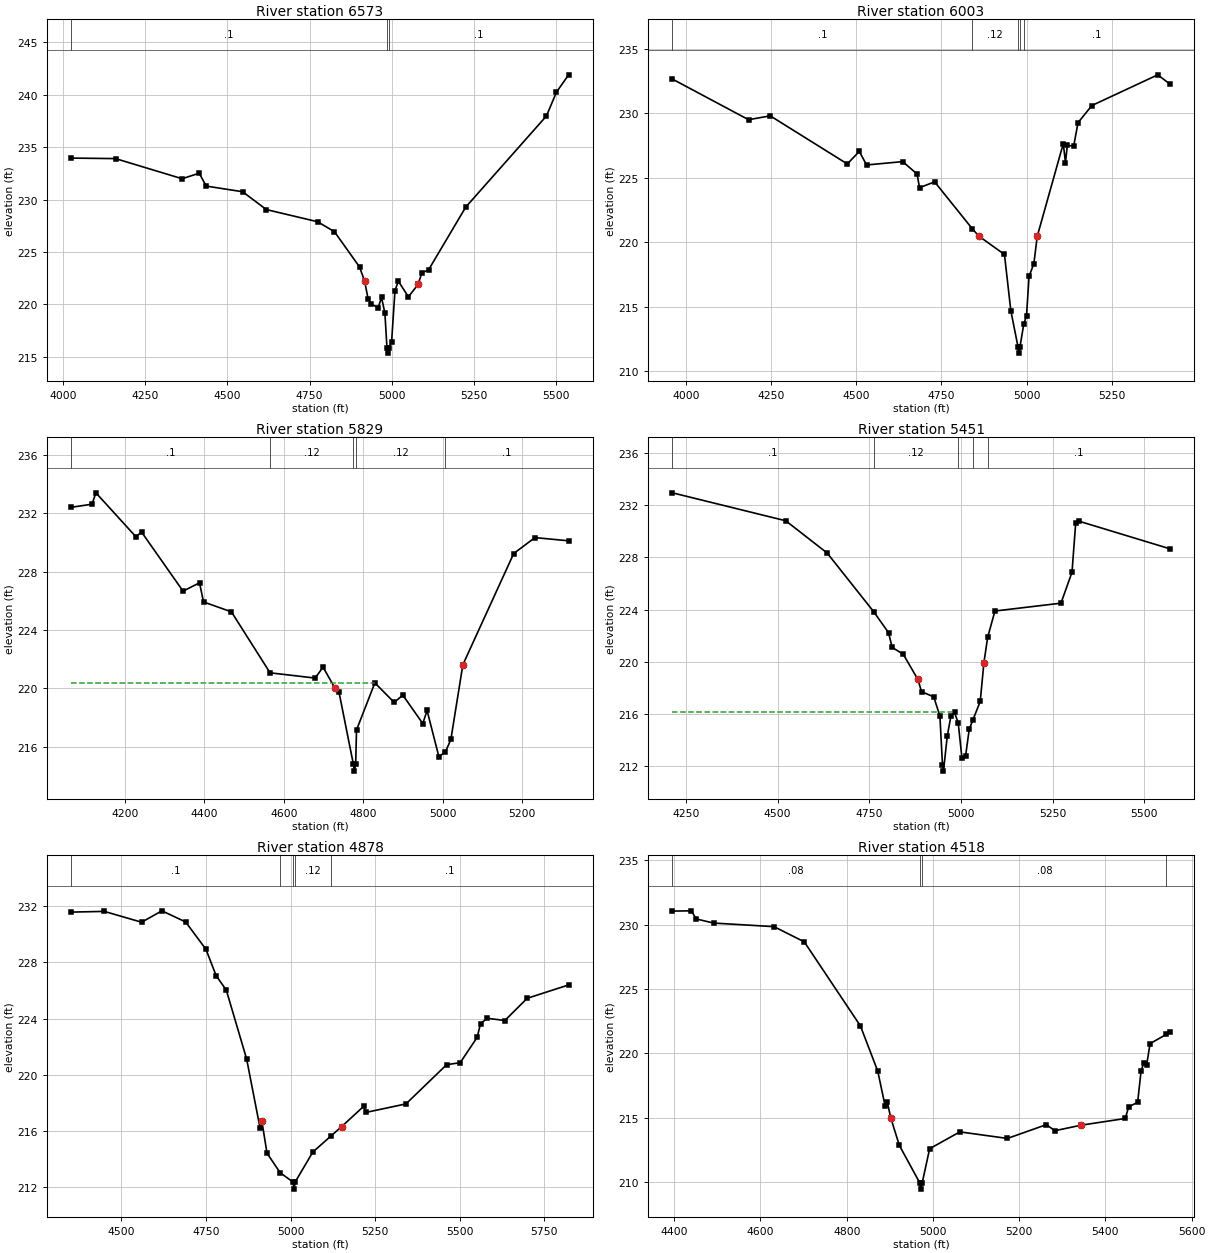
Type RM Length L Ch R = 1 ,6573    ,570,570,570
BEGIN DESCRIPTION:
Mapping XS 0142d78b
END DESCRIPTION:
XS GIS Cut Line= 3
       2257193.2     13212666.47      2257551.87     13212066.62
      2257372.96     13211270.78
#Sta/Elev= 30
  4024.6  233.95  4159.1   233.9    4362  231.98  4413.9  232.51  4435.3  231.28
  4546.2  230.74  4618.4  229.04  4774.5  227.88  4825.8  226.93  4902.3  223.57
    4918  222.19  4928.3  220.53  4938.5  220.01    4959  219.69  4969.3  220.66
  4979.5  219.18  4985.9  215.85  4988.7  215.35  4991.9  215.85    5000  216.45
  5010.2  221.31  5020.5  222.21  5051.2  220.72  5080.6   221.9  5092.2  223.01
  5112.7   223.3  5225.9  229.28  5471.5  237.96  5502.2  240.24  5539.2  241.89
#Mann= 3 ,-1 , 0
  4024.6      .1       0  4985.9     .07       0  4991.9      .1       0
Bank Sta=4918,5080.6
XS Rating Curve= 0 ,0
Exp/Cntr=0.3,0.1

Type RM Length L Ch R = 1 ,6003    ,174,174,174
BEGIN DESCRIPTION:
UNT 058 IN LACR 10.0
END DESCRIPTION:
XS GIS Cut Line= 4
      2257357.61     13212443.03      2257887.09     13211922.23
      2258086.74     13211431.78      2258025.96     13211253.78
#Sta/Elev= 30
    3960  232.64  4183.7  229.49  4247.3  229.79  4473.6  226.06  4508.9  227.03
  4530.2  225.98  4636.2  226.24  4678.6  225.28  4685.7  224.22  4730.1  224.67
  4840.9  221.03  4859.6  220.47  4935.2  219.04  4953.9  214.68  4974.9  211.89
  4977.7  211.39  4980.9  211.89    4992  213.66    5000  214.28  5007.4  217.34
  5021.6  218.33  5031.4  220.44    5108  227.64  5114.4  226.16  5119.8   227.5
  5138.5  227.44  5151.2  229.26    5192  230.59  5385.4  232.97  5420.3  232.27
#Mann= 5 ,-1 , 0
    3960      .1       0  4840.9     .12       0  4974.9     .07       0
  4980.9     .12       0    4992      .1       0
Bank Sta=4859.6,5031.4
XS Rating Curve= 0 ,0
Exp/Cntr=0.3,0.1

Type RM Length L Ch R = 1 ,5829    ,378,378,378
BEGIN DESCRIPTION:
Mapping XS ba2e9e87
END DESCRIPTION:
XS GIS Cut Line= 3
      2258056.35     13212638.39      2258130.14      13211844.1
      2258190.91     13211392.69
#Sta/Elev= 30
  4064.6  232.41  4116.4  232.62  4126.4   233.4  4226.8   230.4  4241.7   230.7
    4346  226.66  4387.5  227.23  4397.6  225.92  4467.9  225.24  4565.3  221.06
  4678.9   220.7  4698.9  221.45    4729     220    4739  219.74  4775.1  214.82
  4777.9  214.32  4781.1  214.82  4783.2  217.14  4829.4  220.37  4878.2  219.03
  4899.9  219.53  4950.3  217.58    4961  218.48  4990.7  215.32  5007.2  215.63
    5021  216.49  5051.2  221.61  5179.4  229.24  5232.9  230.33  5317.8  230.11
#Mann= 5 ,-1 , 0
  4064.6      .1       0  4565.3     .12       0  4775.1     .07       0
  4781.1     .12       0  5007.2      .1       0
#XS Ineff= 2 , 0
         4828.86  220.39
Permanent Ineff=
       F       F
Bank Sta=4729,5051.2
XS Rating Curve= 0 ,0
Exp/Cntr=0.3,0.1

Type RM Length L Ch R = 1 ,5451    ,573,573,573
BEGIN DESCRIPTION:
Mapping XS 53a2b6db
END DESCRIPTION:
XS GIS Cut Line= 3
       2258438.3     13212655.78       2258481.7     13211392.71
      2258451.32     13211305.89
#Sta/Elev= 30
  4213.2  232.95  4522.3  230.81  4635.2  228.34  4763.1  223.81  4802.5  222.24
  4812.5  221.11  4842.5   220.6  4882.5  218.66  4892.5  217.73  4925.9  217.32
  4942.6  215.85  4949.6  212.14  4952.3  211.64  4962.6  214.31  4972.6  215.85
  4982.6  216.13  4992.6  215.31  5002.6  212.66  5012.6   212.8  5022.6  214.85
  5032.6  215.56  5052.6  216.98  5062.6  219.95  5072.8  221.88  5092.6   223.9
  5272.7   224.5  5302.8  226.87  5312.8  230.62  5322.8  230.77    5569  228.67
#Mann= 5 ,-1 , 0
  4213.2      .1       0  4763.1     .12       0  4992.6     .07       0
  5032.6     .12       0  5072.8      .1       0
#XS Ineff= 2 , 0
         4981.93  216.13
Permanent Ineff=
       F       F
Bank Sta=4882.5,5062.6
XS Rating Curve= 0 ,0
Exp/Cntr=0.3,0.1

Type RM Length L Ch R = 1 ,4878    ,360,360,360
BEGIN DESCRIPTION:
Mapping XS e612f52a
END DESCRIPTION:
XS GIS Cut Line= 3
       2259019.9     13212503.85      2258937.43     13211258.16
      2258850.63     13211054.18
#Sta/Elev= 30
  4352.2  231.58  4449.4  231.63  4559.7  230.86  4619.8  231.67  4689.9  230.88
  4750.1  228.93  4780.1  227.06  4810.2  226.03  4870.3  221.13  4910.2   216.2
  4915.2  216.74  4930.5  214.44  4969.3  213.05  5007.6  212.38  5010.4  211.88
  5013.6  212.38  5066.1  214.52  5119.7  215.66  5150.9  216.32  5216.9  217.78
    5222  217.33  5341.4  217.94  5461.6  220.73  5501.7  220.87  5551.8  222.67
  5561.8  223.65  5581.9  224.03  5633.7  223.87  5699.8  225.45  5822.3   226.4
#Mann= 5 ,-1 , 0
  4352.2      .1       0  4969.3     .12       0  5007.6     .07       0
  5013.6     .12       0  5119.7      .1       0
Bank Sta=4915.2,5150.9
XS Rating Curve= 0 ,0
Exp/Cntr=0.3,0.1

Type RM Length L Ch R = 1 ,4518    ,581,581,581
BEGIN DESCRIPTION:
UNT 058 IN LACR 9.0
END DESCRIPTION:
XS GIS Cut Line= 3
       2259315.9     13212311.97      2259246.46     13211277.26
      2259156.17     13211204.34
#Sta/Elev= 30
  4395.8  231.06  4439.7  231.08    4451  230.45  4491.1  230.13  4631.4  229.85
  4701.6  228.67  4831.9  222.13    4872  218.62  4889.2   215.9  4894.2  216.22
  4902.1  214.99  4922.1  212.85  4969.2  209.95    4972  209.45  4975.2  209.95
  4992.3  212.59  5062.4   213.9  5172.7  213.39  5262.9  214.46  5282.9  213.99
  5343.7  214.42    5446  214.94  5453.9  215.84  5474.7   216.2  5482.6  218.61
  5489.1  219.28  5495.6  219.09  5503.5  220.76  5541.5  221.48  5548.9  221.69
#Mann= 4 ,-1 , 0
  4395.8     .08       0  4969.2     .07       0  4975.2     .08       0
  5541.5      .1       0
Bank Sta=4902.1,5343.7
XS Rating Curve= 0 ,0
Exp/Cntr=0.3,0.1

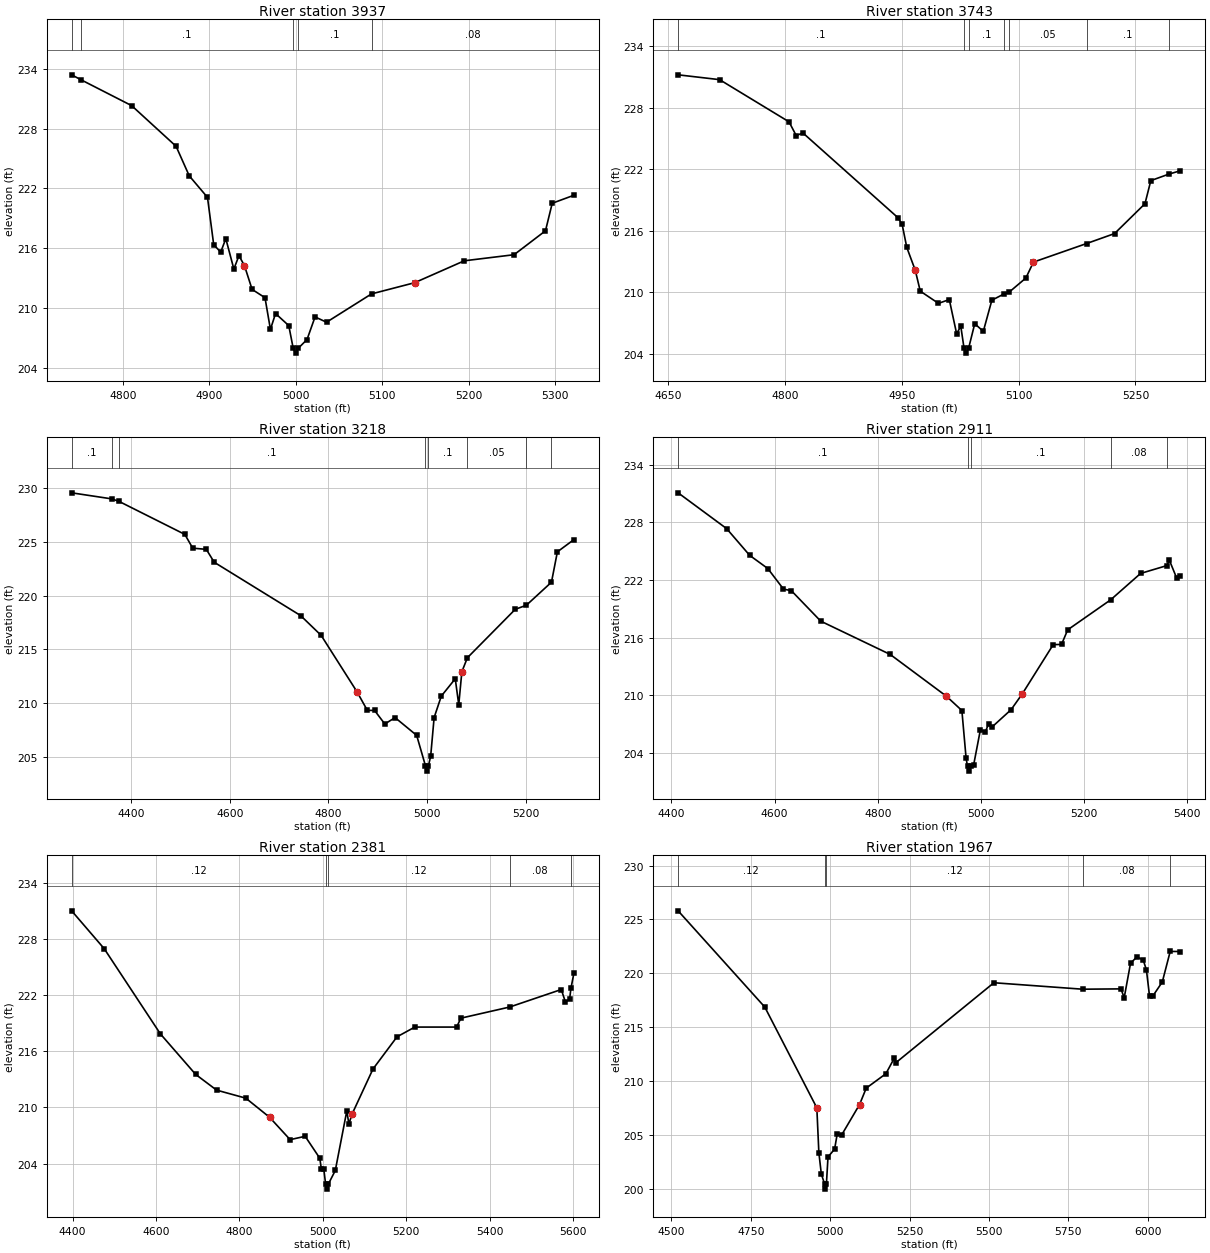
Type RM Length L Ch R = 1 ,3937    ,194,194,194
BEGIN DESCRIPTION:
Mapping XS 8b34b2b6
END DESCRIPTION:
XS GIS Cut Line= 2
      2259656.21     13211405.75      2259166.64     13211093.26
#Sta/Elev= 30
  4740.8  233.39  4751.7  232.89  4810.2   230.3  4861.6  226.22  4876.8  223.26
  4897.9   221.1  4905.1  216.35  4913.2  215.61  4919.1  216.96  4928.4  213.91
  4934.3  215.26  4940.7  214.24  4949.5  211.87  4964.4  211.04  4970.7  207.86
  4976.6  209.45  4991.9  208.24    4997  205.98  4999.8  205.48    5003  205.98
    5013  206.84  5022.3  209.11  5035.6  208.58  5087.6  211.42  5137.4  212.54
  5194.9  214.74  5252.5  215.35  5288.8  217.75  5296.6  220.51  5321.6  221.31
#Mann= 5 ,-1 , 0
  4740.8     .05       0  4751.7      .1       0    4997     .07       0
    5003      .1       0  5087.6     .08       0
Bank Sta=4940.7,5137.4
XS Rating Curve= 0 ,0
Exp/Cntr=0.3,0.1

Type RM Length L Ch R = 1 ,3743    ,525,525,525
BEGIN DESCRIPTION:
UNT 058 IN LACR 8.0
END DESCRIPTION:
XS GIS Cut Line= 2
      2259746.51     13211207.84       2259156.2     13210947.41
#Sta/Elev= 30
  4662.5  231.19  4715.8  230.72    4805  226.61  4814.2  225.27  4822.8  225.53
  4944.9  217.27  4950.3  216.62  4956.3  214.37  4967.2  212.14  4973.6  210.11
    4997  208.92  5010.9  209.29  5020.3  205.97  5025.7  206.68  5029.8  204.57
  5032.5  204.07  5035.8  204.57  5043.6  206.94  5054.6  206.19  5065.6  209.23
  5081.3  209.84  5087.6     210  5109.3  211.39    5119  212.94  5187.3  214.75
  5223.2  215.72  5262.3  218.63  5269.8  220.88  5293.2  221.52  5307.7  221.84
#Mann= 7 ,-1 , 0
  4662.5      .1       0  5029.8     .07       0  5035.8      .1       0
  5081.3     .08       0  5087.6     .05       0  5187.3      .1       0
  5293.2     .08       0
Bank Sta=4967.2,5119
XS Rating Curve= 0 ,0
Exp/Cntr=0.3,0.1

Type RM Length L Ch R = 1 ,3218    ,307,307,307
BEGIN DESCRIPTION:
UNT 058 IN LACR 7.0
END DESCRIPTION:
XS GIS Cut Line= 3
       2259892.3     13211134.91      2259697.85     13210780.73
      2259204.82     13210412.69
#Sta/Elev= 30
  4278.7  229.54  4359.8  228.98  4374.6  228.75  4508.4  225.68  4524.5   224.4
    4552  224.29  4568.1  223.09  4743.4  218.14  4785.1   216.3  4857.6  211.08
  4878.9  209.33  4893.5  209.33  4914.3  208.07  4935.2  208.66    4979  207.01
  4996.8  204.19  4999.6  203.69  5002.8  204.19  5007.4  205.07  5014.4  208.66
    5029  210.66  5057.3  212.27  5064.4  209.86  5070.7  212.92  5081.9  214.22
  5179.1  218.72  5201.7   219.1  5252.6  221.24  5264.6  224.06    5298  225.19
#Mann= 8 ,-1 , 0
  4278.7      .1       0  4359.8     .05       0  4374.6      .1       0
  4996.8     .07       0  5002.8      .1       0  5081.9     .05       0
  5201.7     .08       0  5252.6      .1       0
Bank Sta=4857.6,5070.7
XS Rating Curve= 0 ,0
Exp/Cntr=0.3,0.1

Type RM Length L Ch R = 1 ,2911    ,530,530,530
BEGIN DESCRIPTION:
UNT 058 IN LACR 6.0
END DESCRIPTION:
XS GIS Cut Line= 3
      2260140.21     13210640.72      2259472.82     13210275.89
      2259260.96     13210293.54
#Sta/Elev= 30
  4413.2  231.06  4507.2  227.34  4551.9  224.56    4587  223.19  4617.4  221.05
  4632.6  220.89  4689.6  217.72  4824.2  214.26  4933.3  209.91  4963.1  208.43
  4971.3  203.47    4974  202.63  4976.7  202.13    4980  202.63  4985.9  202.77
  4998.8  206.38  5008.7  206.22  5014.9  207.05  5020.6  206.67  5058.5  208.52
  5080.4  210.18  5140.1  215.28  5156.2   215.3  5168.2  216.82  5251.5  219.94
  5309.4  222.68    5360  223.49  5365.3  224.04  5379.6  222.17  5386.4  222.41
#Mann= 5 ,-1 , 0
  4413.2      .1       0    4974     .07       0    4980      .1       0
  5251.5     .08       0    5360      .1       0
Bank Sta=4933.3,5080.4
XS Rating Curve= 0 ,0
Exp/Cntr=0.3,0.1

Type RM Length L Ch R = 1 ,2381    ,414,414,414
BEGIN DESCRIPTION:
UNT 058 IN LACR 5.0
END DESCRIPTION:
XS GIS Cut Line= 3
      2260287.73     13210446.87      2259887.72     13209996.85
       2259287.7     13210046.86
#Sta/Elev= 30
  4397.9  230.98  4476.1  226.93  4610.7  217.84  4695.2  213.52  4745.4  211.84
  4815.6  210.98  4872.5  208.94  4921.8  206.55  4957.8  206.91  4992.9  204.57
  4996.7  203.41  5002.5  203.41    5007  201.77  5009.8  201.27    5013  201.77
  5030.1  203.26  5057.7  209.62  5062.7  208.22  5070.2  209.27  5120.4  214.09
  5178.1  217.53  5220.8  218.57  5321.1  218.57  5331.1  219.52  5448.2  220.71
    5572  222.58    5582  221.23    5592  221.57  5595.2  222.72  5602.1  224.29
#Mann= 5 ,-1 , 0
  4397.9     .12       0    5007     .07       0    5013     .12       0
  5448.2     .08       0  5595.2      .1       0
Bank Sta=4872.5,5070.2
XS Rating Curve= 0 ,0
Exp/Cntr=0.3,0.1

Type RM Length L Ch R = 1 ,1967    ,448,448,448
BEGIN DESCRIPTION:
UNT 058 IN LACR 4.0
END DESCRIPTION:
XS GIS Cut Line= 4
       2260398.3     13210275.93       2260371.6     13210008.92
      2260149.13     13209733.06      2259191.05     13209713.75
#Sta/Elev= 30
  4521.2   225.8  4794.1  216.86  4957.9   207.5  4964.3  203.33    4972  201.36
  4982.1  200.45  4984.9  199.95  4988.1  200.45  4993.1  202.94  5013.9  203.67
  5021.9  205.05  5036.2  204.99  5092.3   207.8  5113.4  209.33  5175.3  210.67
    5202  212.13    5207   211.7  5515.4  219.12  5794.4  218.52  5915.5  218.55
  5925.5  217.72  5945.5  220.93  5965.5  221.52  5985.5  221.23  5995.5  220.31
  6005.5  217.85  6015.5  217.88  6045.5  219.19  6070.4  222.03  6102.2  222.02
#Mann= 5 ,-1 , 0
  4521.2     .12       0  4982.1     .07       0  4988.1     .12       0
  5794.4     .08       0  6070.4      .1       0
Bank Sta=4957.9,5092.3
XS Rating Curve= 0 ,0
Exp/Cntr=0.3,0.1

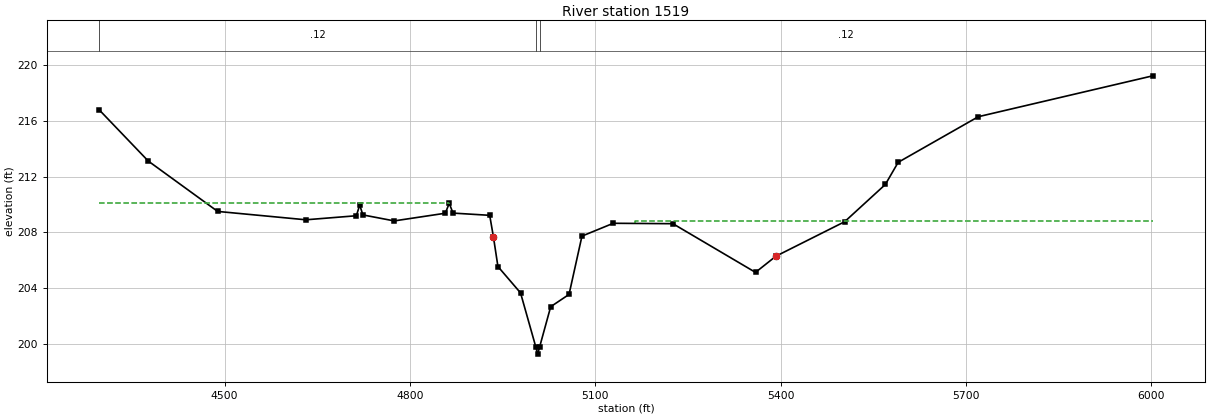
Type RM Length L Ch R = 1 ,1519    ,635,635,635
BEGIN DESCRIPTION:
UNT 058 IN LACR 3.0
END DESCRIPTION:
XS GIS Cut Line= 4
      2260558.49     13210204.65      2260656.36     13209724.16
      2260433.89      13209403.8      2259642.27     13209172.54
#Sta/Elev= 30
    4297  216.78  4376.4  213.11  4488.7   209.5  4631.5   208.9  4713.2  209.19
  4718.6  209.96  4723.7  209.25  4774.4  208.82  4857.1  209.37  4863.5  210.08
  4869.6  209.38    4929  209.22  4935.1  207.65  4942.3  205.55  4978.9  203.66
  5003.7  199.77  5006.5  199.27  5009.7  199.77  5027.7  202.67  5057.4  203.55
  5078.3  207.73    5129  208.65  5225.5  208.62  5359.2  205.13  5392.2  206.29
  5503.4  208.76  5569.3  211.43  5590.1  213.02  5719.8  216.29  6002.1  219.22
#Mann= 3 ,-1 , 0
    4297     .12       0  5003.7     .07       0  5009.7     .12       0
#XS Ineff= 2 , 0
         4863.64  210.08 5163.64          208.83
Permanent Ineff=
       F       F
Bank Sta=4935.1,5392.2
XS Rating Curve= 0 ,0
Exp/Cntr=0.3,0.1