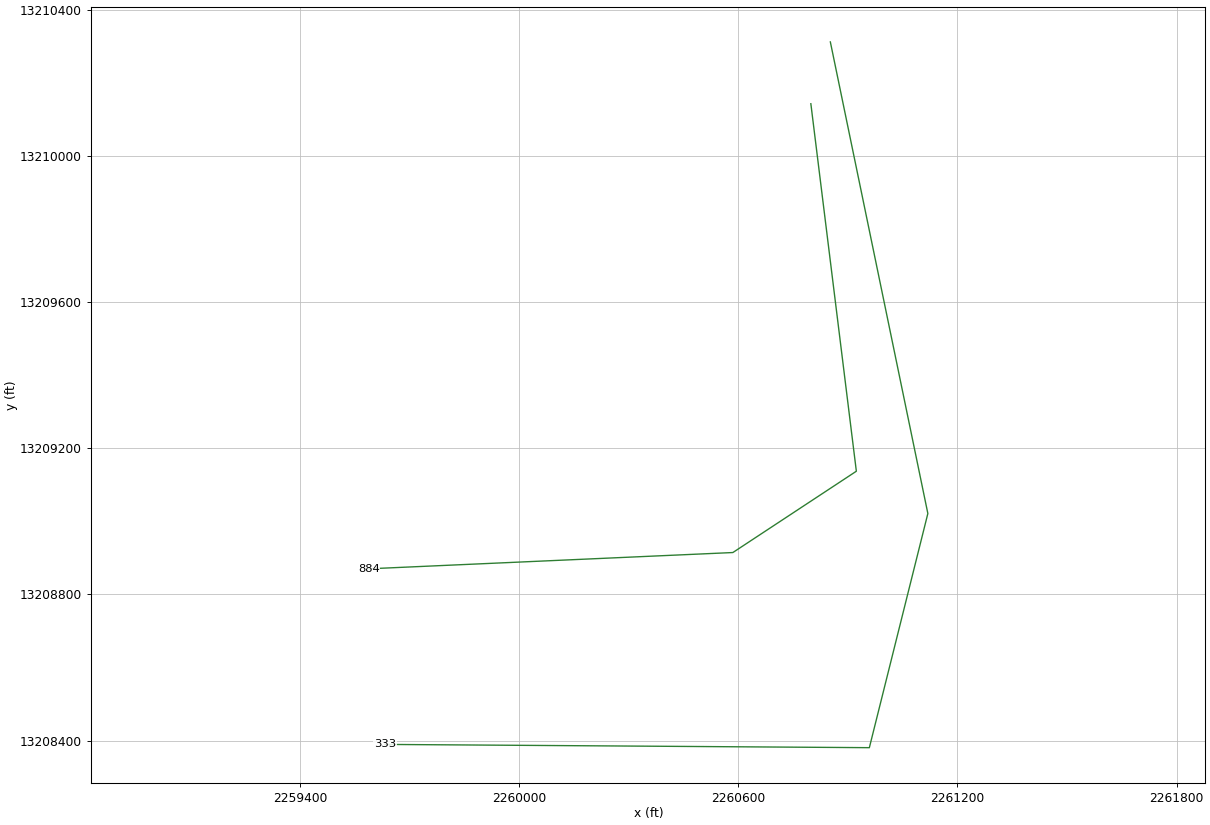
HEC-RAS study UNT 058 IN LACR.prj: UNT 058 IN LACR Base Level Engineering

--- UNT 058 IN LACR.g01 (geometry) --- (continued)

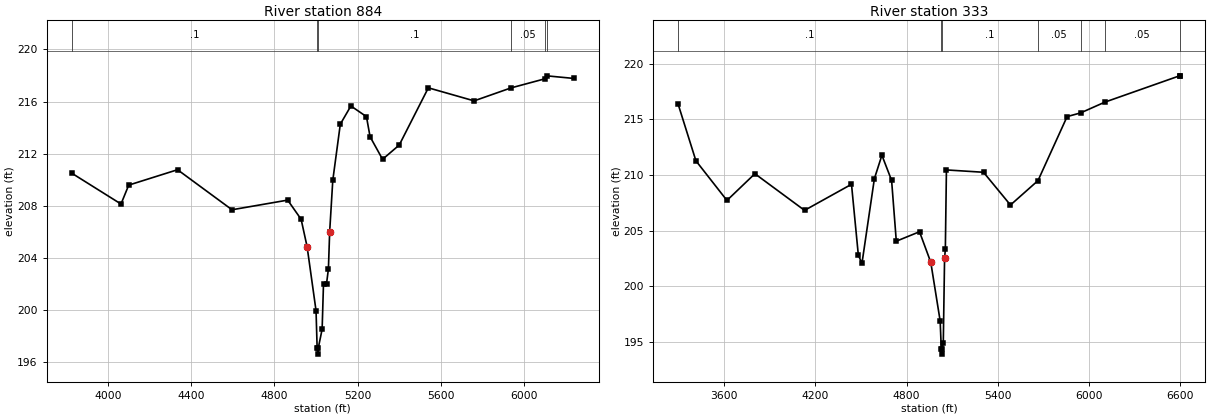
Type RM Length L Ch R = 1 ,884     ,551,551,551
BEGIN DESCRIPTION:
UNT 058 IN LACR 2.0
END DESCRIPTION:
XS GIS Cut Line= 4
      2260798.74     13210142.43      2260923.33     13209136.84
      2260585.17     13208914.37      2259588.52     13208869.87
#Sta/Elev= 30
  3824.4  210.52  4061.8  208.15  4098.9   209.6  4333.8  210.78  4595.8  207.71
  4863.6  208.45  4928.2  206.98    4957  204.88    5000  199.97  5005.2  197.14
    5008  196.64  5011.2  197.14  5029.3  198.55  5035.9  202.05  5050.4  202.03
  5059.5  203.17  5065.5  206.01  5080.5  209.96  5116.7  214.27  5167.6  215.67
  5242.5  214.85  5259.9  213.31    5320  211.58  5400.1  212.67  5540.2  217.06
  5760.4  216.06  5937.1  217.05  6100.4  217.75  6109.5  217.98  6240.1  217.78
#Mann= 6 ,-1 , 0
  3824.4      .1       0  5005.2     .07       0  5011.2      .1       0
  5937.1     .05       0  6100.4      .1       0  6109.5     .08       0
Bank Sta=4957,5065.5
XS Rating Curve= 0 ,0
Exp/Cntr=0.3,0.1

Type RM Length L Ch R = 1 ,333     ,0,0,0
BEGIN DESCRIPTION:
UNT 058 IN LACR 1.0
END DESCRIPTION:
XS GIS Cut Line= 4
      2260852.13     13210311.51       2261119.1     13209021.15
      2260958.92     13208380.44      2259632.97     13208389.34
#Sta/Elev= 30
  3296.5  216.36  3413.6  211.27  3617.8  207.71  3801.6  210.11  4128.4  206.82
  4437.2  209.16  4482.3  202.79  4506.2  202.07  4587.9  209.67  4637.3  211.77
  4701.1  209.51    4732  204.05  4884.7   204.9  4958.8  202.16  5020.6  196.89
  5027.9  194.41  5030.7  193.91  5033.9  194.41  5041.2  194.93  5049.6  202.51
  5054.7  203.33  5061.8  210.45  5305.8  210.24  5483.1   207.3  5664.2  209.49
  5855.8  215.24  5944.5  215.57  6104.6  216.54  6595.5   218.9  6600.6   218.9
#Mann= 7 ,-1 , 0
  3296.5      .1       0  5027.9     .07       0  5033.9      .1       0
  5664.2     .05       0  5944.5      .1       0  6104.6     .05       0
  6595.5      .1       0
Bank Sta=4958.8,5049.6
XS Rating Curve= 0 ,0
Exp/Cntr=0.3,0.1

Chan Stop Cuts=-1
Use User Specified Reach Order=0
Composite Channel Slope=5