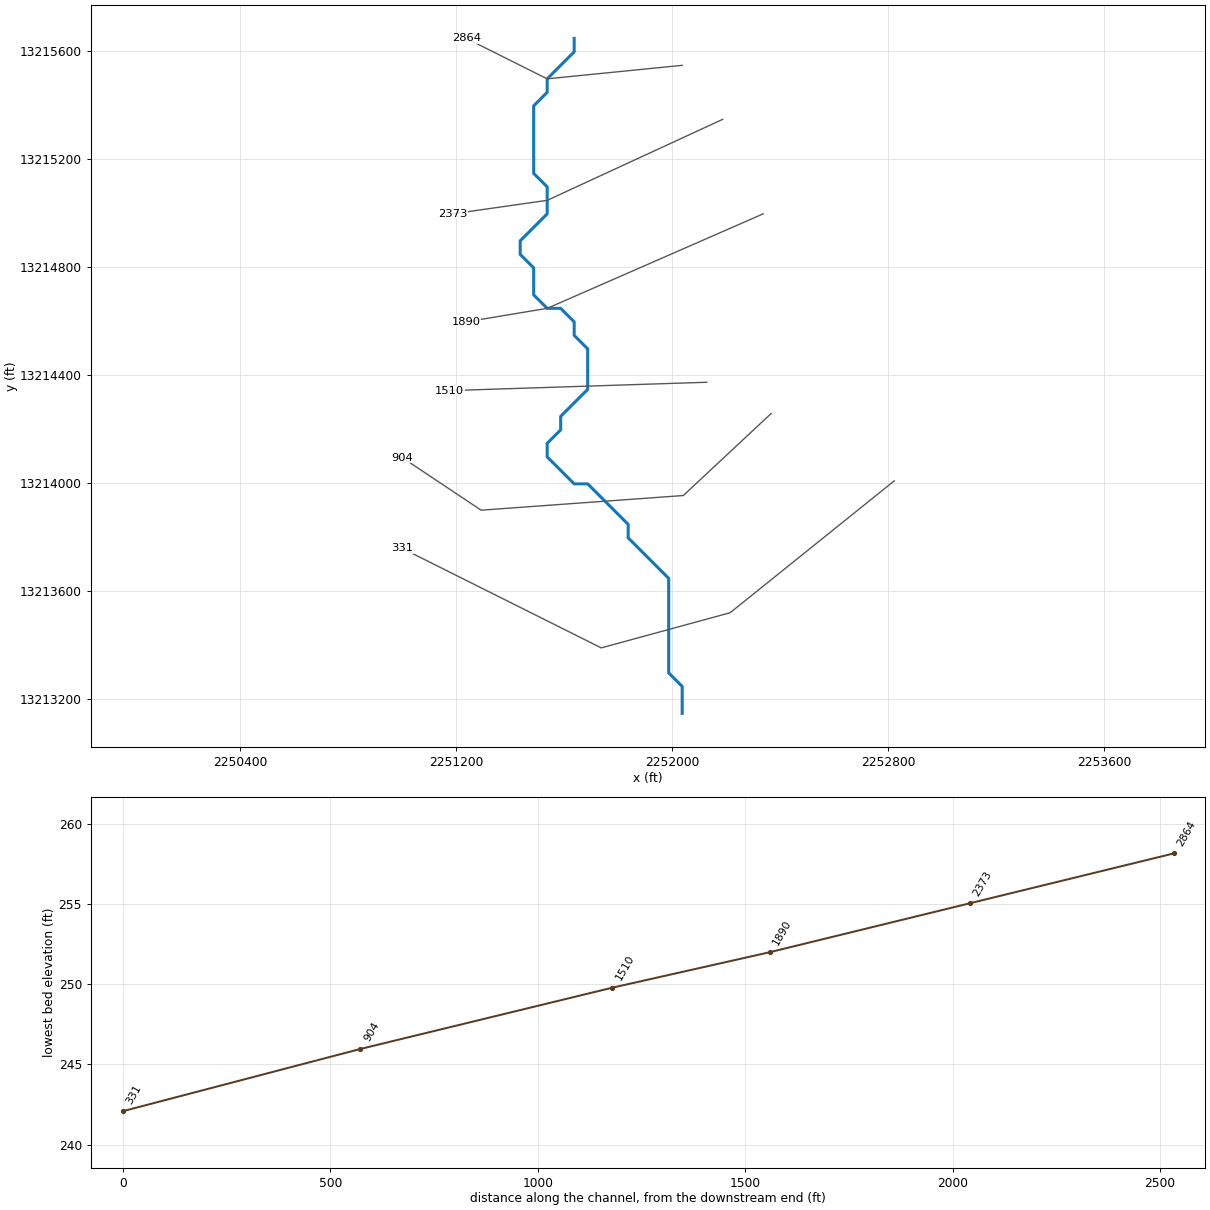
--- UNT 059 IN LACR.prj (project) ---

Proj Title=UNT 059 IN LACR Base Level Engineering
Current Plan=p01
Default Exp/Contr=0.3,0.1
English Units
Geom File=g01
Flow File=f01
Plan File=p01
BEGIN DESCRIPTION:
UNT 059 IN LACR
END DESCRIPTION:

--- UNT 059 IN LACR.p01 (plan) ---

Plan Title=Multiple Run
Short Identifier=Multiple
Geom File=g01
Flow File=f01
Subcritical Flow
K Sum by GR= 0
Std Step Tol= 0.01
Critical Tol= 0.01
Num of Std Step Trials= 20
Max Error Tol= 0.3
Flow Tol Ratio= 0.001
Split Flow NTrial= 30
Split Flow Tol= 0.02
Split Flow Ratio= 0.02
Log Output Level= 0
Friction Slope Method= 1
Unsteady Friction Slope Method= 2
Unsteady Bridges Friction Slope Method= 1
Parabolic Critical Depth
Global Vel Dist=  1 , 1 , 1
Global Log Level= 0
CheckData=True
Encroach Param= -1, 0, 0, 0
BEGIN DESCRIPTION:
Multiple Run
END DESCRIPTION:

--- UNT 059 IN LACR.f01 (steady flow) ---

Flow Title=Multiple
Number of Profiles=7
Profile Names=10-year,25-year,50-year,1pct_min,100-year,1pct_plu,500-year
River Rch & RM= UNT 059 IN LACR,Reach-1,2864
     220     305     376     342     462     625     708
River Rch & RM= UNT 059 IN LACR,Reach-1,2373
     228     317     391     355     481     650     736
Boundary for River Rch & Prof#=UNT 059 IN LACR,Reach-1,1
Up Type=0
Dn Type=3
Dn Slope=0.005
Boundary for River Rch & Prof#=UNT 059 IN LACR,Reach-1,2
Up Type=0
Dn Type=3
Dn Slope=0.005
Boundary for River Rch & Prof#=UNT 059 IN LACR,Reach-1,3
Up Type=0
Dn Type=3
Dn Slope=0.005
Boundary for River Rch & Prof#=UNT 059 IN LACR,Reach-1,4
Up Type=0
Dn Type=3
Dn Slope=0.005
Boundary for River Rch & Prof#=UNT 059 IN LACR,Reach-1,5
Up Type=0
Dn Type=3
Dn Slope=0.005
Boundary for River Rch & Prof#=UNT 059 IN LACR,Reach-1,6
Up Type=0
Dn Type=3
Dn Slope=0.005
Boundary for River Rch & Prof#=UNT 059 IN LACR,Reach-1,7
Up Type=0
Dn Type=3
Dn Slope=0.005

--- UNT 059 IN LACR.g01 (geometry) ---

Geom Title=Existing Conditions

River Reach=UNT 059 IN LACR,Reach-1
Reach XY= 30
      2251637.72     13215646.85      2251637.72     13215596.86
      2251537.72     13215496.85      2251537.72     13215446.86
      2251487.72     13215396.85      2251487.72     13215146.85
      2251537.72     13215096.85      2251537.72     13214996.85
      2251437.72     13214896.85      2251437.72     13214846.85
      2251487.72     13214796.86      2251487.72     13214696.85
      2251537.72     13214646.85      2251587.72     13214646.85
      2251637.72     13214596.85      2251637.72     13214546.85
      2251687.72     13214496.85      2251687.72     13214346.85
      2251587.72     13214246.85      2251587.72     13214196.85
      2251537.72     13214146.86      2251537.72     13214096.85
      2251637.72     13213996.85      2251687.72     13213996.85
      2251837.72     13213846.85      2251837.72     13213796.86
      2251987.72     13213646.86      2251987.72     13213296.86
      2252037.72     13213246.85      2252037.72     13213146.86

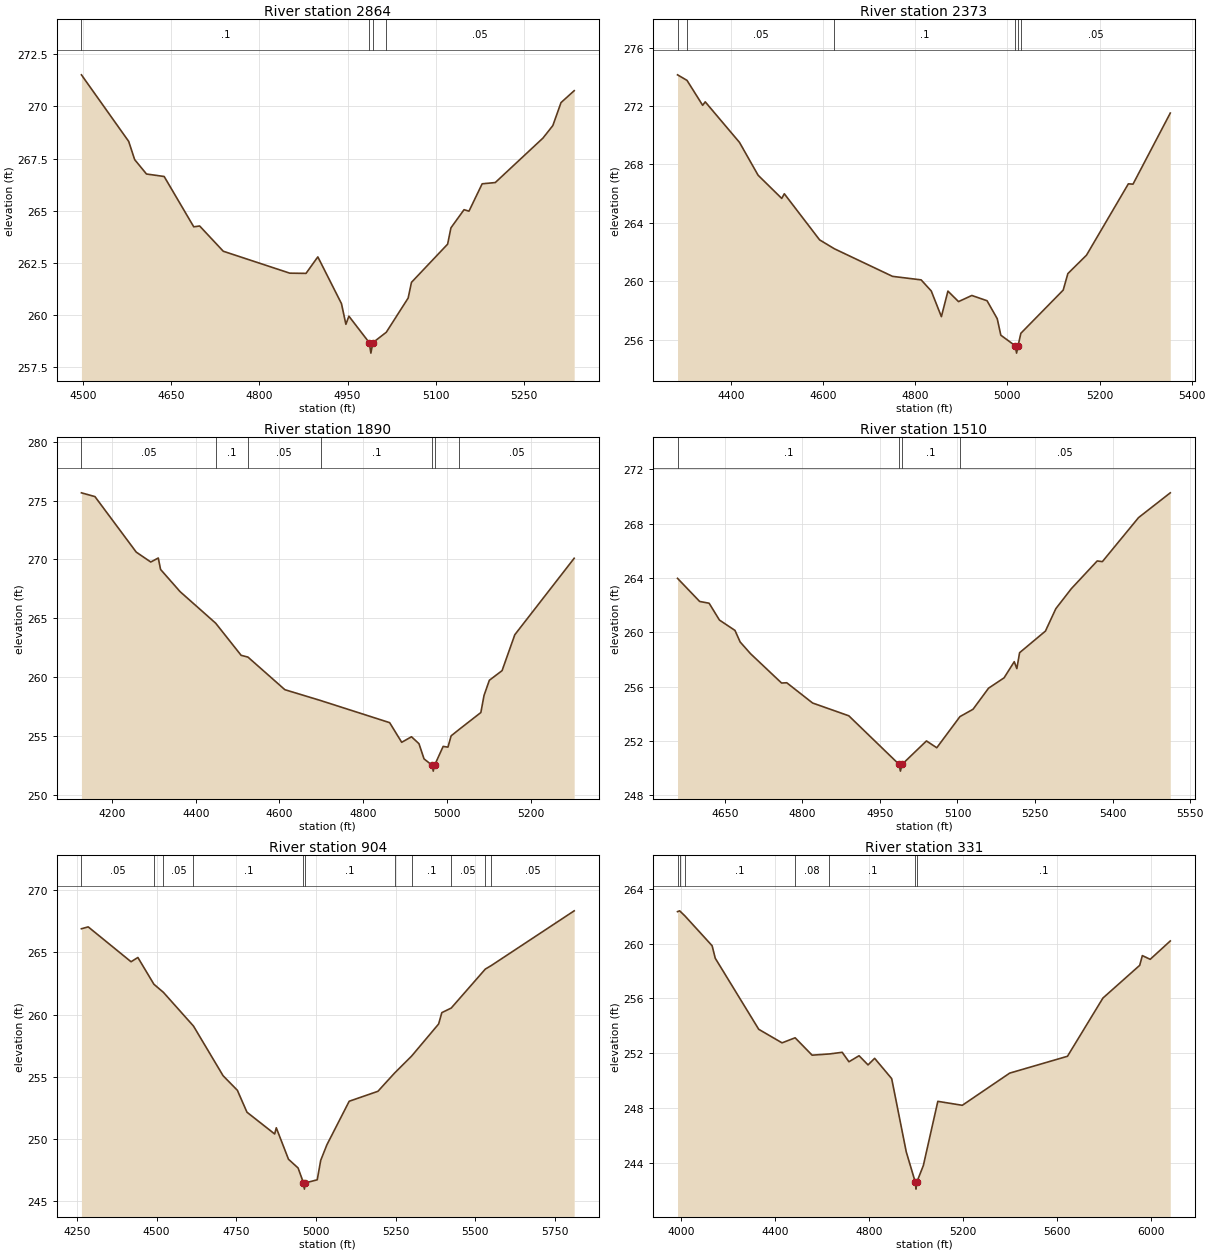
Type RM Length L Ch R = 1,2864,491,491,491
BEGIN DESCRIPTION:
UNT 059 IN LACR 5.0
END DESCRIPTION:
XS GIS Cut Line= 3
      2252037.73     13215546.86      2251537.72     13215496.85
      2251237.73     13215646.85
#Sta/Elev= 30
  4497.5  271.51  4577.9  268.32  4588.0  267.45  4608.1  266.76  4638.2  266.64
  4688.5  264.23  4698.5  264.27  4738.7  263.06  4851.8  262.01  4879.4  262.00
  4899.5  262.79  4939.7  260.55  4947.2  259.56  4952.3  259.95  4987.0  258.68
  4989.7  258.18  4993.0  258.68  5015.9  259.18  5053.1  260.82  5058.7  261.57
  5120.2  263.40  5125.8  264.18  5148.1  265.05  5156.5  264.98  5178.9  266.29
  5201.2  266.35  5282.3  268.48  5299.1  269.08  5313.0  270.18  5335.4  270.75
#Mann=4,-1,0
  4497.5     0.1       0  4987.0    0.07       0  4993.0     0.1       0
  5015.9    0.05       0
Bank Sta=4987,4993
Exp/Cntr=0.3,0.1

Type RM Length L Ch R = 1,2373,483,483,483
BEGIN DESCRIPTION:
UNT 059 IN LACR 4.0
END DESCRIPTION:
XS GIS Cut Line= 3
      2252187.73     13215346.86      2251537.72     13215046.85
      2251187.67     13214996.85
#Sta/Elev= 30
  4284.1  274.14  4304.7  273.76  4338.7  272.05  4344.2  272.29  4418.6  269.51
  4459.0  267.26  4510.3  265.67  4515.9  265.99  4592.5  262.83  4624.6  262.22
  4750.8  260.33  4812.8  260.09  4834.8  259.33  4856.8  257.57  4871.0  259.32
  4894.0  258.60  4922.9  259.02  4955.9  258.66  4978.0  257.43  4985.8  256.30
  5017.2  255.57  5020.0  255.07  5023.2  255.57  5029.3  256.43  5121.2  259.39
  5131.3  260.52  5171.7  261.78  5262.6  266.67  5272.7  266.65  5353.6  271.52
#Mann=6,-1,0
  4284.1     0.1       0  4304.7    0.05       0  4624.6     0.1       0
  5017.2    0.07       0  5023.2     0.1       0  5029.3    0.05       0
Bank Sta=5017.2,5023.2
Exp/Cntr=0.3,0.1

Type RM Length L Ch R = 1,1890,380,380,380
BEGIN DESCRIPTION:
UNT 059 IN LACR 3.0
END DESCRIPTION:
XS GIS Cut Line= 3
      2252337.71     13214996.85      2251537.72     13214646.85
      2251237.76     13214596.86
#Sta/Elev= 30
  4126.8  275.66  4159.1  275.34  4257.8  270.62  4292.5  269.78  4310.4  270.12
  4315.9  269.15  4362.6  267.26  4447.6  264.58  4508.4  261.85  4524.7  261.70
  4612.9  258.93  4698.2  258.01  4863.2  256.13  4892.0  254.46  4915.4  254.93
  4933.3  254.34  4945.4  253.05  4964.6  252.51  4967.4  252.01  4970.6  252.51
  4991.0  254.11  5002.5  254.05  5010.1  255.01  5029.5  255.56  5081.1  256.99
  5088.7  258.44  5101.4  259.73  5131.8  260.55  5162.2  263.60  5304.1  270.10
#Mann=7,-1,0
  4126.8    0.05       0  4447.6     0.1       0  4524.7    0.05       0
  4698.2     0.1       0  4964.6    0.07       0  4970.6     0.1       0
  5029.5    0.05       0
Bank Sta=4964.6,4970.6
Exp/Cntr=0.3,0.1

Type RM Length L Ch R = 1,1510,606,606,606
BEGIN DESCRIPTION:
UNT 059 IN LACR 2.0
END DESCRIPTION:
XS GIS Cut Line= 2
      2252128.79     13214373.13      2251176.49     13214342.22
#Sta/Elev= 30
  4558.7  263.97  4601.5  262.27  4619.8  262.14  4639.8  260.90  4669.8  260.14
  4679.8  259.29  4699.8  258.43  4759.9  256.27  4769.9  256.29  4819.9  254.80
  4889.9  253.86  4987.0  250.29  4989.7  249.79  4993.0  250.29  5040.0  252.01
  5060.0  251.51  5104.8  253.80  5130.1  254.34  5160.1  255.89  5190.1  256.65
  5209.8  257.84  5214.8  257.33  5220.1  258.50  5270.1  260.09  5290.2  261.74
  5320.2  263.21  5370.2  265.25  5380.2  265.20  5450.2  268.44  5511.5  270.26
#Mann=4,-1,0
  4558.7     0.1       0  4987.0    0.07       0  4993.0     0.1       0
  5104.8    0.05       0
Bank Sta=4987,4993
Exp/Cntr=0.3,0.1

Type RM Length L Ch R = 1,904,573,573,573
BEGIN DESCRIPTION:
Mapping XS 3efe3210
END DESCRIPTION:
XS GIS Cut Line= 4
      2252367.23     13214257.44      2252041.73     13213953.64
      2251293.03     13213899.38      2251001.40     13214093.80
#Sta/Elev= 30
  4264.2  266.89  4285.5  267.04  4419.9  264.24  4441.4  264.58  4491.7  262.43
  4521.5  261.78  4615.9  259.07  4708.8  255.08  4753.6  253.91  4783.7  252.15
  4870.7  250.40  4875.7  250.90  4914.0  248.37  4944.1  247.67  4961.1  246.47
  4963.9  245.97  4967.1  246.47  5004.2  246.72  5015.1  248.28  5034.3  249.52
  5104.5  253.03  5194.7  253.83  5246.7  255.29  5300.4  256.66  5385.2  259.24
  5395.2  260.15  5424.8  260.52  5531.7  263.65  5549.0  263.91  5810.6  268.33
#Mann=11,-1,0
  4264.2    0.05       0  4491.7     0.1       0  4521.5    0.05       0
  4615.9     0.1       0  4961.1    0.07       0  4967.1     0.1       0
  5246.7    0.05       0  5300.4     0.1       0  5424.8    0.05       0
  5531.7     0.1       0  5549.0    0.05       0
Bank Sta=4961.1,4967.1
Exp/Cntr=0.3,0.1

Type RM Length L Ch R = 1,331,0,0,0
BEGIN DESCRIPTION:
UNT 059 IN LACR 1.0
END DESCRIPTION:
XS GIS Cut Line= 4
      2252822.94     13214007.86      2252215.34     13213519.61
      2251737.91     13213389.40      2251001.38     13213757.67
#Sta/Elev= 30
  3984.6  262.34  3993.7  262.40  4016.6  262.02  4131.9  259.85  4145.2  258.94
  4330.3  253.75  4429.6  252.76  4485.3  253.13  4557.6  251.86  4631.5  251.95
  4685.6  252.07  4714.4  251.38  4757.5  251.82  4795.7  251.15  4823.8  251.63
  4896.3  250.15  4958.5  244.79  4997.0  242.58  4999.8  242.08  5003.0  242.58
  5031.1  243.80  5092.8  248.49  5196.9  248.20  5398.7  250.55  5644.7  251.78
  5795.6  256.03  5952.2  258.42  5963.5  259.13  5996.9  258.86  6082.4  260.20
#Mann=7,-1,0
  3984.6     0.1       0  3993.7    0.08       0  4016.6     0.1       0
  4485.3    0.08       0  4631.5     0.1       0  4997.0    0.07       0
  5003.0     0.1       0
Bank Sta=4997,5003
Exp/Cntr=0.3,0.1

Chan Stop Cuts=-1