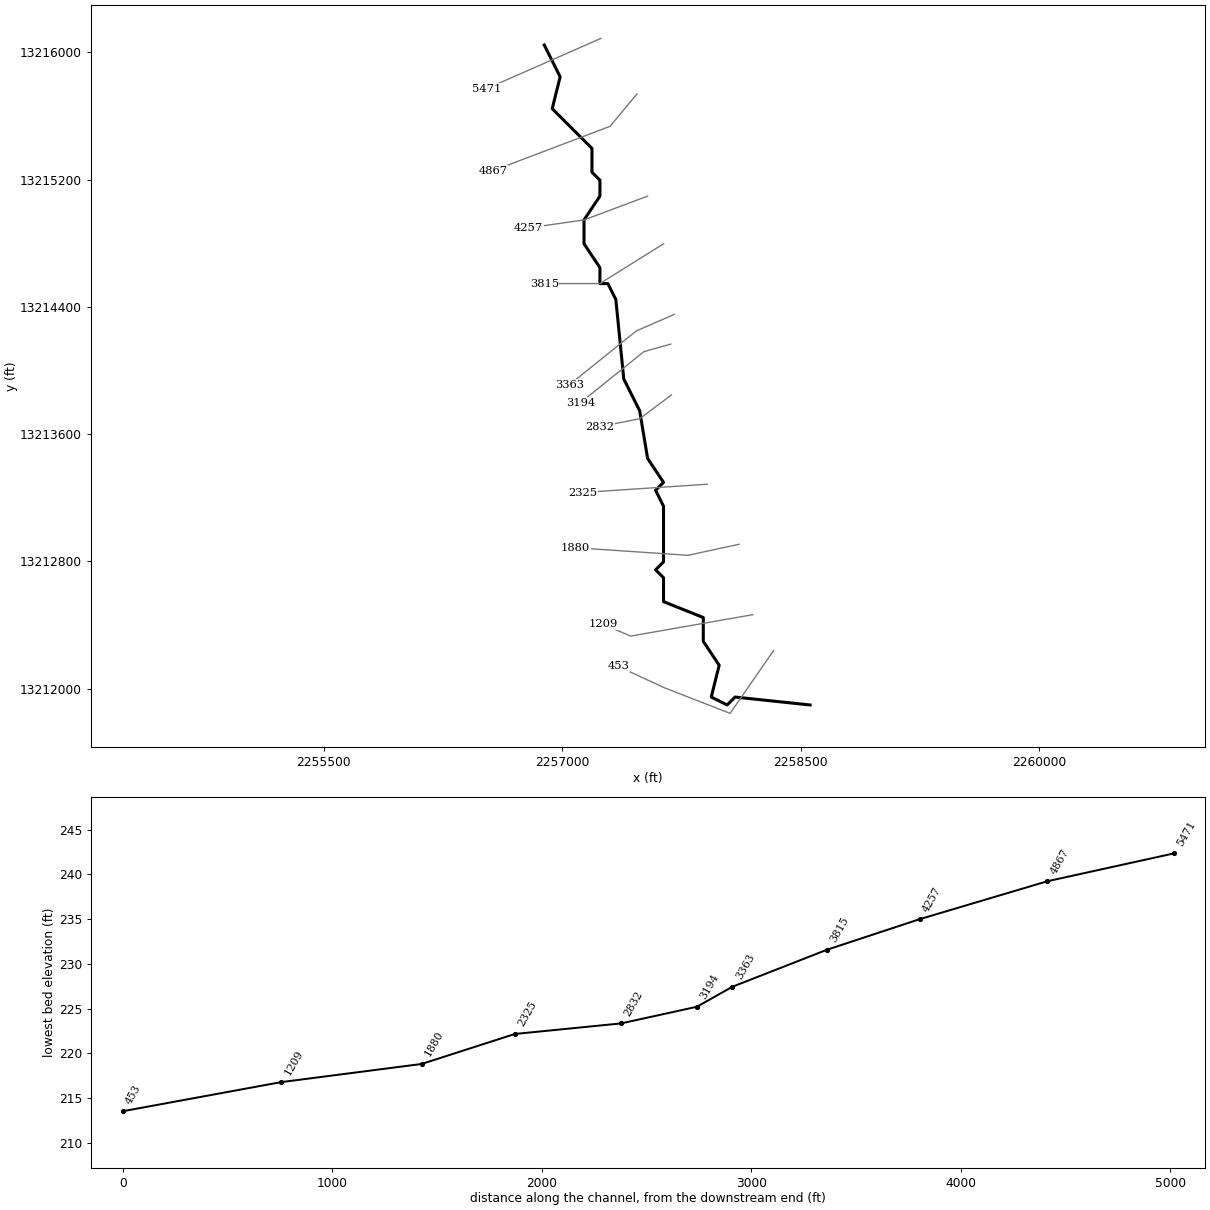
--- UNT 060 IN LACR.prj (project) ---

Proj Title=UNT 060 IN LACR Base Level Engineering
Current Plan=p01
Default Exp/Contr=0.3,0.1
English Units
Geom File=g01
Flow File=f01
Plan File=p01
BEGIN DESCRIPTION:
UNT 060 IN LACR
END DESCRIPTION:

--- UNT 060 IN LACR.p01 (plan) ---

Plan Title=Multiple Run
Short Identifier=Multiple
Geom File=g01
Flow File=f01
Subcritical Flow
K Sum by GR= 0
Std Step Tol= 0.01
Critical Tol= 0.01
Num of Std Step Trials= 20
Max Error Tol= 0.3
Flow Tol Ratio= 0.001
Split Flow NTrial= 30
Split Flow Tol= 0.02
Split Flow Ratio= 0.02
Log Output Level= 0
Friction Slope Method= 1
Unsteady Friction Slope Method= 2
Unsteady Bridges Friction Slope Method= 1
Parabolic Critical Depth
Global Vel Dist=  1 , 1 , 1
Global Log Level= 0
CheckData=True
Encroach Param= -1, 0, 0, 0
BEGIN DESCRIPTION:
Multiple Run
END DESCRIPTION:

--- UNT 060 IN LACR.f01 (steady flow) ---

Flow Title=Multiple
Number of Profiles=7
Profile Names=10-year,25-year,50-year,1pct_min,100-year,1pct_plu,500-year
River Rch & RM= UNT 060 IN LACR,Reach-1,5471
     228     314     385     348     471     636     713
Boundary for River Rch & Prof#=UNT 060 IN LACR,Reach-1,1
Up Type=0
Dn Type=3
Dn Slope=0.005
Boundary for River Rch & Prof#=UNT 060 IN LACR,Reach-1,2
Up Type=0
Dn Type=3
Dn Slope=0.005
Boundary for River Rch & Prof#=UNT 060 IN LACR,Reach-1,3
Up Type=0
Dn Type=3
Dn Slope=0.005
Boundary for River Rch & Prof#=UNT 060 IN LACR,Reach-1,4
Up Type=0
Dn Type=3
Dn Slope=0.005
Boundary for River Rch & Prof#=UNT 060 IN LACR,Reach-1,5
Up Type=0
Dn Type=3
Dn Slope=0.005
Boundary for River Rch & Prof#=UNT 060 IN LACR,Reach-1,6
Up Type=0
Dn Type=3
Dn Slope=0.005
Boundary for River Rch & Prof#=UNT 060 IN LACR,Reach-1,7
Up Type=0
Dn Type=3
Dn Slope=0.005

--- UNT 060 IN LACR.g01 (geometry) ---

Geom Title=Existing Conditions

River Reach=UNT 060 IN LACR,Reach-1
Reach XY= 30
      2256887.72     13216046.85      2256987.72     13215846.85
      2256937.72     13215646.85      2257187.72     13215396.85
      2257187.72     13215246.85      2257237.72     13215196.85
      2257237.72     13215096.85      2257137.72     13214946.86
      2257137.72     13214796.86      2257237.72     13214646.85
      2257237.72     13214546.85      2257287.72     13214546.85
      2257337.72     13214446.86      2257387.72     13213946.85
      2257487.72     13213746.85      2257537.72     13213446.85
      2257637.72     13213296.86      2257587.72     13213246.85
      2257637.72     13213146.86      2257637.72     13212796.85
      2257587.72     13212746.85      2257637.72     13212696.85
      2257637.72     13212546.85      2257887.72     13212446.85
      2257887.72     13212296.85      2257987.72     13212146.86
      2257937.72     13211946.85      2258037.72     13211896.85
      2258087.72     13211946.85      2258559.50     13211896.85

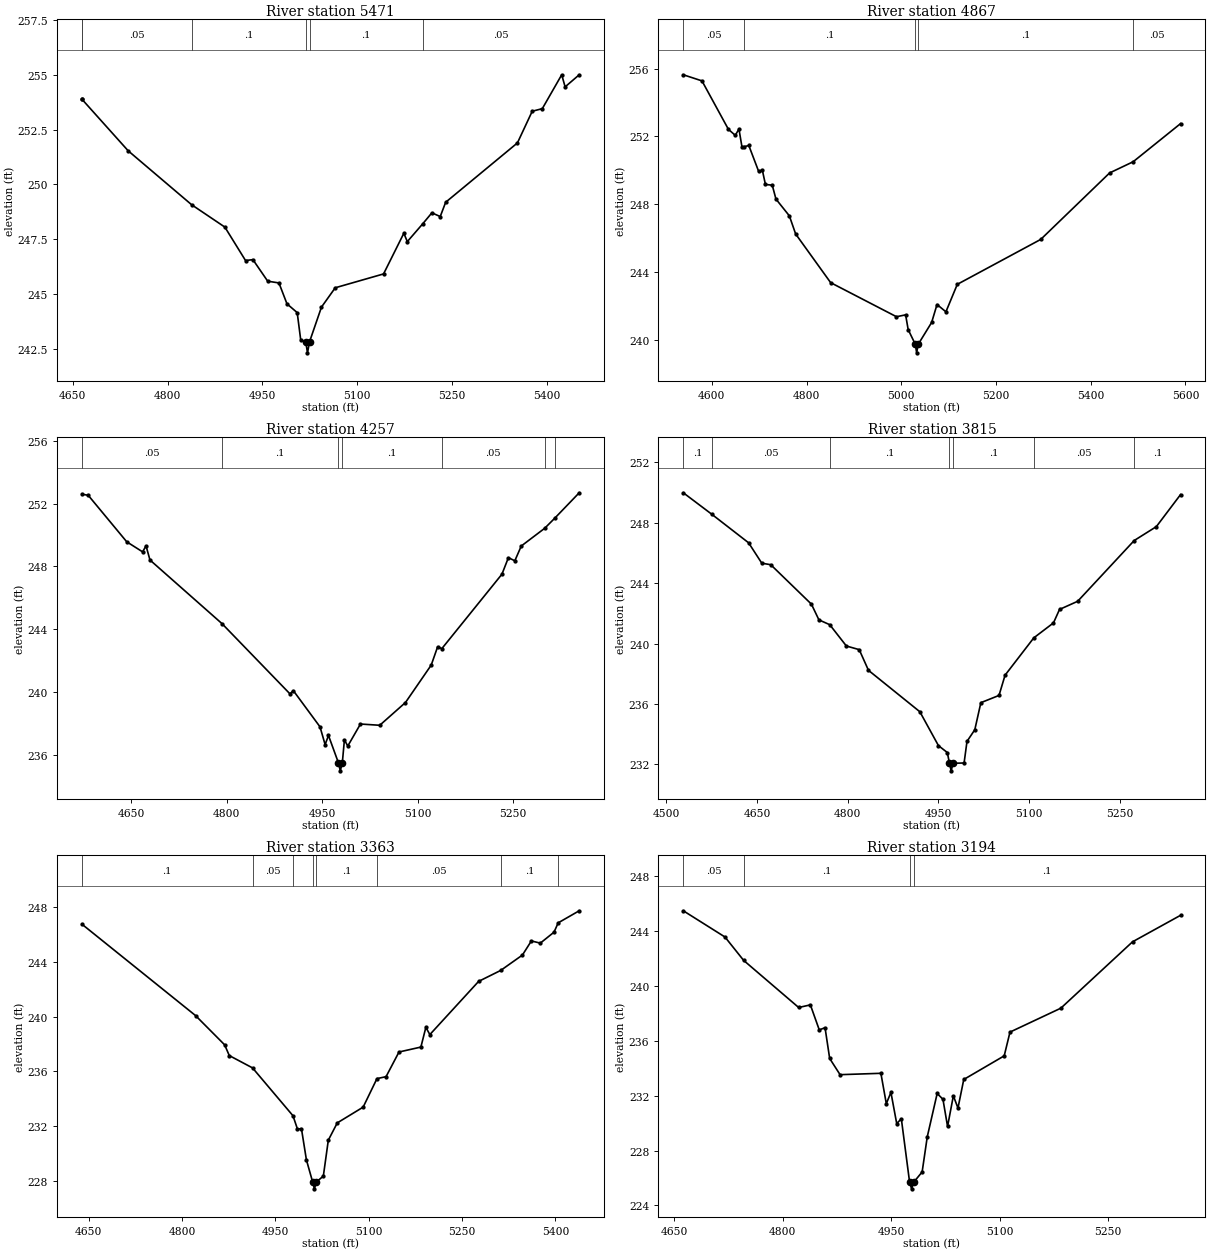
Type RM Length L Ch R = 1,5471,604,604,604
BEGIN DESCRIPTION:
UNT 060 IN LACR 8.0
END DESCRIPTION:
XS GIS Cut Line= 2
      2257244.74     13216088.90      2256524.24     13215772.05
#Sta/Elev= 30
  4664.6  253.88  4664.8  253.87  4737.8  251.53  4838.1  249.08  4890.8  248.06
  4923.5  246.54  4935.2  246.58  4958.6  245.60  4976.4  245.52  4989.1  244.57
  5005.3  244.17  5010.9  242.92  5018.8  242.84  5021.6  242.34  5024.8  242.84
  5043.7  244.42  5065.5  245.30  5142.0  245.93  5174.1  247.78  5179.6  247.40
  5204.3  248.22  5218.5  248.71  5231.7  248.54  5240.3  249.19  5353.9  251.89
  5377.3  253.33  5393.3  253.45  5424.0  254.99  5429.4  254.44  5451.7  254.99
#Mann=6,-1,0
  4664.6     0.1       0  4664.8    0.05       0  4838.1     0.1       0
  5018.8    0.07       0  5024.8     0.1       0  5204.3    0.05       0
Bank Sta=5018.8,5024.8
Exp/Cntr=0.3,0.1

Type RM Length L Ch R = 1,4867,610,610,610
BEGIN DESCRIPTION:
UNT 060 IN LACR 7.0
END DESCRIPTION:
XS GIS Cut Line= 3
      2257470.64     13215738.85      2257301.37     13215535.72
      2256566.96     13215257.07
#Sta/Elev= 30
  4539.8  255.63  4579.2  255.27  4635.1  252.41  4649.5  252.06  4657.3  252.43
  4663.8  251.35  4668.6  251.39  4678.1  251.46  4698.9  249.93  4706.7  250.00
  4713.2  249.16  4727.6  249.12  4735.4  248.30  4763.7  247.31  4777.0  246.24
  4850.9  243.37  4989.9  241.36  5009.2  241.47  5014.6  240.60  5029.7  239.73
  5032.5  239.23  5035.7  239.73  5064.1  241.02  5075.5  242.08  5094.3  241.65
  5118.3  243.27  5294.5  245.92  5439.9  249.84  5489.6  250.50  5589.7  252.75
#Mann=5,-1,0
  4539.8    0.05       0  4668.6     0.1       0  5029.7    0.07       0
  5035.7     0.1       0  5489.6    0.05       0
Bank Sta=5029.7,5035.7
Exp/Cntr=0.3,0.1

Type RM Length L Ch R = 1,4257,442,442,442
BEGIN DESCRIPTION:
UNT 060 IN LACR 6.0
END DESCRIPTION:
XS GIS Cut Line= 3
      2257537.72     13215096.85      2257137.72     13214946.86
      2256787.67     13214896.85
#Sta/Elev= 30
  4572.8  252.60  4582.6  252.53  4643.1  249.57  4668.0  248.93  4673.4  249.31
  4679.6  248.41  4792.7  244.36  4899.4  239.89  4904.8  240.09  4946.6  237.79
  4954.6  236.66  4959.9  237.24  4975.6  235.49  4978.4  234.99  4981.6  235.49
  4984.9  236.96  4990.2  236.57  5010.1  237.97  5040.4  237.89  5080.8  239.34
  5121.2  241.72  5131.3  242.89  5137.9  242.77  5232.3  247.51  5242.4  248.56
  5252.5  248.36  5262.6  249.30  5299.4  250.43  5315.4  251.08  5353.6  252.69
#Mann=7,-1,0
  4572.8    0.05       0  4792.7     0.1       0  4975.6    0.07       0
  4981.6     0.1       0  5137.9    0.05       0  5299.4     0.1       0
  5315.4    0.05       0
Bank Sta=4975.6,4981.6
Exp/Cntr=0.3,0.1

Type RM Length L Ch R = 1,3815,452,452,452
BEGIN DESCRIPTION:
UNT 060 IN LACR 5.0
END DESCRIPTION:
XS GIS Cut Line= 3
      2257637.72     13214796.86      2257237.72     13214546.85
      2256887.72     13214546.85
#Sta/Elev= 30
  4528.3  249.98  4575.0  248.57  4636.2  246.67  4658.0  245.32  4672.8  245.22
  4740.0  242.61  4752.4  241.57  4770.3  241.25  4797.8  239.84  4819.0  239.60
  4834.3  238.23  4919.2  235.49  4949.9  233.25  4964.6  232.79  4968.1  232.08
  4970.9  231.58  4974.1  232.08  4992.3  232.10  4997.1  233.53  5010.0  234.30
  5020.0  236.09  5050.0  236.57  5060.0  237.91  5107.5  240.38  5140.0  241.37
  5150.0  242.26  5180.0  242.80  5273.4  246.82  5310.0  247.74  5350.0  249.86
#Mann=7,-1,0
  4528.3     0.1       0  4575.0    0.05       0  4770.3     0.1       0
  4968.1    0.07       0  4974.1     0.1       0  5107.5    0.05       0
  5273.4     0.1       0
Bank Sta=4968.1,4974.1
Exp/Cntr=0.3,0.1

Type RM Length L Ch R = 1,3363,169,169,169
BEGIN DESCRIPTION:
Mapping XS 7d45601b
END DESCRIPTION:
XS GIS Cut Line= 3
      2257704.79     13214352.78      2257466.08     13214248.62
      2257046.15     13213910.94
#Sta/Elev= 30
  4639.0  246.74  4821.5  240.08  4868.4  237.94  4875.8  237.16  4913.2  236.26
  4978.2  232.77  4985.4  231.80  4991.8  231.83  4999.8  229.55  5009.8  227.94
  5012.6  227.44  5015.8  227.94  5027.0  228.37  5035.0  230.99  5049.4  232.25
  5091.0  233.40  5113.2  235.48  5127.8  235.62  5148.6  237.42  5183.8  237.78
  5191.8  239.22  5198.2  238.69  5276.6  242.57  5312.1  243.37  5347.0  244.49
  5361.4  245.52  5375.8  245.36  5397.8  246.16  5404.5  246.84  5438.3  247.72
#Mann=8,-1,0
  4639.0     0.1       0  4913.2    0.05       0  4978.2     0.1       0
  5009.8    0.07       0  5015.8     0.1       0  5113.2    0.05       0
  5312.1     0.1       0  5404.5    0.05       0
Bank Sta=5009.8,5015.8
Exp/Cntr=0.3,0.1

Type RM Length L Ch R = 1,3194,362,362,362
BEGIN DESCRIPTION:
UNT 060 IN LACR 4.0
END DESCRIPTION:
XS GIS Cut Line= 3
      2257683.09     13214166.15      2257513.82     13214118.41
      2257114.53     13213797.24
#Sta/Elev= 30
  4662.3  245.45  4720.0  243.54  4745.8  241.84  4822.0  238.41  4838.2  238.60
  4850.5  236.78  4858.5  236.94  4864.9  234.70  4879.3  233.52  4935.8  233.62
  4943.3  231.41  4949.7  232.23  4957.7  229.96  4964.1  230.31  4975.5  225.71
  4978.3  225.21  4981.5  225.71  4992.9  226.44  5000.0  229.00  5013.7  232.15
  5021.7  231.73  5028.1  229.75  5036.1  231.98  5042.5  231.09  5050.5  233.17
  5106.5  234.89  5114.5  236.62  5184.9  238.36  5284.1  243.19  5350.6  245.12
#Mann=4,-1,0
  4662.3    0.05       0  4745.8     0.1       0  4975.5    0.07       0
  4981.5     0.1       0
Bank Sta=4975.5,4981.5
Exp/Cntr=0.3,0.1

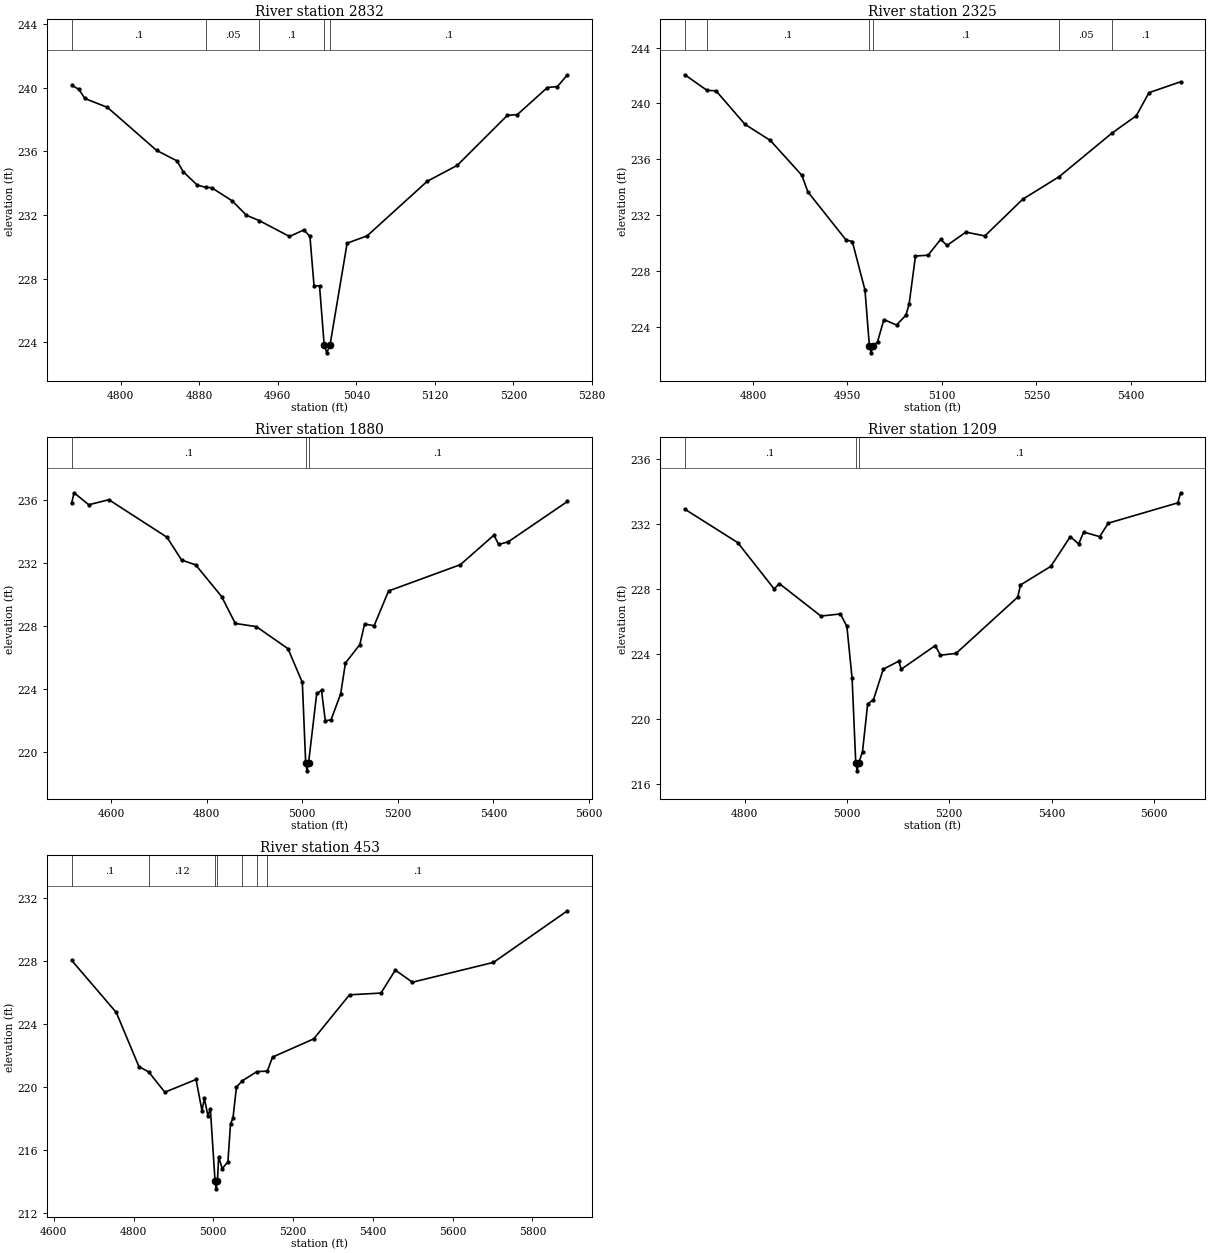
Type RM Length L Ch R = 1,2832,507,507,507
BEGIN DESCRIPTION:
UNT 060 IN LACR 3.0
END DESCRIPTION:
XS GIS Cut Line= 3
      2257687.72     13213846.85      2257487.72     13213696.85
      2257237.67     13213646.85
#Sta/Elev= 30
  4750.0  240.16  4757.3  239.91  4763.5  239.33  4786.5  238.77  4836.5  236.07
  4857.3  235.41  4863.5  234.74  4878.1  233.88  4886.7  233.75  4892.7  233.72
  4913.5  232.90  4928.1  231.99  4941.1  231.66  4971.9  230.66  4986.5  231.07
  4992.7  230.67  4996.9  227.56  5002.5  227.56  5007.2  223.85  5009.9  223.35
  5013.2  223.85  5030.6  230.24  5051.0  230.70  5112.2  234.13  5142.8  235.13
  5193.8  238.27  5204.0  238.32  5234.6  240.02  5244.8  240.08  5255.0  240.82
#Mann=5,-1,0
  4750.0     0.1       0  4886.7    0.05       0  4941.1     0.1       0
  5007.2    0.07       0  5013.2     0.1       0
Bank Sta=5007.2,5013.2
Exp/Cntr=0.3,0.1

Type RM Length L Ch R = 1,2325,445,445,445
BEGIN DESCRIPTION:
UNT 060 IN LACR 2.0
END DESCRIPTION:
XS GIS Cut Line= 2
      2257913.17     13213285.08      2257127.50     13213232.99
#Sta/Elev= 30
  4691.7  242.05  4726.8  240.94  4741.3  240.90  4787.4  238.50  4827.4  237.36
  4877.6  234.86  4887.1  233.68  4947.7  230.24  4957.7  230.13  4977.8  226.66
  4984.8  222.67  4987.5  222.17  4990.8  222.67  4997.8  222.96  5007.8  224.55
  5027.9  224.16  5042.8  224.86  5047.9  225.66  5058.0  229.09  5078.0  229.15
  5098.0  230.28  5108.1  229.85  5138.1  230.80  5168.2  230.53  5228.3  233.15
  5286.4  234.77  5369.5  237.86  5408.7  239.12  5428.8  240.77  5479.1  241.55
#Mann=6,-1,0
  4691.7    0.05       0  4726.8     0.1       0  4984.8    0.07       0
  4990.8     0.1       0  5286.4    0.05       0  5369.5     0.1       0
Bank Sta=4984.8,4990.8
Exp/Cntr=0.3,0.1

Type RM Length L Ch R = 1,1880,671,671,671
BEGIN DESCRIPTION:
Mapping XS 52a1409e
END DESCRIPTION:
XS GIS Cut Line= 3
      2258112.75     13212907.46      2257791.60     13212838.03
      2257084.18     13212885.77
#Sta/Elev= 30
  4517.2  235.80  4522.3  236.46  4553.0  235.70  4595.1  236.02  4716.7  233.64
  4747.4  232.19  4776.7  231.89  4831.0  229.88  4859.7  228.17  4903.7  227.97
  4969.9  226.57  5000.0  224.43  5007.0  219.32  5009.8  218.82  5013.0  219.32
  5030.1  223.73  5040.1  223.92  5048.1  221.99  5060.1  222.06  5080.2  223.70
  5090.2  225.66  5120.3  226.83  5130.3  228.13  5150.3  228.03  5180.4  230.23
  5330.8  231.90  5400.9  233.77  5410.9  233.18  5431.0  233.35  5554.8  235.91
#Mann=3,-1,0
  4517.2     0.1       0  5007.0    0.07       0  5013.0     0.1       0
Bank Sta=5007,5013
Exp/Cntr=0.3,0.1

Type RM Length L Ch R = 1,1209,756,756,756
BEGIN DESCRIPTION:
Mapping XS 704cba3f
END DESCRIPTION:
XS GIS Cut Line= 3
      2258199.57     13212464.76      2257431.36     13212330.21
      2257257.70     13212404.02
#Sta/Elev= 30
  4683.4  232.90  4786.8  230.84  4857.9  227.99  4868.0  228.32  4949.2  226.32
  4987.4  226.45  5000.0  225.68  5010.2  222.48  5017.3  217.29  5020.1  216.79
  5023.3  217.29  5030.5  217.97  5040.6  220.91  5051.9  221.17  5071.1  223.05
  5101.2  223.54  5106.3  223.05  5172.6  224.50  5182.7  223.91  5213.2  224.02
  5333.9  227.49  5339.0  228.23  5398.4  229.38  5436.5  231.21  5452.8  230.76
  5462.6  231.49  5493.8  231.21  5510.7  232.04  5646.5  233.29  5652.0  233.91
#Mann=3,-1,0
  4683.4     0.1       0  5017.3    0.07       0  5023.3     0.1       0
Bank Sta=5017.3,5023.3
Exp/Cntr=0.3,0.1

Type RM Length L Ch R = 1,453,0,0,0
BEGIN DESCRIPTION:
UNT 060 IN LACR 1.0
END DESCRIPTION:
XS GIS Cut Line= 4
      2258329.79     13212239.06      2258056.36     13211844.10
      2257644.03     13212004.69      2257353.22     13212139.25
#Sta/Elev= 30
  4644.6  228.06  4756.5  224.75  4813.3  221.31  4837.8  220.97  4878.4  219.68
  4956.6  220.49  4971.4  218.51  4977.5  219.29  4986.3  218.18  4992.4  218.64
  5004.2  214.04  5007.0  213.54  5010.2  214.04  5013.3  215.57  5022.1  214.82
  5036.5  215.26  5043.0  217.68  5049.1  218.02  5057.9  220.01  5072.8  220.41
  5109.2  220.99  5135.3  221.02  5148.3  221.91  5251.7  223.07  5341.4  225.87
  5420.3  225.98  5456.2  227.44  5499.1  226.67  5702.4  227.93  5887.9  231.21
#Mann=7,-1,0
  4644.6     0.1       0  4837.8    0.12       0  5004.2    0.07       0
  5010.2    0.12       0  5072.8     0.1       0  5109.2    0.12       0
  5135.3     0.1       0
Bank Sta=5004.2,5010.2
Exp/Cntr=0.3,0.1

Chan Stop Cuts=-1