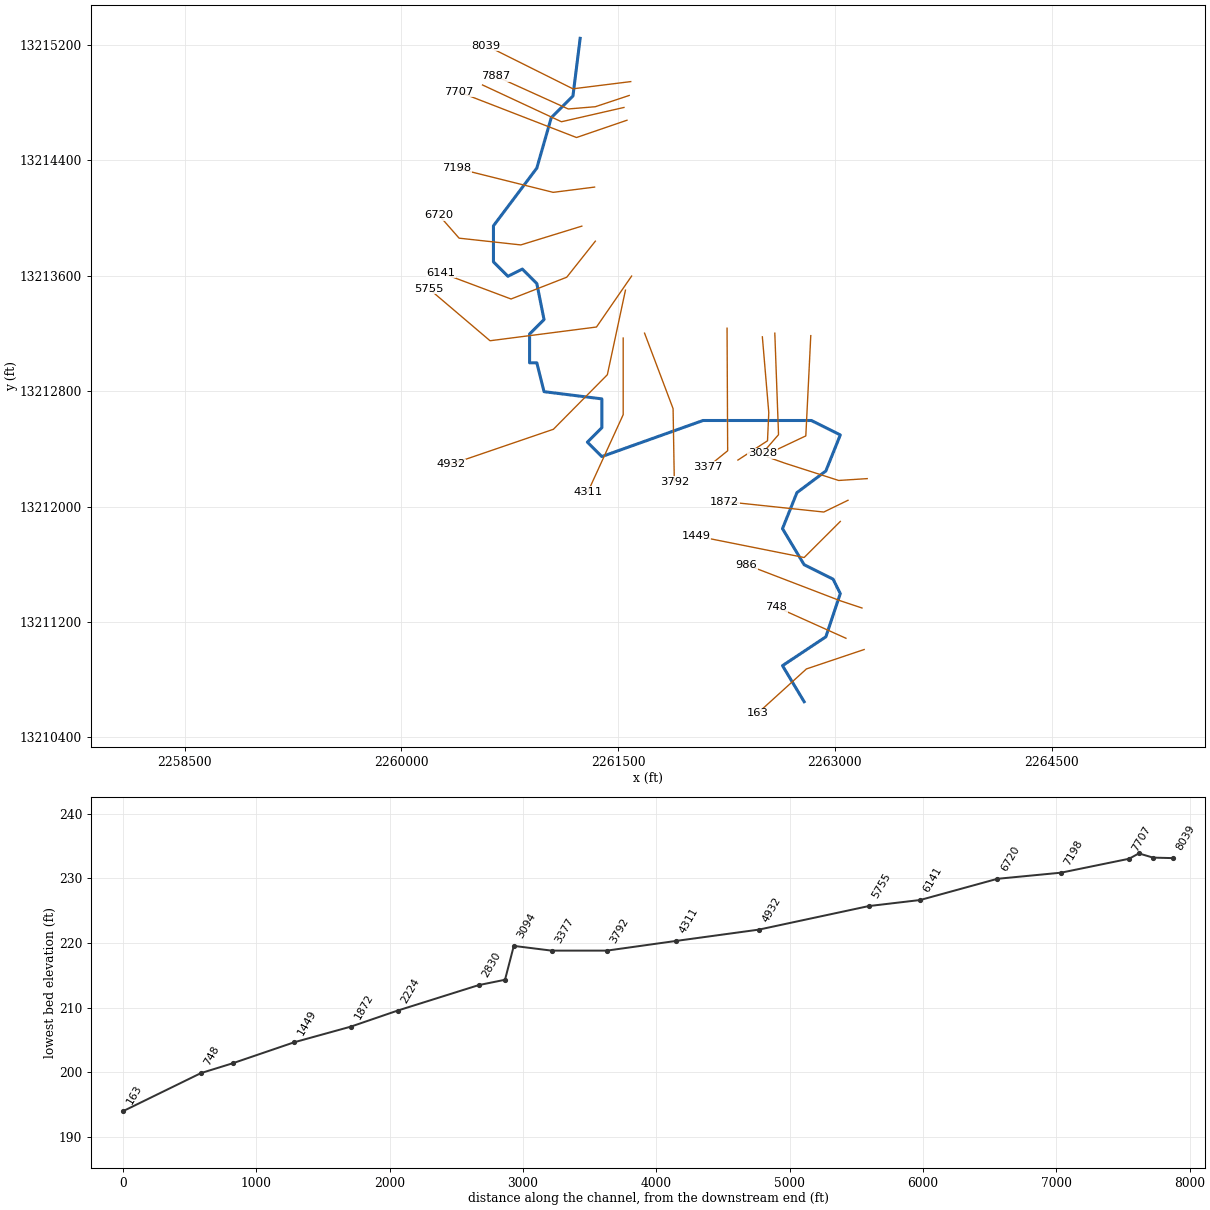
--- UNT 061 IN LACR.prj (project) ---

Proj Title=UNT 061 IN LACR Base Level Engineering
Current Plan=p01
Default Exp/Contr=0.3,0.1
English Units
Geom File=g01
Flow File=f01
Plan File=p01
BEGIN DESCRIPTION:
UNT 061 IN LACR
END DESCRIPTION:

--- UNT 061 IN LACR.p01 (plan) ---

Plan Title=Multiple Run
Short Identifier=Multiple
Geom File=g01
Flow File=f01
Subcritical Flow
K Sum by GR= 0
Std Step Tol= 0.01
Critical Tol= 0.01
Num of Std Step Trials= 20
Max Error Tol= 0.3
Flow Tol Ratio= 0.001
Split Flow NTrial= 30
Split Flow Tol= 0.02
Split Flow Ratio= 0.02
Log Output Level= 0
Friction Slope Method= 1
Unsteady Friction Slope Method= 2
Unsteady Bridges Friction Slope Method= 1
Parabolic Critical Depth
Global Vel Dist=  1 , 1 , 1
Global Log Level= 0
CheckData=True
Encroach Param= -1, 0, 0, 0
BEGIN DESCRIPTION:
Multiple Run
END DESCRIPTION:

--- UNT 061 IN LACR.f01 (steady flow) ---

Flow Title=Multiple
Number of Profiles=7
Profile Names=10-year,25-year,50-year,1pct_min,100-year,1pct_plu,500-year
River Rch & RM= UNT 061 IN LACR,Reach-1,8039
     181     245     297     265     358     484     529
River Rch & RM= UNT 061 IN LACR,Reach-1,7198
     262     361     443     400     541     731     818
Boundary for River Rch & Prof#=UNT 061 IN LACR,Reach-1,1
Up Type=0
Dn Type=3
Dn Slope=0.005
Boundary for River Rch & Prof#=UNT 061 IN LACR,Reach-1,2
Up Type=0
Dn Type=3
Dn Slope=0.005
Boundary for River Rch & Prof#=UNT 061 IN LACR,Reach-1,3
Up Type=0
Dn Type=3
Dn Slope=0.005
Boundary for River Rch & Prof#=UNT 061 IN LACR,Reach-1,4
Up Type=0
Dn Type=3
Dn Slope=0.005
Boundary for River Rch & Prof#=UNT 061 IN LACR,Reach-1,5
Up Type=0
Dn Type=3
Dn Slope=0.005
Boundary for River Rch & Prof#=UNT 061 IN LACR,Reach-1,6
Up Type=0
Dn Type=3
Dn Slope=0.005
Boundary for River Rch & Prof#=UNT 061 IN LACR,Reach-1,7
Up Type=0
Dn Type=3
Dn Slope=0.005

--- UNT 061 IN LACR.g01 (geometry) ---

Geom Title=Existing Conditions

River Reach=UNT 061 IN LACR,Reach-1
Reach XY= 30
      2261237.72     13215246.85      2261187.72     13214846.85
      2261037.72     13214696.85      2260937.72     13214346.85
      2260637.72     13213946.85      2260637.72     13213696.85
      2260737.72     13213596.85      2260837.72     13213646.86
      2260937.72     13213546.85      2260987.72     13213296.86
      2260887.72     13213196.85      2260887.72     13212996.86
      2260937.72     13212996.86      2260987.72     13212796.85
      2261387.72     13212746.85      2261387.72     13212546.85
      2261287.72     13212446.85      2261387.72     13212346.86
      2262087.72     13212596.85      2262837.72     13212596.85
      2263037.72     13212496.86      2262937.72     13212246.85
      2262737.72     13212096.85      2262637.72     13211846.86
      2262787.72     13211596.85      2262987.72     13211496.86
      2263037.72     13211396.85      2262937.72     13211096.85
      2262637.72     13210896.85      2262787.72     13210646.85

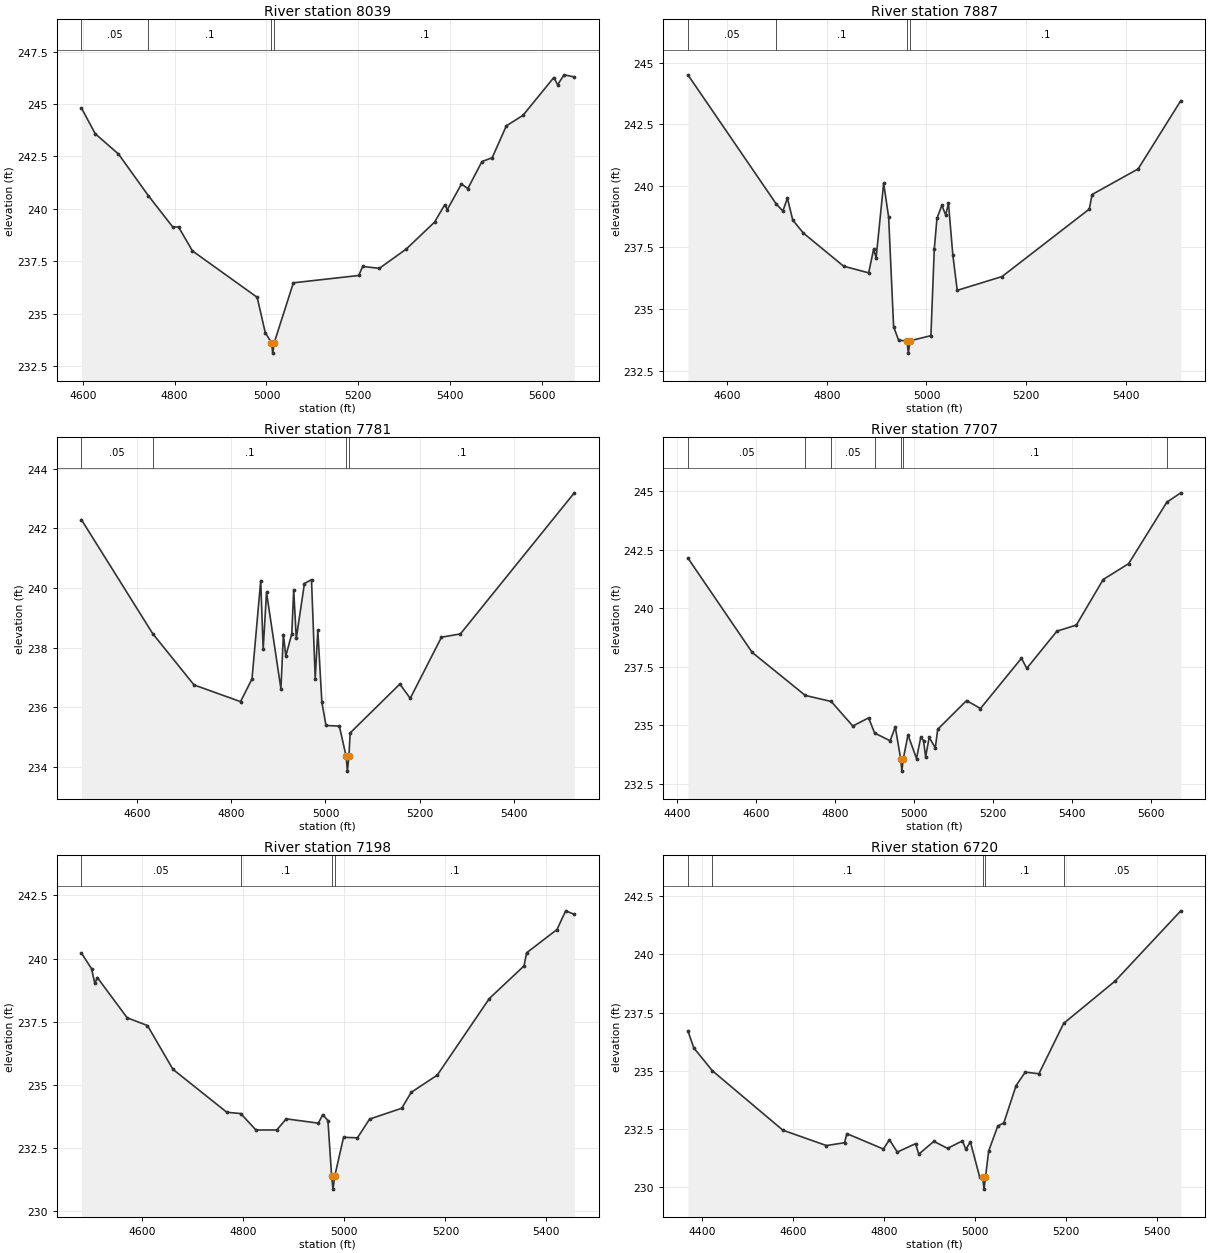
Type RM Length L Ch R = 1,8039,152,152,152
BEGIN DESCRIPTION:
UNT 061 IN LACR 13.0
END DESCRIPTION:
XS GIS Cut Line= 3
      2261587.71     13214946.85      2261187.72     13214896.85
      2260587.74     13215196.85
#Sta/Elev= 30
  4596.9  244.81  4627.1  243.58  4677.5  242.62  4742.8  240.63  4795.9  239.14
  4808.5  239.14  4838.8  238.00  4979.8  235.79  4997.5  234.10  5011.0  233.63
  5013.7  233.13  5017.0  233.63  5058.7  236.48  5201.2  236.83  5209.6  237.26
  5246.0  237.17  5304.7  238.09  5366.2  239.37  5388.5  240.20  5394.1  239.97
  5424.9  241.19  5438.8  240.97  5469.6  242.26  5491.9  242.44  5522.7  243.96
  5559.0  244.46  5626.1  246.26  5634.5  245.92  5648.5  246.39  5670.8  246.29
#Mann=4,-1,0
  4596.9    0.05       0  4742.8     0.1       0  5011.0    0.07       0
  5017.0     0.1       0
Bank Sta=5011,5017
Exp/Cntr=0.3,0.1

Type RM Length L Ch R = 1,7887,106,106,106
BEGIN DESCRIPTION:
Mapping XS d8afc7a1
END DESCRIPTION:
XS GIS Cut Line= 4
      2261577.11     13214850.81      2261342.74     13214772.68
      2261155.24     13214757.06      2260651.36     13214985.62
#Sta/Elev= 30
  4521.5  244.51  4698.9  239.26  4711.9  238.98  4721.1  239.50  4731.7  238.62
  4752.8  238.09  4833.8  236.74  4884.0  236.47  4894.0  237.43  4899.0  237.08
  4914.1  240.11  4924.1  238.73  4934.1  234.28  4944.2  233.73  4960.9  233.71
  4963.6  233.21  4966.9  233.71  5008.9  233.92  5015.6  237.42  5021.0  238.68
  5030.8  239.21  5038.6  238.82  5044.1  239.30  5052.8  237.20  5061.7  235.76
  5151.6  236.32  5326.6  239.06  5332.1  239.65  5424.5  240.69  5510.0  243.46
#Mann=4,-1,0
  4521.5    0.05       0  4698.9     0.1       0  4960.9    0.07       0
  4966.9     0.1       0
Bank Sta=4960.9,4966.9
Exp/Cntr=0.3,0.1

Type RM Length L Ch R = 1,7781,74,74,74
BEGIN DESCRIPTION:
Mapping XS fde2352c
END DESCRIPTION:
XS GIS Cut Line= 3
      2261540.71     13214767.48      2261108.37     13214668.51
      2260562.14     13214923.42
#Sta/Elev= 30
  4482.0  242.29  4633.3  238.47  4721.0  236.75  4819.7  236.19  4844.1  236.95
  4862.6  240.25  4867.8  237.94  4874.9  239.85  4905.5  236.62  4910.7  238.44
  4915.9  237.72  4928.6  238.47  4932.6  239.94  4938.1  238.31  4955.4  240.15
  4970.4  240.28  4978.3  236.96  4983.8  238.58  4992.4  236.17  5001.2  235.39
  5029.5  235.37  5043.9  234.36  5046.6  233.86  5049.9  234.36  5052.4  235.14
  5158.0  236.78  5180.0  236.30  5246.3  238.35  5286.5  238.46  5528.3  243.19
#Mann=4,-1,0
  4482.0    0.05       0  4633.3     0.1       0  5043.9    0.07       0
  5049.9     0.1       0
Bank Sta=5043.9,5049.9
Exp/Cntr=0.3,0.1

Type RM Length L Ch R = 1,7707,509,509,509
BEGIN DESCRIPTION:
Mapping XS 74968976
END DESCRIPTION:
XS GIS Cut Line= 3
      2261561.51     13214678.94      2261212.53     13214559.14
      2260394.85     13214876.84
#Sta/Elev= 30
  4428.2  242.15  4590.8  238.11  4725.0  236.27  4790.6  236.01  4845.2  234.96
  4885.1  235.31  4900.3  234.66  4939.6  234.33  4952.5  234.92  4966.5  233.53
  4969.2  233.03  4972.5  233.53  4984.7  234.58  5006.2  233.57  5016.9  234.47
  5023.9  234.34  5029.3  233.64  5038.3  234.48  5053.8  234.02  5059.8  234.82
  5132.8  236.05  5168.0  235.71  5271.5  237.86  5285.1  237.43  5361.2  239.02
  5410.3  239.28  5478.2  241.23  5542.6  241.91  5639.2  244.54  5674.4  244.94
#Mann=7,-1,0
  4428.2    0.05       0  4725.0     0.1       0  4790.6    0.05       0
  4900.3     0.1       0  4966.5    0.07       0  4972.5     0.1       0
  5639.2    0.08       0
Bank Sta=4966.5,4972.5
Exp/Cntr=0.3,0.1

Type RM Length L Ch R = 1,7198,478,478,478
BEGIN DESCRIPTION:
UNT 061 IN LACR 12.0
END DESCRIPTION:
XS GIS Cut Line= 3
      2261337.52     13214215.39      2261051.07     13214178.93
      2260384.44     13214345.59
#Sta/Elev= 30
  4479.3  240.22  4499.3  239.60  4505.8  239.02  4510.8  239.25  4569.8  237.66
  4610.1  237.35  4660.5  235.62  4767.2  233.92  4794.7  233.87  4824.8  233.22
  4866.0  233.22  4884.9  233.66  4948.5  233.49  4957.1  233.83  4967.4  233.59
  4974.7  231.38  4977.4  230.88  4980.7  231.38  4998.3  232.93  5025.8  232.91
  5049.8  233.65  5113.4  234.08  5132.3  234.71  5183.8  235.39  5286.9  238.42
  5355.6  239.71  5360.8  240.23  5420.9  241.15  5438.1  241.89  5455.2  241.75
#Mann=4,-1,0
  4479.3    0.05       0  4794.7     0.1       0  4974.7    0.07       0
  4980.7     0.1       0
Bank Sta=4974.7,4980.7
Exp/Cntr=0.3,0.1

Type RM Length L Ch R = 1,6720,579,579,579
BEGIN DESCRIPTION:
UNT 061 IN LACR 11.0
END DESCRIPTION:
XS GIS Cut Line= 4
      2261248.95     13213944.54      2260827.12     13213814.35
      2260400.03     13213861.22      2260259.02     13214022.17
#Sta/Elev= 30
  4368.0  236.72  4381.0  235.99  4421.8  235.01  4577.0  232.46  4672.8  231.80
  4712.8  231.92  4718.0  232.31  4798.4  231.65  4811.7  232.05  4829.0  231.52
  4869.2  231.88  4876.3  231.43  4909.5  231.98  4939.6  231.68  4972.4  232.00
  4979.9  231.64  4989.9  231.96  5010.1  230.47  5017.1  230.43  5019.9  229.93
  5023.1  230.43  5030.2  231.57  5050.3  232.64  5063.5  232.77  5090.5  234.37
  5110.7  234.95  5140.8  234.88  5195.2  237.04  5308.7  238.86  5453.1  241.87
#Mann=5,-1,0
  4368.0    0.05       0  4421.8     0.1       0  5017.1    0.07       0
  5023.1     0.1       0  5195.2    0.05       0
Bank Sta=5017.1,5023.1
Exp/Cntr=0.3,0.1

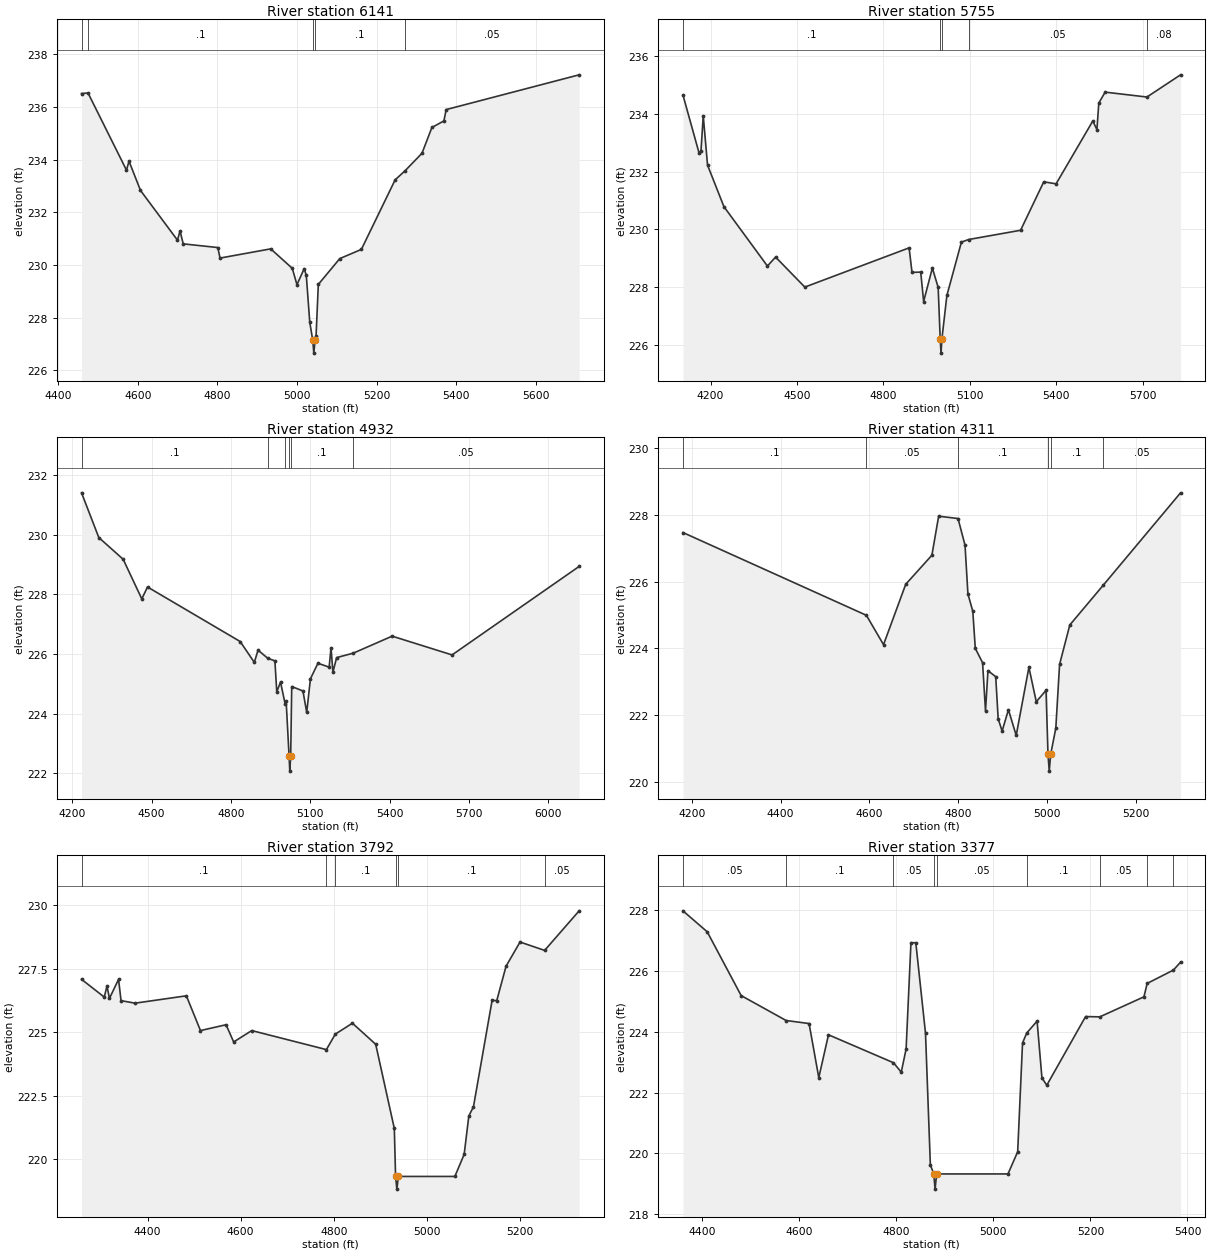
Type RM Length L Ch R = 1,6141,386,386,386
BEGIN DESCRIPTION:
UNT 061 IN LACR 10.0
END DESCRIPTION:
XS GIS Cut Line= 4
      2261342.74     13213840.39      2261144.82     13213590.39
      2260759.41     13213439.35      2260274.99     13213621.65
#Sta/Elev= 30
  4458.7  236.51  4475.0  236.53  4571.6  233.60  4578.0  233.94  4606.8  232.83
  4699.8  230.94  4706.2  231.29  4714.2  230.80  4801.1  230.66  4806.7  230.26
  4934.1  230.61  4988.3  229.87  5000.0  229.25  5018.2  229.86  5023.5  229.60
  5032.2  227.82  5039.6  227.15  5042.4  226.65  5045.6  227.15  5048.0  227.29
  5053.7  229.26  5107.6  230.24  5161.9  230.59  5246.7  233.23  5271.9  233.58
  5314.2  234.24  5339.1  235.22  5369.3  235.47  5375.0  235.90  5709.1  237.22
#Mann=5,-1,0
  4458.7    0.05       0  4475.0     0.1       0  5039.6    0.07       0
  5045.6     0.1       0  5271.9    0.05       0
Bank Sta=5039.6,5045.6
Exp/Cntr=0.3,0.1

Type RM Length L Ch R = 1,5755,823,823,823
BEGIN DESCRIPTION:
UNT 061 IN LACR 9.0
END DESCRIPTION:
XS GIS Cut Line= 4
      2261593.71     13213598.35      2261350.68     13213245.09
      2260614.06     13213149.88      2260191.64     13213509.81
#Sta/Elev= 30
  4104.4  234.66  4160.0  232.66  4166.9  232.71  4174.8  233.94  4189.7  232.23
  4246.5  230.79  4397.5  228.73  4425.8  229.04  4527.3  228.00  4889.1  229.36
  4899.2  228.51  4929.4  228.52  4939.5  227.50  4969.8  228.66  4989.9  227.99
  4997.0  226.21  4999.8  225.71  5003.0  226.21  5020.2  227.71  5070.6  229.56
  5095.9  229.65  5275.9  229.97  5356.3  231.65  5399.1  231.58  5526.5  233.76
  5540.8  233.46  5547.3  234.38  5569.3  234.76  5714.3  234.59  5830.9  235.36
#Mann=5,-1,0
  4104.4     0.1       0  4997.0    0.07       0  5003.0     0.1       0
  5095.9    0.05       0  5714.3    0.08       0
Bank Sta=4997,5003
Exp/Cntr=0.3,0.1

Type RM Length L Ch R = 1,4932,621,621,621
BEGIN DESCRIPTION:
Mapping XS 1db06e79
END DESCRIPTION:
XS GIS Cut Line= 4
      2261551.12     13213500.64      2261425.85     13212914.36
      2261052.52     13212536.03      2260343.45     13212292.99
#Sta/Elev= 30
  4235.4  231.41  4300.6  229.91  4392.7  229.18  4463.1  227.85  4484.7  228.25
  4834.9  226.42  4888.4  225.72  4902.5  226.13  4938.8  225.86  4966.2  225.77
  4973.2  224.73  4987.4  225.06  5005.3  224.31  5008.6  224.43  5019.8  222.57
  5022.5  222.07  5025.8  222.57  5029.8  224.91  5072.2  224.76  5086.4  224.04
  5100.5  225.17  5128.8  225.69  5171.2  225.56  5178.3  226.21  5185.4  225.39
  5199.5  225.88  5262.6  226.03  5409.3  226.60  5635.8  225.97  6116.0  228.94
#Mann=6,-1,0
  4235.4     0.1       0  4938.8    0.05       0  5005.3     0.1       0
  5019.8    0.03       0  5025.8     0.1       0  5262.6    0.05       0
Bank Sta=5019.8,5025.8
Exp/Cntr=0.3,0.1

Type RM Length L Ch R = 1,4311,519,519,519
BEGIN DESCRIPTION:
UNT 061 IN LACR 8.0
END DESCRIPTION:
XS GIS Cut Line= 3
      2261535.45     13213168.50      2261535.45     13212637.26
      2261290.91     13212101.36
#Sta/Elev= 30
  4180.3  227.47  4593.3  224.99  4631.9  224.11  4681.9  225.92  4740.8  226.79
  4756.0  227.96  4799.6  227.89  4815.4  227.09  4821.9  225.63  4832.9  225.11
  4838.5  224.00  4854.9  223.57  4861.5  222.12  4867.0  223.33  4884.5  223.15
  4890.0  221.89  4898.9  221.52  4913.1  222.16  4930.6  221.39  4959.2  223.43
  4975.8  222.40  4997.8  222.74  5002.2  220.82  5005.0  220.32  5008.2  220.82
  5019.8  221.61  5028.3  223.52  5051.3  224.70  5127.1  225.90  5300.6  228.66
#Mann=6,-1,0
  4180.3     0.1       0  4593.3    0.05       0  4799.6     0.1       0
  5002.2    0.07       0  5008.2     0.1       0  5127.1    0.05       0
Bank Sta=5002.2,5008.2
Exp/Cntr=0.3,0.1

Type RM Length L Ch R = 1,3792,415,415,415
BEGIN DESCRIPTION:
UNT 061 IN LACR 7.0
END DESCRIPTION:
XS GIS Cut Line= 3
      2261683.29     13213202.54      2261880.73     13212678.92
      2261889.28     13212170.00
#Sta/Elev= 30
  4258.3  227.09  4307.1  226.39  4312.9  226.82  4318.3  226.34  4337.8  227.09
  4343.1  226.25  4373.3  226.15  4483.4  226.44  4513.7  225.07  4568.7  225.30
  4585.0  224.62  4623.8  225.07  4784.1  224.32  4803.3  224.93  4840.0  225.36
  4890.0  224.53  4930.0  221.21  4932.7  219.32  4935.5  218.82  4938.7  219.32
  5060.0  219.32  5080.0  220.19  5090.0  221.70  5100.0  222.07  5140.0  226.26
  5150.0  226.25  5170.0  227.61  5200.0  228.56  5252.8  228.23  5326.9  229.79
#Mann=6,-1,0
  4258.3     0.1       0  4784.1    0.05       0  4803.3     0.1       0
  4932.7    0.07       0  4938.7     0.1       0  5252.8    0.05       0
Bank Sta=4932.7,4938.7
Exp/Cntr=0.3,0.1

Type RM Length L Ch R = 1,3377,283,283,283
BEGIN DESCRIPTION:
Mapping XS 04255779
END DESCRIPTION:
XS GIS Cut Line= 3
      2262254.11     13213236.85      2262258.40     13212387.08
      2262121.87     13212276.14
#Sta/Elev= 30
  4360.0  227.98  4410.0  227.29  4480.0  225.19  4572.7  224.37  4620.0  224.27
  4640.0  222.49  4660.0  223.90  4794.0  222.98  4810.0  222.67  4820.0  223.43
  4830.0  226.93  4840.0  226.93  4860.0  223.95  4870.0  219.62  4877.0  219.32
  4879.7  218.82  4883.0  219.32  5030.0  219.32  5050.0  220.05  5060.0  223.63
  5068.7  223.96  5090.0  224.35  5100.0  222.48  5110.0  222.24  5190.0  224.50
  5219.3  224.49  5310.3  225.15  5316.9  225.59  5371.0  226.03  5385.7  226.29
#Mann=9,-1,0
  4360.0    0.05       0  4572.7     0.1       0  4794.0    0.05       0
  4877.0   0.033       0  4883.0    0.05       0  5068.7     0.1       0
  5219.3    0.05       0  5316.9     0.1       0  5371.0    0.05       0
Bank Sta=4877,4883
Exp/Cntr=0.3,0.1

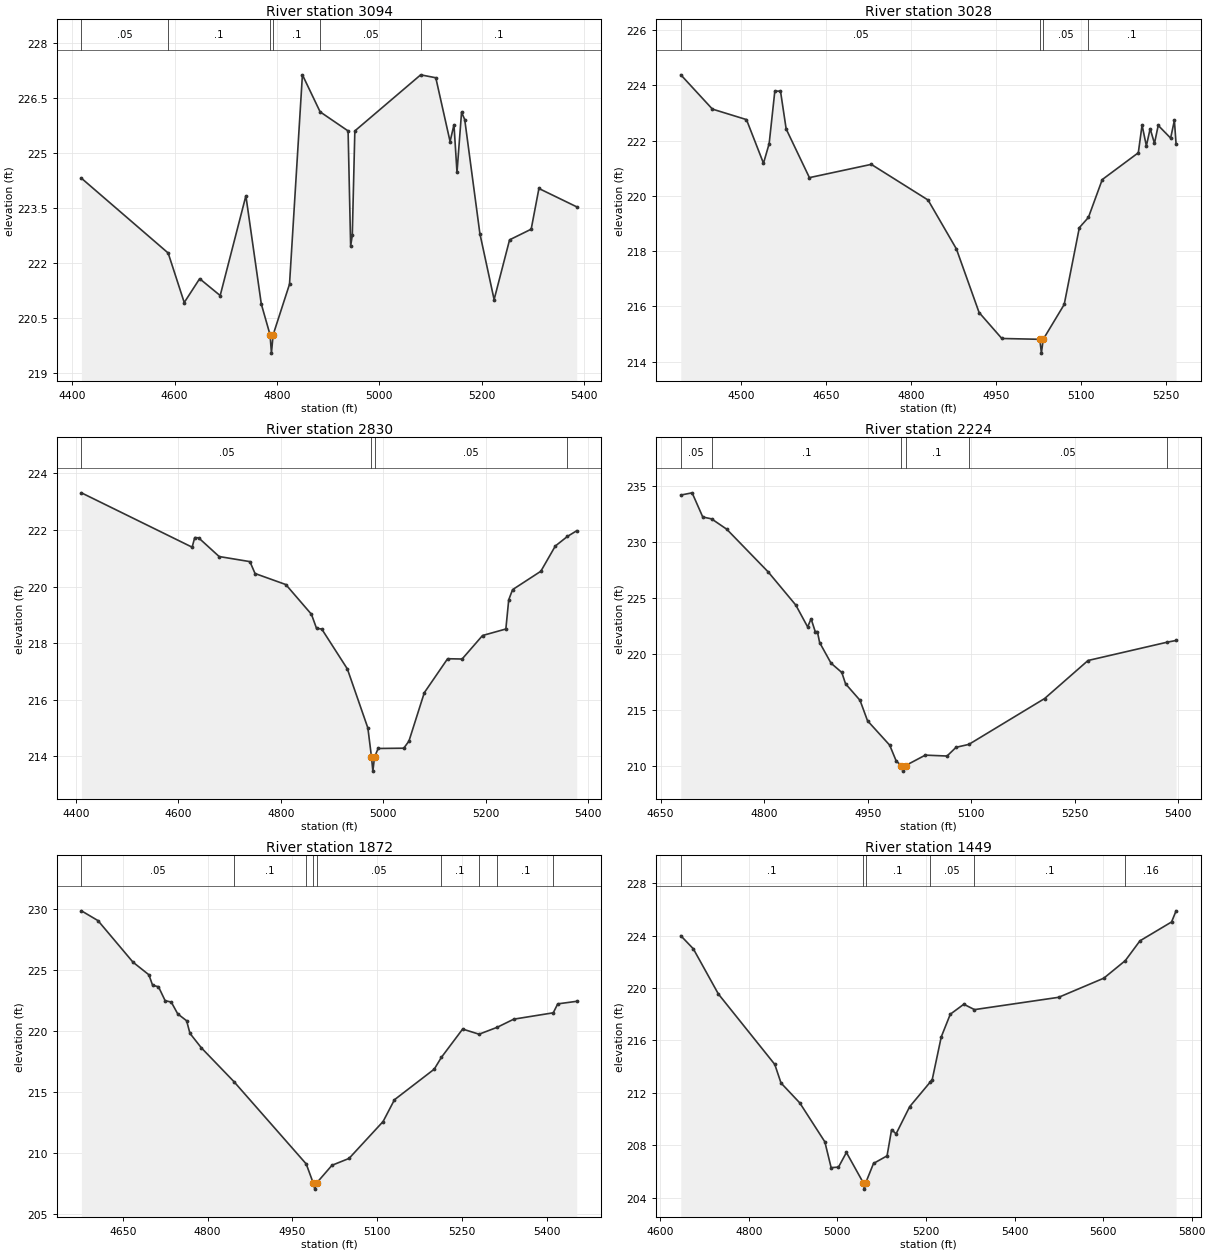
Type RM Length L Ch R = 1,3094,66,66,66
BEGIN DESCRIPTION:
UNT 061 IN LACR 6.0
END DESCRIPTION:
XS GIS Cut Line= 4
      2262498.42     13213176.92      2262542.91     13212651.87
      2262534.01     13212456.09      2262329.31     13212322.59
#Sta/Elev= 30
  4418.0  224.32  4587.4  222.28  4618.8  220.93  4648.9  221.58  4689.0  221.12
  4739.2  223.84  4769.3  220.89  4786.4  220.05  4789.1  219.55  4792.4  220.05
  4824.4  221.43  4849.6  227.14  4884.2  226.13  4938.8  225.61  4943.8  222.47
  4947.0  222.76  4952.0  225.61  5080.6  227.14  5110.1  227.06  5138.0  225.32
  5145.6  225.78  5151.5  224.48  5160.4  226.12  5166.6  225.92  5196.2  222.81
  5224.0  221.01  5254.2  222.64  5296.4  222.93  5311.5  224.04  5385.3  223.54
#Mann=6,-1,0
  4418.0    0.05       0  4587.4     0.1       0  4786.4   0.033       0
  4792.4     0.1       0  4884.2    0.05       0  5080.6     0.1       0
Bank Sta=4786.4,4792.4
Exp/Cntr=0.3,0.1

Type RM Length L Ch R = 1,3028,198,198,198
BEGIN DESCRIPTION:
Mapping XS 7a872243
END DESCRIPTION:
XS GIS Cut Line= 3
      2262584.58     13213202.55      2262610.33     13212498.66
      2262499.62     13212370.92
#Sta/Elev= 30
  4393.9  224.38  4449.6  223.14  4509.7  222.76  4539.7  221.18  4549.7  221.89
  4559.7  223.79  4569.7  223.79  4579.7  222.42  4620.7  220.66  4729.8  221.14
  4829.9  219.85  4879.9  218.08  4919.9  215.78  4960.0  214.84  5027.0  214.81
  5029.8  214.31  5033.0  214.81  5070.0  216.07  5096.7  218.85  5112.7  219.22
  5137.1  220.59  5200.7  221.56  5207.3  222.56  5214.9  221.81  5221.6  222.43
  5229.2  221.90  5235.8  222.55  5257.7  222.09  5264.3  222.73  5267.3  221.88
#Mann=4,-1,0
  4393.9    0.05       0  5027.0    0.03       0  5033.0    0.05       0
  5112.7     0.1       0
Bank Sta=5027,5033
Exp/Cntr=0.3,0.1

Type RM Length L Ch R = 1,2830,606,606,606
BEGIN DESCRIPTION:
Mapping XS cf933c40
END DESCRIPTION:
XS GIS Cut Line= 3
      2262833.50     13213185.34      2262799.17     13212490.08
      2262554.53     13212374.20
#Sta/Elev= 30
  4410.8  223.31  4626.9  221.39  4632.0  221.73  4639.6  221.72  4679.6  221.06
  4739.7  220.88  4749.7  220.46  4809.8  220.07  4859.8  219.02  4869.8  218.52
  4879.9  218.50  4929.9  217.09  4970.0  215.00  4977.0  213.98  4979.7  213.48
  4983.0  213.98  4990.0  214.28  5040.0  214.29  5050.1  214.54  5080.1  216.25
  5125.6  217.45  5153.9  217.44  5193.8  218.27  5239.3  218.50  5244.9  219.53
  5252.4  219.89  5307.6  220.54  5335.8  221.43  5359.5  221.77  5377.6  221.97
#Mann=4,-1,0
  4410.8    0.05       0  4977.0    0.03       0  4983.0    0.05       0
  5359.5     0.1       0
Bank Sta=4977,4983
Exp/Cntr=0.3,0.1

Type RM Length L Ch R = 1,2224,352,352,352
BEGIN DESCRIPTION:
UNT 061 IN LACR 5.0
END DESCRIPTION:
XS GIS Cut Line= 4
      2263224.07     13212193.95      2263026.63     13212181.07
      2262653.25     13212301.24      2262533.08     13212344.16
#Sta/Elev= 30
  4679.2  234.23  4695.6  234.43  4711.0  232.27  4723.8  232.10  4745.7  231.18
  4805.8  227.36  4845.9  224.39  4863.0  222.44  4868.0  223.17  4874.0  222.02
  4877.1  222.02  4880.4  221.04  4896.9  219.20  4912.5  218.37  4917.9  217.36
  4938.9  215.88  4949.8  214.05  4981.9  211.87  4991.5  210.43  4999.0  210.05
  5001.7  209.55  5005.0  210.05  5033.5  210.98  5065.0  210.90  5078.1  211.68
  5096.6  211.94  5206.4  216.04  5269.3  219.44  5384.2  221.08  5396.9  221.23
#Mann=6,-1,0
  4679.2    0.05       0  4723.8     0.1       0  4999.0    0.07       0
  5005.0     0.1       0  5096.6    0.05       0  5384.2     0.1       0
Bank Sta=4999,5005
Exp/Cntr=0.3,0.1

Type RM Length L Ch R = 1,1872,423,423,423
BEGIN DESCRIPTION:
UNT 061 IN LACR 4.0
END DESCRIPTION:
XS GIS Cut Line= 3
      2263090.99     13212043.72      2262923.63     13211962.19
      2262236.96     13212035.15
#Sta/Elev= 30
  4576.6  229.82  4605.9  229.02  4667.9  225.62  4696.0  224.59  4702.6  223.73
  4713.0  223.61  4724.8  222.47  4735.6  222.36  4747.1  221.39  4762.8  220.83
  4768.7  219.80  4788.8  218.62  4846.4  215.86  4974.5  209.12  4986.9  207.56
  4989.7  207.06  4992.9  207.56  5020.1  209.01  5050.3  209.57  5110.6  212.59
  5130.7  214.37  5201.1  216.87  5213.7  217.83  5251.4  220.15  5280.5  219.73
  5312.8  220.30  5341.9  220.96  5411.8  221.48  5419.7  222.21  5453.3  222.42
#Mann=9,-1,0
  4576.6    0.05       0  4846.4     0.1       0  4974.5    0.05       0
  4986.9    0.03       0  4992.9    0.05       0  5213.7     0.1       0
  5280.5    0.05       0  5312.8     0.1       0  5411.8    0.05       0
Bank Sta=4986.9,4992.9
Exp/Cntr=0.3,0.1

Type RM Length L Ch R = 1,1449,463,463,463
BEGIN DESCRIPTION:
UNT 061 IN LACR 3.0
END DESCRIPTION:
XS GIS Cut Line= 3
      2263037.75     13211896.89      2262787.72     13211646.85
      2262037.67     13211796.86
#Sta/Elev= 30
  4646.4  223.99  4674.7  222.99  4731.3  219.54  4858.6  214.17  4872.7  212.75
  4915.1  211.23  4971.7  208.26  4985.9  206.29  5002.5  206.33  5020.4  207.45
  5058.2  205.15  5060.9  204.65  5064.2  205.15  5081.6  206.61  5112.2  207.19
  5122.4  209.19  5132.6  208.87  5163.2  210.94  5208.9  212.79  5214.2  213.01
  5234.6  216.27  5255.0  218.00  5285.5  218.76  5309.6  218.35  5499.7  219.29
  5601.7  220.75  5650.2  222.09  5683.3  223.60  5754.7  225.04  5764.9  225.89
#Mann=6,-1,0
  4646.4     0.1       0  5058.2    0.07       0  5064.2     0.1       0
  5208.9    0.05       0  5309.6     0.1       0  5650.2    0.16       0
Bank Sta=5058.2,5064.2
Exp/Cntr=0.3,0.1

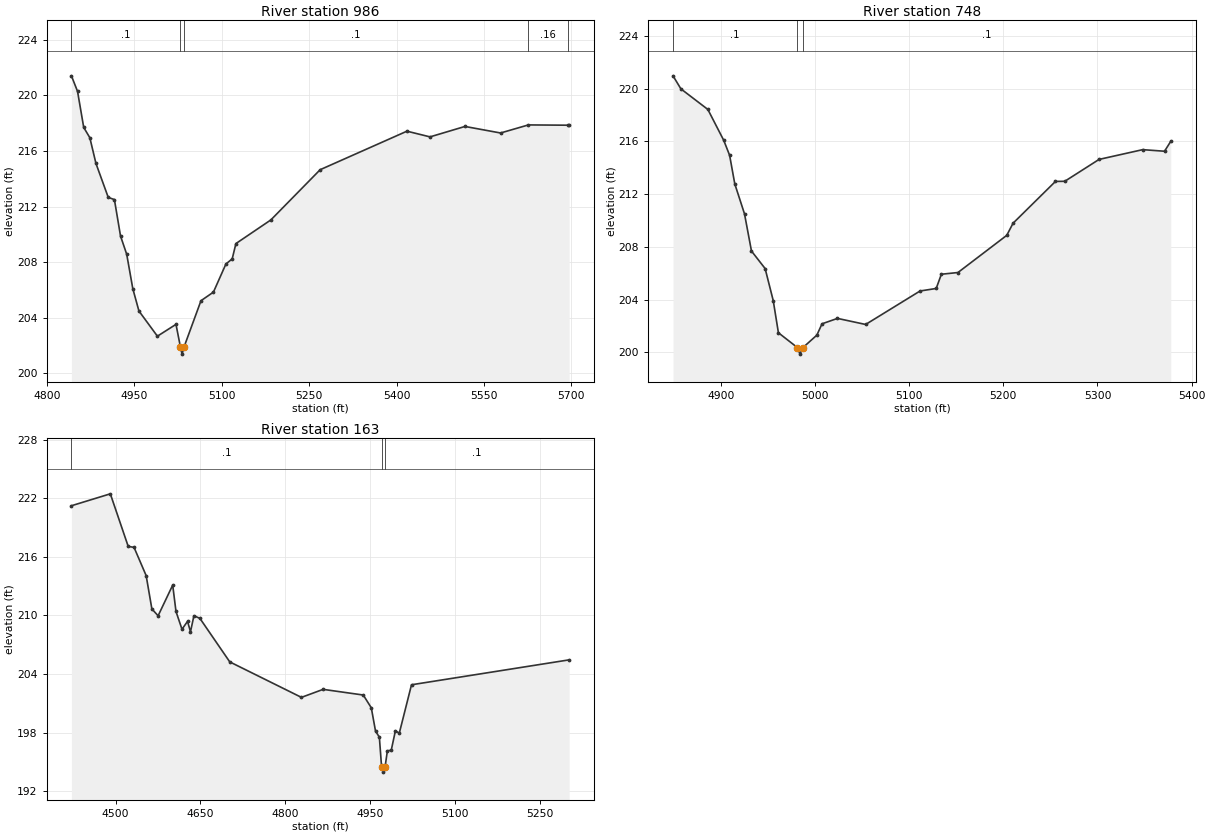
Type RM Length L Ch R = 1,986,238,238,238
BEGIN DESCRIPTION:
UNT 061 IN LACR 2.0
END DESCRIPTION:
XS GIS Cut Line= 3
      2263187.71     13211296.86      2263037.72     13211346.86
      2262387.74     13211596.85
#Sta/Elev= 30
  4841.9  221.40  4852.4  220.28  4863.0  217.69  4873.5  216.95  4884.0  215.10
  4905.1  212.66  4915.7  212.50  4926.2  209.88  4936.8  208.57  4947.3  206.09
  4957.8  204.49  4989.5  202.68  5021.4  203.53  5029.1  201.89  5031.9  201.39
  5035.1  201.89  5064.3  205.23  5085.7  205.85  5107.1  207.87  5117.9  208.24
  5124.3  209.34  5184.3  211.04  5268.9  214.65  5417.9  217.42  5457.5  217.01
  5517.5  217.76  5578.6  217.29  5626.4  217.87  5693.9  217.85  5696.4  217.85
#Mann=5,-1,0
  4841.9     0.1       0  5029.1    0.07       0  5035.1     0.1       0
  5626.4    0.16       0  5693.9     0.1       0
Bank Sta=5029.1,5035.1
Exp/Cntr=0.3,0.1

Type RM Length L Ch R = 1,748,585,585,585
BEGIN DESCRIPTION:
Mapping XS 6d229e79
END DESCRIPTION:
XS GIS Cut Line= 2
      2263076.91     13211086.87      2262595.13     13211303.89
#Sta/Elev= 30
  4849.4  220.98  4857.8  219.99  4886.4  218.43  4903.3  216.08  4909.5  214.95
  4915.0  212.78  4925.3  210.51  4932.7  207.69  4947.2  206.36  4955.8  203.93
  4961.3  201.49  4981.4  200.37  4984.2  199.87  4987.4  200.37  5002.1  201.31
  5007.6  202.17  5024.0  202.58  5053.9  202.12  5111.7  204.66  5128.8  204.85
  5134.3  205.93  5151.9  206.06  5203.7  208.88  5210.4  209.80  5255.4  212.97
  5265.3  212.98  5301.7  214.64  5348.0  215.38  5371.2  215.26  5377.8  216.01
#Mann=3,-1,0
  4849.4     0.1       0  4981.4    0.07       0  4987.4     0.1       0
Bank Sta=4981.4,4987.4
Exp/Cntr=0.3,0.1

Type RM Length L Ch R = 1,163,0,0,0
BEGIN DESCRIPTION:
UNT 061 IN LACR 1.0
END DESCRIPTION:
XS GIS Cut Line= 3
      2263202.79     13211008.77      2262803.45     13210874.21
      2262464.91     13210566.05
#Sta/Elev= 30
  4422.1  221.23  4490.8  222.45  4522.4  217.07  4532.7  216.97  4554.1  214.08
  4564.2  210.67  4575.2  209.97  4601.0  213.11  4606.8  210.41  4617.4  208.59
  4627.2  209.40  4632.4  208.33  4638.5  209.98  4649.1  209.70  4701.8  205.25
  4828.4  201.62  4866.7  202.44  4937.6  201.86  4951.8  200.55  4959.3  198.15
  4966.0  197.56  4970.0  194.47  4972.7  193.97  4976.0  194.47  4980.2  196.15
  4987.0  196.21  4994.4  198.21  5001.2  197.95  5022.8  202.91  5301.3  205.46
#Mann=3,-1,0
  4422.1     0.1       0  4970.0    0.07       0  4976.0     0.1       0
Bank Sta=4970,4976
Exp/Cntr=0.3,0.1

Chan Stop Cuts=-1