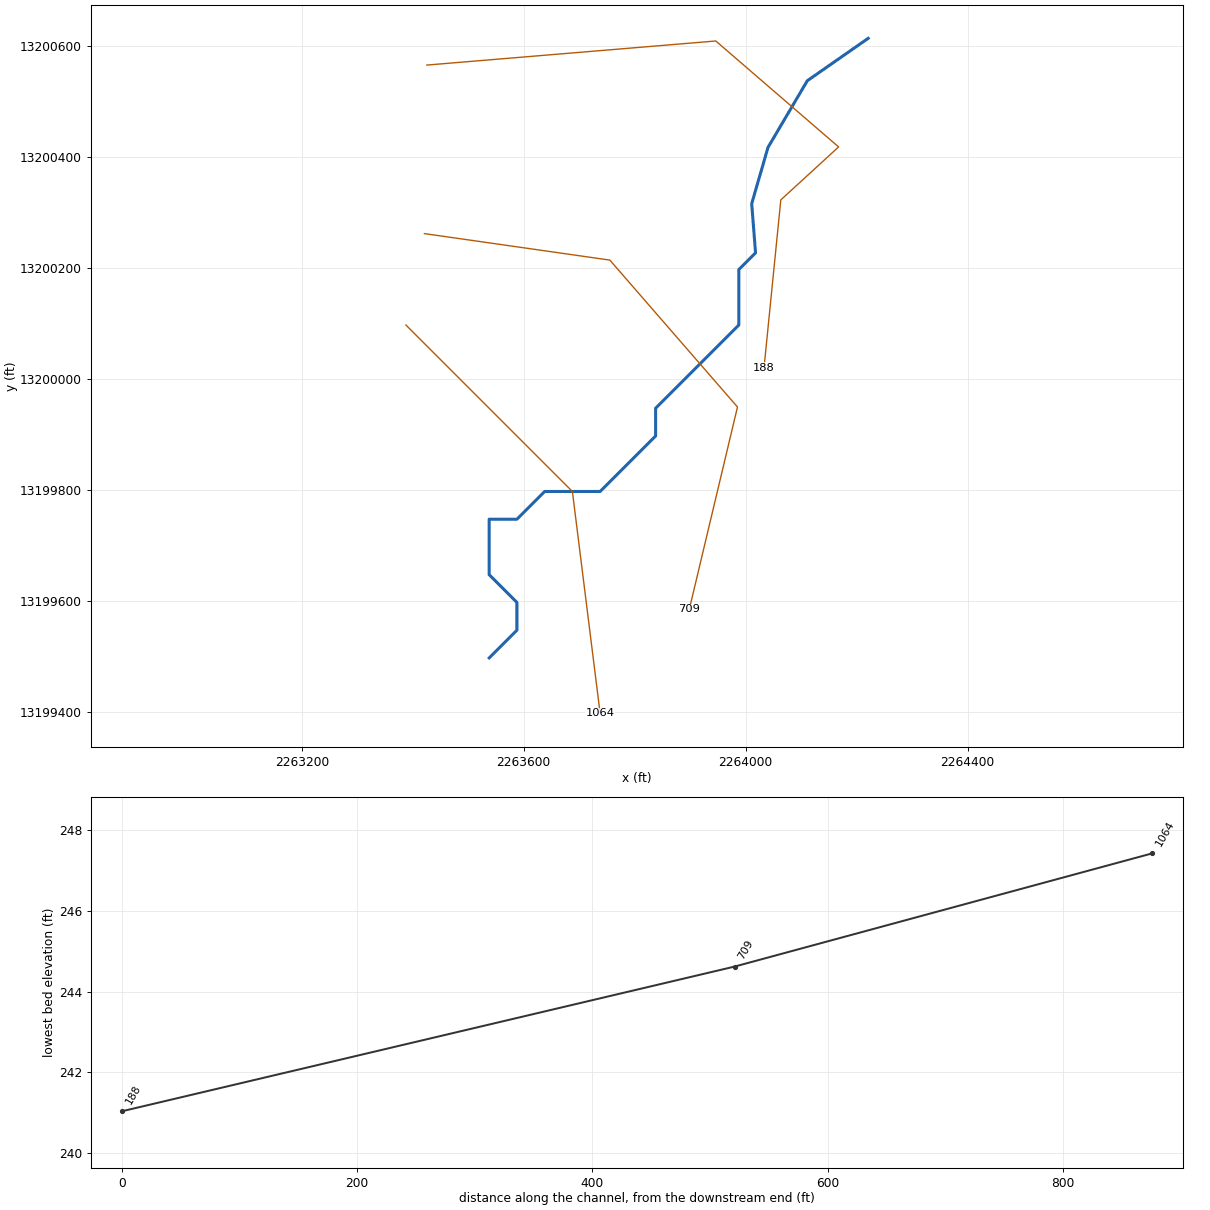
--- UNT 062 IN LACR.prj (project) ---

Proj Title=UNT 062 IN LACR Base Level Engineering
Current Plan=p01
Default Exp/Contr=0.3,0.1
English Units
Geom File=g01
Flow File=f01
Plan File=p01
BEGIN DESCRIPTION:
UNT 062 IN LACR
END DESCRIPTION:

--- UNT 062 IN LACR.p01 (plan) ---

Plan Title=Multiple Run
Short Identifier=Multiple
Geom File=g01
Flow File=f01
Subcritical Flow
K Sum by GR= 0
Std Step Tol= 0.01
Critical Tol= 0.01
Num of Std Step Trials= 20
Max Error Tol= 0.3
Flow Tol Ratio= 0.001
Split Flow NTrial= 30
Split Flow Tol= 0.02
Split Flow Ratio= 0.02
Log Output Level= 0
Friction Slope Method= 1
Unsteady Friction Slope Method= 2
Unsteady Bridges Friction Slope Method= 1
Parabolic Critical Depth
Global Vel Dist=  1 , 1 , 1
Global Log Level= 0
CheckData=True
Encroach Param= -1, 0, 0, 0
BEGIN DESCRIPTION:
Multiple Run
END DESCRIPTION:

--- UNT 062 IN LACR.f01 (steady flow) ---

Flow Title=Multiple
Number of Profiles=7
Profile Names=10-year,25-year,50-year,1pct_min,100-year,1pct_plu,500-year
River Rch & RM= UNT 062 IN LACR,Reach-1,1064
      97     127     150     131     177     239     250
River Rch & RM= UNT 062 IN LACR,Reach-1,188
     233     320     391     352     476     644     715
Boundary for River Rch & Prof#=UNT 062 IN LACR,Reach-1,1
Up Type=0
Dn Type=3
Dn Slope=0.005
Boundary for River Rch & Prof#=UNT 062 IN LACR,Reach-1,2
Up Type=0
Dn Type=3
Dn Slope=0.005
Boundary for River Rch & Prof#=UNT 062 IN LACR,Reach-1,3
Up Type=0
Dn Type=3
Dn Slope=0.005
Boundary for River Rch & Prof#=UNT 062 IN LACR,Reach-1,4
Up Type=0
Dn Type=3
Dn Slope=0.005
Boundary for River Rch & Prof#=UNT 062 IN LACR,Reach-1,5
Up Type=0
Dn Type=3
Dn Slope=0.005
Boundary for River Rch & Prof#=UNT 062 IN LACR,Reach-1,6
Up Type=0
Dn Type=3
Dn Slope=0.005
Boundary for River Rch & Prof#=UNT 062 IN LACR,Reach-1,7
Up Type=0
Dn Type=3
Dn Slope=0.005

--- UNT 062 IN LACR.g01 (geometry) ---

Geom Title=Existing Conditions

River Reach=UNT 062 IN LACR,Reach-1
Reach XY= 23
      2263537.72     13199496.85      2263587.72     13199546.86
      2263587.72     13199596.85      2263537.72     13199646.85
      2263537.72     13199696.86      2263537.72     13199746.85
      2263587.72     13199746.85      2263637.72     13199796.85
      2263687.72     13199796.85      2263737.72     13199796.85
      2263787.72     13199846.86      2263837.72     13199896.85
      2263837.72     13199946.85      2263887.72     13199996.85
      2263937.72     13200046.85      2263987.72     13200096.85
      2263987.72     13200146.85      2263987.72     13200196.86
      2264017.88     13200227.02      2264010.95     13200315.64
      2264040.34     13200417.09      2264111.17     13200537.23
      2264220.92     13200613.65

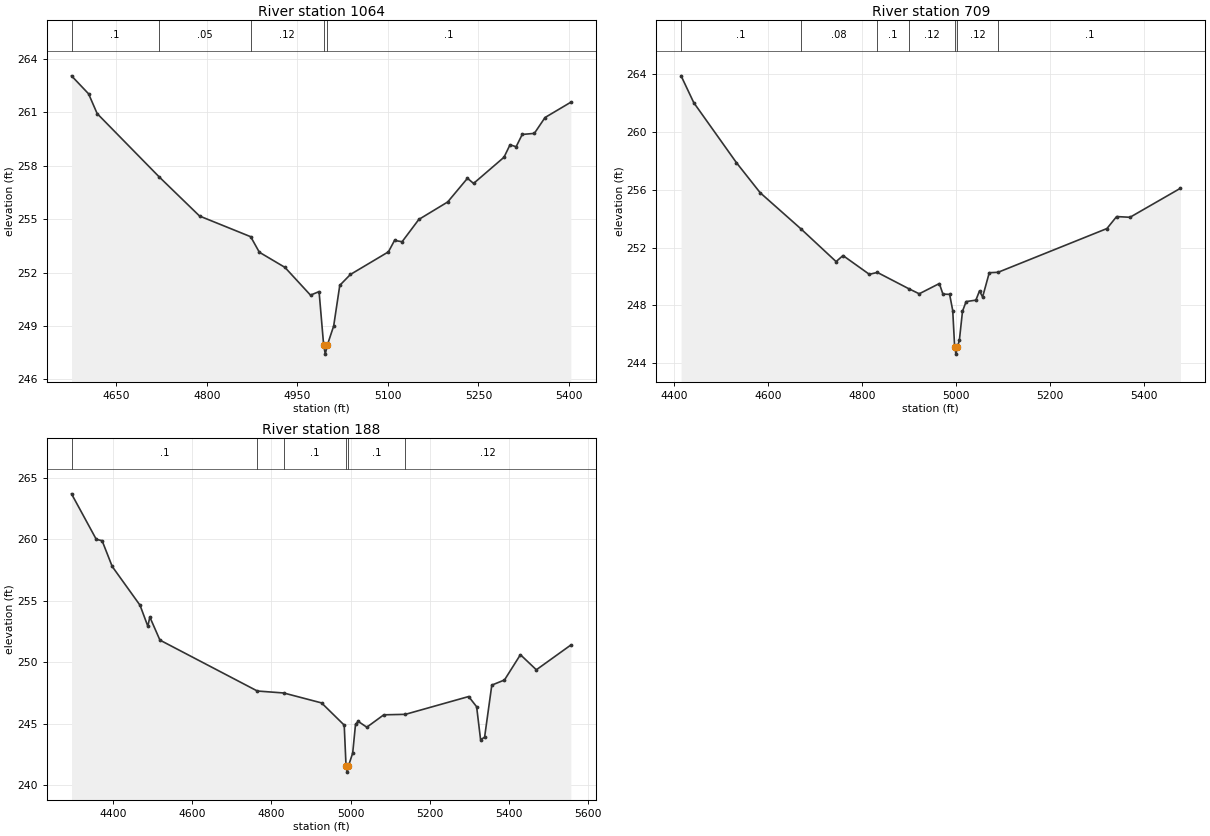
Type RM Length L Ch R = 1,1064,355,355,355
BEGIN DESCRIPTION:
UNT 062 IN LACR 1.0
END DESCRIPTION:
XS GIS Cut Line= 3
      2263387.70     13200096.88      2263687.72     13199796.85
      2263737.72     13199396.87
#Sta/Elev= 30
  4575.7  263.04  4604.0  262.03  4618.2  260.92  4720.6  257.38  4787.9  255.17
  4872.6  254.01  4886.9  253.14  4929.3  252.29  4971.7  250.73  4985.9  250.93
  4993.5  247.92  4996.2  247.42  4999.5  247.92  5010.1  249.00  5020.2  251.28
  5037.8  251.89  5100.8  253.16  5110.9  253.80  5123.5  253.73  5151.2  254.98
  5199.0  255.96  5231.8  257.29  5241.9  257.00  5292.3  258.47  5302.3  259.17
  5312.4  259.06  5322.5  259.75  5342.6  259.81  5360.3  260.70  5403.1  261.56
#Mann=5,-1,0
  4575.7     0.1       0  4720.6    0.05       0  4872.6    0.12       0
  4993.5    0.07       0  4999.5     0.1       0
Bank Sta=4993.5,4999.5
Exp/Cntr=0.3,0.1

Type RM Length L Ch R = 1,709,521,521,521
BEGIN DESCRIPTION:
Mapping XS d2375db3
END DESCRIPTION:
XS GIS Cut Line= 4
      2263421.00     13200261.66      2263755.25     13200213.91
      2263985.29     13199949.15      2263898.49     13199584.62
#Sta/Elev= 30
  4414.6  263.90  4441.6  262.04  4532.5  257.88  4583.0  255.80  4669.7  253.30
  4744.6  251.03  4759.3  251.45  4815.3  250.15  4832.5  250.28  4898.8  249.16
  4921.6  248.80  4964.4  249.51  4972.0  248.78  4986.3  248.76  4992.9  247.64
  4997.0  245.12  4999.8  244.62  5003.0  245.12  5007.1  245.60  5013.7  247.59
  5021.4  248.26  5042.2  248.36  5049.9  249.00  5056.5  248.58  5070.7  250.26
  5089.5  250.29  5321.2  253.32  5341.8  254.15  5370.3  254.10  5477.7  256.11
#Mann=7,-1,0
  4414.6     0.1       0  4669.7    0.08       0  4832.5     0.1       0
  4898.8    0.12       0  4997.0    0.07       0  5003.0    0.12       0
  5089.5     0.1       0
Bank Sta=4997,5003
Exp/Cntr=0.3,0.1

Type RM Length L Ch R = 1,188,0,0,0
BEGIN DESCRIPTION:
UNT 062 IN LACR 2.0
END DESCRIPTION:
XS GIS Cut Line= 5
      2263425.41     13200565.47      2263946.22     13200608.87
      2264167.58     13200417.90      2264063.41     13200322.42
      2264033.19     13200020.20
#Sta/Elev= 30
  4296.0  263.72  4358.5  260.01  4373.2  259.90  4398.7  257.80  4468.9  254.64
  4488.6  252.93  4493.6  253.68  4519.1  251.80  4764.9  247.65  4831.4  247.49
  4927.0  246.68  4984.1  244.87  4988.7  241.54  4991.5  241.04  4994.7  241.54
  5005.5  242.59  5012.6  244.93  5019.2  245.18  5041.1  244.70  5083.9  245.71
  5138.5  245.75  5298.1  247.20  5318.2  246.37  5328.2  243.69  5338.3  243.88
  5356.5  248.13  5388.5  248.55  5428.7  250.61  5468.9  249.38  5556.0  251.40
#Mann=6,-1,0
  4296.0     0.1       0  4764.9    0.08       0  4831.4     0.1       0
  4988.7    0.07       0  4994.7     0.1       0  5138.5    0.12       0
Bank Sta=4988.7,4994.7
Exp/Cntr=0.3,0.1

Chan Stop Cuts=-1