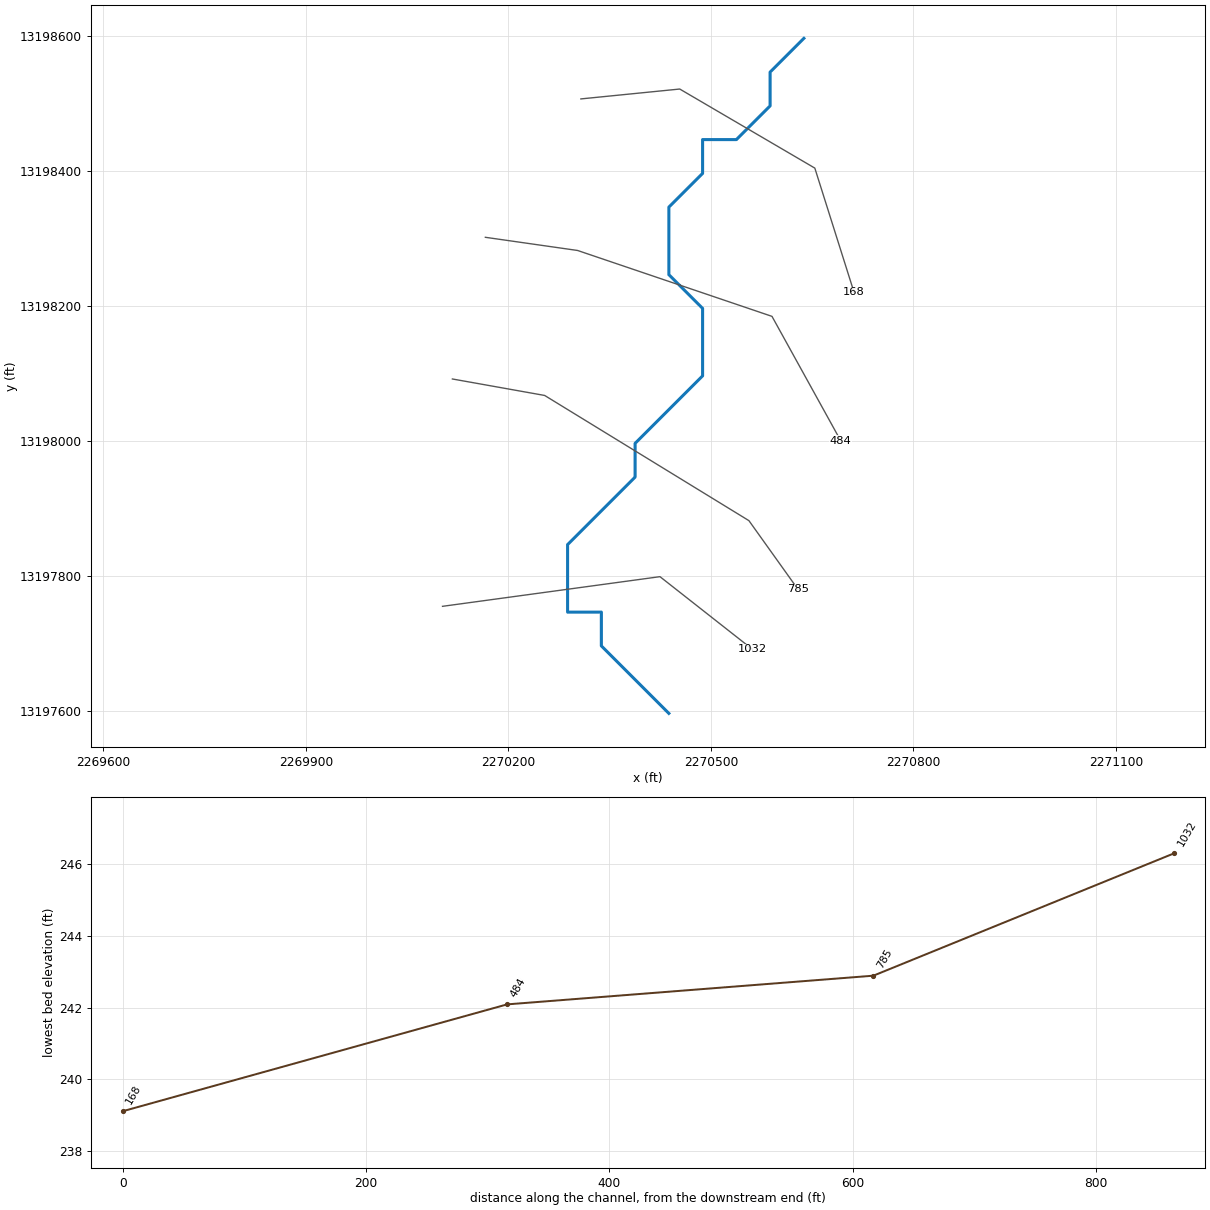
--- UNT 064 IN LACR.prj (project) ---

Proj Title=UNT 064 IN LACR Base Level Engineering
Current Plan=p01
Default Exp/Contr=0.3,0.1
English Units
Geom File=g01
Flow File=f01
Plan File=p01
BEGIN DESCRIPTION:
UNT 064 IN LACR
END DESCRIPTION:

--- UNT 064 IN LACR.p01 (plan) ---

Plan Title=Multiple Run
Short Identifier=Multiple
Geom File=g01
Flow File=f01
Subcritical Flow
K Sum by GR= 0
Std Step Tol= 0.01
Critical Tol= 0.01
Num of Std Step Trials= 20
Max Error Tol= 0.3
Flow Tol Ratio= 0.001
Split Flow NTrial= 30
Split Flow Tol= 0.02
Split Flow Ratio= 0.02
Log Output Level= 0
Friction Slope Method= 1
Unsteady Friction Slope Method= 2
Unsteady Bridges Friction Slope Method= 1
Parabolic Critical Depth
Global Vel Dist=  1 , 1 , 1
Global Log Level= 0
CheckData=True
Encroach Param= -1, 0, 0, 0
BEGIN DESCRIPTION:
Multiple Run
END DESCRIPTION:

--- UNT 064 IN LACR.f01 (steady flow) ---

Flow Title=Multiple
Number of Profiles=7
Profile Names=10-year,25-year,50-year,1pct_min,100-year,1pct_plu,500-year
River Rch & RM= UNT 064 IN LACR,Reach-1,1032
     135     180     216     191     258     349     375
Boundary for River Rch & Prof#=UNT 064 IN LACR,Reach-1,1
Up Type=0
Dn Type=3
Dn Slope=0.005
Boundary for River Rch & Prof#=UNT 064 IN LACR,Reach-1,2
Up Type=0
Dn Type=3
Dn Slope=0.005
Boundary for River Rch & Prof#=UNT 064 IN LACR,Reach-1,3
Up Type=0
Dn Type=3
Dn Slope=0.005
Boundary for River Rch & Prof#=UNT 064 IN LACR,Reach-1,4
Up Type=0
Dn Type=3
Dn Slope=0.005
Boundary for River Rch & Prof#=UNT 064 IN LACR,Reach-1,5
Up Type=0
Dn Type=3
Dn Slope=0.005
Boundary for River Rch & Prof#=UNT 064 IN LACR,Reach-1,6
Up Type=0
Dn Type=3
Dn Slope=0.005
Boundary for River Rch & Prof#=UNT 064 IN LACR,Reach-1,7
Up Type=0
Dn Type=3
Dn Slope=0.005

--- UNT 064 IN LACR.g01 (geometry) ---

Geom Title=Existing Conditions

River Reach=UNT 064 IN LACR,Reach-1
Reach XY= 23
      2270437.72     13197596.85      2270387.72     13197646.85
      2270337.72     13197696.85      2270337.72     13197746.86
      2270287.72     13197746.86      2270287.72     13197796.85
      2270287.72     13197846.85      2270337.72     13197896.86
      2270387.72     13197946.85      2270387.72     13197996.85
      2270437.72     13198046.86      2270487.72     13198096.85
      2270487.72     13198146.85      2270487.72     13198196.85
      2270437.72     13198246.85      2270437.72     13198296.85
      2270437.72     13198346.85      2270487.72     13198396.86
      2270487.72     13198446.85      2270537.72     13198446.85
      2270587.72     13198496.85      2270587.72     13198546.86
      2270637.72     13198596.85

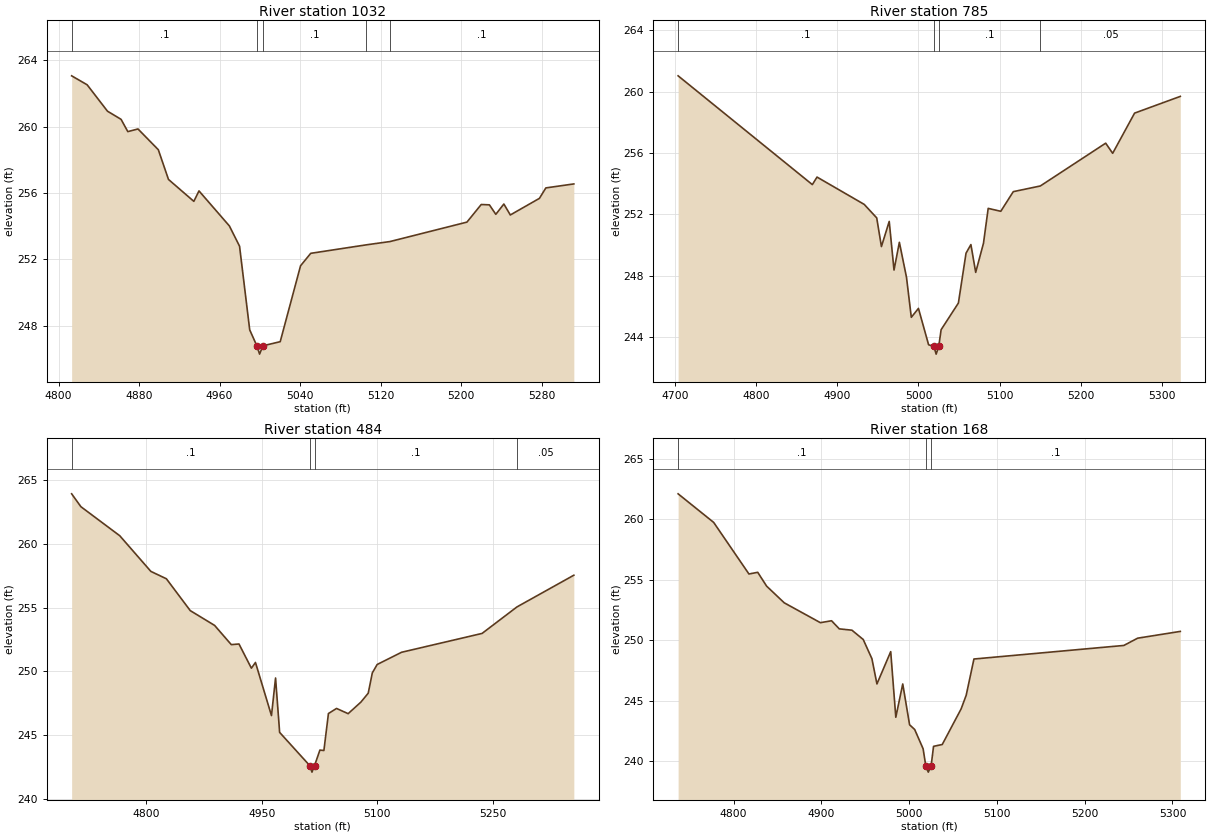
Type RM Length L Ch R = 1,1032,247,247,247
BEGIN DESCRIPTION:
UNT 064 IN LACR 2.0
END DESCRIPTION:
XS GIS Cut Line= 3
      2270102.44     13197755.44      2270424.56     13197799.37
      2270561.22     13197692.00
#Sta/Elev= 30
  4813.0  263.06  4828.4  262.52  4848.6  260.93  4862.1  260.44  4868.8  259.70
  4878.9  259.86  4899.1  258.61  4909.2  256.82  4934.4  255.50  4939.5  256.13
  4969.7  254.02  4979.8  252.80  4989.9  247.76  4997.0  246.80  4999.7  246.30
  5003.0  246.80  5020.2  247.05  5040.4  251.62  5050.5  252.37  5105.6  252.88
  5129.3  253.08  5205.7  254.25  5219.9  255.31  5228.0  255.29  5234.4  254.72
  5242.4  255.34  5248.8  254.68  5277.7  255.68  5284.1  256.31  5311.9  256.55
#Mann=5,-1,0
  4813.0     0.1       0  4997.0    0.07       0  5003.0     0.1       0
  5105.6    0.16       0  5129.3     0.1       0
Bank Sta=4997,5003
Exp/Cntr=0.3,0.1

Type RM Length L Ch R = 1,785,301,301,301
BEGIN DESCRIPTION:
Mapping XS 9dd2c34a
END DESCRIPTION:
XS GIS Cut Line= 4
      2270117.05     13198092.23      2270253.73     13198067.82
      2270556.35     13197882.35      2270628.84     13197780.86
#Sta/Elev= 30
  4704.0  261.03  4869.3  253.94  4875.1  254.43  4933.2  252.65  4948.6  251.77
  4954.4  249.90  4964.0  251.54  4969.9  248.37  4976.5  250.18  4985.3  247.89
  4991.2  245.29  5000.0  245.87  5012.5  243.50  5019.0  243.39  5021.8  242.89
  5025.0  243.39  5027.9  244.48  5049.2  246.22  5058.6  249.47  5064.6  250.03
  5070.5  248.22  5080.1  250.12  5085.9  252.39  5101.4  252.20  5116.8  253.48
  5150.1  253.85  5230.6  256.64  5239.2  255.98  5266.2  258.60  5322.5  259.69
#Mann=4,-1,0
  4704.0     0.1       0  5019.0    0.07       0  5025.0     0.1       0
  5150.1    0.05       0
Bank Sta=5019,5025
Exp/Cntr=0.3,0.1

Type RM Length L Ch R = 1,484,316,316,316
BEGIN DESCRIPTION:
Mapping XS 84ed558f
END DESCRIPTION:
XS GIS Cut Line= 4
      2270165.89     13198302.11      2270302.54     13198282.59
      2270590.52     13198184.97      2270692.23     13198000.91
#Sta/Elev= 30
  4703.1  263.94  4715.1  262.93  4765.6  260.65  4806.0  257.85  4826.2  257.27
  4857.2  254.77  4888.8  253.61  4910.5  252.10  4920.5  252.15  4936.6  250.25
  4941.9  250.70  4962.7  246.53  4968.0  249.48  4973.3  245.21  5012.6  242.59
  5015.3  242.09  5018.6  242.59  5025.6  243.82  5030.8  243.79  5036.7  246.69
  5047.2  247.09  5062.3  246.68  5078.9  247.59  5088.4  248.29  5093.7  249.88
  5100.0  250.54  5131.7  251.50  5236.3  252.98  5281.6  255.06  5355.5  257.55
#Mann=4,-1,0
  4703.1     0.1       0  5012.6    0.07       0  5018.6     0.1       0
  5281.6    0.05       0
Bank Sta=5012.6,5018.6
Exp/Cntr=0.3,0.1

Type RM Length L Ch R = 1,168,0,0,0
BEGIN DESCRIPTION:
UNT 064 IN LACR 1.0
END DESCRIPTION:
XS GIS Cut Line= 4
      2270307.42     13198507.11      2270453.85     13198521.75
      2270653.97     13198404.61      2270712.10     13198220.51
#Sta/Elev= 30
  4736.8  262.09  4777.3  259.73  4817.5  255.47  4827.5  255.61  4837.6  254.47
  4857.7  253.09  4898.9  251.45  4911.6  251.61  4920.4  250.94  4934.8  250.83
  4947.7  250.06  4957.6  248.47  4963.3  246.39  4979.0  249.06  4984.8  243.64
  4992.7  246.39  5000.5  243.02  5006.3  242.63  5015.9  241.04  5019.0  239.61
  5021.8  239.11  5025.0  239.61  5027.8  241.24  5037.7  241.39  5059.2  244.33
  5065.0  245.46  5073.8  248.45  5244.6  249.57  5260.3  250.17  5308.9  250.73
#Mann=3,-1,0
  4736.8     0.1       0  5019.0    0.07       0  5025.0     0.1       0
Bank Sta=5019,5025
Exp/Cntr=0.3,0.1

Chan Stop Cuts=-1