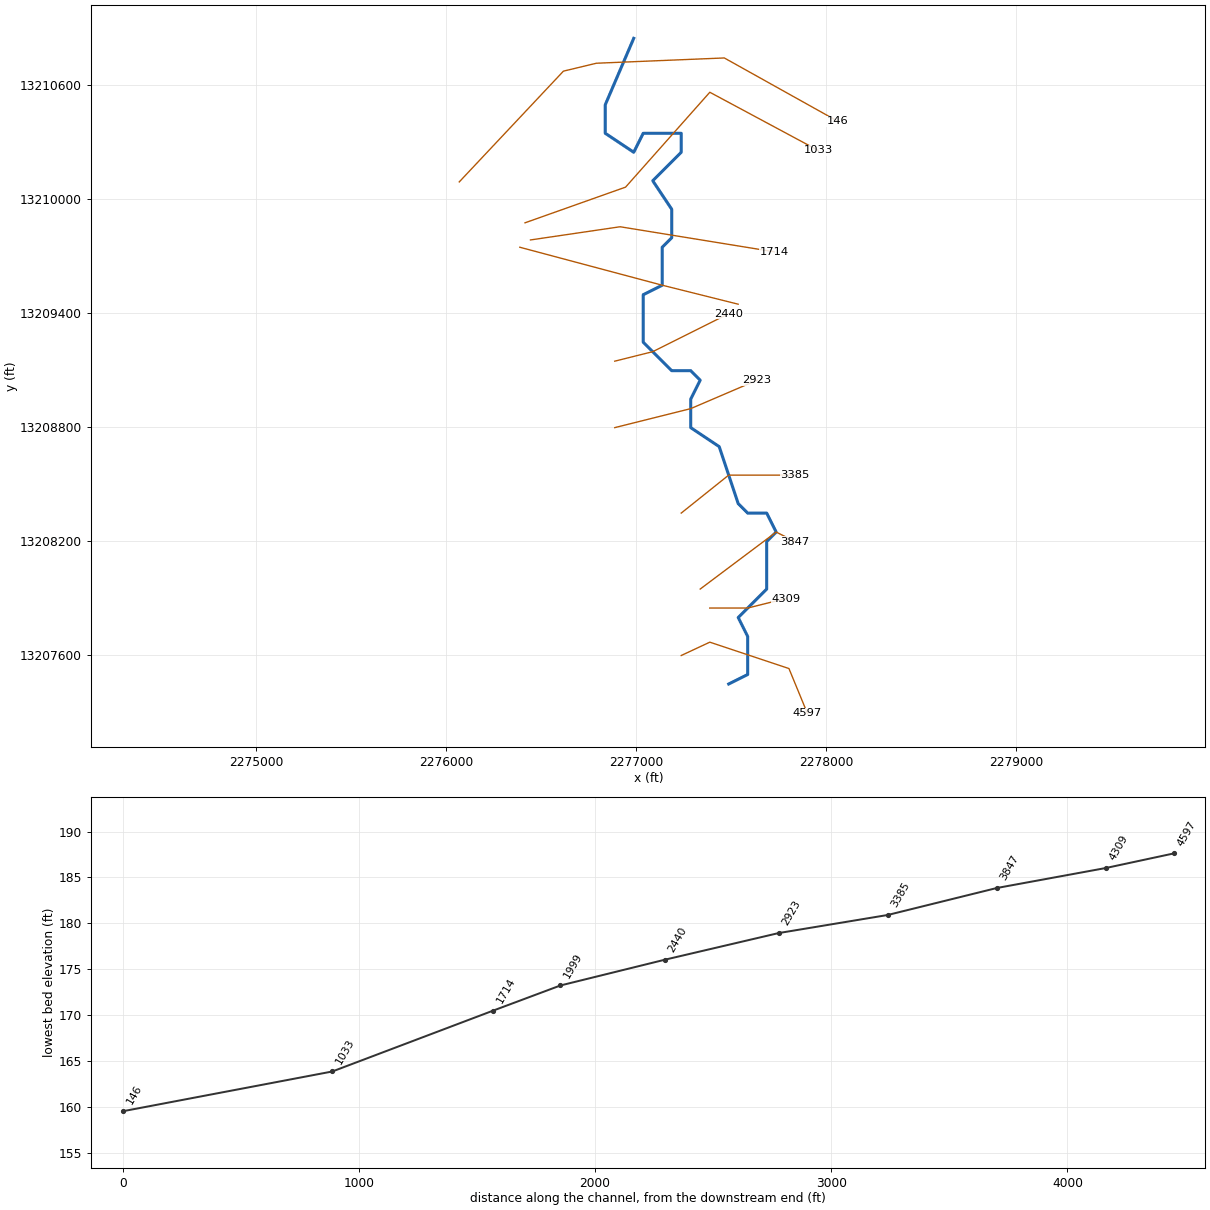
--- UNT 065 IN LACR.prj (project) ---

Proj Title=UNT 065 IN LACR Base Level Engineering
Current Plan=p01
Default Exp/Contr=0.3,0.1
English Units
Geom File=g01
Flow File=f01
Plan File=p01
BEGIN DESCRIPTION:
UNT 065 IN LACR
END DESCRIPTION:

--- UNT 065 IN LACR.p01 (plan) ---

Plan Title=Multiple Run
Short Identifier=Multiple
Geom File=g01
Flow File=f01
Subcritical Flow
K Sum by GR= 0
Std Step Tol= 0.01
Critical Tol= 0.01
Num of Std Step Trials= 20
Max Error Tol= 0.3
Flow Tol Ratio= 0.001
Split Flow NTrial= 30
Split Flow Tol= 0.02
Split Flow Ratio= 0.02
Log Output Level= 0
Friction Slope Method= 1
Unsteady Friction Slope Method= 2
Unsteady Bridges Friction Slope Method= 1
Parabolic Critical Depth
Global Vel Dist=  1 , 1 , 1
Global Log Level= 0
CheckData=True
Encroach Param= -1, 0, 0, 0
BEGIN DESCRIPTION:
Multiple Run
END DESCRIPTION:

--- UNT 065 IN LACR.f01 (steady flow) ---

Flow Title=Multiple
Number of Profiles=7
Profile Names=10-year,25-year,50-year,1pct_min,100-year,1pct_plu,500-year
River Rch & RM= UNT 065 IN LACR,Reach-1,4597
     236     327     403     365     493     667     752
River Rch & RM= UNT 065 IN LACR,Reach-1,3847
     343     484     602     552     746    1009    1162
Boundary for River Rch & Prof#=UNT 065 IN LACR,Reach-1,1
Up Type=0
Dn Type=3
Dn Slope=0.005
Boundary for River Rch & Prof#=UNT 065 IN LACR,Reach-1,2
Up Type=0
Dn Type=3
Dn Slope=0.005
Boundary for River Rch & Prof#=UNT 065 IN LACR,Reach-1,3
Up Type=0
Dn Type=3
Dn Slope=0.005
Boundary for River Rch & Prof#=UNT 065 IN LACR,Reach-1,4
Up Type=0
Dn Type=3
Dn Slope=0.005
Boundary for River Rch & Prof#=UNT 065 IN LACR,Reach-1,5
Up Type=0
Dn Type=3
Dn Slope=0.005
Boundary for River Rch & Prof#=UNT 065 IN LACR,Reach-1,6
Up Type=0
Dn Type=3
Dn Slope=0.005
Boundary for River Rch & Prof#=UNT 065 IN LACR,Reach-1,7
Up Type=0
Dn Type=3
Dn Slope=0.005

--- UNT 065 IN LACR.g01 (geometry) ---

Geom Title=Existing Conditions

River Reach=UNT 065 IN LACR,Reach-1
Reach XY= 30
      2277487.72     13207446.85      2277587.72     13207496.85
      2277587.72     13207696.85      2277537.72     13207796.85
      2277687.72     13207946.85      2277687.72     13208196.85
      2277737.72     13208246.86      2277687.72     13208346.85
      2277587.72     13208346.85      2277537.72     13208396.86
      2277437.72     13208696.85      2277287.72     13208796.85
      2277287.72     13208946.85      2277337.72     13209046.86
      2277287.72     13209096.85      2277187.72     13209096.85
      2277037.72     13209246.85      2277037.72     13209496.85
      2277137.72     13209546.86      2277137.72     13209746.85
      2277187.72     13209796.85      2277187.72     13209946.85
      2277087.72     13210096.85      2277237.72     13210246.85
      2277237.72     13210346.86      2277037.72     13210346.86
      2276987.72     13210246.85      2276837.72     13210346.86
      2276837.72     13210496.85      2276987.72     13210846.86

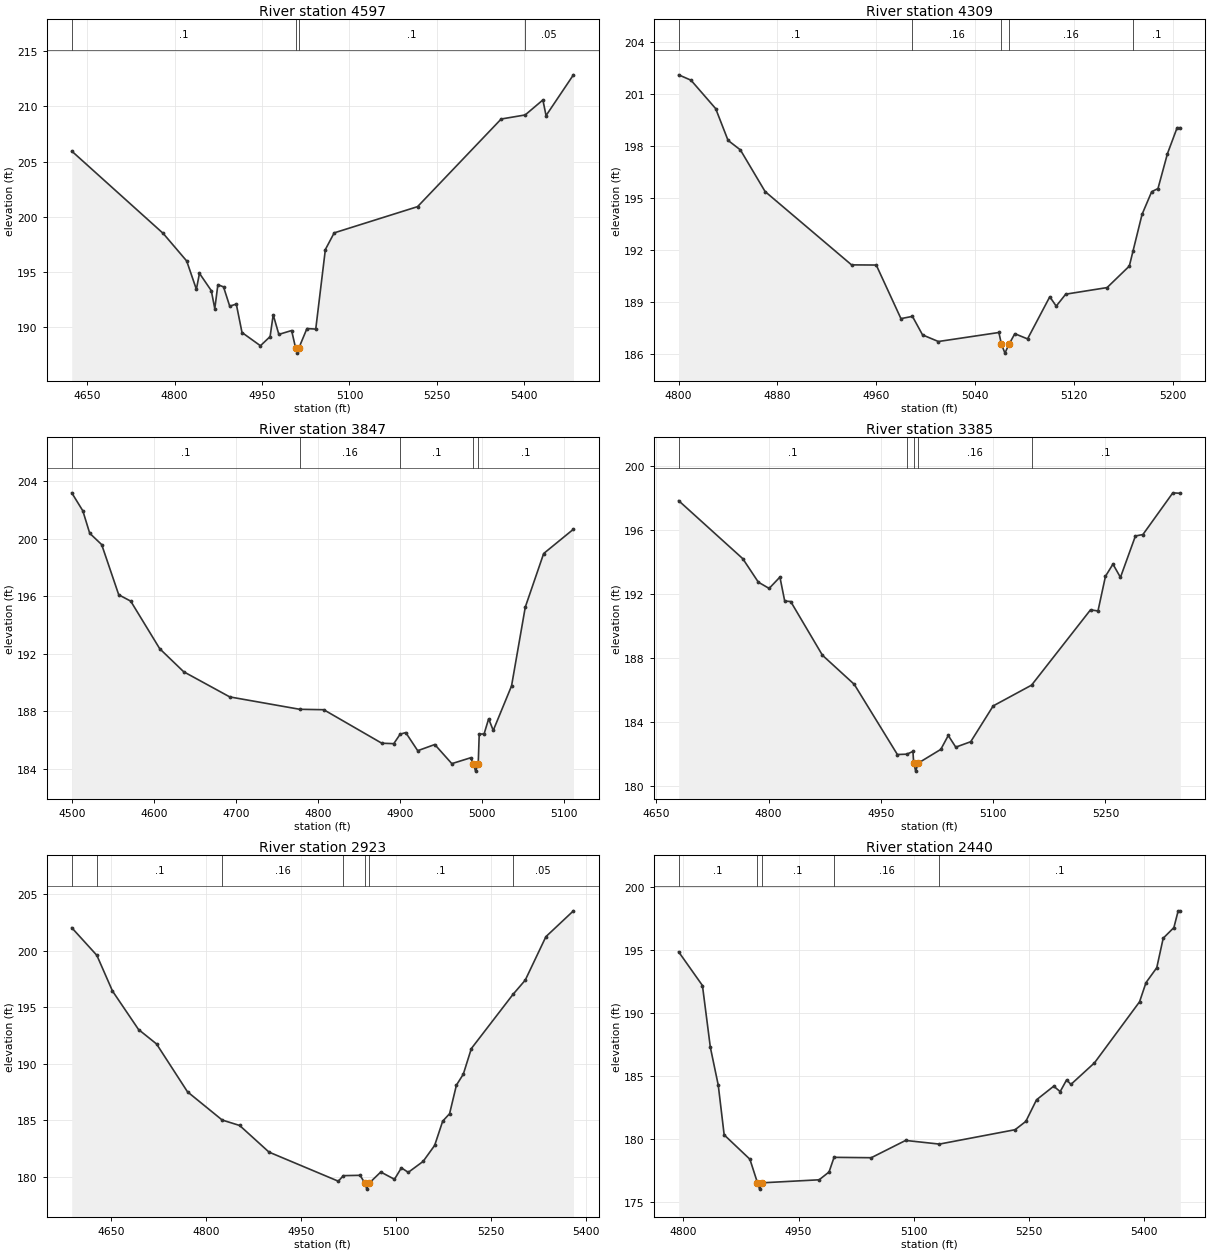
Type RM Length L Ch R = 1,4597,288,288,288
BEGIN DESCRIPTION:
UNT 065 IN LACR 10.0
END DESCRIPTION:
XS GIS Cut Line= 4
      2277237.71     13207596.85      2277388.30     13207667.15
      2277804.97     13207528.26      2277902.17     13207292.19
#Sta/Elev= 30
  4623.6  205.95  4780.5  198.48  4820.8  195.98  4837.4  193.41  4842.7  194.86
  4863.0  193.29  4869.0  191.65  4874.3  193.83  4884.0  193.63  4894.6  191.88
  4905.9  192.07  4915.7  189.49  4947.3  188.29  4963.9  189.12  4969.2  191.10
  4978.9  189.32  5000.8  189.67  5007.5  188.12  5010.3  187.62  5013.5  188.12
  5027.1  189.85  5042.2  189.80  5058.7  197.02  5073.8  198.53  5216.9  200.91
  5360.3  208.86  5401.5  209.23  5431.9  210.59  5437.3  209.17  5484.3  212.87
#Mann=4,-1,0
  4623.6     0.1       0  5007.5    0.07       0  5013.5     0.1       0
  5401.5    0.05       0
Bank Sta=5007.5,5013.5
Exp/Cntr=0.3,0.1

Type RM Length L Ch R = 1,4309,462,462,462
BEGIN DESCRIPTION:
UNT 065 IN LACR 9.0
END DESCRIPTION:
XS GIS Cut Line= 3
      2277387.72     13207846.85      2277587.72     13207846.85
      2277787.76     13207896.87
#Sta/Elev= 30
  4800.0  202.08  4810.0  201.77  4830.0  200.13  4840.0  198.30  4850.0  197.75
  4870.0  195.35  4940.0  191.12  4960.0  191.11  4980.0  188.02  4989.3  188.15
  4997.5  187.08  5010.3  186.70  5059.3  187.22  5061.4  186.53  5064.2  186.03
  5067.4  186.53  5072.2  187.15  5082.5  186.85  5100.5  189.28  5105.7  188.74
  5113.4  189.43  5146.9  189.81  5164.9  191.05  5167.9  191.92  5175.2  194.03
  5183.0  195.34  5188.1  195.52  5195.8  197.54  5203.6  199.03  5206.2  199.03
#Mann=5,-1,0
  4800.0     0.1       0  4989.3    0.16       0  5061.4    0.07       0
  5067.4    0.16       0  5167.9     0.1       0
Bank Sta=5061.4,5067.4
Exp/Cntr=0.3,0.1

Type RM Length L Ch R = 1,3847,462,462,462
BEGIN DESCRIPTION:
UNT 065 IN LACR 8.0
END DESCRIPTION:
XS GIS Cut Line= 3
      2277337.72     13207946.86      2277737.72     13208246.86
      2277837.72     13208196.86
#Sta/Elev= 30
  4500.0  203.20  4513.5  201.95  4521.9  200.39  4536.5  199.60  4557.3  196.11
  4571.9  195.67  4607.3  192.36  4636.5  190.76  4692.7  189.01  4777.9  188.15
  4807.3  188.12  4878.1  185.79  4892.7  185.76  4900.5  186.42  4907.3  186.53
  4921.9  185.27  4942.7  185.70  4963.5  184.37  4986.5  184.78  4989.7  184.35
  4992.5  183.85  4995.7  184.35  4996.9  186.43  5002.8  186.43  5008.4  187.49
  5014.0  186.68  5036.3  189.77  5053.1  195.26  5075.5  198.98  5111.8  200.67
#Mann=5,-1,0
  4500.0     0.1       0  4777.9    0.16       0  4900.5     0.1       0
  4989.7    0.07       0  4995.7     0.1       0
Bank Sta=4989.7,4995.7
Exp/Cntr=0.3,0.1

Type RM Length L Ch R = 1,3385,462,462,462
BEGIN DESCRIPTION:
UNT 065 IN LACR 7.0
END DESCRIPTION:
XS GIS Cut Line= 3
      2277237.69     13208346.83      2277487.72     13208546.86
      2277837.72     13208546.85
#Sta/Elev= 30
  4679.8  197.83  4765.5  194.20  4786.3  192.73  4800.7  192.34  4815.1  193.05
  4821.5  191.55  4829.5  191.52  4871.9  188.16  4914.4  186.34  4972.0  181.95
  4984.5  181.97  4992.8  182.14  4993.8  181.41  4996.5  180.91  4999.8  181.41
  5030.0  182.27  5040.0  183.14  5050.0  182.41  5070.0  182.75  5100.0  184.99
  5151.3  186.29  5230.0  191.00  5240.0  190.93  5250.0  193.10  5260.0  193.86
  5270.0  193.03  5290.0  195.62  5300.0  195.71  5340.0  198.32  5350.0  198.29
#Mann=5,-1,0
  4679.8     0.1       0  4984.5    0.16       0  4993.8    0.07       0
  4999.8    0.16       0  5151.3     0.1       0
Bank Sta=4993.8,4999.8
Exp/Cntr=0.3,0.1

Type RM Length L Ch R = 1,2923,483,483,483
BEGIN DESCRIPTION:
UNT 065 IN LACR 6.0
END DESCRIPTION:
XS GIS Cut Line= 3
      2276887.73     13208796.86      2277287.72     13208896.86
      2277637.73     13209046.86
#Sta/Elev= 30
  4587.7  202.02  4627.4  199.58  4652.1  196.43  4693.3  193.03  4721.7  191.76
  4770.7  187.53  4825.5  185.04  4853.1  184.56  4899.5  182.21  5009.1  179.64
  5017.1  180.13  5043.5  180.16  5051.4  179.44  5054.1  178.94  5057.4  179.44
  5076.2  180.45  5097.9  179.81  5108.8  180.82  5119.7  180.42  5143.2  181.39
  5161.4  182.80  5174.1  184.94  5185.0  185.60  5195.8  188.12  5206.7  189.09
  5219.4  191.35  5285.2  196.13  5304.6  197.39  5337.3  201.23  5380.8  203.51
#Mann=7,-1,0
  4587.7    0.05       0  4627.4     0.1       0  4825.5    0.16       0
  5017.1     0.1       0  5051.4    0.07       0  5057.4     0.1       0
  5285.2    0.05       0
Bank Sta=5051.4,5057.4
Exp/Cntr=0.3,0.1

Type RM Length L Ch R = 1,2440,441,441,441
BEGIN DESCRIPTION:
UNT 065 IN LACR 5.0
END DESCRIPTION:
XS GIS Cut Line= 3
      2276887.68     13209146.84      2277087.72     13209196.86
      2277487.71     13209396.85
#Sta/Elev= 30
  4793.8  194.84  4824.8  192.17  4835.1  187.27  4845.4  184.27  4853.1  180.33
  4886.6  178.40  4896.5  176.53  4899.2  176.03  4902.5  176.53  4976.8  176.77
  4989.7  177.39  4996.2  178.55  5044.7  178.52  5089.4  179.89  5133.4  179.60
  5232.0  180.74  5246.0  181.40  5259.9  183.11  5282.3  184.19  5290.7  183.76
  5299.1  184.69  5304.7  184.33  5335.4  186.04  5394.1  190.88  5402.5  192.40
  5416.5  193.58  5424.9  195.92  5438.8  196.76  5444.4  198.09  5447.2  198.09
#Mann=5,-1,0
  4793.8     0.1       0  4896.5    0.07       0  4902.5     0.1       0
  4996.2    0.16       0  5133.4     0.1       0
Bank Sta=4896.5,4902.5
Exp/Cntr=0.3,0.1

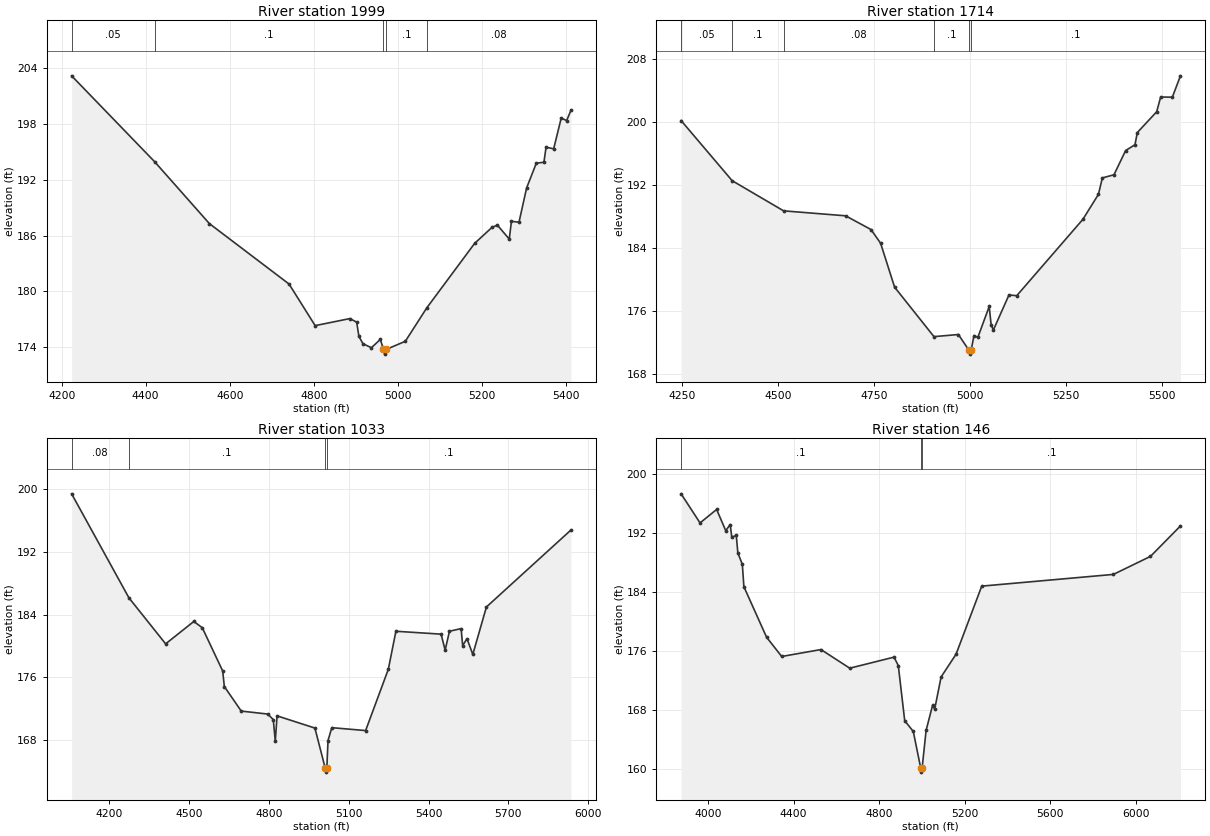
Type RM Length L Ch R = 1,1999,285,285,285
BEGIN DESCRIPTION:
UNT 065 IN LACR 4.0
END DESCRIPTION:
XS GIS Cut Line= 3
      2276387.73     13209746.85      2277137.72     13209546.86
      2277537.71     13209446.86
#Sta/Elev= 30
  4223.8  203.21  4421.3  193.96  4551.7  187.29  4741.3  180.78  4803.4  176.30
  4886.2  177.06  4902.3  176.67  4907.5  175.15  4917.2  174.35  4937.3  173.92
  4958.6  174.82  4966.0  173.73  4968.7  173.23  4972.0  173.73  5018.0  174.61
  5069.2  178.22  5183.0  185.16  5224.2  186.88  5237.1  187.13  5265.4  185.62
  5270.6  187.54  5288.6  187.44  5306.7  191.13  5329.8  193.80  5347.9  193.90
  5353.0  195.52  5371.1  195.35  5389.1  198.66  5402.0  198.39  5412.3  199.50
#Mann=5,-1,0
  4223.8    0.05       0  4421.3     0.1       0  4966.0    0.07       0
  4972.0     0.1       0  5069.2    0.08       0
Bank Sta=4966,4972
Exp/Cntr=0.3,0.1

Type RM Length L Ch R = 1,1714,681,681,681
BEGIN DESCRIPTION:
UNT 065 IN LACR 3.0
END DESCRIPTION:
XS GIS Cut Line= 3
      2276443.86     13209785.21      2276916.08     13209854.65
      2277728.54     13209722.71
#Sta/Elev= 30
  4247.5  200.14  4380.4  192.51  4514.4  188.68  4675.9  188.05  4741.9  186.31
  4767.0  184.57  4803.5  178.99  4906.0  172.71  4969.6  172.98  4997.0  170.99
  4999.7  170.49  5003.0  170.99  5010.1  172.85  5020.3  172.62  5049.9  176.54
  5054.9  174.20  5060.8  173.56  5101.3  178.00  5121.6  177.91  5293.8  187.60
  5334.3  190.77  5344.5  192.86  5374.8  193.26  5405.2  196.34  5429.5  197.07
  5435.6  198.62  5486.0  201.26  5496.4  203.13  5526.8  203.11  5547.9  205.82
#Mann=6,-1,0
  4247.5    0.05       0  4380.4     0.1       0  4514.4    0.08       0
  4906.0     0.1       0  4997.0    0.07       0  5003.0     0.1       0
Bank Sta=4997,5003
Exp/Cntr=0.3,0.1

Type RM Length L Ch R = 1,1033,887,887,887
BEGIN DESCRIPTION:
UNT 065 IN LACR 2.0
END DESCRIPTION:
XS GIS Cut Line= 4
      2276415.00     13209875.39      2276944.66     13210063.29
      2277388.30     13210562.98      2277957.78     13210257.41
#Sta/Elev= 30
  4058.8  199.42  4274.1  186.13  4412.1  180.25  4517.9  183.11  4549.8  182.31
  4626.5  176.78  4632.6  174.80  4696.2  171.66  4795.7  171.28  4816.6  170.57
  4824.1  167.80  4830.8  171.05  4973.0  169.49  5011.8  164.36  5014.5  163.86
  5017.8  164.36  5022.3  167.90  5036.5  169.54  5163.6  169.17  5248.9  177.00
  5277.4  181.86  5447.2  181.49  5462.4  179.45  5478.7  181.86  5522.5  182.20
  5528.2  180.03  5544.5  180.91  5566.4  178.90  5617.5  184.96  5935.3  194.80
#Mann=4,-1,0
  4058.8    0.08       0  4274.1     0.1       0  5011.8    0.07       0
  5017.8     0.1       0
Bank Sta=5011.8,5017.8
Exp/Cntr=0.3,0.1

Type RM Length L Ch R = 1,146,0,0,0
BEGIN DESCRIPTION:
UNT 065 IN LACR 1.0
END DESCRIPTION:
XS GIS Cut Line= 5
      2276068.85     13210090.75      2276617.47     13210674.09
      2276791.08     13210715.76      2277464.69     13210743.54
      2278060.46     13210411.02
#Sta/Elev= 30
  3873.9  197.31  3962.5  193.36  4040.1  195.19  4082.6  192.31  4103.6  193.14
  4110.9  191.43  4132.0  191.66  4139.3  189.29  4160.3  187.74  4167.6  184.70
  4273.6  177.85  4344.4  175.23  4528.1  176.17  4662.8  173.64  4869.9  175.14
  4889.9  173.99  4919.9  166.51  4960.0  165.05  4995.1  160.03  4997.8  159.53
  5001.1  160.03  5020.0  165.20  5050.0  168.58  5060.1  168.08  5090.1  172.45
  5160.1  175.54  5280.2  184.78  5895.9  186.37  6069.6  188.82  6209.7  192.95
#Mann=3,-1,0
  3873.9     0.1       0  4995.1    0.07       0  5001.1     0.1       0
Bank Sta=4995.1,5001.1
Exp/Cntr=0.3,0.1

Chan Stop Cuts=-1