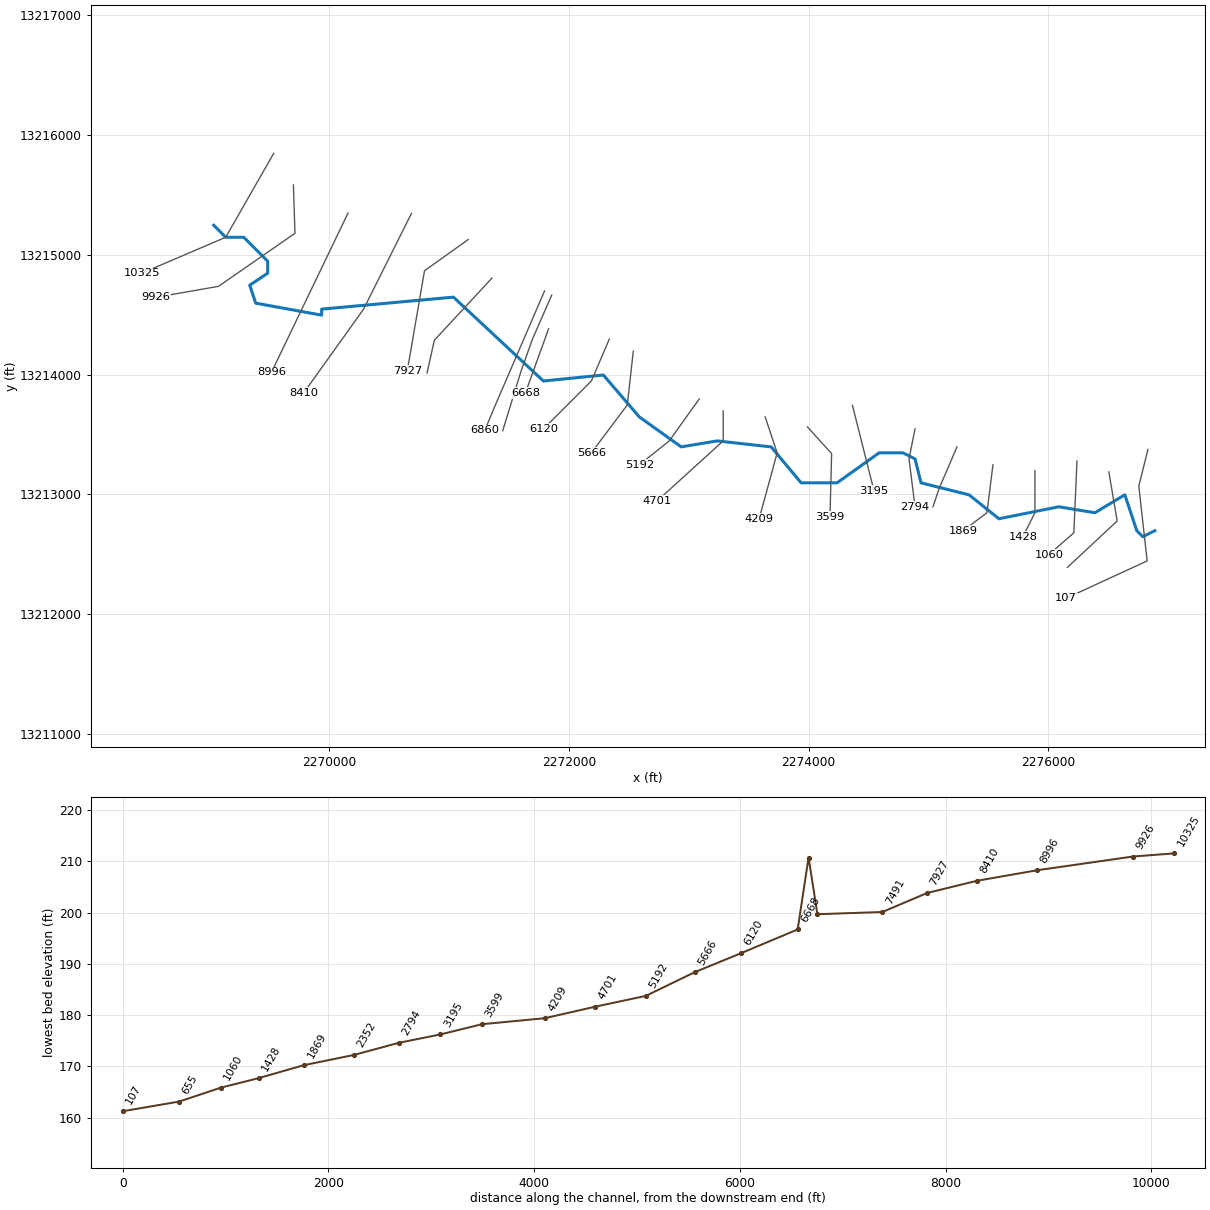
--- UNT 066 IN LACR.prj (project) ---

Proj Title=UNT 066 IN LACR Base Level Engineering
Current Plan=p01
Default Exp/Contr=0.3,0.1
English Units
Geom File=g01
Flow File=f01
Plan File=p01
Y Axis Title=Elevation
X Axis Title(PF)=Main Channel Distance
X Axis Title(XS)=Station
BEGIN DESCRIPTION:
UNT 066 IN LACR
END DESCRIPTION:
DSS Export Rating Curves= 0
DSS Export Rating Curve Sorted= 0
DSS Export Volume Flow Curves= 0
DXF OffsetX= 0
DXF OffsetY= 0
DXF ScaleX= 1
DXF ScaleY= 10

--- UNT 066 IN LACR.p01 (plan) ---

Plan Title=Multiple Run
Short Identifier=Multiple
Geom File=g01
Flow File=f01
Subcritical Flow
K Sum by GR= 0
Std Step Tol= 0.01
Critical Tol= 0.01
Num of Std Step Trials= 20
Max Error Tol= 0.3
Flow Tol Ratio= 0.001
Split Flow NTrial= 30
Split Flow Tol= 0.02
Split Flow Ratio= 0.02
Log Output Level= 0
Friction Slope Method= 1
Unsteady Friction Slope Method= 2
Unsteady Bridges Friction Slope Method= 1
Parabolic Critical Depth
Global Vel Dist=  1 , 1 , 1
Global Log Level= 0
CheckData=True
Encroach Param= -1, 0, 0, 0
BEGIN DESCRIPTION:
Multiple Run
END DESCRIPTION:

--- UNT 066 IN LACR.f01 (steady flow) ---

Flow Title=Multiple
Program Version=4.10
Number of Profiles= 7
Profile Names=10-year,25-year,50-year,1pct_min,100-year,1pct_plu,500-year
River Rch & RM=UNT 066 IN LACR,Reach-1         ,10325
     285     395     485     438     592     801     898
Boundary for River Rch & Prof#=UNT 066 IN LACR,Reach-1         , 1
Up Type= 0
Dn Type= 3
Dn Slope=0.003
Boundary for River Rch & Prof#=UNT 066 IN LACR,Reach-1         , 2
Up Type= 0
Dn Type= 3
Dn Slope=0.003
Boundary for River Rch & Prof#=UNT 066 IN LACR,Reach-1         , 3
Up Type= 0
Dn Type= 3
Dn Slope=0.003
Boundary for River Rch & Prof#=UNT 066 IN LACR,Reach-1         , 4
Up Type= 0
Dn Type= 3
Dn Slope=0.003
Boundary for River Rch & Prof#=UNT 066 IN LACR,Reach-1         , 5
Up Type= 0
Dn Type= 3
Dn Slope=0.003
Boundary for River Rch & Prof#=UNT 066 IN LACR,Reach-1         , 6
Up Type= 0
Dn Type= 3
Dn Slope=0.003
Boundary for River Rch & Prof#=UNT 066 IN LACR,Reach-1         , 7
Up Type= 0
Dn Type= 3
Dn Slope=0.003
DSS Import GetInterval= 0
DSS Import GetPeak= 0
DSS Import FillOption= 0

--- UNT 066 IN LACR.g01 (geometry) ---

Geom Title=Existing Conditions
Program Version=4.10

River Reach=UNT 066 IN LACR ,Reach-1
Reach XY= 30
      2269037.72     13215246.85      2269137.72     13215146.85
      2269287.72     13215146.85      2269487.72     13214946.86
      2269487.72     13214846.85      2269337.72     13214746.85
      2269387.72     13214596.85      2269937.72     13214496.85
      2269937.72     13214546.85      2271037.72     13214646.85
      2271787.72     13213946.85      2272287.72     13213996.85
      2272587.72     13213646.86      2272937.72     13213396.85
      2273237.72     13213446.85      2273687.72     13213396.85
      2273937.72     13213096.85      2274237.72     13213096.85
      2274587.72     13213346.85      2274787.72     13213346.85
      2274887.72     13213296.86      2274937.72     13213096.85
      2275337.72     13212996.86      2275587.72     13212796.85
      2276087.72     13212896.85      2276387.72     13212846.85
      2276637.72     13212996.86      2276737.72     13212696.85
      2276787.72     13212646.86      2276887.72     13212696.85

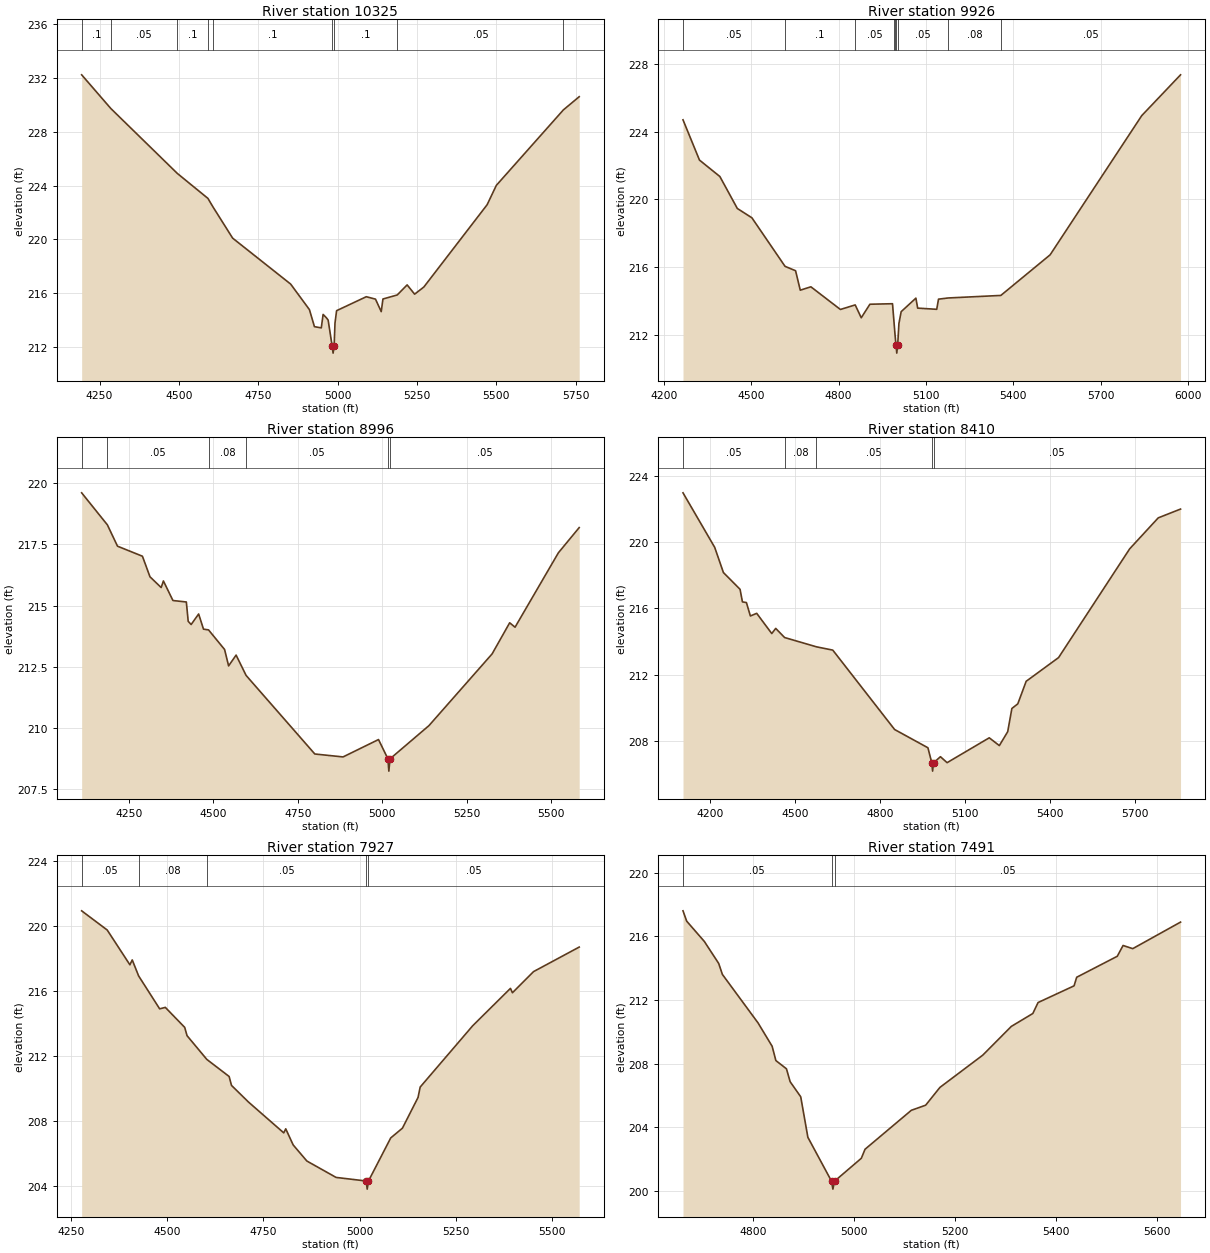
Type RM Length L Ch R = 1 ,10325   ,399,399,399
BEGIN DESCRIPTION:
UNT 066 IN LACR 21.0
END DESCRIPTION:
XS GIS Cut Line= 3
      2269537.71     13215846.83      2269137.72     13215146.85
       2268437.7     13214846.85
#Sta/Elev= 30
  4193.8  232.24  4285.8  229.73  4495.2   224.9  4591.7  223.04  4607.2  222.42
  4669.6  220.08  4852.4  216.66  4911.5  214.76  4927.3  213.49  4948.9   213.4
  4954.6   214.4  4964.7  214.16  4970.5  213.98  4983.3  212.02  4986.1  211.52
  4989.3  212.02  4992.1  213.76  4997.1  214.68  5090.7  215.72  5119.7  215.54
  5137.8  214.61  5143.2  215.55  5188.2  215.85  5219.4   216.6    5243  215.91
    5272  216.44  5471.5  222.57  5500.5  224.01  5711.8  229.63  5761.6  230.61
#Mann= 9 ,-1 , 0
  4193.8      .1       0  4285.8     .05       0  4495.2      .1       0
  4591.7     .05       0  4607.2      .1       0  4983.3     .07       0
  4989.3      .1       0  5188.2     .05       0  5711.8     .08       0
Bank Sta=4983.3,4989.3
XS Rating Curve= 0 ,0
Exp/Cntr=0.3,0.1

Type RM Length L Ch R = 1 ,9926    ,930,930,930
BEGIN DESCRIPTION:
UNT 066 IN LACR 20.0
END DESCRIPTION:
XS GIS Cut Line= 4
      2269702.26     13215583.38      2269715.28     13215179.77
      2269077.26     13214737.06      2268556.47     13214645.92
#Sta/Elev= 30
  4265.3   224.7  4321.9  222.32  4391.9  221.35  4451.9  219.46  4501.9  218.91
  4615.8  216.04    4652  215.78  4668.1  214.63  4704.6  214.83    4806  213.49
  4856.8  213.76  4877.6     213  4907.3   213.8    4985  213.83    4989  212.98
  4993.4  212.05  4996.8  211.41  4999.6  210.91  5002.8  211.41    5007  212.66
  5014.7  213.36  5065.3  214.16  5071.4  213.57  5136.9   213.5    5143   214.1
    5176  214.17  5357.1  214.32  5526.4  216.72  5841.2  224.95  5974.4  227.36
#Mann= 9 ,-1 , 0
  4265.3     .05       0  4615.8      .1       0  4856.8     .05       0
    4989      .1       0  4993.4     .05       0  4996.8     .03       0
  5002.8     .05       0    5176     .08       0  5357.1     .05       0
Bank Sta=4996.8,5002.8
XS Rating Curve= 0 ,0
Exp/Cntr=0.3,0.1

Type RM Length L Ch R = 1 ,8996    ,586,586,586
BEGIN DESCRIPTION:
UNT 066 IN LACR 19.0
END DESCRIPTION:
XS GIS Cut Line= 2
      2270157.97       13215349.      2269520.17     13214021.35
#Sta/Elev= 30
  4110.1  219.61  4186.3   218.3  4216.2  217.43    4290  217.02  4312.3  216.18
  4345.5  215.74  4352.1  216.01  4380.3  215.21    4420  215.15  4425.5  214.36
  4434.2  214.23  4456.4  214.66  4470.8  214.04  4485.7  214.01  4533.2  213.21
  4545.1  212.54  4567.3  212.98  4596.9  212.15  4800.3  208.94  4883.9  208.82
  4988.9  209.53  5016.8  208.74  5019.5  208.24  5022.8  208.74  5138.3   210.1
  5325.2  213.03  5377.2   214.3  5393.1  214.12  5521.4  217.16    5583  218.19
#Mann= 6 ,-1 , 0
  4110.1      .1       0  4186.3     .05       0  4485.7     .08       0
  4596.9     .05       0  5016.8     .03       0  5022.8     .05       0
Bank Sta=5016.8,5022.8
XS Rating Curve= 0 ,0
Exp/Cntr=0.3,0.1

Type RM Length L Ch R = 1 ,8410    ,483,483,483
BEGIN DESCRIPTION:
UNT 066 IN LACR 18.0
END DESCRIPTION:
XS GIS Cut Line= 3
      2270687.71     13215346.83      2270287.72     13214546.85
      2269787.74     13213846.88
#Sta/Elev= 30
  4105.6  222.97  4217.4  219.68  4248.1  218.16  4306.8  217.15  4315.2  216.39
  4329.2  216.35  4343.2  215.54  4365.5   215.7  4418.6  214.48  4432.6  214.79
  4463.9  214.24  4576.1  213.68  4633.8  213.48  4851.9  208.69  4969.3  207.59
    4983  206.68  4985.8  206.18    4989  206.68  5013.5  207.05  5036.9  206.69
  5185.6  208.19  5221.2  207.72  5250.7  208.56  5265.4  209.96  5286.3  210.24
  5315.8   211.6  5430.1  213.03  5680.8  219.59  5781.6  221.46  5860.2  221.99
#Mann= 5 ,-1 , 0
  4105.6     .05       0  4463.9     .08       0  4576.1     .05       0
    4983     .03       0    4989     .05       0
Bank Sta=4983,4989
XS Rating Curve= 0 ,0
Exp/Cntr=0.3,0.1

Type RM Length L Ch R = 1 ,7927    ,436,436,436
BEGIN DESCRIPTION:
UNT 066 IN LACR 17.0
END DESCRIPTION:
XS GIS Cut Line= 3
      2271160.58     13215127.67      2270796.01     13214867.27
      2270652.77     13214033.91
#Sta/Elev= 30
  4277.6  220.93    4344  219.75    4403  217.61  4409.1  217.91  4425.6  216.93
  4480.4   214.9  4495.1  214.99  4545.5  213.76  4551.6  213.25    4603  211.79
    4661  210.74  4667.2  210.19  4711.2  209.17  4803.1  207.27  4808.2  207.52
  4827.5  206.53  4863.1  205.54  4939.1  204.53  5017.3  204.31    5020  203.81
  5023.3  204.31  5081.2  206.96  5111.6  207.56  5152.2  209.45  5157.8  210.09
  5294.3  213.86  5392.5  216.16  5397.6  215.89  5452.5  217.19  5571.2   218.7
#Mann= 5 ,-1 , 0
  4277.6     .05       0  4425.6     .08       0    4603     .05       0
  5017.3     .03       0  5023.3     .05       0
Bank Sta=5017.3,5023.3
XS Rating Curve= 0 ,0
Exp/Cntr=0.3,0.1

Type RM Length L Ch R = 1 ,7491    ,631,631,631
BEGIN DESCRIPTION:
UNT 066 IN LACR 16.0
END DESCRIPTION:
XS GIS Cut Line= 3
      2271358.76     13214806.01      2270877.85     13214286.98
      2270817.12     13214014.35
#Sta/Elev= 30
  4660.2  217.61  4667.5  216.96  4702.6  215.68    4731   214.3  4738.3  213.61
    4809  210.56    4837  209.09  4844.4  208.19  4865.4  207.67  4872.7  206.86
  4893.7  205.91  4907.9  203.36  4954.8   200.6  4957.5   200.1  4960.8   200.6
  5013.9  202.04  5021.3  202.61  5113.1  205.06  5141.5  205.38  5169.8   206.5
  5254.8  208.53  5311.5  210.34  5354.1  211.15  5364.5  211.84  5435.9  212.89
  5441.1  213.43  5521.6  214.75  5533.1  215.43  5552.3  215.23  5647.1   216.9
#Mann= 3 ,-1 , 0
  4660.2     .05       0  4954.8     .03       0  4960.8     .05       0
Bank Sta=4954.8,4960.8
XS Rating Curve= 0 ,0
Exp/Cntr=0.3,0.1

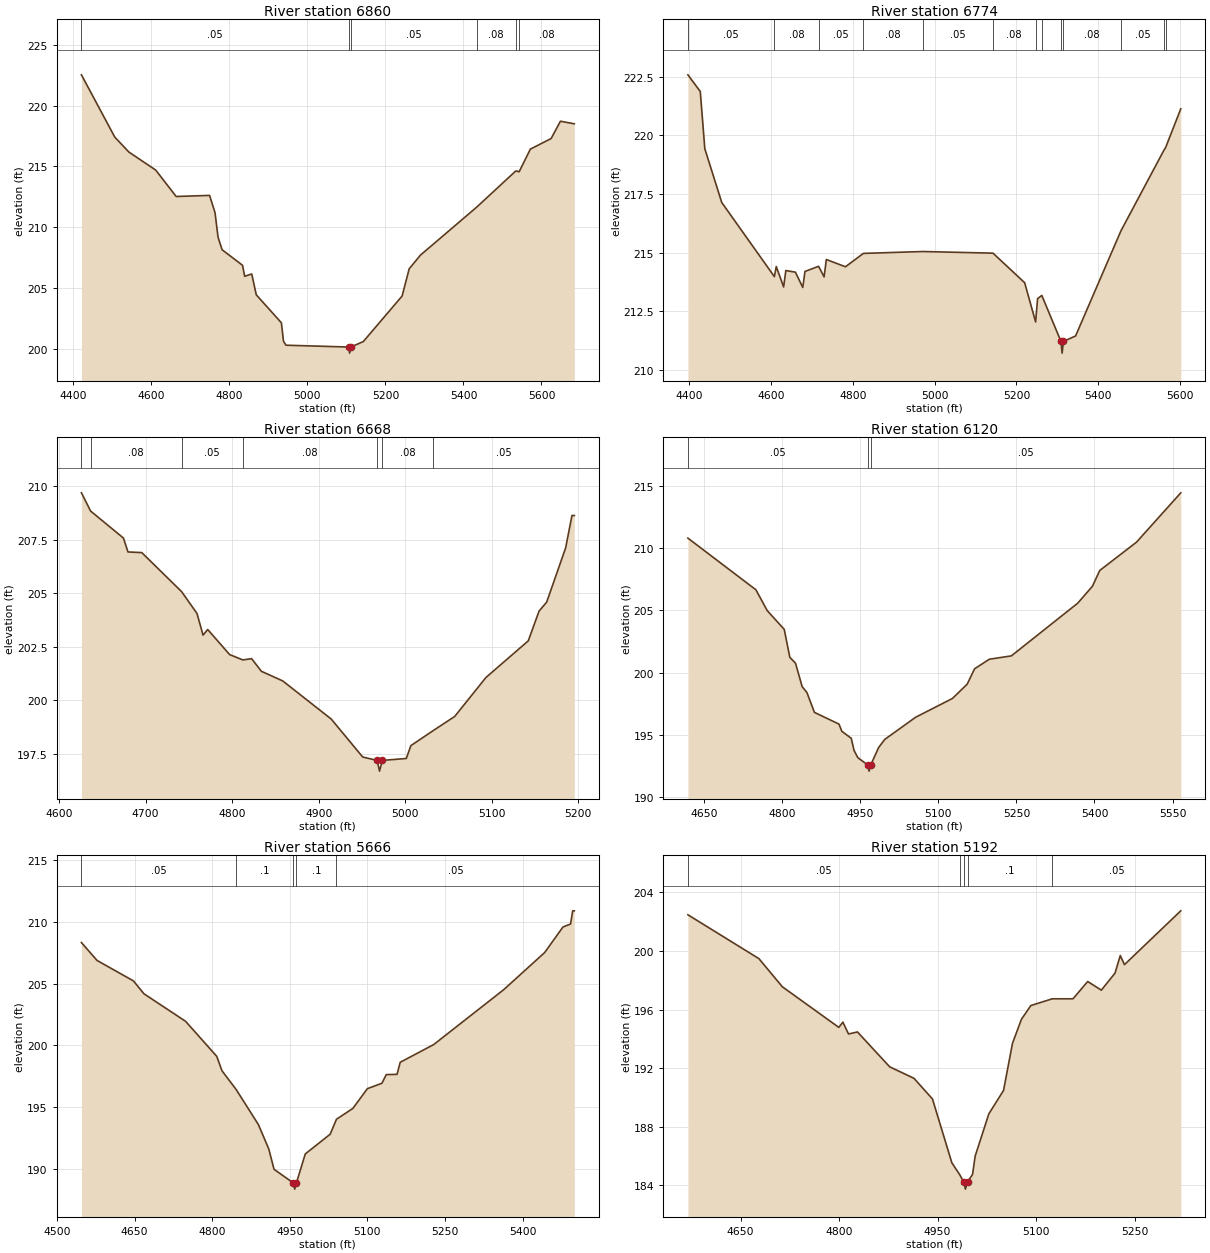
Type RM Length L Ch R = 1 ,6860    ,86,86,86
BEGIN DESCRIPTION:
UNT 066 IN LACR 15.0
END DESCRIPTION:
XS GIS Cut Line= 3
      2271797.32      13214698.5      2271375.42     13213719.29
      2271299.92     13213537.04
#Sta/Elev= 30
  4420.7  222.52  4506.1  217.41  4542.3  216.18  4611.1   214.7  4663.6  212.53
  4749.2  212.62  4763.2   211.2  4770.9  209.19  4781.3  208.16  4833.7  206.88
  4839.2  205.98  4857.3  206.17  4868.9  204.46  4933.3  202.16  4938.7  200.65
  4945.1  200.32  5105.5  200.17  5108.2  199.67  5111.5  200.17  5143.3  200.62
  5242.8  204.36  5260.9  206.59  5289.9  207.72  5434.1  211.66  5534.3  214.63
  5542.8  214.56  5571.6  216.42  5624.8  217.29  5648.6  218.71  5684.2   218.5
#Mann= 6 ,-1 , 0
  4420.7     .05       0  5105.5    .033       0  5111.5     .05       0
  5434.1     .08       0  5534.3     .05       0  5542.8     .08       0
Bank Sta=5105.5,5111.5
XS Rating Curve= 0 ,0
Exp/Cntr=0.3,0.1

Type RM Length L Ch R = 1 ,6774    ,106,106,106
BEGIN DESCRIPTION:
UNT 066 IN LACR 14.0
END DESCRIPTION:
XS GIS Cut Line= 4
      2271857.21     13214664.63      2271695.74     13214294.81
      2271601.37      13214029.8      2271448.35     13213531.82
#Sta/Elev= 30
  4396.1  222.58  4426.4  221.87  4437.5  219.43  4478.9  217.14  4607.7  213.98
  4612.3  214.41  4630.3  213.54  4635.7  214.24  4659.1  214.17  4677.1  213.52
  4682.5   214.2  4715.8  214.42  4729.3  213.97  4734.8  214.71  4781.6   214.4
  4825.4  214.97  4971.2  215.05  5142.5  214.98    5220  213.72  5246.8  212.05
  5251.6  213.04  5261.9  213.18  5308.8  211.22  5311.6  210.72  5314.8  211.22
  5344.5  211.45  5455.5  215.93  5561.1  219.38  5564.6  219.47  5601.9  221.13
#Mann= 13 ,-1 , 0
  4396.1     .05       0  4607.7     .08       0  4715.8     .05       0
  4825.4     .08       0  4971.2     .05       0  5142.5     .08       0
  5246.8     .05       0  5261.9     .08       0  5308.8    .033       0
  5314.8     .08       0  5455.5     .05       0  5561.1      .1       0
  5564.6     .05       0
Bank Sta=5308.8,5314.8
XS Rating Curve= 0 ,0
Exp/Cntr=0.3,0.1

Type RM Length L Ch R = 1 ,6668    ,548,548,548
BEGIN DESCRIPTION:
UNT 066 IN LACR 14.1
END DESCRIPTION:
XS GIS Cut Line= 2
      2271831.02     13214382.44      2271637.72     13213846.85
#Sta/Elev= 30
  4625.9  209.69  4636.5  208.84  4674.4  207.58  4679.7  206.93  4695.6   206.9
  4741.6  205.08  4759.4  204.06  4766.4  203.05  4771.8  203.31  4797.1  202.14
  4812.4  201.89  4822.5  201.95  4833.8  201.36  4858.5  200.91  4914.5  199.13
  4950.8  197.36  4967.5   197.2  4970.3   196.7  4973.5   197.2  5001.2  197.29
  5006.5  197.89  5032.6   198.6  5057.1  199.25  5093.2  201.07  5142.1  202.78
  5154.6  204.17  5163.4  204.59  5185.3  207.12  5192.6  208.63  5195.3  208.63
#Mann= 7 ,-1 , 0
  4625.9     .05       0  4636.5     .08       0  4741.6     .05       0
  4812.4     .08       0  4967.5     .07       0  4973.5     .08       0
  5032.6     .05       0
Bank Sta=4967.5,4973.5
XS Rating Curve= 0 ,0
Exp/Cntr=0.3,0.1

Type RM Length L Ch R = 1 ,6120    ,454,454,454
BEGIN DESCRIPTION:
UNT 066 IN LACR 13.0
END DESCRIPTION:
XS GIS Cut Line= 3
      2272337.72     13214296.87      2272187.72     13213946.85
      2271787.71     13213546.84
#Sta/Elev= 30
  4619.2  210.81  4749.8  206.66  4771.5  204.99  4804.2  203.48    4815  201.23
  4825.9  200.76  4838.6  198.88  4847.7  198.41  4862.2  196.81  4909.3  195.87
  4914.8  195.29  4932.9  194.73  4938.3  193.75  4945.6  193.17  4964.4  192.59
  4967.1  192.09  4970.4  192.59  4985.5  193.99  4997.3  194.64  5056.6  196.42
  5127.3  197.93  5155.6  199.08  5169.7  200.31    5198  201.08  5240.4  201.35
  5367.7  205.58    5396  206.94  5410.1  208.21  5480.8  210.49  5565.7  214.45
#Mann= 3 ,-1 , 0
  4619.2     .05       0  4964.4    .035       0  4970.4     .05       0
Bank Sta=4964.4,4970.4
XS Rating Curve= 0 ,0
Exp/Cntr=0.3,0.1

Type RM Length L Ch R = 1 ,5666    ,474,474,474
BEGIN DESCRIPTION:
UNT 066 IN LACR 12.0
END DESCRIPTION:
XS GIS Cut Line= 3
      2272537.72     13214196.89      2272487.72     13213746.85
      2272187.72     13213346.85
#Sta/Elev= 30
  4547.2  208.34  4577.4  206.89  4647.8  205.23    4668  204.19  4748.5  201.96
  4808.8  199.12  4818.9  197.95  4846.2  196.44  4889.3  193.59  4909.4  191.61
  4919.5  189.97  4956.8  188.86  4959.5  188.36  4962.8  188.86  4979.9  191.21
  5028.1  192.81  5040.2  194.02  5071.9   194.9    5100   196.5  5128.1  196.94
  5136.5  197.64  5157.3  197.66  5163.5  198.64  5228.1  200.07  5363.5  204.52
  5442.7  207.53  5478.1   209.6  5492.7  209.84  5496.9  210.91    5500  210.91
#Mann= 5 ,-1 , 0
  4547.2     .05       0  4846.2      .1       0  4956.8     .07       0
  4962.8      .1       0  5040.2     .05       0
Bank Sta=4956.8,4962.8
XS Rating Curve= 0 ,0
Exp/Cntr=0.3,0.1

Type RM Length L Ch R = 1 ,5192    ,491,491,491
BEGIN DESCRIPTION:
UNT 066 IN LACR 11.0
END DESCRIPTION:
XS GIS Cut Line= 3
      2273087.71     13213796.84      2272837.72     13213446.85
      2272587.69     13213246.83
#Sta/Elev= 30
  4569.9  202.46    4678  199.47  4713.7  197.55  4799.7  194.78  4805.8  195.14
  4814.4  194.33    4828  194.47  4877.1  192.09    4914  191.31  4942.2   189.9
  4971.7  185.55  4983.9  184.72  4989.6  184.25  4992.4  183.75  4995.6  184.25
  5003.2  184.75  5007.2     186    5028  188.88  5050.4  190.48    5064  193.69
  5077.6  195.33    5092  196.27  5124.6  196.73  5156.1  196.73  5178.5  197.91
  5199.3  197.32  5220.1  198.48  5228.1  199.68  5234.5  199.06  5320.2  202.73
#Mann= 5 ,-1 , 0
  4569.9     .05       0  4983.9      .1       0  4989.6     .07       0
  4995.6      .1       0  5124.6     .05       0
Bank Sta=4989.6,4995.6
XS Rating Curve= 0 ,0
Exp/Cntr=0.3,0.1

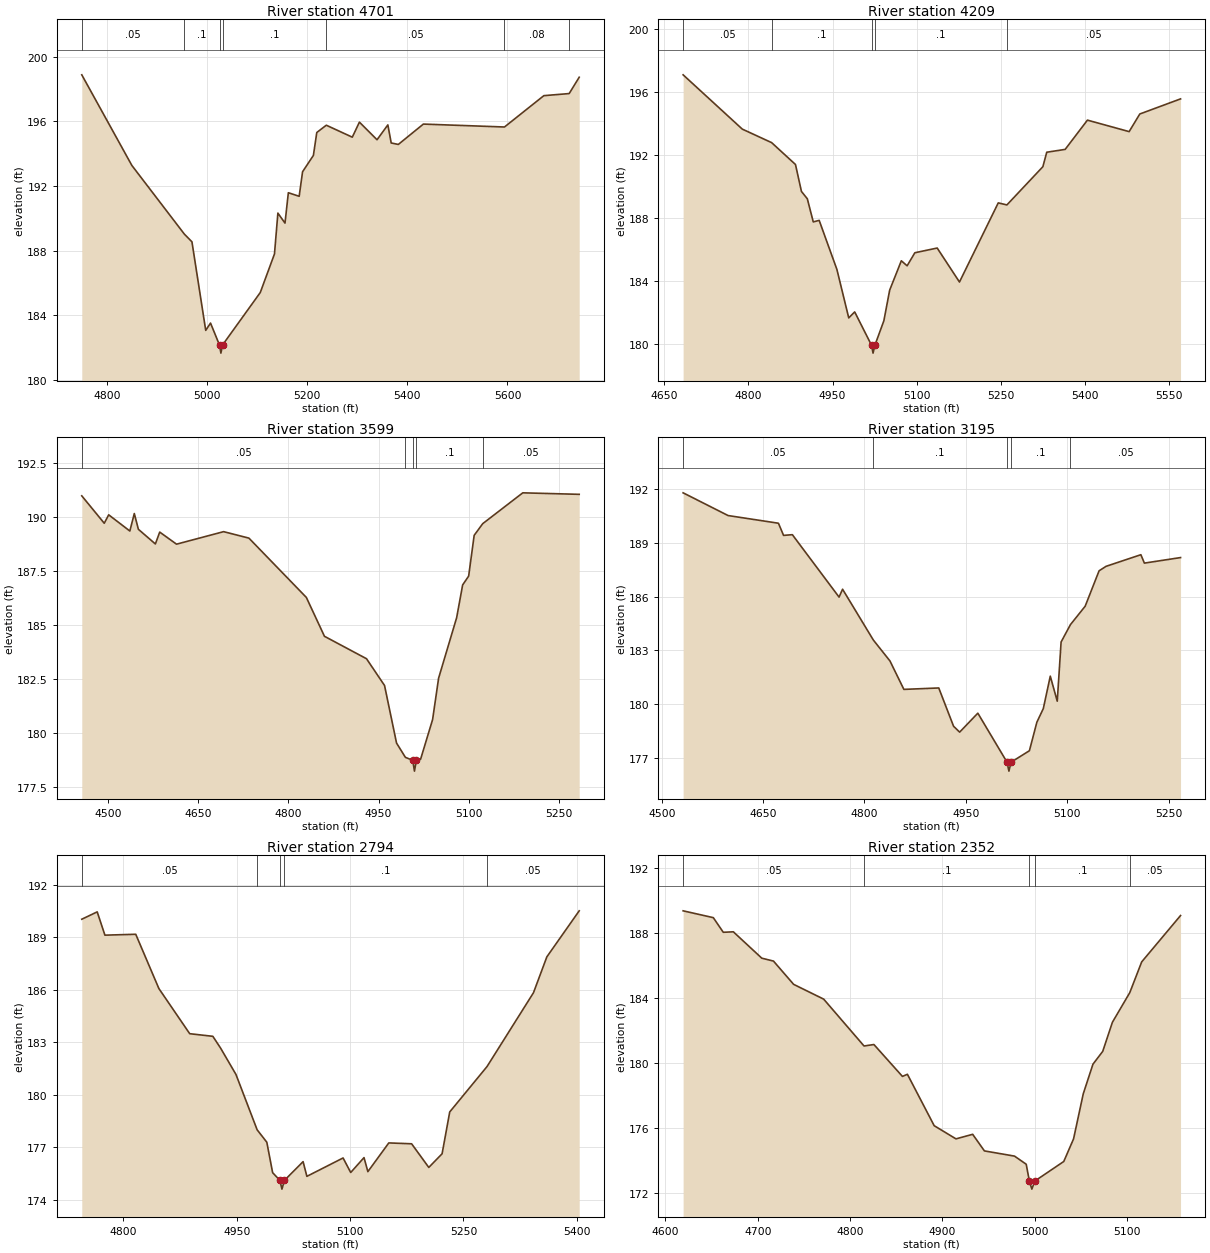
Type RM Length L Ch R = 1 ,4701    ,492,492,492
BEGIN DESCRIPTION:
UNT 066 IN LACR 10.0
END DESCRIPTION:
XS GIS Cut Line= 3
      2273287.72     13213696.85      2273287.72     13213446.85
      2272737.72     13212946.86
#Sta/Elev= 30
    4750  198.88    4850  193.27  4954.8  189.02    4970  188.54  4997.5  183.06
  5007.1  183.51    5025  182.15  5027.8  181.65    5031  182.15  5106.4   185.4
  5134.8  187.79  5141.6  190.32  5155.8   189.7  5162.5  191.58  5184.1  191.36
  5190.9  192.88  5212.5  193.89  5219.3  195.31  5238.3  195.76  5290.2  195.02
  5304.4  195.95  5339.6  194.86  5361.2  195.78  5367.9  194.66  5382.1  194.57
  5432.1  195.83  5594.1  195.65  5672.7  197.59  5723.3  197.72  5743.3  198.73
#Mann= 7 ,-1 , 0
    4750     .05       0  4954.8      .1       0    5025     .07       0
    5031      .1       0  5238.3     .05       0  5594.1     .08       0
  5723.3     .05       0
Bank Sta=5025,5031
XS Rating Curve= 0 ,0
Exp/Cntr=0.3,0.1

Type RM Length L Ch R = 1 ,4209    ,610,610,610
BEGIN DESCRIPTION:
UNT 066 IN LACR 9.0
END DESCRIPTION:
XS GIS Cut Line= 3
      2273637.73     13213646.83      2273737.72     13213346.85
      2273587.72     13212796.84
#Sta/Elev= 30
  4683.8  197.09  4789.2  193.64  4841.5  192.78    4884  191.39  4894.6  189.68
  4905.1  189.21  4915.7  187.74  4926.2  187.84  4957.8  184.72  4978.9  181.64
  4989.5  182.02  5019.5   179.9  5022.2   179.4  5025.5   179.9  5041.5  181.46
  5051.8   183.4  5072.6  185.27  5082.9  184.95  5096.7  185.78  5136.5  186.08
  5176.2  183.92  5245.3  188.95  5260.7  188.82  5324.8  191.25  5331.7  192.17
  5364.5  192.35  5404.2  194.21  5478.5  193.48  5497.5   194.6  5570.1  195.56
#Mann= 5 ,-1 , 0
  4683.8     .05       0  4841.5      .1       0  5019.5     .07       0
  5025.5      .1       0  5260.7     .05       0
Bank Sta=5019.5,5025.5
XS Rating Curve= 0 ,0
Exp/Cntr=0.3,0.1

Type RM Length L Ch R = 1 ,3599    ,404,404,404
BEGIN DESCRIPTION:
UNT 066 IN LACR 8.0
END DESCRIPTION:
XS GIS Cut Line= 3
      2273990.73     13213562.99      2274192.12     13213340.76
      2274178.23     13212812.95
#Sta/Elev= 30
  4456.1  190.99  4493.5  189.72  4500.9  190.11  4536.1  189.36  4543.5  190.17
  4550.3  189.44  4578.6  188.76  4585.8  189.31  4613.8  188.75  4692.2  189.33
  4734.3  189.03  4829.9  186.28    4860  184.48    4930  183.44    4960   182.2
    4980  179.53  4994.7  178.87    5007  178.73  5009.8  178.23    5013  178.73
    5020  178.78    5040  180.62    5050  182.54    5080  185.34    5090  186.86
    5100  187.27  5109.2  189.16  5123.4   189.7  5190.1  191.13    5284  191.06
#Mann= 5 ,-1 , 0
  4456.1     .05       0  4994.7      .1       0    5007     .07       0
    5013      .1       0  5123.4     .05       0
Bank Sta=5007,5013
XS Rating Curve= 0 ,0
Exp/Cntr=0.3,0.1

Type RM Length L Ch R = 1 ,3195    ,401,401,401
BEGIN DESCRIPTION:
UNT 066 IN LACR 7.0
END DESCRIPTION:
XS GIS Cut Line= 2
      2274365.73     13213743.54      2274545.84     13213030.02
#Sta/Elev= 30
  4531.7   191.8  4598.2  190.53  4672.7   190.1  4680.3  189.42  4693.3  189.46
  4762.4  185.97  4767.6  186.41  4813.1  183.57  4837.7   182.4  4858.3  180.81
  4909.9  180.89  4931.8  178.75  4940.8  178.42  4967.7  179.48  5010.9  176.74
  5013.7  176.24  5016.9  176.74    5044  177.38    5055  178.97  5064.6  179.74
  5074.9  181.55  5085.2  180.15  5090.9  183.46  5104.7  184.43  5126.5  185.46
  5147.1  187.44  5157.4  187.69  5208.9  188.34  5214.1  187.87  5267.6  188.18
#Mann= 5 ,-1 , 0
  4531.7     .05       0  4813.1      .1       0  5010.9     .07       0
  5016.9      .1       0  5104.7     .05       0
Bank Sta=5010.9,5016.9
XS Rating Curve= 0 ,0
Exp/Cntr=0.3,0.1

Type RM Length L Ch R = 1 ,2794    ,442,442,442
BEGIN DESCRIPTION:
UNT 066 IN LACR 6.0
END DESCRIPTION:
XS GIS Cut Line= 3
      2274887.73      13213546.9      2274837.72     13213296.86
      2274887.72     13212896.87
#Sta/Elev= 30
    4745  190.04  4765.4  190.46  4775.6  189.13  4816.4  189.18    4847  186.08
  4887.8   183.5  4918.4  183.35  4928.6  182.68    4949  181.17    4977  178.01
  4989.8   177.3  4997.5  175.56  5007.1  175.12  5009.8  174.62  5013.1  175.12
  5037.8  176.19  5042.8  175.35  5090.7   176.4  5100.8  175.57  5118.4  176.42
  5123.5  175.62  5151.2  177.26  5181.4  177.21  5204.1  175.86  5221.7  176.64
  5231.8  179.03  5281.1  181.62  5342.6  185.84  5360.3  187.89  5403.1  190.52
#Mann= 5 ,-1 , 0
    4745     .05       0    4977      .1       0  5007.1     .07       0
  5013.1      .1       0  5281.1     .05       0
Bank Sta=5007.1,5013.1
XS Rating Curve= 0 ,0
Exp/Cntr=0.3,0.1

Type RM Length L Ch R = 1 ,2352    ,483,483,483
BEGIN DESCRIPTION:
UNT 066 IN LACR 5.0
END DESCRIPTION:
XS GIS Cut Line= 3
      2275237.72     13213396.87      2275087.72     13213046.85
      2275037.72     13212896.87
#Sta/Elev= 30
  4619.2  189.34  4651.9  188.92  4662.7  188.02  4673.6  188.05  4704.4  186.43
  4717.1  186.25  4738.9  184.82  4771.5  183.91  4815.2  181.03  4825.9  181.12
  4856.8  179.16  4862.2  179.29  4891.2  176.13  4914.8  175.32  4932.9   175.6
  4945.6  174.58  4978.2  174.26  4990.9  173.76  4994.3  172.73    4997  172.23
  5000.3  172.73  5031.6  173.93  5042.2  175.32  5052.7  178.09  5063.2  179.91
  5073.8   180.7  5084.3  182.49  5103.1  184.31    5116   186.2  5158.1  189.05
#Mann= 5 ,-1 , 0
  4619.2     .05       0  4815.2      .1       0  4994.3     .07       0
  5000.3      .1       0  5103.1     .05       0
Bank Sta=4994.3,5000.3
XS Rating Curve= 0 ,0
Exp/Cntr=0.3,0.1

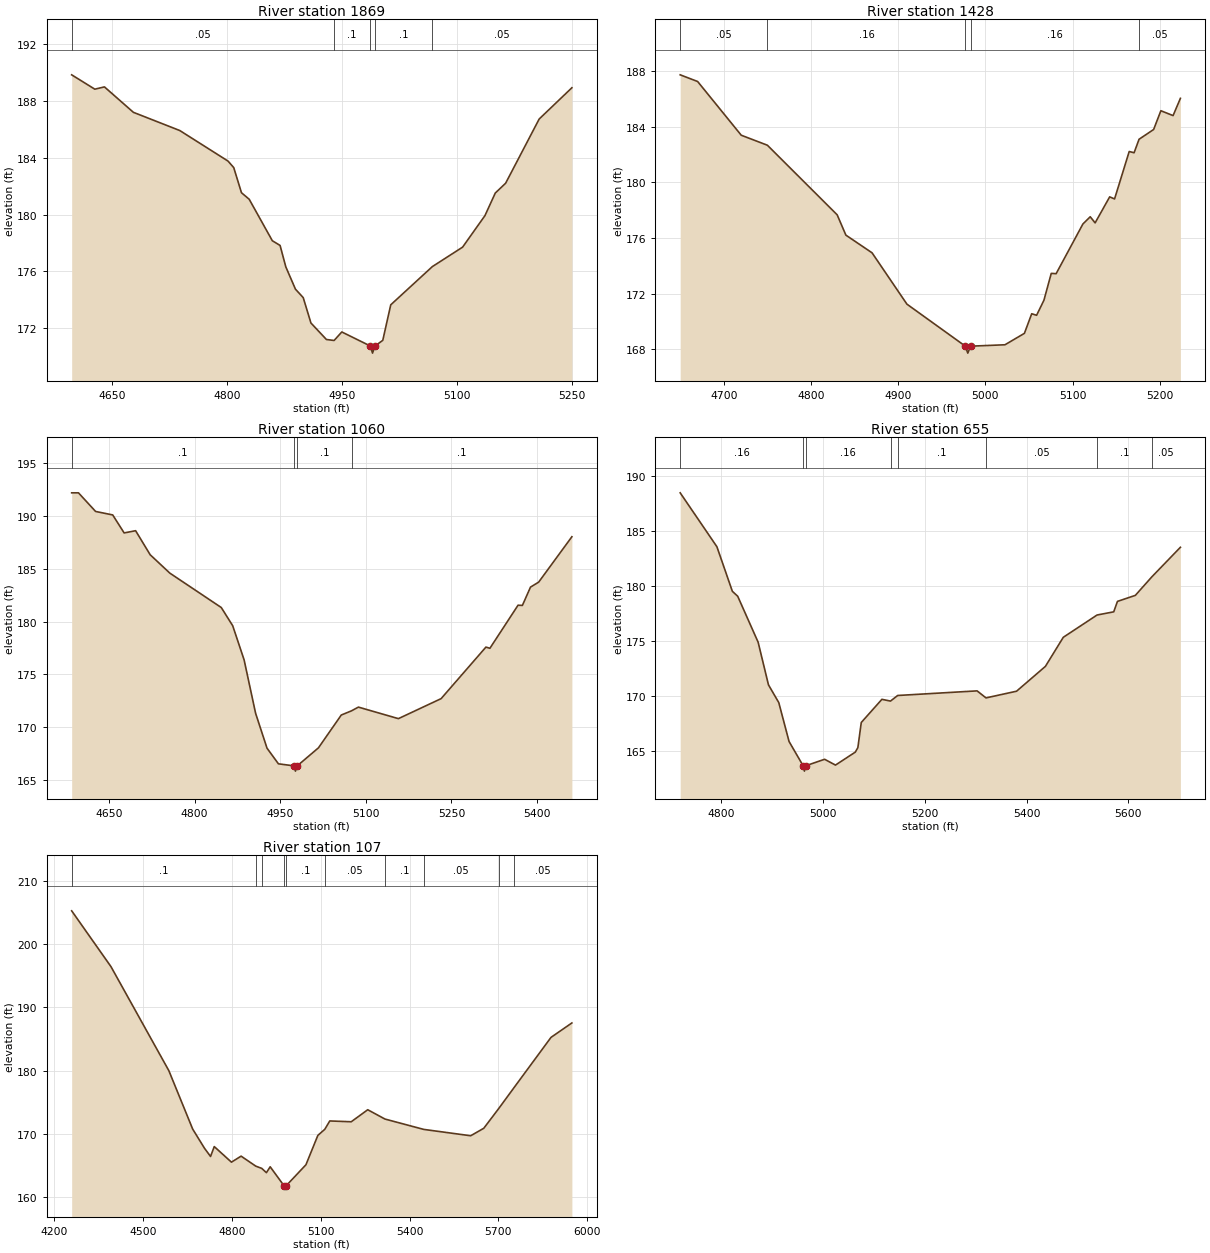
Type RM Length L Ch R = 1 ,1869    ,441,441,441
BEGIN DESCRIPTION:
UNT 066 IN LACR 4.0
END DESCRIPTION:
XS GIS Cut Line= 3
      2275537.72     13213246.84      2275487.72     13212846.85
      2275287.72     13212696.86
#Sta/Elev= 30
  4596.9  189.84  4627.1  188.83  4639.7  188.99  4677.5   187.2    4738  185.92
    4801  183.77  4808.5  183.31  4818.6  181.54  4828.7  181.08  4858.9  178.16
    4869  177.83  4876.5  176.32  4889.1  174.75  4899.2  174.16  4909.3  172.37
  4929.5  171.21  4939.5  171.14  4949.6  171.74  4986.9  170.75  4989.7  170.25
  4992.9  170.75  5003.1  171.15  5013.5  173.65  5067.8  176.34  5107.3  177.71
  5136.5  179.93    5150  181.52  5163.5  182.21  5207.3  186.73    5250  188.93
#Mann= 5 ,-1 , 0
  4596.9     .05       0  4939.5      .1       0  4986.9     .07       0
  4992.9      .1       0  5067.8     .05       0
Bank Sta=4986.9,4992.9
XS Rating Curve= 0 ,0
Exp/Cntr=0.3,0.1

Type RM Length L Ch R = 1 ,1428    ,368,368,368
BEGIN DESCRIPTION:
UNT 066 IN LACR 3.0
END DESCRIPTION:
XS GIS Cut Line= 3
      2275887.72     13213196.85      2275887.72     13212846.85
      2275787.72     13212646.86
#Sta/Elev= 30
    4650  187.72    4670  187.24    4720  183.38    4750  182.66    4830  177.66
    4840   176.2    4870  174.93    4910  171.24    4977  168.22  4979.8  167.72
    4983  168.22  5022.4  168.32  5044.7  169.14  5053.1  170.55  5058.7  170.44
  5067.1  171.52  5075.5  173.45  5081.1  173.43  5111.8     177  5120.2  177.52
  5125.8  177.08  5142.5  178.95  5148.1   178.8  5164.9  182.21  5170.5  182.12
  5176.2  183.09  5192.9  183.79  5201.2  185.14  5215.2  184.79  5223.6  186.03
#Mann= 5 ,-1 , 0
    4650     .05       0    4750     .16       0    4977     .07       0
    4983     .16       0  5176.2     .05       0
Bank Sta=4977,4983
XS Rating Curve= 0 ,0
Exp/Cntr=0.3,0.1

Type RM Length L Ch R = 1 ,1060    ,405,405,405
BEGIN DESCRIPTION:
UNT 066 IN LACR 2.0
END DESCRIPTION:
XS GIS Cut Line= 3
      2276238.71      13213278.7      2276212.67     13212679.77
      2276004.36     13212497.49
#Sta/Elev= 30
  4584.8  192.16  4596.7  192.16  4626.7   190.4  4656.7  190.07  4676.7  188.37
  4696.8  188.58  4722.3  186.31  4756.8  184.57  4846.9  181.32  4866.9   179.6
  4886.9  176.37    4907  171.33    4927  168.03    4947  166.55    4974  166.36
  4976.8  165.86    4980  166.36  5017.1  168.06  5057.1  171.16  5075.1  171.56
  5087.1  171.91  5157.2  170.82    5232  172.71  5310.5  177.58  5317.5  177.47
  5366.8  181.54  5374.4  181.52  5388.6  183.25  5402.9  183.72  5461.1  188.01
#Mann= 4 ,-1 , 0
  4584.8      .1       0    4974     .07       0    4980      .1       0
  5075.1      .1       0
Bank Sta=4974,4980
XS Rating Curve= 0 ,0
Exp/Cntr=0.3,0.1

Type RM Length L Ch R = 1 ,655     ,548,548,548
BEGIN DESCRIPTION:
Mapping XS 2e1fa0c1
END DESCRIPTION:
XS GIS Cut Line= 3
      2276504.62     13213187.99      2276574.07     13212778.26
      2276158.74     13212390.62
#Sta/Elev= 30
  4718.8   188.5    4791  183.59  4821.4  179.53  4831.9  179.08  4872.1  174.89
  4892.4  171.01  4912.7  169.39  4932.9  165.85  4960.4  163.65  4963.1  163.15
  4966.4  163.65  5002.8  164.23  5024.2   163.7  5063.1  164.88  5068.2  165.29
  5074.9  167.58  5115.5  169.69  5132.4  169.53  5146.5  170.04  5302.7  170.46
  5320.2  169.82  5380.3  170.43    5437  172.69  5472.2  175.34  5538.6  177.37
  5571.4  177.66  5578.7  178.61  5613.9  179.16  5646.2  180.84  5702.5  183.54
#Mann= 8 ,-1 , 0
  4718.8     .16       0  4960.4     .07       0  4966.4     .16       0
  5132.4     .05       0  5146.5      .1       0  5320.2     .05       0
  5538.6      .1       0  5646.2     .05       0
Bank Sta=4960.4,4966.4
XS Rating Curve= 0 ,0
Exp/Cntr=0.3,0.1

Type RM Length L Ch R = 1 ,107     ,0,0,0
BEGIN DESCRIPTION:
UNT 066 IN LACR 1.0
END DESCRIPTION:
XS GIS Cut Line= 4
        2276831.     13213375.45      2276754.62     13213069.93
      2276824.07     13212444.93      2276147.54     13212132.88
#Sta/Elev= 30
  4259.4  205.23    4392  196.42  4587.5  179.98    4668  170.75  4708.2   167.7
  4728.3  166.43  4740.8  167.99  4798.8  165.53  4831.4  166.48    4881   164.9
    4901  164.55  4916.9  163.87  4929.6   164.8  4976.9  161.77  4979.6  161.27
  4982.9  161.77  5050.3  165.12  5090.6  169.76    5114  170.72  5130.8  172.04
  5203.2  171.91    5259  173.81  5317.1  172.34  5448.4   170.7  5606.6   169.7
  5650.7  170.88  5700.7  173.97  5754.4   177.4  5877.7  185.24  5948.2  187.52
#Mann= 10 ,-1 , 0
  4259.4      .1       0    4881     .05       0    4901      .1       0
  4976.9     .07       0  4982.9      .1       0    5114     .05       0
  5317.1      .1       0  5448.4     .05       0  5700.7      .1       0
  5754.4     .05       0
Bank Sta=4976.9,4982.9
XS Rating Curve= 0 ,0
Exp/Cntr=0.3,0.1

Chan Stop Cuts=-1
Use User Specified Reach Order=0
Composite Channel Slope=5