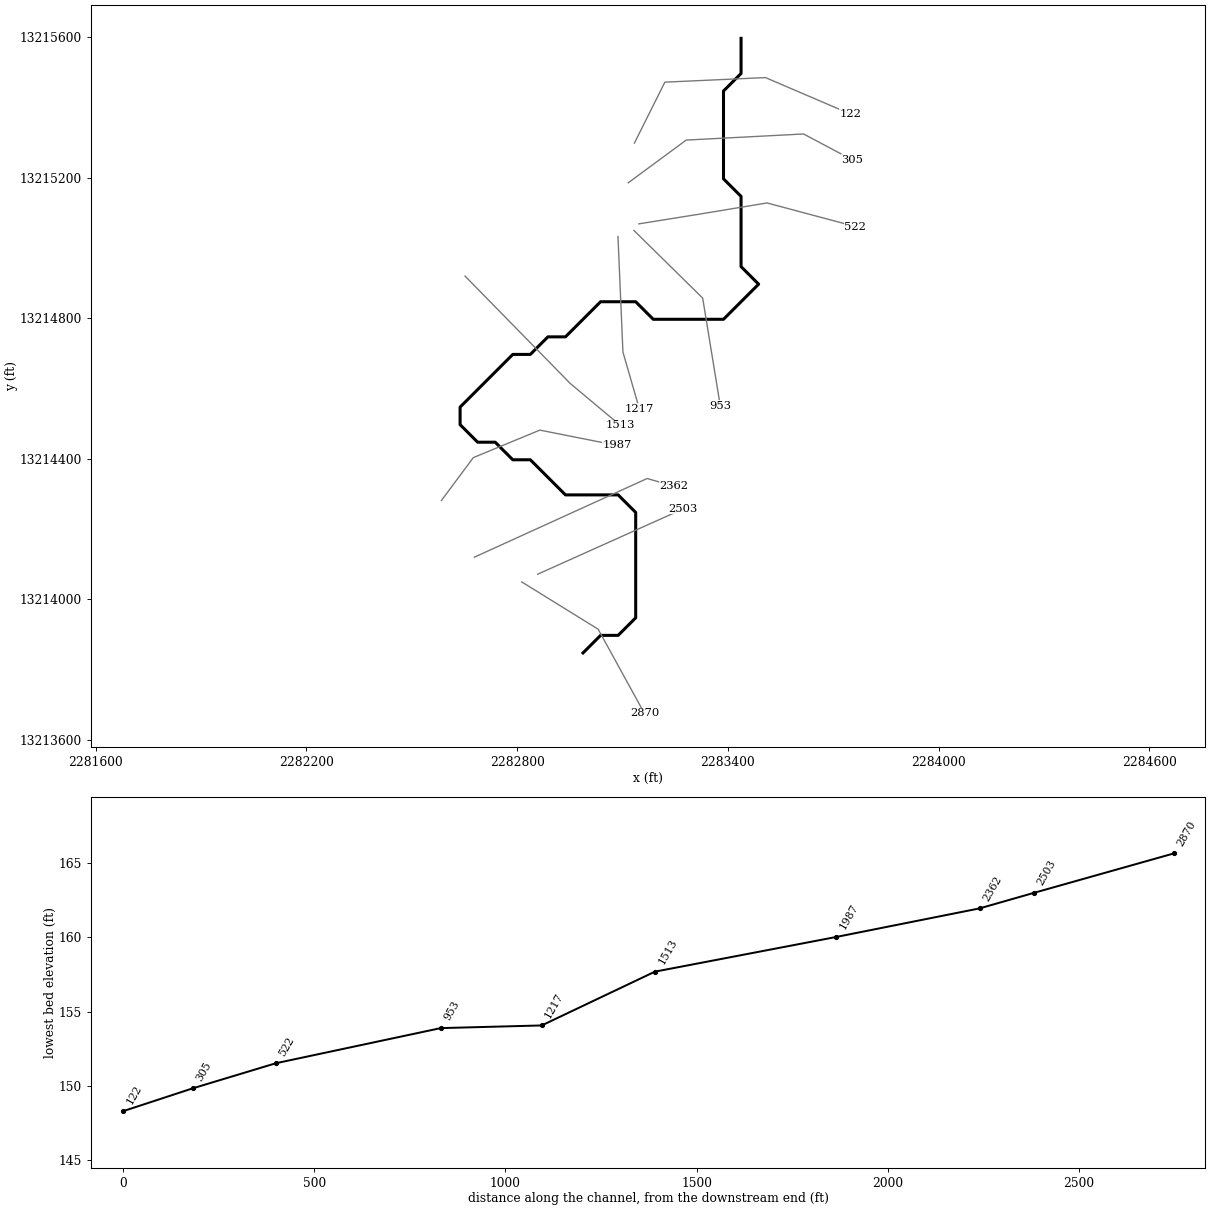
--- UNT 067 IN LACR.prj (project) ---

Proj Title=UNT 067 IN LACR Base Level Engineering
Current Plan=p01
Default Exp/Contr=0.3,0.1
English Units
Geom File=g01
Flow File=f01
Plan File=p01
Y Axis Title=Elevation
X Axis Title(PF)=Main Channel Distance
X Axis Title(XS)=Station
BEGIN DESCRIPTION:
UNT 067 IN LACR
END DESCRIPTION:
DSS Export Rating Curves= 0
DSS Export Rating Curve Sorted= 0
DSS Export Volume Flow Curves= 0
DXF OffsetX= 0
DXF OffsetY= 0
DXF ScaleX= 1
DXF ScaleY= 10

--- UNT 067 IN LACR.p01 (plan) ---

Plan Title=Multiple Run
Short Identifier=Multiple
Geom File=g01
Flow File=f01
Subcritical Flow
K Sum by GR= 0
Std Step Tol= 0.01
Critical Tol= 0.01
Num of Std Step Trials= 20
Max Error Tol= 0.3
Flow Tol Ratio= 0.001
Split Flow NTrial= 30
Split Flow Tol= 0.02
Split Flow Ratio= 0.02
Log Output Level= 0
Friction Slope Method= 1
Unsteady Friction Slope Method= 2
Unsteady Bridges Friction Slope Method= 1
Parabolic Critical Depth
Global Vel Dist=  1 , 1 , 1
Global Log Level= 0
CheckData=True
Encroach Param= -1, 0, 0, 0
BEGIN DESCRIPTION:
Multiple Run
END DESCRIPTION:

--- UNT 067 IN LACR.f01 (steady flow) ---

Flow Title=Multiple
Number of Profiles=7
Profile Names=10-year,25-year,50-year,1pct_min,100-year,1pct_plu,500-year
River Rch & RM= UNT 067 IN LACR,Reach-1,2870
     248     343     422     383     518     700     790
River Rch & RM= UNT 067 IN LACR,Reach-1,1513
     291     406     504     459     621     840     958
Boundary for River Rch & Prof#=UNT 067 IN LACR,Reach-1,1
Up Type=0
Dn Type=3
Dn Slope=0.005
Boundary for River Rch & Prof#=UNT 067 IN LACR,Reach-1,2
Up Type=0
Dn Type=3
Dn Slope=0.005
Boundary for River Rch & Prof#=UNT 067 IN LACR,Reach-1,3
Up Type=0
Dn Type=3
Dn Slope=0.005
Boundary for River Rch & Prof#=UNT 067 IN LACR,Reach-1,4
Up Type=0
Dn Type=3
Dn Slope=0.005
Boundary for River Rch & Prof#=UNT 067 IN LACR,Reach-1,5
Up Type=0
Dn Type=3
Dn Slope=0.005
Boundary for River Rch & Prof#=UNT 067 IN LACR,Reach-1,6
Up Type=0
Dn Type=3
Dn Slope=0.005
Boundary for River Rch & Prof#=UNT 067 IN LACR,Reach-1,7
Up Type=0
Dn Type=3
Dn Slope=0.005

--- UNT 067 IN LACR.g01 (geometry) ---

Geom Title=Existing Conditions
Program Version=4.10

River Reach=UNT 067 IN LACR ,Reach-1
Reach XY= 30
      2282987.72     13213846.85      2283037.72     13213896.85
      2283087.72     13213896.85      2283137.72     13213946.85
      2283137.72     13214246.85      2283087.72     13214296.86
      2282937.72     13214296.86      2282837.72     13214396.85
      2282787.72     13214396.85      2282737.72     13214446.86
      2282687.72     13214446.86      2282637.72     13214496.85
      2282637.72     13214546.85      2282787.72     13214696.85
      2282837.72     13214696.85      2282887.72     13214746.85
      2282937.72     13214746.85      2282987.72     13214796.86
      2283037.72     13214846.85      2283137.72     13214846.85
      2283187.72     13214796.86      2283387.72     13214796.86
      2283437.72     13214846.85      2283487.72     13214896.85
      2283437.72     13214946.86      2283437.72     13215146.85
      2283387.72     13215196.85      2283387.72     13215446.86
      2283437.72     13215496.85      2283437.72     13215596.86

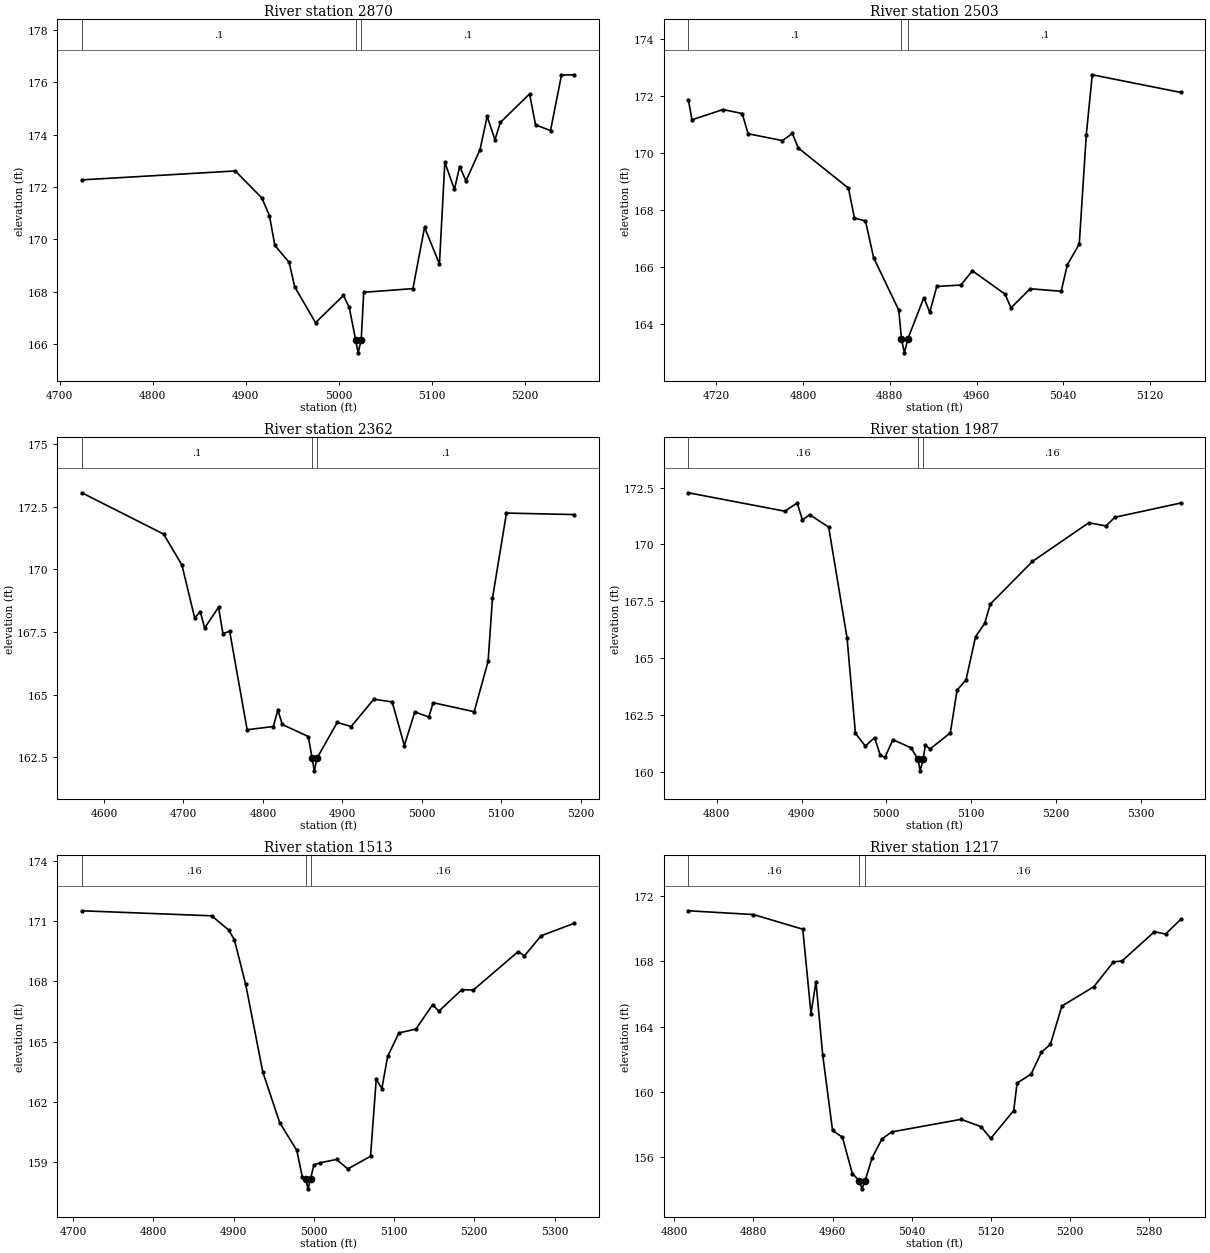
Type RM Length L Ch R = 1 ,2870    ,367,367,367
BEGIN DESCRIPTION:
UNT 067 IN LACR 5.0
END DESCRIPTION:
XS GIS Cut Line= 3
      2282813.16     13214049.07      2283030.88     13213914.36
      2283162.45     13213674.73
#Sta/Elev= 30
    4724  172.27  4888.9  172.61  4917.5  171.58  4925.6  170.91  4931.5  169.77
  4946.8  169.12  4952.8  168.19  4975.2  166.82  5005.2  167.86  5011.4  167.41
  5018.3  166.17    5021  165.67  5024.3  166.17    5027  167.98  5079.9  168.12
  5092.4  170.46  5108.4  169.06  5114.2  172.94  5124.5  171.91  5130.2  172.78
  5136.9  172.23    5152  173.42  5159.7  174.69  5168.1   173.8  5173.8  174.46
  5205.3  175.55  5211.7  174.37  5227.8  174.15  5239.6  176.27  5253.4  176.28
#Mann= 3 ,-1 , 0
    4724      .1       0  5018.3     .07       0  5024.3      .1       0
Bank Sta=5018.3,5024.3
XS Rating Curve= 0 ,0
Exp/Cntr=0.3,0.1

Type RM Length L Ch R = 1 ,2503    ,141,141,141
BEGIN DESCRIPTION:
UNT 067 IN LACR 4.0
END DESCRIPTION:
XS GIS Cut Line= 2
      2282858.57     13214070.96      2283273.19     13214257.15
#Sta/Elev= 30
    4694  171.89  4697.4  171.18    4726  171.54  4743.7   171.4  4749.2  170.69
  4780.8  170.45    4790   170.7  4795.5  170.19  4841.8  168.78  4847.3  167.73
  4857.5  167.63    4865  166.34  4888.2   164.5  4890.7   163.5  4893.4     163
  4896.7   163.5  4911.4  164.94  4916.8  164.42  4923.3  165.33  4945.5  165.38
  4956.2  165.88  4986.3  165.06  4991.8  164.58  5009.5  165.25  5038.1  165.16
  5043.8  166.09  5054.8  166.82  5061.3  170.66  5066.8  172.76  5148.5  172.14
#Mann= 3 ,-1 , 0
    4694      .1       0  4890.7     .07       0  4896.7      .1       0
Bank Sta=4890.7,4896.7
XS Rating Curve= 0 ,0
Exp/Cntr=0.3,0.1

Type RM Length L Ch R = 1 ,2362    ,375,375,375
BEGIN DESCRIPTION:
Mapping XS 68b53be9
END DESCRIPTION:
XS GIS Cut Line= 3
      2282678.46     13214119.51      2283170.27     13214343.49
      2283246.51      13214321.7
#Sta/Elev= 30
  4572.1  173.06    4675  171.41    4698  170.18  4714.1  168.06  4721.1  168.32
  4726.6  167.66  4744.1  168.49  4749.6  167.44  4758.1  167.53  4780.1   163.6
    4813  163.73  4818.8  164.39  4824.3  163.81    4857  163.33  4861.9  162.46
  4864.6  161.96  4867.9  162.46  4893.4  163.89    4911  163.73  4939.5  164.82
  4962.6  164.71  4977.9  162.97  4991.1  164.31  5008.7  164.11  5014.2  164.68
  5065.8  164.32  5083.3  166.33  5088.8  168.85  5106.4  172.25  5191.8  172.19
#Mann= 3 ,-1 , 0
  4572.1      .1       0  4861.9     .07       0  4867.9      .1       0
Bank Sta=4861.9,4867.9
XS Rating Curve= 0 ,0
Exp/Cntr=0.3,0.1

Type RM Length L Ch R = 1 ,1987    ,474,474,474
BEGIN DESCRIPTION:
Mapping XS 6f4d603e
END DESCRIPTION:
XS GIS Cut Line= 4
      2282584.56     13214280.88      2282675.37       13214403.
      2282864.87     13214481.31      2283084.16     13214437.76
#Sta/Elev= 30
  4766.5  172.27  4880.3  171.46  4894.9  171.82  4901.1  171.07  4909.5  171.31
    4932  170.76  4953.7  165.88  4963.6  161.68  4975.3  161.12  4986.1  161.49
  4992.9  160.72  4998.3  160.62  5007.8   161.4  5029.4  161.04  5037.3  160.53
    5040  160.03  5043.3  160.53  5046.1  161.16  5051.5  160.99  5075.5   161.7
  5083.5  163.59    5094  164.03  5105.2  165.93    5116  166.52  5122.6  167.37
  5172.4  169.25  5238.8  170.95  5259.2  170.81  5269.4  171.19  5347.3  171.82
#Mann= 3 ,-1 , 0
  4766.5     .16       0  5037.3     .07       0  5043.3     .16       0
Bank Sta=5037.3,5043.3
XS Rating Curve= 0 ,0
Exp/Cntr=0.3,0.1

Type RM Length L Ch R = 1 ,1513    ,296,296,296
BEGIN DESCRIPTION:
UNT 067 IN LACR 3.0
END DESCRIPTION:
XS GIS Cut Line= 3
      2282651.87     13214919.83      2282951.01     13214614.43
      2283093.88     13214494.86
#Sta/Elev= 30
  4710.9  171.51  4872.7  171.26    4894  170.55    4901  170.07  4915.1  167.85
  4936.4   163.5  4957.5  160.98  4978.8   159.6  4985.8  158.26    4990  158.19
  4992.7  157.69    4996  158.19    5000  158.87  5007.1  158.98  5028.3  159.15
  5042.4  158.68  5070.7  159.31  5077.8  163.14  5084.8  162.67    5092  164.27
  5106.1  165.44  5127.3  165.63    5148  166.84  5155.8  166.52  5184.5  167.59
  5198.8  167.57  5254.7  169.48  5262.5  169.27  5283.4  170.27  5324.7  170.89
#Mann= 3 ,-1 , 0
  4710.9     .16       0    4990     .07       0    4996     .16       0
Bank Sta=4990,4996
XS Rating Curve= 0 ,0
Exp/Cntr=0.3,0.1

Type RM Length L Ch R = 1 ,1217    ,264,264,264
BEGIN DESCRIPTION:
UNT 067 IN LACR 2.0
END DESCRIPTION:
XS GIS Cut Line= 3
      2283087.26     13215032.58      2283101.36      13214703.7
       2283148.2     13214541.31
#Sta/Elev= 30
  4814.1   171.1  4879.9  170.87  4929.9  169.97  4938.2   164.8  4943.2  166.75
    4950  162.29    4960  157.64    4970  157.22    4980     155    4987  154.56
  4989.7  154.06    4993  154.56    5000  155.96    5010  157.12    5020  157.55
  5090.1  158.32  5110.1  157.87  5120.1  157.15  5143.3  158.86  5146.7  160.55
  5160.8  161.08  5171.2  162.42  5180.4  162.92    5192  165.26  5224.4  166.45
  5244.1  167.96  5252.9  168.03  5285.7  169.82  5296.9  169.67  5312.3  170.58
#Mann= 3 ,-1 , 0
  4814.1     .16       0    4987     .07       0    4993     .16       0
Bank Sta=4987,4993
XS Rating Curve= 0 ,0
Exp/Cntr=0.3,0.1

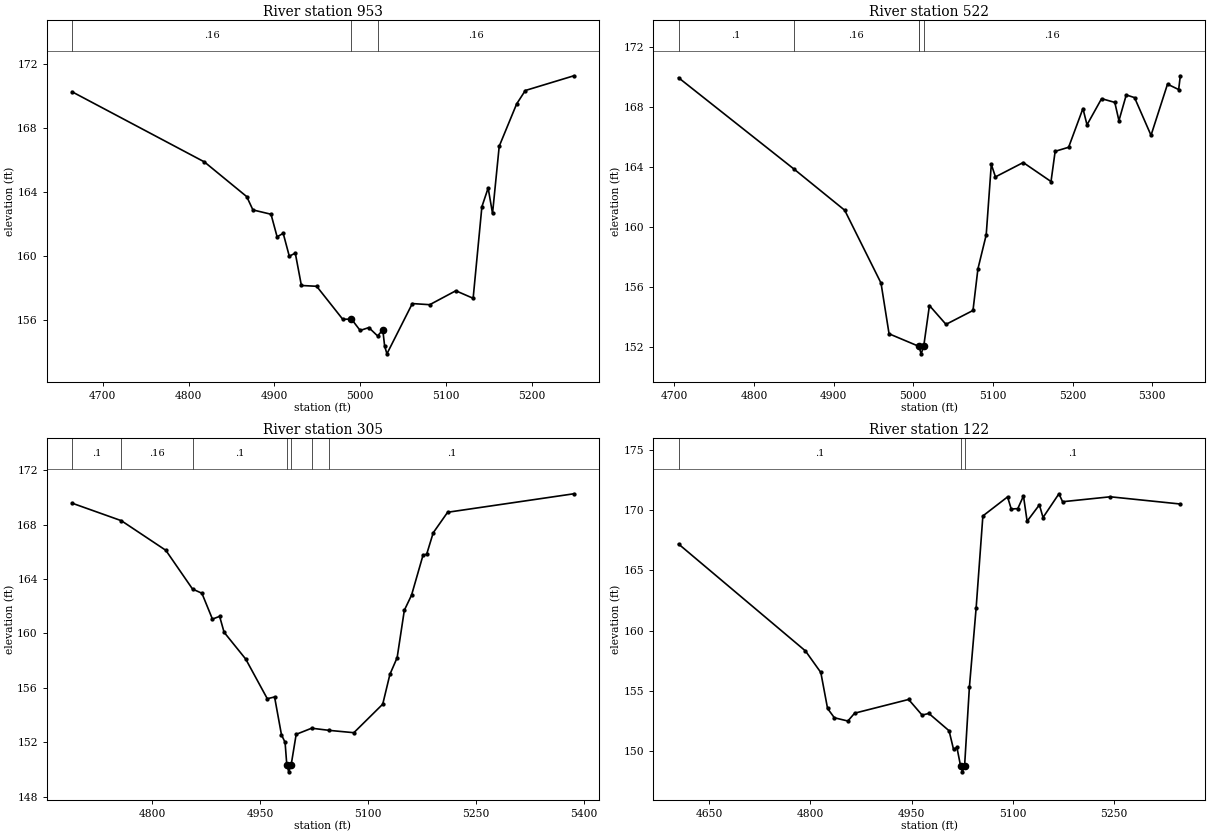
Type RM Length L Ch R = 1 ,953     ,431,431,431
BEGIN DESCRIPTION:
Mapping XS c9241309
END DESCRIPTION:
XS GIS Cut Line= 3
      2283132.67     13215049.83      2283328.45     13214857.18
      2283378.44     13214551.01
#Sta/Elev= 30
  4664.2  170.25  4818.4  165.87  4867.8   163.7    4875  162.87  4896.1   162.6
  4903.2  161.19  4910.3  161.41  4917.4  159.98  4924.4  160.17  4931.5  158.15
  4949.3   158.1  4979.7  156.04  4989.9  156.05    5000  155.34  5010.1  155.52
  5020.3     155  5026.4  155.37  5028.5  154.38  5031.2  153.88  5060.8  157.02
  5081.1  156.95  5111.5  157.82  5131.7  157.35  5141.9  163.07  5149.2  164.24
  5154.3  162.65  5162.1  166.85  5182.4  169.49  5192.5  170.33  5249.1  171.25
#Mann= 3 ,-1 , 0
  4664.2     .16       0  4989.9     .07       0  5020.3     .16       0
Bank Sta=4989.9,5026.4
XS Rating Curve= 0 ,0
Exp/Cntr=0.3,0.1

Type RM Length L Ch R = 1 ,522     ,217,217,217
BEGIN DESCRIPTION:
Mapping XS bc4f778a
END DESCRIPTION:
XS GIS Cut Line= 4
      2283146.74      13215068.6      2283312.79     13215095.23
      2283511.69     13215128.12       2283763.3     13215060.92
#Sta/Elev= 30
  4705.2  169.97  4849.8  163.88  4913.9  161.11  4959.5  156.24  4969.6  152.85
  5007.1  152.01  5009.9  151.51  5013.1  152.01  5020.3  154.74  5041.1  153.48
    5075  154.41  5081.2  157.19  5091.6  159.46    5098  164.18  5103.2  163.34
  5138.1   164.3    5173  163.03  5178.2  165.05  5195.1  165.32  5213.1  167.91
  5218.2  166.82  5236.5  168.57  5253.1  168.32  5258.3   167.1  5267.5  168.82
  5277.9  168.64  5298.6  166.12  5319.3  169.54  5333.3  169.18  5335.4   170.1
#Mann= 5 ,-1 , 0
  4705.2      .1       0  4849.8     .16       0  5007.1      .1       0
  5007.1     .07       0  5013.1     .16       0
Bank Sta=5007.1,5013.1
XS Rating Curve= 0 ,0
Exp/Cntr=0.3,0.1

Type RM Length L Ch R = 1 ,305     ,183,183,183
BEGIN DESCRIPTION:
Mapping XS 4899e25e
END DESCRIPTION:
XS GIS Cut Line= 4
       2283116.6     13215185.62      2283281.54     13215307.15
      2283615.74     13215324.51      2283754.63     13215250.73
#Sta/Elev= 30
  4688.8  169.59  4757.2   168.3    4819  166.12  4856.1  163.27  4869.1  162.96
  4883.7  161.06  4893.7  161.26  4899.9  160.09  4929.9  158.12  4959.9   155.2
    4970  155.33  4979.6  152.54  4984.6  151.99    4987  150.32  4989.7  149.82
    4993  150.32    5000  152.58  5021.5  153.03  5046.1  152.87  5080.1   152.7
  5120.2   154.8  5130.2     157  5140.2  158.22  5150.2  161.71  5160.2  162.82
  5176.2  165.77  5181.2  165.83  5190.3  167.41  5210.3  168.92  5385.6  170.28
#Mann= 7 ,-1 , 0
  4688.8      .1       0  4757.2     .16       0  4856.1      .1       0
    4987     .07       0    4993      .1       0  5021.5     .16       0
  5046.1      .1       0
Bank Sta=4987,4993
XS Rating Curve= 0 ,0
Exp/Cntr=0.3,0.1

Type RM Length L Ch R = 1 ,122     ,0,0,0
BEGIN DESCRIPTION:
UNT 067 IN LACR 1.0
END DESCRIPTION:
XS GIS Cut Line= 4
      2283133.99      13215298.5      2283220.77     13215472.08
      2283507.23      13215485.1      2283749.22     13215381.39
#Sta/Elev= 30
  4604.4  167.19  4792.6  158.31  4815.4  156.52  4825.4  153.53  4835.5  152.76
  4855.5  152.49  4865.5  153.14  4945.6  154.28  4965.6  152.98  4975.6  153.12
  5005.6  151.68  5012.2  150.13  5017.2   150.3  5022.6  148.77  5025.4  148.27
  5028.6  148.77  5035.7  155.29  5045.7  161.87  5055.7  169.52  5092.3   171.1
  5097.8  170.09  5107.5  170.13  5115.9  171.18  5121.3  169.08  5139.5  170.44
  5144.9  169.39  5168.5  171.36  5173.9   170.7  5244.6  171.11  5348.5  170.51
#Mann= 3 ,-1 , 0
  4604.4      .1       0  5022.6     .07       0  5028.6      .1       0
Bank Sta=5022.6,5028.6
XS Rating Curve= 0 ,0
Exp/Cntr=0.3,0.1

Chan Stop Cuts=-1
Use User Specified Reach Order=0
Composite Channel Slope=5