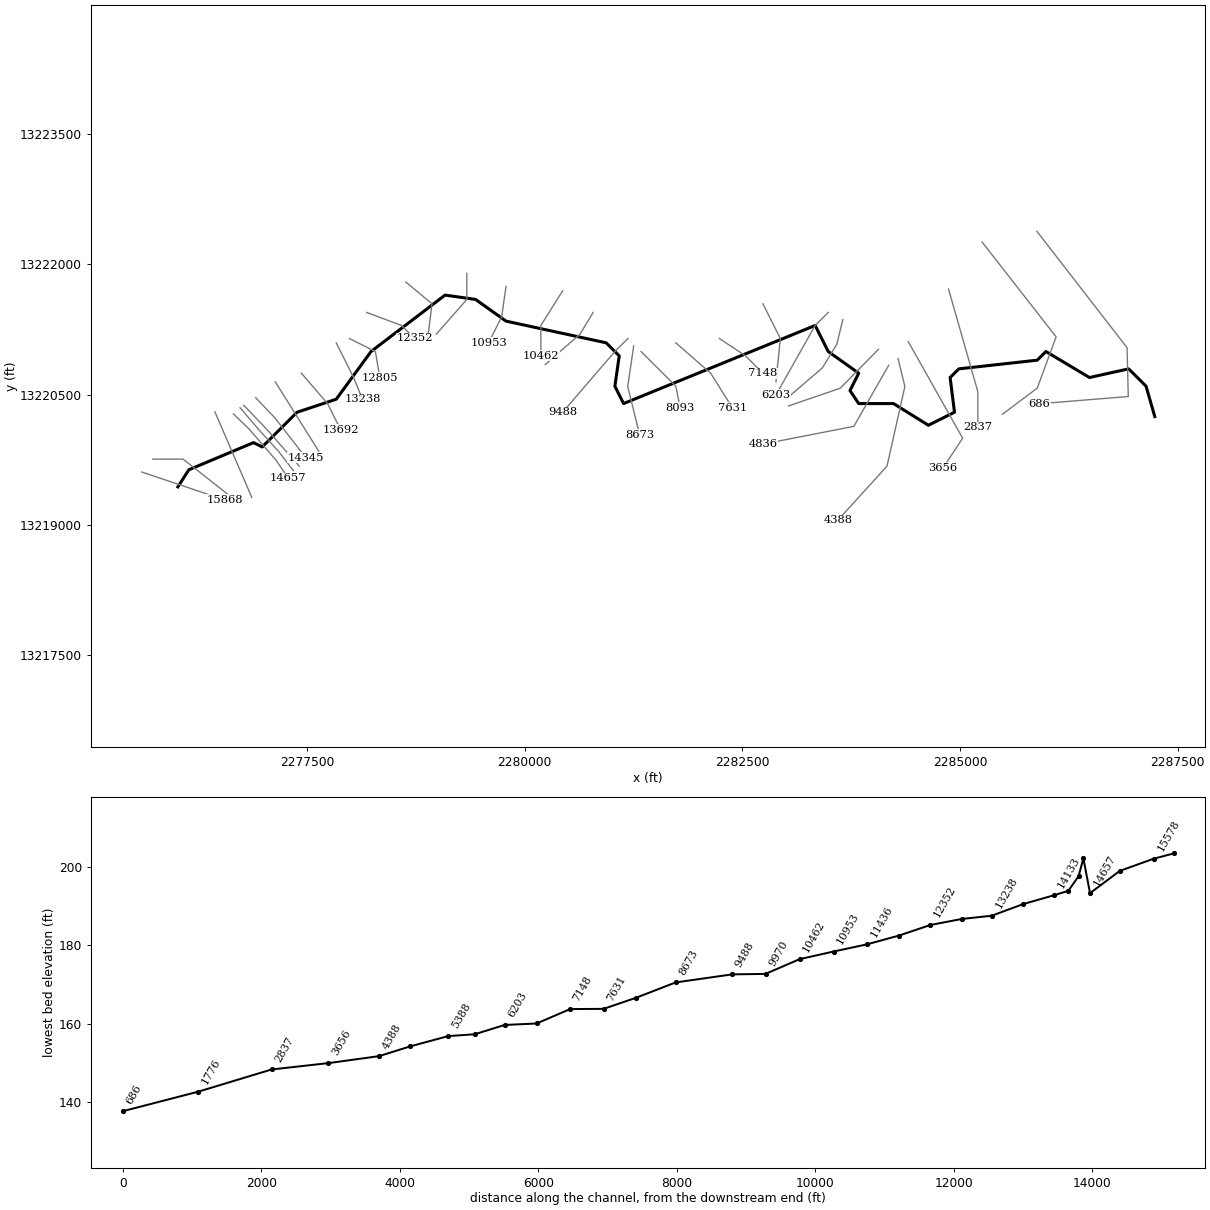
--- UNT 068 IN LACR.prj (project) ---

Proj Title=UNT 068 IN LACR Base Level Engineering
Current Plan=p01
Default Exp/Contr=0.3,0.1
English Units
Geom File=g01
Flow File=f01
Plan File=p01
Y Axis Title=Elevation
X Axis Title(PF)=Main Channel Distance
X Axis Title(XS)=Station
BEGIN DESCRIPTION:
UNT 068 IN LACR
END DESCRIPTION:
DSS Export Rating Curves= 0
DSS Export Rating Curve Sorted= 0
DSS Export Volume Flow Curves= 0
DXF OffsetX= 0
DXF OffsetY= 0
DXF ScaleX= 1
DXF ScaleY= 10

--- UNT 068 IN LACR.p01 (plan) ---

Plan Title=Multiple Run
Short Identifier=Multiple
Geom File=g01
Flow File=f01
Subcritical Flow
K Sum by GR= 0
Std Step Tol= 0.01
Critical Tol= 0.01
Num of Std Step Trials= 20
Max Error Tol= 0.3
Flow Tol Ratio= 0.001
Split Flow NTrial= 30
Split Flow Tol= 0.02
Split Flow Ratio= 0.02
Log Output Level= 0
Friction Slope Method= 1
Unsteady Friction Slope Method= 2
Unsteady Bridges Friction Slope Method= 1
Parabolic Critical Depth
Global Vel Dist=  1 , 1 , 1
Global Log Level= 0
CheckData=True
Encroach Param= -1, 0, 0, 0
BEGIN DESCRIPTION:
Multiple Run
END DESCRIPTION:

--- UNT 068 IN LACR.f01 (steady flow) ---

Flow Title=Multiple
Number of Profiles=7
Profile Names=10-year,25-year,50-year,1pct_min,100-year,1pct_plu,500-year
River Rch & RM= UNT 068 IN LACR,Reach-1,15868
     214     293     358     322     435     588     652
River Rch & RM= UNT 068 IN LACR,Reach-1,15087
     320     446     552     502     678     917    1040
River Rch & RM= UNT 068 IN LACR,Reach-1,8093
     403     567     706     645     872    1180    1353
Boundary for River Rch & Prof#=UNT 068 IN LACR,Reach-1,1
Up Type=0
Dn Type=3
Dn Slope=0.005
Boundary for River Rch & Prof#=UNT 068 IN LACR,Reach-1,2
Up Type=0
Dn Type=3
Dn Slope=0.005
Boundary for River Rch & Prof#=UNT 068 IN LACR,Reach-1,3
Up Type=0
Dn Type=3
Dn Slope=0.005
Boundary for River Rch & Prof#=UNT 068 IN LACR,Reach-1,4
Up Type=0
Dn Type=3
Dn Slope=0.005
Boundary for River Rch & Prof#=UNT 068 IN LACR,Reach-1,5
Up Type=0
Dn Type=3
Dn Slope=0.005
Boundary for River Rch & Prof#=UNT 068 IN LACR,Reach-1,6
Up Type=0
Dn Type=3
Dn Slope=0.005
Boundary for River Rch & Prof#=UNT 068 IN LACR,Reach-1,7
Up Type=0
Dn Type=3
Dn Slope=0.005

--- UNT 068 IN LACR.g01 (geometry) ---

Geom Title=Existing Conditions
Program Version=4.10

River Reach=UNT 068 IN LACR ,Reach-1
Reach XY= 30
      2276019.14     13219436.38        2276145.     13219633.86
      2276887.72     13219946.85      2276987.72     13219896.85
      2277387.72     13220296.85      2277837.72     13220446.85
      2278237.72     13220996.85      2279087.72     13221646.85
      2279437.72     13221596.85      2279787.72     13221346.86
      2280937.72     13221096.85      2281087.72     13220946.85
      2281037.72     13220596.85      2281137.72     13220396.85
      2283337.72     13221296.85      2283487.72     13220996.85
      2283837.72     13220746.85      2283737.72     13220546.86
      2283837.72     13220396.85      2284237.72     13220396.85
      2284637.72     13220146.85      2284937.72     13220296.85
      2284887.72     13220696.86      2284987.72     13220796.85
      2285887.72     13220896.85      2285987.72     13220996.85
      2286487.72     13220696.86      2286937.72     13220796.85
      2287137.72     13220596.85      2287237.72     13220246.85

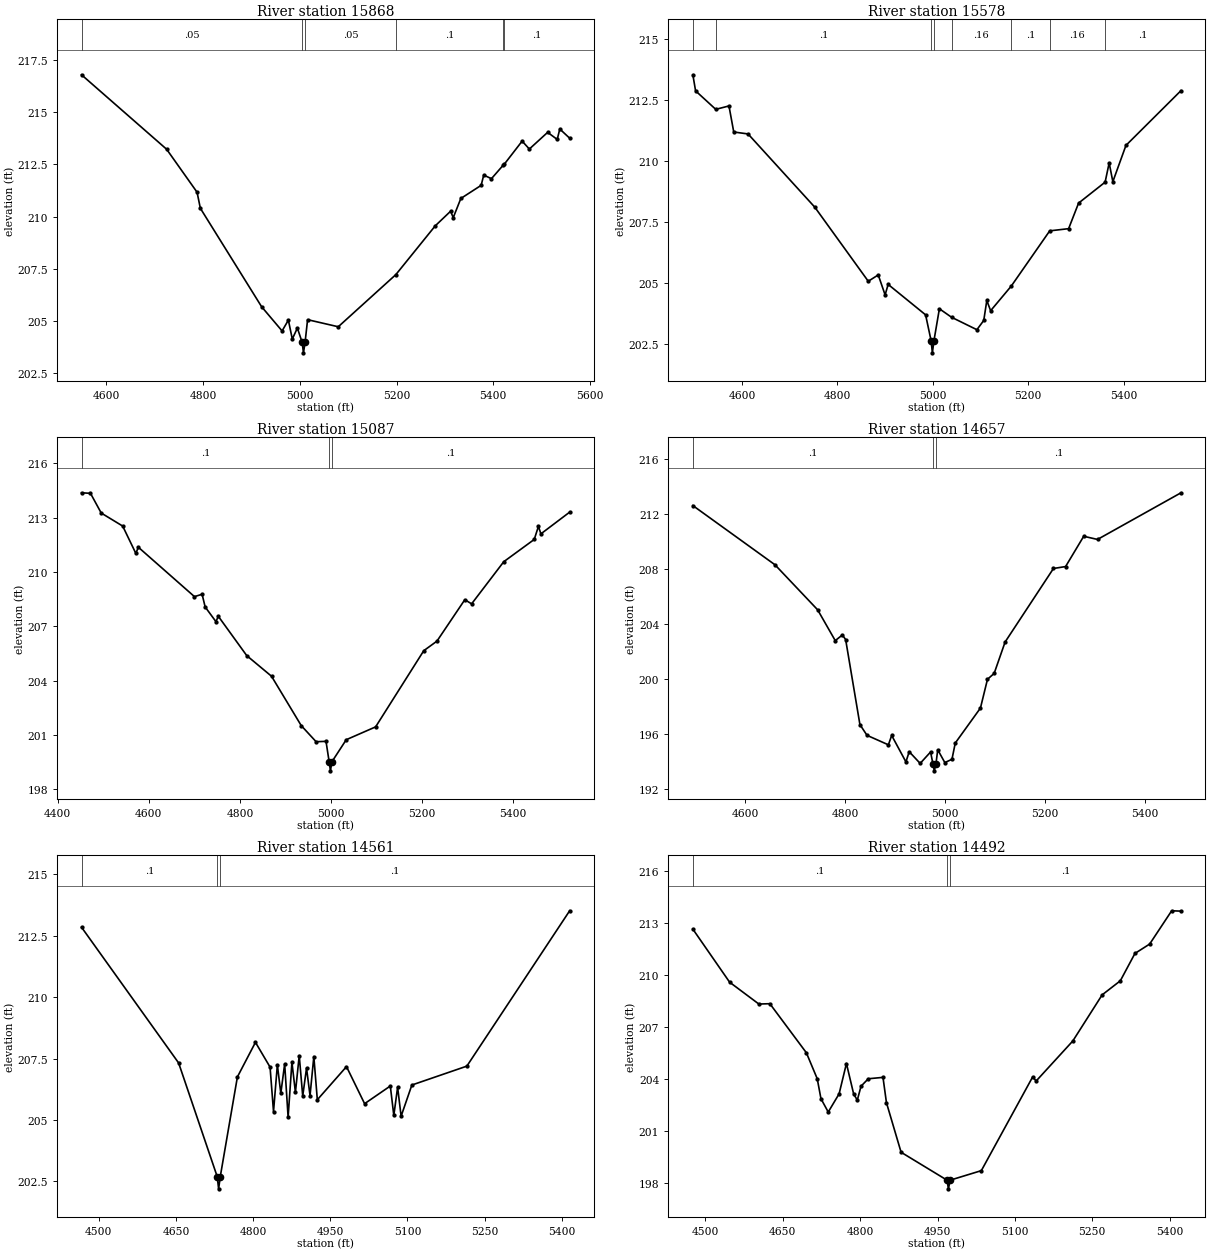
Type RM Length L Ch R = 1 ,15868   ,290,290,290
BEGIN DESCRIPTION:
UNT 068 IN LACR 24.0
END DESCRIPTION:
XS GIS Cut Line= 2
      2275605.06     13219607.82      2276560.78     13219284.91
#Sta/Elev= 30
    4549   216.8  4724.9  213.23  4787.8  211.17  4794.6   210.4  4921.2  205.68
  4963.5  204.52  4976.5  205.04  4984.6  204.13  4995.1  204.66    5005  203.97
  5007.7  203.47    5011  203.97  5016.2  205.06  5079.6  204.72  5198.6  207.22
  5280.1  209.56  5311.8  210.26  5317.2  209.95  5332.9  210.87  5374.9   211.5
  5380.2  211.99  5396.2  211.82  5420.6  212.47  5422.6  212.51  5459.6  213.62
  5474.5  213.24  5512.3  214.04  5532.1   213.7  5537.4   214.2  5557.8  213.76
#Mann= 6 ,-1 , 0
    4549     .05       0    5005     .04       0    5011     .05       0
  5198.6      .1       0  5420.6     .16       0  5422.6      .1       0
Bank Sta=5005,5011
XS Rating Curve= 0 ,0
Exp/Cntr=0.3,0.1

Type RM Length L Ch R = 1 ,15578   ,491,491,491
BEGIN DESCRIPTION:
Mapping XS ba631d28
END DESCRIPTION:
XS GIS Cut Line= 3
      2275732.01     13219756.47      2276079.61     13219756.47
      2276609.84     13219337.64
#Sta/Elev= 30
  4497.1  213.55  4502.8  212.89  4545.1  212.13  4572.8  212.27  4582.8   211.2
  4612.8  211.12  4752.8  208.11  4864.8  205.07  4885.7  205.33  4900.1  204.51
  4906.5  204.94    4985  203.69  4996.5  202.63  4999.2  202.13  5002.5  202.63
  5013.9  203.94  5039.5  203.59  5092.5  203.08  5106.9  203.46  5113.3  204.28
  5121.3  203.86  5164.5  204.87  5245.2  207.14  5284.8  207.23  5305.7  208.28
  5361.3  209.14  5369.8  209.93  5377.5  209.16    5405  210.65  5520.4   212.9
#Mann= 8 ,-1 , 0
  4497.1     .05       0  4545.1      .1       0  4996.5     .07       0
  5002.5      .1       0  5039.5     .16       0  5164.5      .1       0
  5245.2     .16       0  5361.3      .1       0
Bank Sta=4996.5,5002.5
XS Rating Curve= 0 ,0
Exp/Cntr=0.3,0.1

Type RM Length L Ch R = 1 ,15087   ,430,430,430
BEGIN DESCRIPTION:
Mapping XS 1c2ce041
END DESCRIPTION:
XS GIS Cut Line= 2
      2276444.99     13220300.13      2276868.31     13219315.36
#Sta/Elev= 30
  4452.2  214.38  4471.9  214.35  4495.5  213.26  4542.6  212.54  4571.5  211.03
    4577  211.37  4700.2  208.64    4717  208.77  4723.7  208.07  4747.3  207.26
  4752.7  207.55    4815  205.38  4869.4  204.24  4934.7  201.51  4967.3  200.62
  4989.1  200.64    4996  199.51  4998.8  199.01    5002  199.51  5033.5  200.73
    5098  201.44  5203.7  205.65  5232.7  206.18  5293.9  208.47  5308.8  208.24
  5379.4  210.57  5446.3   211.8  5455.5  212.52    5461  212.11  5524.1  213.31
#Mann= 3 ,-1 , 0
  4452.2      .1       0    4996     .07       0    5002      .1       0
Bank Sta=4996,5002
XS Rating Curve= 0 ,0
Exp/Cntr=0.3,0.1

Type RM Length L Ch R = 1 ,14657   ,96,96,96
BEGIN DESCRIPTION:
Mapping XS 10dd0d77
END DESCRIPTION:
XS GIS Cut Line= 4
       2276656.2     13220277.73      2276833.85     13220107.25
      2277146.19     13219744.77      2277288.01     13219535.62
#Sta/Elev= 30
  4495.5   212.6  4659.9   208.3  4745.3  205.03  4780.6  202.79  4794.8   203.2
  4801.4  202.87    4830  196.69  4844.2  195.91    4887  195.22  4893.6   195.9
  4922.1  193.98  4928.7  194.72  4950.6  193.87  4971.5   194.7  4976.2  193.83
  4978.9  193.33  4982.2  193.83  4985.8  194.86    5000  193.93  5014.3  194.17
  5020.9  195.35  5071.3  197.89  5085.4  199.98  5098.8  200.41  5120.7  202.69
  5217.5  208.03  5241.8  208.17  5278.1  210.37  5305.7  210.14  5472.9  213.53
#Mann= 3 ,-1 , 0
  4495.5      .1       0  4976.2     .07       0  4982.2      .1       0
Bank Sta=4976.2,4982.2
XS Rating Curve= 0 ,0
Exp/Cntr=0.3,0.1

Type RM Length L Ch R = 1 ,14561   ,69,69,69
BEGIN DESCRIPTION:
Mapping XS 587f45aa
END DESCRIPTION:
XS GIS Cut Line= 4
      2276733.57     13220349.37      2276939.87     13220105.82
      2277174.84     13219846.49      2277345.33     13219624.42
#Sta/Elev= 30
  4466.3  212.85  4655.1  207.32  4730.1  202.69  4732.9  202.19  4736.1  202.69
  4769.4  206.75  4804.5  208.16  4832.9  207.15  4839.6  205.34  4847.1  207.24
  4853.8  206.08  4861.3  207.28    4868  205.11  4875.4  207.35  4882.2  206.12
  4889.6  207.62  4896.4  205.97  4903.8  207.11  4910.6  205.99    4918  207.58
  4924.8  205.82  4981.5  207.17  5016.7  205.66  5066.7  206.38  5073.5  205.18
  5080.9  206.33  5087.7  205.15  5108.6  206.42  5215.5  207.19  5415.4  213.52
#Mann= 3 ,-1 , 0
  4466.3      .1       0  4730.1     .07       0  4736.1      .1       0
Bank Sta=4730.1,4736.1
XS Rating Curve= 0 ,0
Exp/Cntr=0.3,0.1

Type RM Length L Ch R = 1 ,14492   ,147,147,147
BEGIN DESCRIPTION:
Mapping XS a8c9abe8
END DESCRIPTION:
XS GIS Cut Line= 3
      2276776.51     13220376.64      2277022.97     13220118.71
       2277412.7     13219675.97
#Sta/Elev= 30
  4475.6  212.66  4546.9   209.6  4603.6  208.34  4624.9  208.36  4695.7  205.53
  4716.8  204.03    4724  202.88  4738.1  202.11  4759.2  203.16  4773.4  204.91
  4787.5  203.14  4794.5   202.8  4801.7   203.6  4815.8  204.03  4844.3  204.11
    4851  202.65  4879.4  199.79  4968.5  198.18  4971.2  197.68  4974.5  198.18
    5035  198.73  5134.6  204.14  5141.3   203.9  5212.4  206.21  5269.3  208.87
  5304.5  209.68  5332.9  211.26  5361.4   211.8  5404.1  213.72  5422.2   213.7
#Mann= 3 ,-1 , 0
  4475.6      .1       0  4968.5     .07       0  4974.5      .1       0
Bank Sta=4968.5,4974.5
XS Rating Curve= 0 ,0
Exp/Cntr=0.3,0.1

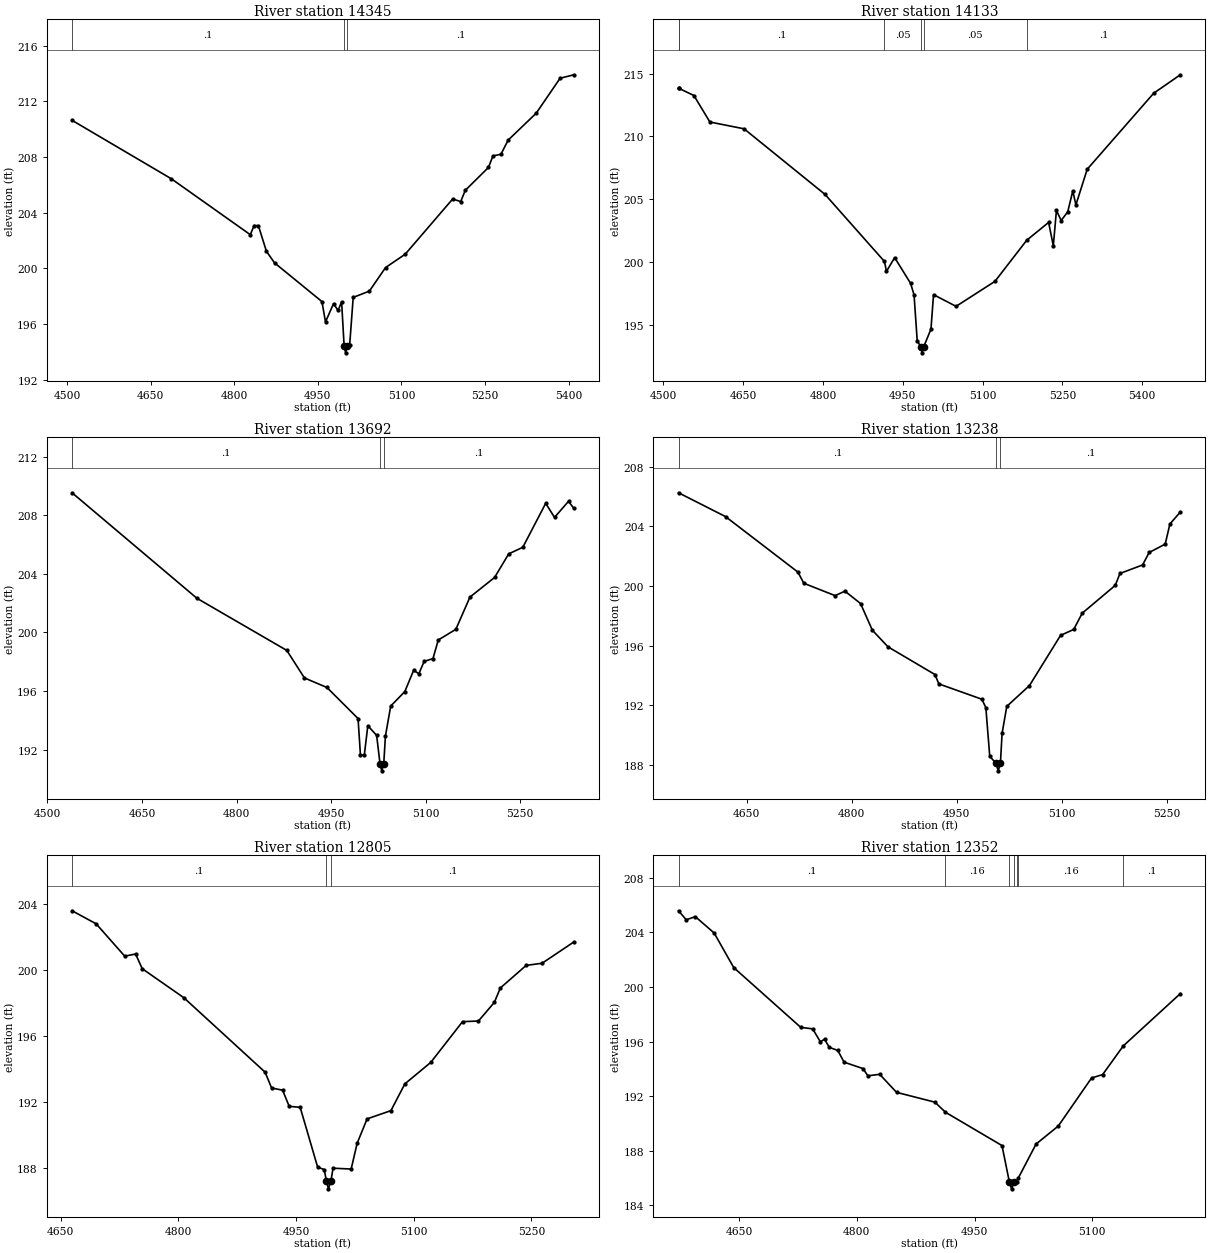
Type RM Length L Ch R = 1 ,14345   ,212,212,212
BEGIN DESCRIPTION:
Mapping XS 0276f36d
END DESCRIPTION:
XS GIS Cut Line= 3
      2276912.67     13220463.98      2277133.29      13220231.9
      2277488.64     13219773.39
#Sta/Elev= 30
  4509.1  210.63  4687.4  206.43  4828.9  202.42  4835.7  203.08  4843.4  203.07
  4857.8  201.23  4872.3   200.4  4957.4  197.62  4963.8  196.16  4978.2  197.47
  4986.4  196.98  4992.7   197.6  4997.2  194.44  4999.9  193.94  5003.2  194.44
  5007.2  194.52  5013.5  197.92  5042.5  198.37  5071.5  200.06  5106.8  201.02
  5191.9  204.98  5206.4   204.8  5214.5   205.6  5256.2  207.25  5264.3  208.08
  5278.5  208.19  5291.5  209.21  5341.8  211.14  5384.7  213.65  5409.4   213.9
#Mann= 3 ,-1 , 0
  4509.1      .1       0  4997.2     .07       0  5003.2      .1       0
Bank Sta=4997.2,5003.2
XS Rating Curve= 0 ,0
Exp/Cntr=0.3,0.1

Type RM Length L Ch R = 1 ,14133   ,441,441,441
BEGIN DESCRIPTION:
UNT 068 IN LACR 22.0
END DESCRIPTION:
XS GIS Cut Line= 3
      2277137.72     13220646.86      2277387.72     13220246.85
      2277637.72     13219846.85
#Sta/Elev= 30
  4528.3  213.82  4529.5  213.82  4557.2  213.26  4587.3  211.15  4651.5  210.61
  4803.7  205.39  4915.5  200.05  4919.2  199.26  4934.6  200.36  4964.6  198.31
  4971.1  197.39    4977  193.76  4983.4  193.28  4986.2  192.78  4989.4  193.28
  5002.9  194.67  5007.7  197.41  5050.1  196.48  5123.2  198.47  5182.9  201.74
  5224.1  203.16  5232.9   201.3  5238.8  204.12  5247.6  203.31    5260     204
  5269.5  205.66  5275.4  204.56  5296.6  207.39  5421.6  213.44  5471.7  214.91
#Mann= 6 ,-1 , 0
  4528.3     .05       0  4529.5      .1       0  4915.5     .05       0
  4983.4     .04       0  4989.4     .05       0  5182.9      .1       0
Bank Sta=4983.4,4989.4
XS Rating Curve= 0 ,0
Exp/Cntr=0.3,0.1

Type RM Length L Ch R = 1 ,13692   ,454,454,454
BEGIN DESCRIPTION:
UNT 068 IN LACR 21.0
END DESCRIPTION:
XS GIS Cut Line= 3
      2277437.71     13220746.87      2277737.72     13220396.85
      2277887.72     13220096.86
#Sta/Elev= 30
    4539  209.53  4737.1  202.33  4879.8  198.77  4907.8  196.89  4943.5  196.24
  4992.9  194.12  4996.7  191.62  5002.8  191.62  5008.4  193.63  5022.4  192.97
  5027.7  191.05  5030.5  190.55  5033.7  191.05  5036.3  192.91  5044.7  194.97
  5067.1  195.96  5081.1  197.41  5089.4  197.18  5097.8  198.02  5111.8  198.21
  5120.2  199.48  5148.1  200.21  5170.5  202.41  5209.6  203.75    5232  205.36
  5254.4  205.81  5290.7  208.81  5304.7  207.85    5327  208.95  5335.4  208.46
#Mann= 3 ,-1 , 0
    4539      .1       0  5027.7     .07       0  5033.7      .1       0
Bank Sta=5027.7,5033.7
XS Rating Curve= 0 ,0
Exp/Cntr=0.3,0.1

Type RM Length L Ch R = 1 ,13238   ,433,433,433
BEGIN DESCRIPTION:
UNT 068 IN LACR 20.0
END DESCRIPTION:
XS GIS Cut Line= 3
      2277837.73     13221096.84      2278037.72     13220696.86
      2278137.74     13220446.82
#Sta/Elev= 30
  4552.8  206.26  4619.9  204.66  4723.3  200.93  4731.7  200.18  4776.4  199.35
  4790.4  199.65  4812.7  198.82  4829.5  197.03  4851.9  195.91  4918.9  194.05
  4924.5  193.42    4986  192.39  4991.6  191.82  4997.2  188.55  5006.4  188.08
  5009.2  187.58  5012.4  188.08  5014.8   190.1  5021.5  191.91  5053.9  193.31
  5098.3  196.68  5117.1  197.08  5129.2  198.17  5176.4  200.04  5183.1  200.84
  5215.4  201.41  5224.8  202.25  5247.7  202.81  5254.4  204.16  5269.3  204.97
#Mann= 3 ,-1 , 0
  4552.8      .1       0  5006.4     .07       0  5012.4      .1       0
Bank Sta=5006.4,5012.4
XS Rating Curve= 0 ,0
Exp/Cntr=0.3,0.1

Type RM Length L Ch R = 1 ,12805   ,453,453,453
BEGIN DESCRIPTION:
UNT 068 IN LACR 19.0
END DESCRIPTION:
XS GIS Cut Line= 3
      2277987.73     13221146.85      2278287.72     13220996.85
      2278337.71     13220696.89
#Sta/Elev= 30
  4664.6   203.6  4695.3  202.81  4731.7  200.85  4745.6  200.98    4754  200.09
  4807.1  198.33  4910.6  193.82  4918.9  192.86  4932.9  192.73  4941.3  191.75
  4955.3  191.69  4977.6  188.06    4986  187.92  4988.6  187.25  4991.4  186.75
  4994.6  187.25  4997.2     188  5020.3  187.95  5027.9  189.51  5040.6  190.99
    5071  191.49  5088.7  193.11  5121.7  194.41  5162.2  196.88  5182.5  196.92
  5202.8  198.05  5210.4  198.92  5243.3  200.29  5263.6  200.42  5304.1  201.71
#Mann= 3 ,-1 , 0
  4664.6      .1       0  4988.6     .07       0  4994.6      .1       0
Bank Sta=4988.6,4994.6
XS Rating Curve= 0 ,0
Exp/Cntr=0.3,0.1

Type RM Length L Ch R = 1 ,12352   ,454,454,454
BEGIN DESCRIPTION:
UNT 068 IN LACR 18.0
END DESCRIPTION:
XS GIS Cut Line= 3
      2278187.72     13221446.85      2278587.72     13221296.85
       2278737.7     13221146.88
#Sta/Elev= 30
  4572.8  205.59  4582.6  204.93  4594.2  205.16  4618.2  203.96  4643.1  201.43
  4728.5  197.05  4743.7  196.94  4753.5  195.99  4758.8  196.18    4765  195.58
  4775.7  195.36  4783.7   194.5  4807.8  194.03    4814   193.5  4829.1  193.61
  4850.5  192.29  4899.4  191.57  4912.9  190.83  4984.9  188.39  4994.3  185.72
  4997.1  185.22  5000.3  185.72  5003.7  185.75  5005.4  185.98  5028.3   188.5
  5056.6  189.82    5099  193.34  5113.1  193.59  5139.4  195.69  5212.1  199.52
#Mann= 7 ,-1 , 0
  4572.8      .1       0  4912.9     .16       0  4994.3     .07       0
  5000.3     .16       0  5003.7      .1       0  5005.4     .16       0
  5139.4      .1       0
Bank Sta=4994.3,5000.3
XS Rating Curve= 0 ,0
Exp/Cntr=0.3,0.1

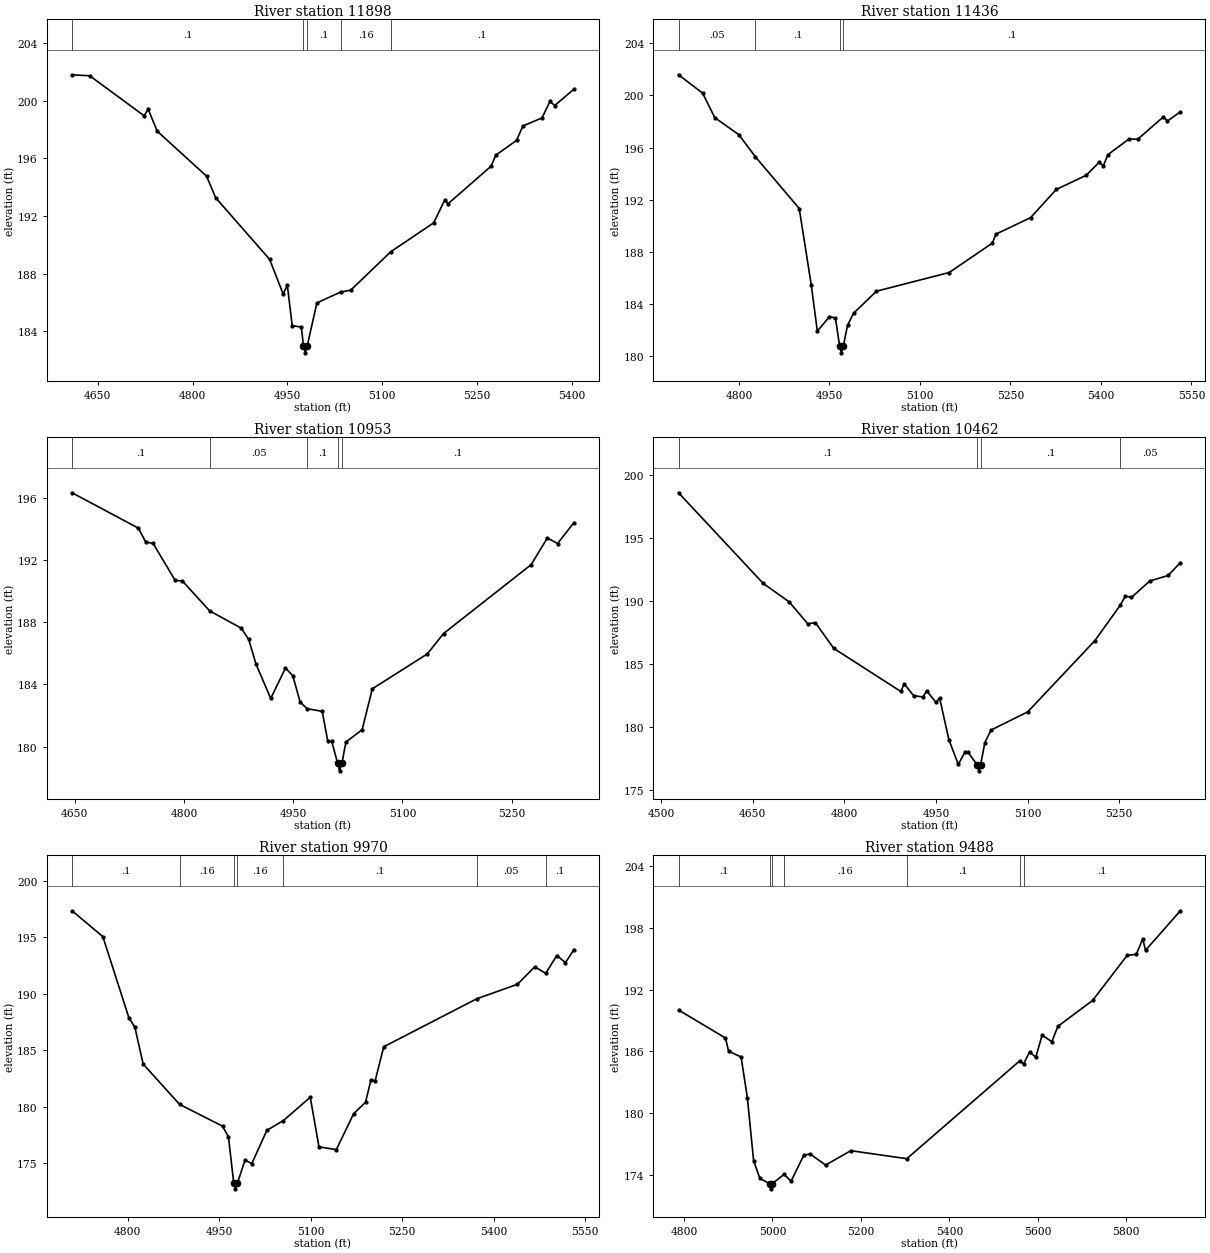
Type RM Length L Ch R = 1 ,11898   ,462,462,462
BEGIN DESCRIPTION:
UNT 068 IN LACR 17.0
END DESCRIPTION:
XS GIS Cut Line= 3
      2278637.73     13221796.85      2278937.72     13221546.85
      2278887.72     13221146.87
#Sta/Elev= 30
  4609.5  201.79  4637.5  201.72  4723.4  198.95  4729.9   199.4  4744.2  197.88
  4822.3  194.76  4836.6  193.27  4921.9     189  4943.4  186.59  4949.9  187.22
  4957.7   184.4    4972  184.31  4975.5  183.02  4978.3  182.52  4981.5  183.02
  4996.7  185.98  5034.1  186.73  5050.4  186.87  5113.4  189.52  5181.4  191.53
    5199  193.12  5204.1  192.85  5272.1  195.45  5279.7  196.22  5312.4  197.24
  5322.5  198.24  5352.7   198.8  5365.3  199.94  5372.9  199.66  5403.1  200.79
#Mann= 5 ,-1 , 0
  4609.5      .1       0  4975.5     .07       0  4981.5      .1       0
  5034.1     .16       0  5113.4      .1       0
Bank Sta=4975.5,4981.5
XS Rating Curve= 0 ,0
Exp/Cntr=0.3,0.1

Type RM Length L Ch R = 1 ,11436   ,483,483,483
BEGIN DESCRIPTION:
UNT 068 IN LACR 16.0
END DESCRIPTION:
XS GIS Cut Line= 3
      2279337.72     13221896.85      2279337.72     13221596.85
      2278987.73     13221196.86
#Sta/Elev= 30
    4700  201.57    4740  200.16    4760  198.29    4800  196.98    4827  195.31
    4900  191.33    4920  185.45    4930  181.94    4950  183.05    4960  182.95
    4967  180.78  4969.8  180.28    4973  180.78    4980  182.38    4990  183.31
    5028     185  5148.5  186.43  5219.7  188.67  5226.4  189.38  5283.3  190.63
    5326  192.79  5375.4  193.87  5397.2  194.88  5403.9  194.59  5411.4  195.45
  5446.6  196.66  5460.8  196.63  5503.5  198.35  5510.2  198.03  5531.5  198.73
#Mann= 4 ,-1 , 0
    4700     .05       0    4827      .1       0    4967     .07       0
    4973      .1       0
Bank Sta=4967,4973
XS Rating Curve= 0 ,0
Exp/Cntr=0.3,0.1

Type RM Length L Ch R = 1 ,10953   ,491,491,491
BEGIN DESCRIPTION:
UNT 068 IN LACR 15.0
END DESCRIPTION:
XS GIS Cut Line= 3
      2279787.73      13221746.9      2279737.72     13221396.85
      2279587.73     13221096.86
#Sta/Elev= 30
  4646.4  196.31  4737.4  194.04  4747.5  193.15  4757.6  193.06  4787.9  190.69
    4798  190.64  4835.2  188.73  4878.8  187.61  4888.9  186.89    4899   185.3
  4919.2   183.1  4939.4  185.05  4949.5  184.56  4959.6  182.86  4969.3  182.44
  4989.9  182.27  4997.5  180.36  5002.8  180.36    5011  178.95  5013.7  178.45
    5017  178.95  5022.4   180.3  5044.7  181.09  5058.7  183.72  5134.2  185.96
  5156.5  187.27  5276.7  191.69  5299.1  193.41    5313  193.05  5335.4  194.39
#Mann= 5 ,-1 , 0
  4646.4      .1       0  4835.2     .05       0  4969.3      .1       0
    5011     .07       0    5017      .1       0
Bank Sta=5011,5017
XS Rating Curve= 0 ,0
Exp/Cntr=0.3,0.1

Type RM Length L Ch R = 1 ,10462   ,492,492,492
BEGIN DESCRIPTION:
UNT 068 IN LACR 14.0
END DESCRIPTION:
XS GIS Cut Line= 3
      2280437.72     13221696.86      2280187.72     13221296.85
      2280187.72     13220946.85
#Sta/Elev= 30
  4528.3  198.59  4666.9  191.39  4709.3  189.93    4740  188.18  4752.4  188.27
  4782.4  186.23  4892.1  182.81    4898   183.4  4913.3  182.47  4928.7  182.37
  4934.6  182.86  4949.9  181.93  4955.8  182.28  4971.1  178.96  4986.4  177.01
  4997.1  177.97  5002.5  177.97    5017     177  5019.8   176.5    5023     177
    5030  178.75    5040  179.74    5100  181.18    5210  186.84  5251.4  189.64
    5260  190.39    5270  190.28    5300  191.58    5330  192.02    5350  193.04
#Mann= 4 ,-1 , 0
  4528.3      .1       0    5017     .07       0    5023      .1       0
  5251.4     .05       0
Bank Sta=5017,5023
XS Rating Curve= 0 ,0
Exp/Cntr=0.3,0.1

Type RM Length L Ch R = 1 ,9970    ,482,482,482
BEGIN DESCRIPTION:
UNT 068 IN LACR 13.0
END DESCRIPTION:
XS GIS Cut Line= 3
       2280787.7     13221446.81      2280637.72     13221196.86
      2280237.73     13220846.86
#Sta/Elev= 30
  4708.5  197.36    4759  195.07  4801.7  187.89  4811.5  187.05  4825.1  183.79
  4884.8  180.22  4955.3  178.29    4965  177.34  4973.7  173.24  4976.4  172.74
  4979.7  173.24  4992.2  175.29  5003.3  174.97    5028  177.92    5055  178.78
  5099.2  180.85  5113.4  176.46  5141.9  176.21  5170.4   179.4  5189.8   180.4
  5198.8  182.41  5205.5  182.29  5219.7  185.32  5372.3  189.57    5439  190.85
  5467.4   192.4  5485.4  191.82  5503.5   193.4  5517.7  192.77  5531.5  193.91
#Mann= 7 ,-1 , 0
  4708.5      .1       0  4884.8     .16       0  4973.7     .07       0
  4979.7     .16       0    5055      .1       0  5372.3     .05       0
  5485.4      .1       0
Bank Sta=4973.7,4979.7
XS Rating Curve= 0 ,0
Exp/Cntr=0.3,0.1

Type RM Length L Ch R = 1 ,9488    ,815,815,815
BEGIN DESCRIPTION:
UNT 068 IN LACR 12.0
END DESCRIPTION:
XS GIS Cut Line= 3
       2281187.7     13221146.83      2281037.72     13220996.85
      2280437.69     13220296.82
#Sta/Elev= 30
  4787.9  190.01  4893.9  187.29    4901  186.01  4929.3  185.44  4943.4  181.48
  4957.6  175.35  4971.7  173.64  4993.5  173.12  4996.2  172.62  4999.5  173.12
  5026.3  174.02  5042.3  173.37  5070.8  175.87  5085.1  176.02  5120.2  174.93
  5177.3  176.33  5303.8  175.55  5558.9  185.06  5567.8  184.77  5581.2  185.92
  5595.4  185.43  5609.7  187.57  5631.6  186.93  5645.4  188.43  5723.8  190.94
  5801.8  195.32  5822.6  195.43  5836.9  196.92  5843.5  195.82    5922  199.66
#Mann= 7 ,-1 , 0
  4787.9      .1       0  4993.5     .07       0  4999.5      .1       0
  5026.3     .16       0  5303.8      .1       0  5558.9     .05       0
  5567.8      .1       0
Bank Sta=4993.5,4999.5
XS Rating Curve= 0 ,0
Exp/Cntr=0.3,0.1

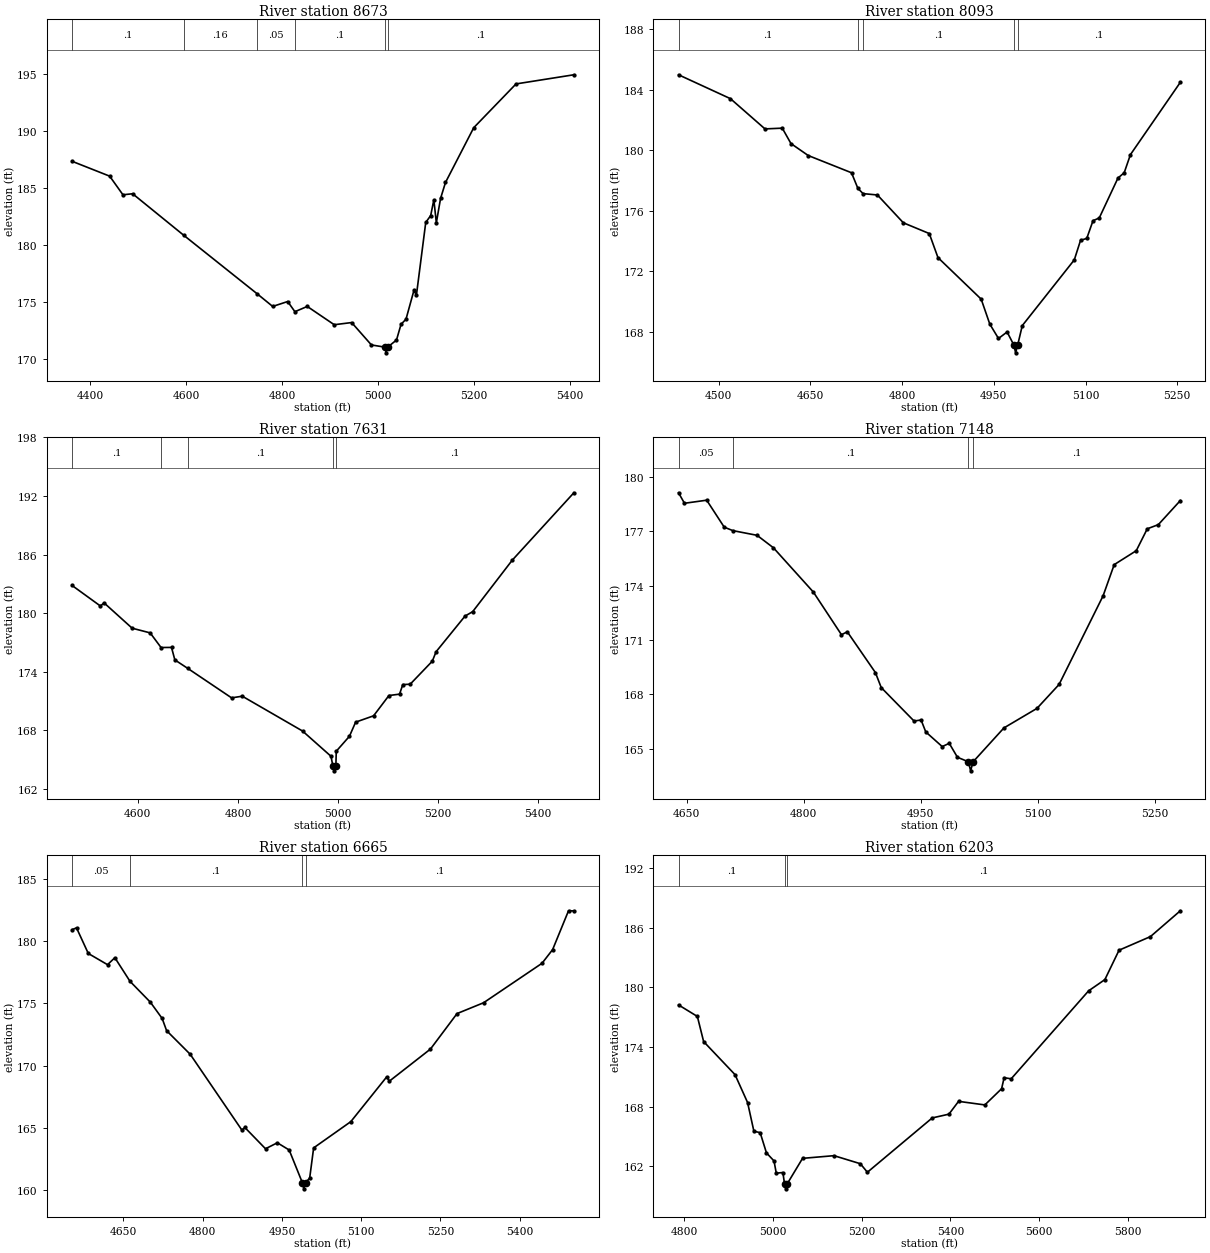
Type RM Length L Ch R = 1 ,8673    ,580,580,580
BEGIN DESCRIPTION:
UNT 068 IN LACR 11.0
END DESCRIPTION:
XS GIS Cut Line= 3
      2281253.67     13221061.87      2281185.34     13220593.28
        2281322.     13220036.86
#Sta/Elev= 30
  4362.1  187.33  4440.5  186.03  4468.2   184.4  4488.4  184.49  4595.2  180.85
  4747.7  175.75  4780.5  174.63  4811.8  175.06  4826.8  174.17  4852.6  174.63
  4908.9  173.03  4945.2  173.22  4986.4  171.26  5014.3  171.07  5017.1  170.57
  5020.3  171.07  5038.7  171.69  5048.2  173.07  5058.5  173.51  5075.1  176.04
  5080.2   175.6  5099.7  181.98    5110  182.58  5116.6  183.96  5121.8  181.95
  5130.6  184.08  5140.9  185.48  5199.8  190.27    5288   194.1  5408.6   194.9
#Mann= 6 ,-1 , 0
  4362.1      .1       0  4595.2     .16       0  4747.7     .05       0
  4826.8      .1       0  5014.3     .07       0  5020.3      .1       0
Bank Sta=5014.3,5020.3
XS Rating Curve= 0 ,0
Exp/Cntr=0.3,0.1

Type RM Length L Ch R = 1 ,8093    ,462,462,462
BEGIN DESCRIPTION:
UNT 068 IN LACR 10.0
END DESCRIPTION:
XS GIS Cut Line= 3
      2281337.71     13220996.87      2281737.72     13220596.85
      2281787.73     13220346.81
#Sta/Elev= 30
  4434.3     185  4519.2  183.42  4575.7  181.42    4604  181.47  4618.2  180.45
  4646.4  179.66  4717.2  178.52  4727.6  177.49  4736.1  177.14  4759.6  177.05
    4802  175.21  4844.4   174.5  4858.6  172.91  4929.3  170.16  4943.4  168.51
  4957.6  167.56  4971.7  167.99  4982.9  167.11  4985.6  166.61  4988.9  167.11
  4996.5  168.41  5081.6  172.76  5091.8  174.05    5102  174.18  5112.2  175.35
  5122.4  175.53    5153  178.17  5163.2  178.52  5173.4  179.72    5255   184.5
#Mann= 5 ,-1 , 0
  4434.3      .1       0  4727.6     .05       0  4736.1      .1       0
  4982.9     .07       0  4988.9      .1       0
Bank Sta=4982.9,4988.9
XS Rating Curve= 0 ,0
Exp/Cntr=0.3,0.1

Type RM Length L Ch R = 1 ,7631    ,483,483,483
BEGIN DESCRIPTION:
UNT 068 IN LACR 9.0
END DESCRIPTION:
XS GIS Cut Line= 3
      2281737.73     13221096.85      2282137.72     13220746.85
      2282387.72     13220346.85
#Sta/Elev= 30
  4468.5  182.83    4525  180.73  4532.6  181.04  4588.6  178.45  4624.6  177.97
  4646.4  176.47  4667.3  176.48    4674   175.2  4700.1  174.32  4787.4  171.31
  4808.8  171.48  4929.3  167.91  4986.2  165.32  4989.9  164.33  4992.6  163.83
  4995.9  164.33  4996.7  165.84    5023  167.37  5035.4  168.82  5071.3  169.47
    5102  171.55  5123.2  171.69  5129.7  172.67  5144.5  172.71  5188.7  175.07
  5196.3  176.04  5254.1  179.69  5269.5  180.15  5348.5  185.42  5471.7  192.33
#Mann= 5 ,-1 , 0
  4468.5      .1       0  4646.4     .05       0  4700.1      .1       0
  4989.9     .07       0  4995.9      .1       0
Bank Sta=4989.9,4995.9
XS Rating Curve= 0 ,0
Exp/Cntr=0.3,0.1

Type RM Length L Ch R = 1 ,7148    ,483,483,483
BEGIN DESCRIPTION:
UNT 068 IN LACR 8.0
END DESCRIPTION:
XS GIS Cut Line= 3
      2282237.68     13221146.88      2282537.72     13220946.85
      2282737.69     13220746.89
#Sta/Elev= 30
  4639.4  179.13    4647  178.55  4675.5  178.72    4698  177.23    4709  177.04
  4740.1  176.78  4761.1  176.09  4812.2  173.65  4848.3  171.29  4855.8  171.45
  4891.8   169.2  4899.3  168.37  4941.4  166.52  4950.4  166.58  4956.4  165.92
  4977.5  165.11  4986.5  165.29    4997  164.52  5011.1  164.27  5013.9  163.77
  5017.1  164.27  5056.6  166.14    5099  167.22  5127.3  168.54  5183.8  173.44
    5198  175.16  5226.3  175.93  5240.4  177.14  5254.6  177.37  5282.8   178.7
#Mann= 4 ,-1 , 0
  4639.4     .05       0    4709      .1       0  5011.1     .07       0
  5017.1      .1       0
Bank Sta=5011.1,5017.1
XS Rating Curve= 0 ,0
Exp/Cntr=0.3,0.1

Type RM Length L Ch R = 1 ,6665    ,462,462,462
BEGIN DESCRIPTION:
UNT 068 IN LACR 7.0
END DESCRIPTION:
XS GIS Cut Line= 3
      2282737.73     13221546.84      2282937.72     13221146.85
      2282887.72     13220646.85
#Sta/Elev= 30
  4552.8  180.92  4561.2  181.07  4583.5  179.01  4619.9  178.11  4633.8  178.67
  4662.5  176.77  4700.9   175.1  4723.3  173.79  4731.7  172.81  4776.4  170.91
  4874.2  164.82  4879.8  165.03  4918.9  163.32  4941.3   163.8  4963.7  163.22
  4988.6   160.6  4991.4   160.1  4994.6   160.6  5002.5  160.96    5010  163.39
  5080.4   165.5  5148.2  169.09  5153.3  168.75  5231.1  171.33  5281.4  174.18
  5331.6  175.05  5442.2  178.22  5462.3  179.32  5492.4  182.44  5502.5  182.43
#Mann= 4 ,-1 , 0
  4552.8     .05       0  4662.5      .1       0  4988.6     .07       0
  4994.6      .1       0
Bank Sta=4988.6,4994.6
XS Rating Curve= 0 ,0
Exp/Cntr=0.3,0.1

Type RM Length L Ch R = 1 ,6203    ,434,434,434
BEGIN DESCRIPTION:
UNT 068 IN LACR 6.0
END DESCRIPTION:
XS GIS Cut Line= 3
       2283487.7     13221446.83      2283337.72     13221296.85
      2282887.71     13220496.84
#Sta/Elev= 30
  4787.9  178.24  4830.3  177.08  4844.4  174.55  4915.1  171.22  4943.4  168.41
  4957.6  165.52  4971.7  165.38  4985.9  163.34  5002.9  162.53    5008   161.3
  5022.9  161.36  5026.6  160.22  5029.4  159.72  5032.6  160.22  5067.2  162.79
    5138  163.06  5197.3  162.25  5213.2  161.39  5359.2  166.86  5396.8  167.24
  5418.5  168.53  5477.7  168.17  5515.4   169.8  5521.1  170.91    5537   170.8
  5711.4  179.66    5748  180.79  5779.9  183.75  5850.6  185.12  5917.9  187.72
#Mann= 3 ,-1 , 0
  4787.9      .1       0  5026.6     .07       0  5032.6      .1       0
Bank Sta=5026.6,5032.6
XS Rating Curve= 0 ,0
Exp/Cntr=0.3,0.1

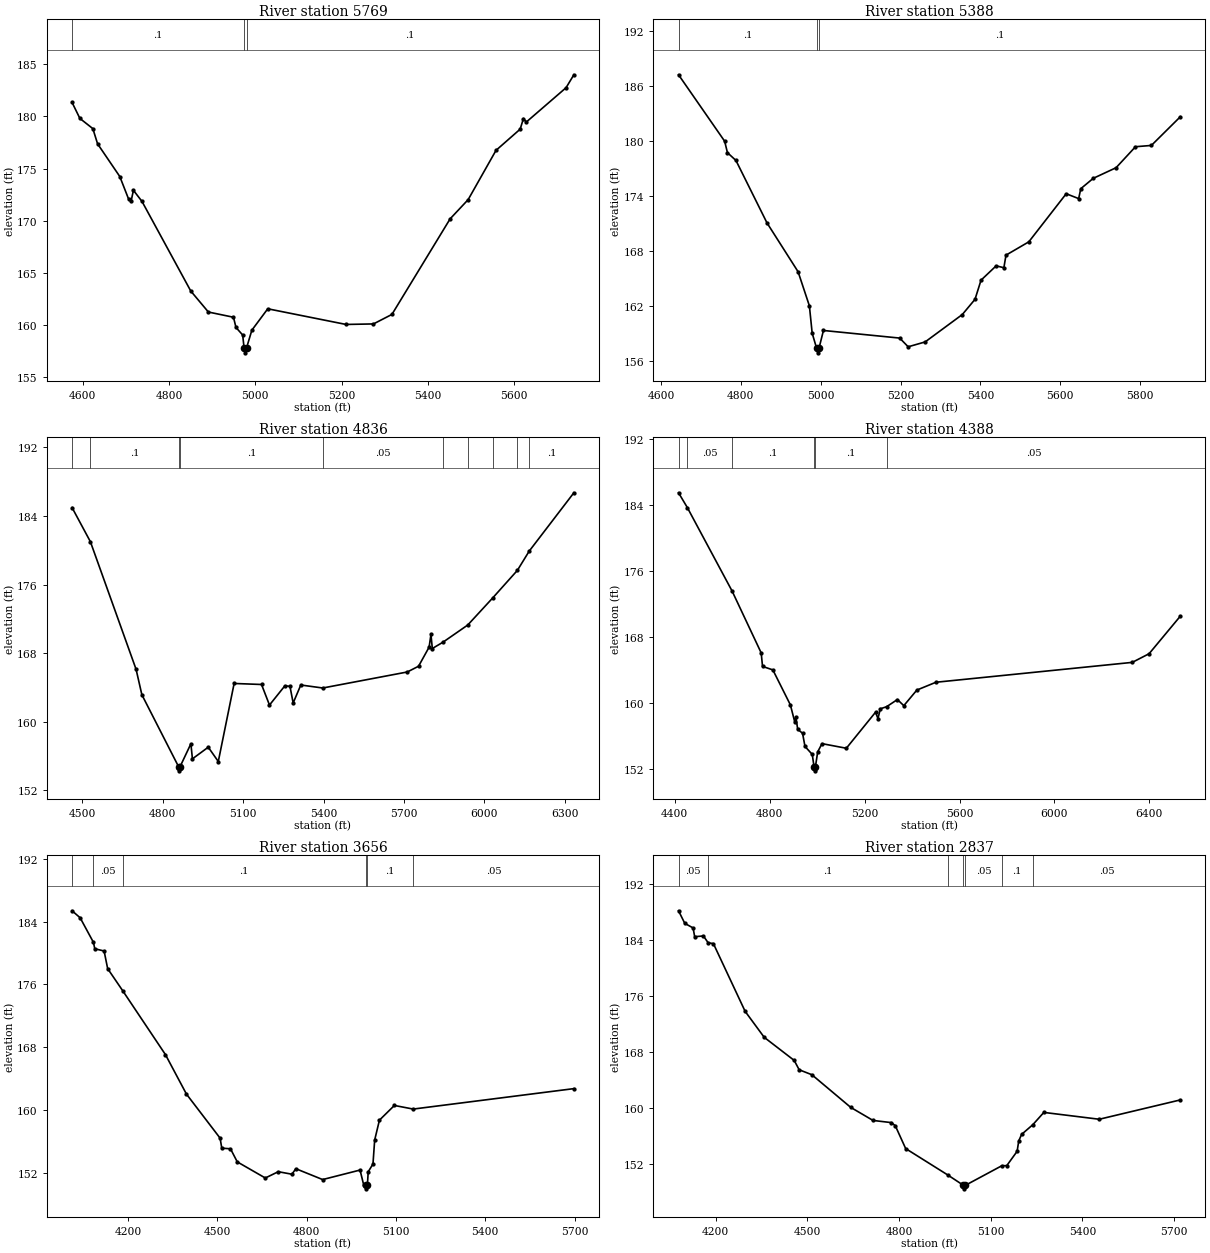
Type RM Length L Ch R = 1 ,5769    ,381,381,381
BEGIN DESCRIPTION:
UNT 068 IN LACR 5.0
END DESCRIPTION:
XS GIS Cut Line= 4
      2283655.09     13221364.43      2283586.76     13221081.37
      2283420.81     13220808.04      2283001.89     13220447.58
#Sta/Elev= 30
  4575.2  181.34  4593.3  179.81  4623.4  178.83  4634.4  177.37  4685.9  174.24
  4706.4  172.07  4712.4  171.94  4717.5  172.92  4737.3  171.86  4850.5  163.27
  4891.3  161.26  4949.5  160.76  4955.3  159.78  4970.8  159.06    4974  157.85
  4976.7  157.35    4980  157.85  4992.1  159.52    5029  161.57  5210.5  160.07
  5274.1  160.12  5316.9  161.03  5451.9  170.19  5493.7  172.03  5558.3  176.75
  5614.3  178.78  5621.9   179.8  5628.5  179.46  5720.7  182.75  5738.8  183.99
#Mann= 3 ,-1 , 0
  4575.2      .1       0    4974     .07       0    4980      .1       0
Bank Sta=4974,4980
XS Rating Curve= 0 ,0
Exp/Cntr=0.3,0.1

Type RM Length L Ch R = 1 ,5388    ,552,552,552
BEGIN DESCRIPTION:
UNT 068 IN LACR 4.0
END DESCRIPTION:
XS GIS Cut Line= 3
      2284065.08     13221022.78      2283625.81     13220573.75
       2283031.5     13220369.16
#Sta/Elev= 30
  4644.1  187.22  4759.6  179.97  4766.6  178.72  4787.9  177.87  4865.6  171.06
  4943.5  165.73  4971.8  162.01  4978.8  159.02  4989.9  157.38  4992.7  156.88
  4995.9  157.38    5007  159.32    5198  158.49  5219.2  157.54  5261.7  158.07
  5354.8  161.06  5386.6  162.72  5401.7  164.81  5439.5  166.37  5458.9  166.17
  5464.2  167.54  5521.3  168.99    5615  174.24  5646.2  173.71  5651.5  174.79
  5682.7  175.92  5739.9  177.08  5788.5  179.37  5828.3  179.51  5900.8  182.64
#Mann= 3 ,-1 , 0
  4644.1      .1       0  4989.9     .07       0  4995.9      .1       0
Bank Sta=4989.9,4995.9
XS Rating Curve= 0 ,0
Exp/Cntr=0.3,0.1

Type RM Length L Ch R = 1 ,4836    ,448,448,448
BEGIN DESCRIPTION:
UNT 068 IN LACR 3.0
END DESCRIPTION:
XS GIS Cut Line= 3
      2284182.23     13220837.31        2283782.     13220134.47
      2282737.44     13219929.46
#Sta/Elev= 30
  4461.1  184.98  4529.5     181  4700.1   166.1  4721.7  163.13  4858.5  154.75
  4861.2  154.25  4864.5  154.75  4904.7  157.41  4910.4  155.65  4969.5  157.01
    5007  155.34  5066.1  164.45  5168.4  164.33  5198.1  161.93  5255.7  164.18
  5274.6  164.11  5286.5  162.17    5315  164.27    5397  163.92  5712.5  165.79
  5754.6  166.46    5794  168.69  5800.9  170.17    5806  168.53  5845.4  169.26
  5938.2  171.27    6031  174.42  6123.5  177.65  6167.7   179.9  6334.4  186.71
#Mann= 10 ,-1 , 0
  4461.1     .05       0  4529.5      .1       0  4858.5     .07       0
  4864.5      .1       0    5397     .05       0  5845.4      .1       0
  5938.2     .05       0    6031      .1       0  6123.5     .05       0
  6167.7      .1       0
Bank Sta=4858.5,4864.5
XS Rating Curve= 0 ,0
Exp/Cntr=0.3,0.1

Type RM Length L Ch R = 1 ,4388    ,732,732,732
BEGIN DESCRIPTION:
UNT 068 IN LACR 2.0
END DESCRIPTION:
XS GIS Cut Line= 4
      2284289.61     13220915.45      2284367.72     13220593.28
      2284162.72     13219675.66      2283596.99     13219051.41
#Sta/Elev= 30
    4416  185.51    4453  183.72  4641.6  173.59  4764.3  166.08  4769.9  164.44
  4813.4  164.02  4887.3  159.77  4905.3  157.74  4910.5  158.31    4918  156.81
  4938.5  156.33  4948.8  154.73  4979.5  153.76  4986.8  152.27  4989.5  151.77
  4992.8  152.27  5002.4  154.08  5020.5  155.07    5123  154.51  5245.9  158.88
  5256.2  158.12  5266.4   159.3  5292.6  159.55  5338.1  160.42  5365.2  159.68
  5420.1  161.57  5500.6  162.52  6327.6  164.93  6398.6  165.98  6530.2  170.54
#Mann= 6 ,-1 , 0
    4416      .1       0    4453     .05       0  4641.6      .1       0
  4986.8     .07       0  4992.8      .1       0  5292.6     .05       0
Bank Sta=4986.8,4992.8
XS Rating Curve= 0 ,0
Exp/Cntr=0.3,0.1

Type RM Length L Ch R = 1 ,3656    ,819,819,819
BEGIN DESCRIPTION:
Mapping XS 39d88e02
END DESCRIPTION:
XS GIS Cut Line= 3
      2284406.76     13221110.67      2285031.53      13219997.8
      2284806.99     13219656.12
#Sta/Elev= 30
  4012.3  185.37  4039.4  184.48  4084.1  181.35  4088.5  180.54  4119.9  180.25
  4131.8  178.01  4183.2  175.15  4325.7  167.08  4396.5  162.04  4509.4  156.44
  4515.1  155.16  4544.2  155.09  4567.1  153.42  4661.2  151.37  4704.8  152.17
  4750.6  151.85  4763.8  152.55  4853.8  151.17  4979.4  152.38  4991.5   150.5
  4998.1  150.49  5000.8  149.99  5004.1  150.49  5006.8  152.16  5022.8  153.15
  5028.5   156.2  5044.5  158.73  5094.7   160.6  5157.9  160.14  5697.4  162.74
#Mann= 6 ,-1 , 0
  4012.3      .1       0  4084.1     .05       0  4183.2      .1       0
  4998.1     .07       0  5004.1      .1       0  5157.9     .05       0
Bank Sta=4998.1,5004.1
XS Rating Curve= 0 ,0
Exp/Cntr=0.3,0.1

Type RM Length L Ch R = 1 ,2837    ,1061,1061,1061
BEGIN DESCRIPTION:
Mapping XS 985831e2
END DESCRIPTION:
XS GIS Cut Line= 3
      2284869.39     13221716.46      2285205.76     13220533.75
      2285205.76     13220121.67
#Sta/Elev= 30
  4078.9  188.21  4099.3  186.41  4126.5  185.75  4131.7   184.5  4160.3   184.6
  4175.9  183.62  4192.9  183.51  4296.8   173.8  4359.2  170.08  4457.3  166.77
  4473.6  165.43  4515.1  164.72  4642.3  160.04  4715.2  158.17  4775.1  157.86
  4788.1  157.41    4822  154.14  4958.9  150.38  5011.2  148.87  5013.9  148.37
  5017.2  148.87  5136.2  151.67  5152.9   151.7  5186.7  153.75  5191.9  155.23
  5201.3  156.17    5238  157.56  5274.1  159.32  5455.4  158.34  5720.6  161.11
#Mann= 7 ,-1 , 0
  4078.9     .05       0  4175.9      .1       0  4958.9     .05       0
  5011.2     .03       0  5017.2     .05       0  5136.2      .1       0
    5238     .05       0
Bank Sta=5011.2,5017.2
XS Rating Curve= 0 ,0
Exp/Cntr=0.3,0.1

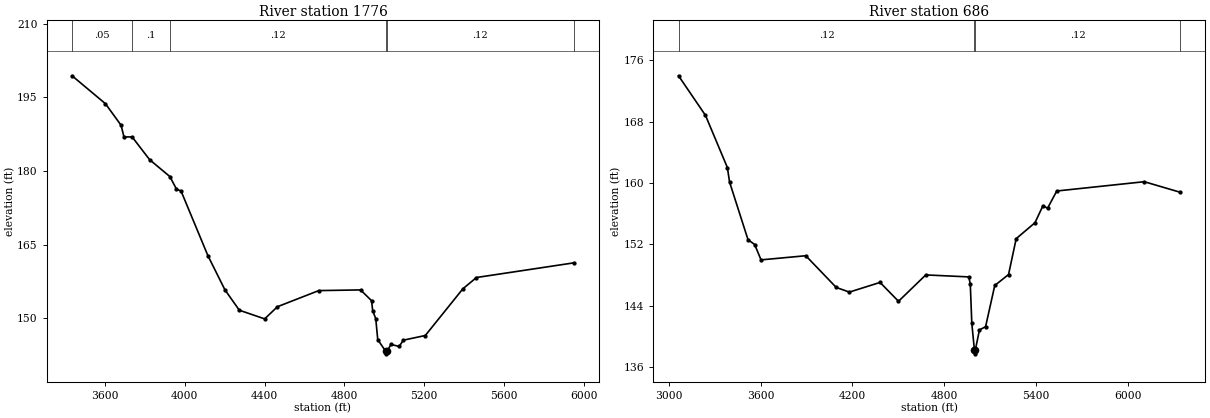
Type RM Length L Ch R = 1 ,1776    ,1090,1090,1090
BEGIN DESCRIPTION:
Mapping XS 27a99a39
END DESCRIPTION:
XS GIS Cut Line= 4
      2285254.29     13222258.96      2286104.97     13221165.23
      2285887.96     13220574.95      2285487.91     13220273.37
#Sta/Elev= 30
    3435  199.42  3602.4  193.72  3680.7  189.33  3695.2  186.94  3736.1  186.95
  3823.7  182.31  3925.3  178.86  3958.5  176.29  3981.2  175.92    4116  162.72
  4201.1  155.77  4273.4   151.6  4400.5  149.83  4464.4  152.31  4671.6   155.6
  4881.3  155.74  4936.1  153.55  4942.2  151.48  4957.4  149.88  4967.4  145.59
  5007.7   143.2  5010.4   142.7  5013.7   143.2  5033.6  144.63  5074.6   144.2
  5095.9  145.49  5205.8  146.44  5394.2  155.97  5462.3  158.27  5950.5  161.26
#Mann= 6 ,-1 , 0
    3435     .05       0  3736.1      .1       0  3925.3     .12       0
  5007.7     .05       0  5013.7     .12       0  5950.5     .05       0
Bank Sta=5007.7,5013.7
XS Rating Curve= 0 ,0
Exp/Cntr=0.3,0.1

Type RM Length L Ch R = 1 ,686     ,0,0,0
BEGIN DESCRIPTION:
UNT 068 IN LACR 1.0
END DESCRIPTION:
XS GIS Cut Line= 4
      2285884.86     13222380.93       2286919.6     13221040.62
      2286933.49     13220478.12      2285912.72     13220394.79
#Sta/Elev= 30
  3062.9  173.97    3239  168.81  3382.1  162.01  3396.5  160.11  3517.1   152.6
  3560.6  151.97  3602.2  149.97  3894.7  150.51    4094  146.37  4179.8  145.77
  4380.2  147.03  4500.7  144.57  4679.1  148.01    4960  147.75    4970  146.84
    4980  141.68    4997  138.22  4999.8  137.72    5003  138.22    5030  140.84
    5070  141.26    5130  146.63  5220.1  148.06  5270.1  152.74  5392.8  154.81
    5445  157.03  5475.1   156.7  5535.3  158.95  6107.2  160.16    6343  158.78
#Mann= 4 ,-1 , 0
  3062.9     .12       0    4997     .07       0    5003     .12       0
    6343     .05       0
Bank Sta=4997,5003
XS Rating Curve= 0 ,0
Exp/Cntr=0.3,0.1

Chan Stop Cuts=-1
Use User Specified Reach Order=0
Composite Channel Slope=5