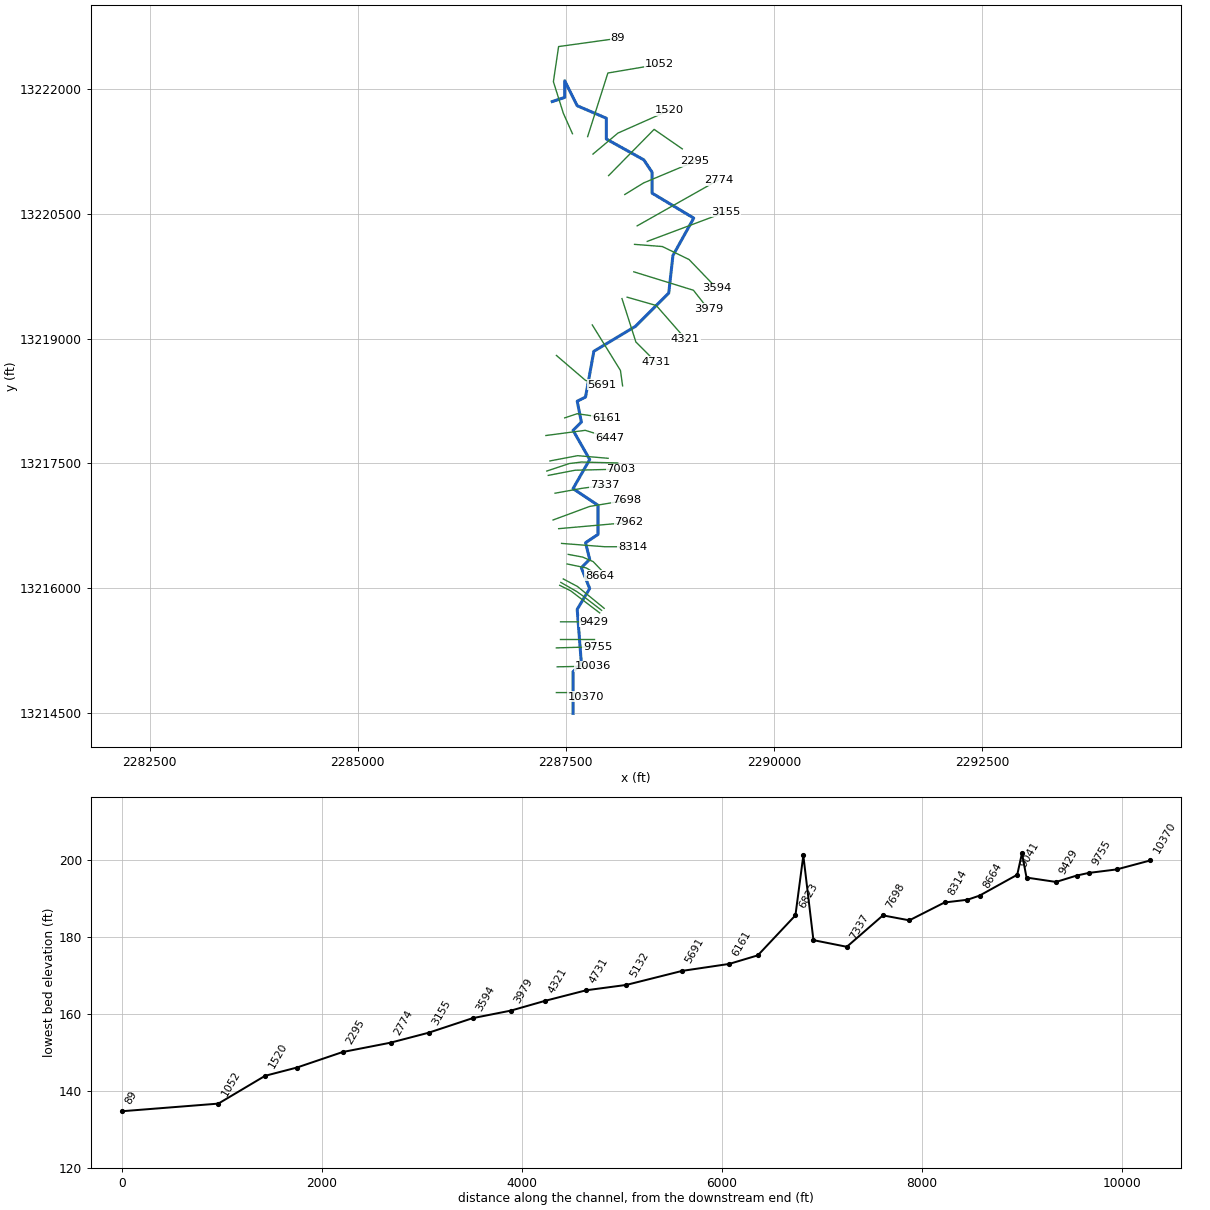
--- UNT 069 IN LACR.prj (project) ---

Proj Title=UNT 069 IN LACR Base Level Engineering
Current Plan=p01
Default Exp/Contr=0.3,0.1
English Units
Geom File=g01
Flow File=f01
Plan File=p01
Y Axis Title=Elevation
X Axis Title(PF)=Main Channel Distance
X Axis Title(XS)=Station
BEGIN DESCRIPTION:
UNT 069 IN LACR
END DESCRIPTION:
DSS Export Rating Curves= 0
DSS Export Rating Curve Sorted= 0
DSS Export Volume Flow Curves= 0
DXF OffsetX= 0
DXF OffsetY= 0
DXF ScaleX= 1
DXF ScaleY= 10

--- UNT 069 IN LACR.p01 (plan) ---

Plan Title=Multiple Run
Short Identifier=Multiple
Geom File=g01
Flow File=f01
Subcritical Flow
K Sum by GR= 0
Std Step Tol= 0.01
Critical Tol= 0.01
Num of Std Step Trials= 20
Max Error Tol= 0.3
Flow Tol Ratio= 0.001
Split Flow NTrial= 30
Split Flow Tol= 0.02
Split Flow Ratio= 0.02
Log Output Level= 0
Friction Slope Method= 1
Unsteady Friction Slope Method= 2
Unsteady Bridges Friction Slope Method= 1
Parabolic Critical Depth
Global Vel Dist=  1 , 1 , 1
Global Log Level= 0
CheckData=True
Encroach Param= -1, 0, 0, 0
BEGIN DESCRIPTION:
Multiple Run
END DESCRIPTION:

--- UNT 069 IN LACR.f01 (steady flow) ---

Flow Title=Multiple
Number of Profiles=7
Profile Names=10-year,25-year,50-year,1pct_min,100-year,1pct_plu,500-year
River Rch & RM= UNT 069 IN LACR,Reach-1,10370
     253     347     425     382     517     699     776
Boundary for River Rch & Prof#=UNT 069 IN LACR,Reach-1,1
Up Type=0
Dn Type=3
Dn Slope=0.005
Boundary for River Rch & Prof#=UNT 069 IN LACR,Reach-1,2
Up Type=0
Dn Type=3
Dn Slope=0.005
Boundary for River Rch & Prof#=UNT 069 IN LACR,Reach-1,3
Up Type=0
Dn Type=3
Dn Slope=0.005
Boundary for River Rch & Prof#=UNT 069 IN LACR,Reach-1,4
Up Type=0
Dn Type=3
Dn Slope=0.005
Boundary for River Rch & Prof#=UNT 069 IN LACR,Reach-1,5
Up Type=0
Dn Type=3
Dn Slope=0.005
Boundary for River Rch & Prof#=UNT 069 IN LACR,Reach-1,6
Up Type=0
Dn Type=3
Dn Slope=0.005
Boundary for River Rch & Prof#=UNT 069 IN LACR,Reach-1,7
Up Type=0
Dn Type=3
Dn Slope=0.005

--- UNT 069 IN LACR.g01 (geometry) ---

Geom Title=Existing Conditions
Program Version=4.10

River Reach=UNT 069 IN LACR ,Reach-1
Reach XY= 30
      2287587.72     13214496.85      2287587.72     13214996.85
      2287687.72     13215096.85      2287637.72     13215746.85
      2287787.72     13215996.85      2287687.72     13216246.86
      2287787.72     13216346.85      2287737.72     13216546.85
      2287887.72     13216646.85      2287887.72     13216996.85
      2287587.72     13217196.85      2287787.72     13217546.85
      2287587.72     13217896.86      2287687.72     13217996.85
      2287637.72     13218246.86      2287737.72     13218296.85
      2287837.72     13218846.85      2288337.72     13219146.85
      2288737.72     13219546.86      2288787.72     13219996.85
      2289037.72     13220446.85      2288537.72     13220746.85
      2288537.72     13220996.85      2288437.72     13221146.85
      2287987.72     13221396.85      2287987.72     13221646.85
      2287637.72     13221796.85      2287487.72     13222096.85
      2287487.72     13221896.85      2287337.72     13221846.86

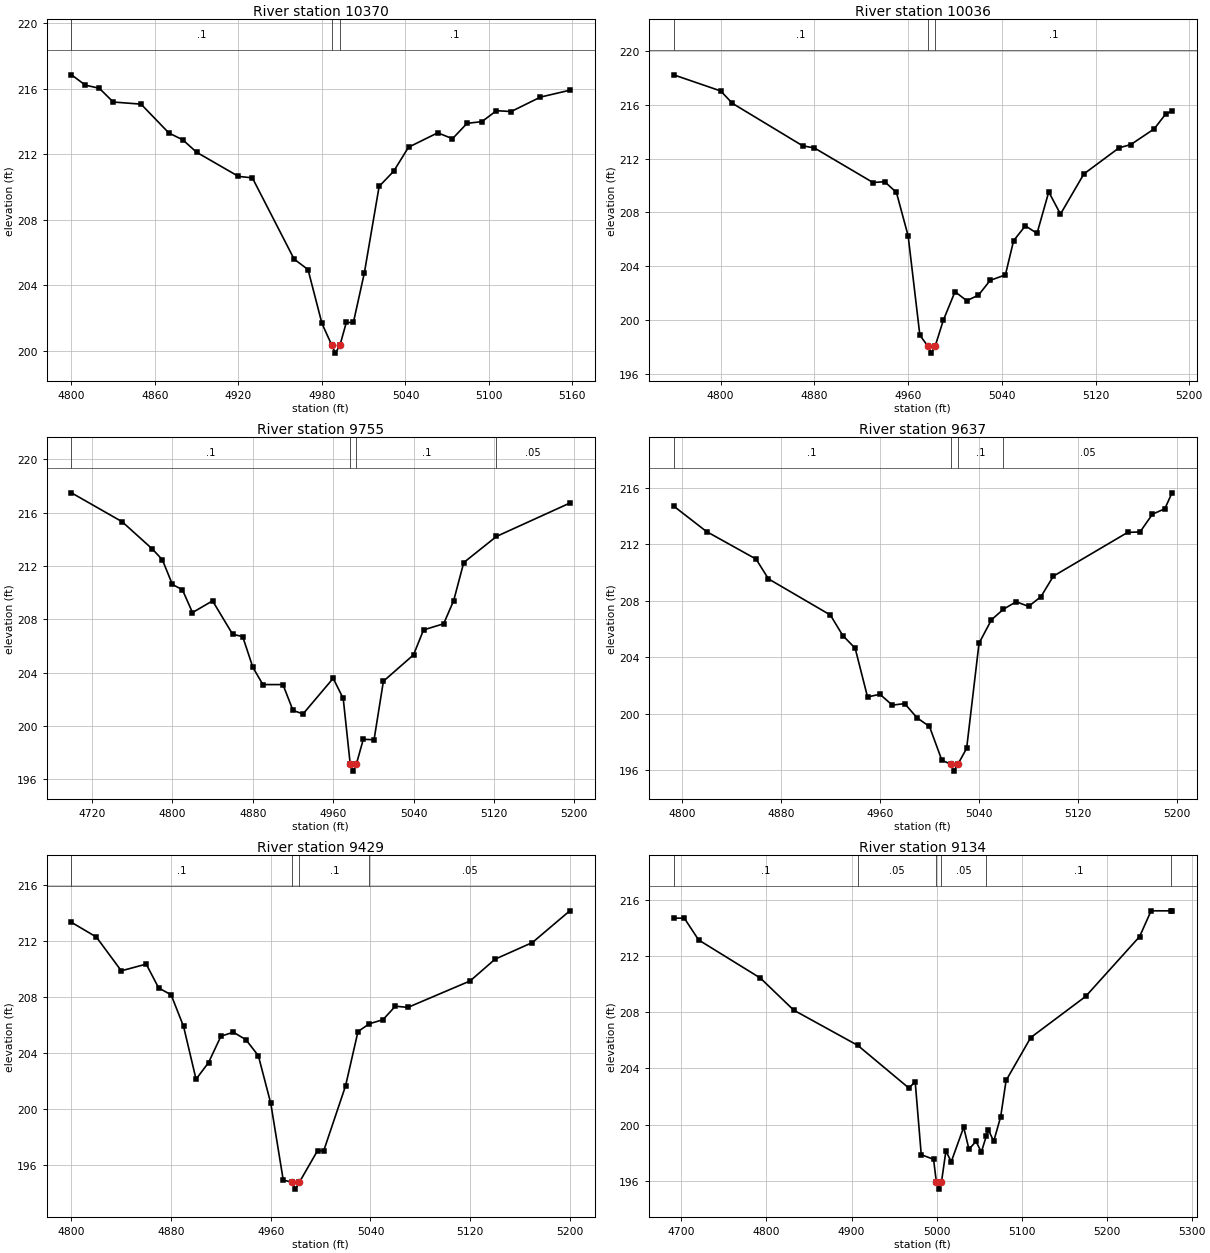
Type RM Length L Ch R = 1 ,10370   ,334,334,334
BEGIN DESCRIPTION:
UNT 069 IN LACR 19.0
END DESCRIPTION:
XS GIS Cut Line= 3
      2287387.72     13214746.85      2287587.72     13214746.85
      2287737.71     13214696.86
#Sta/Elev= 30
    4800  216.85    4810  216.22    4820  216.03    4830  215.19    4850  215.06
    4870   213.3    4880  212.88    4890  212.12    4920  210.65    4930  210.56
    4960   205.6    4970  204.96    4980  201.67    4987  200.36  4989.7  199.86
    4993  200.36  4997.5  201.73  5002.6  201.73  5010.5  204.77  5021.1  210.04
  5031.6  210.97  5042.2  212.43  5063.2  213.31  5073.8  212.95  5084.3  213.89
  5094.9  213.99  5105.4  214.66    5116  214.61    5137  215.49  5158.1  215.91
#Mann= 3 ,-1 , 0
    4800      .1       0    4987     .07       0    4993      .1       0
Bank Sta=4987,4993
XS Rating Curve= 0 ,0
Exp/Cntr=0.3,0.1

Type RM Length L Ch R = 1 ,10036   ,281,281,281
BEGIN DESCRIPTION:
Mapping XS a4e41569
END DESCRIPTION:
XS GIS Cut Line= 2
      2287397.67     13215056.12      2287822.88      13215064.8
#Sta/Elev= 30
  4759.9  218.24    4800  217.04    4810  216.12    4870  212.96    4880   212.8
    4930  210.23    4940  210.29    4950  209.49    4960  206.26    4970  198.87
    4977  198.04  4979.7  197.54    4983  198.04    4990  199.98    5000  202.11
    5010  201.44    5020  201.85    5030  202.95    5043  203.36    5050   205.9
    5060  207.01    5070  206.45    5080  209.53    5090  207.88    5110  210.87
    5140  212.81    5150  213.05    5170  214.22    5180  215.35  5185.2  215.53
#Mann= 3 ,-1 , 0
  4759.9      .1       0    4977     .07       0    4983      .1       0
Bank Sta=4977,4983
XS Rating Curve= 0 ,0
Exp/Cntr=0.3,0.1

Type RM Length L Ch R = 1 ,9755    ,118,118,118
BEGIN DESCRIPTION:
UNT 069 IN LACR 18.0
END DESCRIPTION:
XS GIS Cut Line= 2
      2287387.24     13215283.55      2287883.24     13215297.43
#Sta/Elev= 30
  4699.4  217.49  4749.9  215.32  4779.9  213.28  4789.9  212.47  4799.9  210.62
  4809.9  210.22  4819.9  208.51  4839.9  209.39  4859.9  206.88  4869.9  206.71
    4880  204.41    4890  203.11    4910  203.11    4920  201.17    4930  200.91
    4960  203.58    4970  202.07    4977  197.12  4979.7  196.62    4983  197.12
    4990  199.01  5000.7  198.97    5010  203.36    5040  205.34    5050  207.21
    5070  207.67    5080  209.41    5090  212.26  5122.6  214.22  5195.6  216.72
#Mann= 4 ,-1 , 0
  4699.4      .1       0    4977     .07       0    4983      .1       0
  5122.6     .05       0
Bank Sta=4977,4983
XS Rating Curve= 0 ,0
Exp/Cntr=0.3,0.1

Type RM Length L Ch R = 1 ,9637    ,208,208,208
BEGIN DESCRIPTION:
Mapping XS 3df6eda0
END DESCRIPTION:
XS GIS Cut Line= 2
      2287431.22     13215388.69      2287833.52     13215388.69
#Sta/Elev= 30
  4793.5  214.71    4820  212.91    4860  210.96    4870  209.56    4920     207
    4930  205.55    4940  204.65    4950   201.2    4960  201.39    4970  200.62
    4980  200.73    4990  199.72    5000  199.11    5010  196.72    5017  196.45
  5019.7  195.95    5023  196.45    5030  197.56    5040     205    5050  206.66
  5059.7  207.41    5070  207.94    5080  207.61    5090   208.3    5100  209.75
    5160  212.85    5170  212.88    5180  214.14    5190  214.52  5195.8  215.65
#Mann= 4 ,-1 , 0
  4793.5      .1       0    5017     .07       0    5023      .1       0
  5059.7     .05       0
Bank Sta=5017,5023
XS Rating Curve= 0 ,0
Exp/Cntr=0.3,0.1

Type RM Length L Ch R = 1 ,9429    ,295,295,295
BEGIN DESCRIPTION:
UNT 069 IN LACR 17.0
END DESCRIPTION:
XS GIS Cut Line= 3
      2287437.72     13215596.85      2287637.72     13215596.86
      2287837.72     13215596.85
#Sta/Elev= 30
    4800  213.31    4820  212.26    4840  209.85    4860  210.33    4870  208.63
    4880  208.14    4890  205.88    4900  202.12    4910   203.3    4920  205.19
    4930  205.47    4940  204.94    4950   203.8    4960  200.39    4970  194.92
    4977  194.78  4979.7  194.28    4983  194.78  4997.5  197.02  5002.5  197.02
    5020  201.64    5030  205.52  5039.2  206.08    5050  206.36    5060  207.33
    5070  207.24    5120  209.13    5140  210.68    5170  211.87    5200  214.13
#Mann= 4 ,-1 , 0
    4800      .1       0    4977     .07       0    4983      .1       0
  5039.2     .05       0
Bank Sta=4977,4983
XS Rating Curve= 0 ,0
Exp/Cntr=0.3,0.1

Type RM Length L Ch R = 1 ,9134    ,46,46,46
BEGIN DESCRIPTION:
Mapping XS d5825f1a
END DESCRIPTION:
XS GIS Cut Line= 3
      2287427.21     13216035.27      2287559.12     13215969.32
      2287908.05     13215703.71
#Sta/Elev= 30
  4690.9  214.69  4703.4  214.69  4720.2  213.14  4792.8  210.43    4832  208.15
  4907.4  205.64  4967.4  202.61  4974.9  203.05    4982  197.87  4996.5  197.54
  4999.8  195.92  5002.5  195.42  5005.8  195.92    5011  198.13  5017.3  197.37
  5031.9  199.82  5038.1  198.26  5046.4  198.81  5052.7  198.06  5058.4  199.17
  5060.9  199.65  5067.2  198.82  5075.4  200.56  5081.8  203.15  5110.8   206.2
  5175.3  209.12  5238.8  213.38  5252.3  215.21  5275.9  215.21  5276.9  215.21
#Mann= 6 ,-1 , 0
  4690.9      .1       0  4907.4     .05       0  4999.8     .04       0
  5005.8     .05       0  5058.4      .1       0  5275.9     .05       0
Bank Sta=4999.8,5005.8
XS Rating Curve= 0 ,0
Exp/Cntr=0.3,0.1

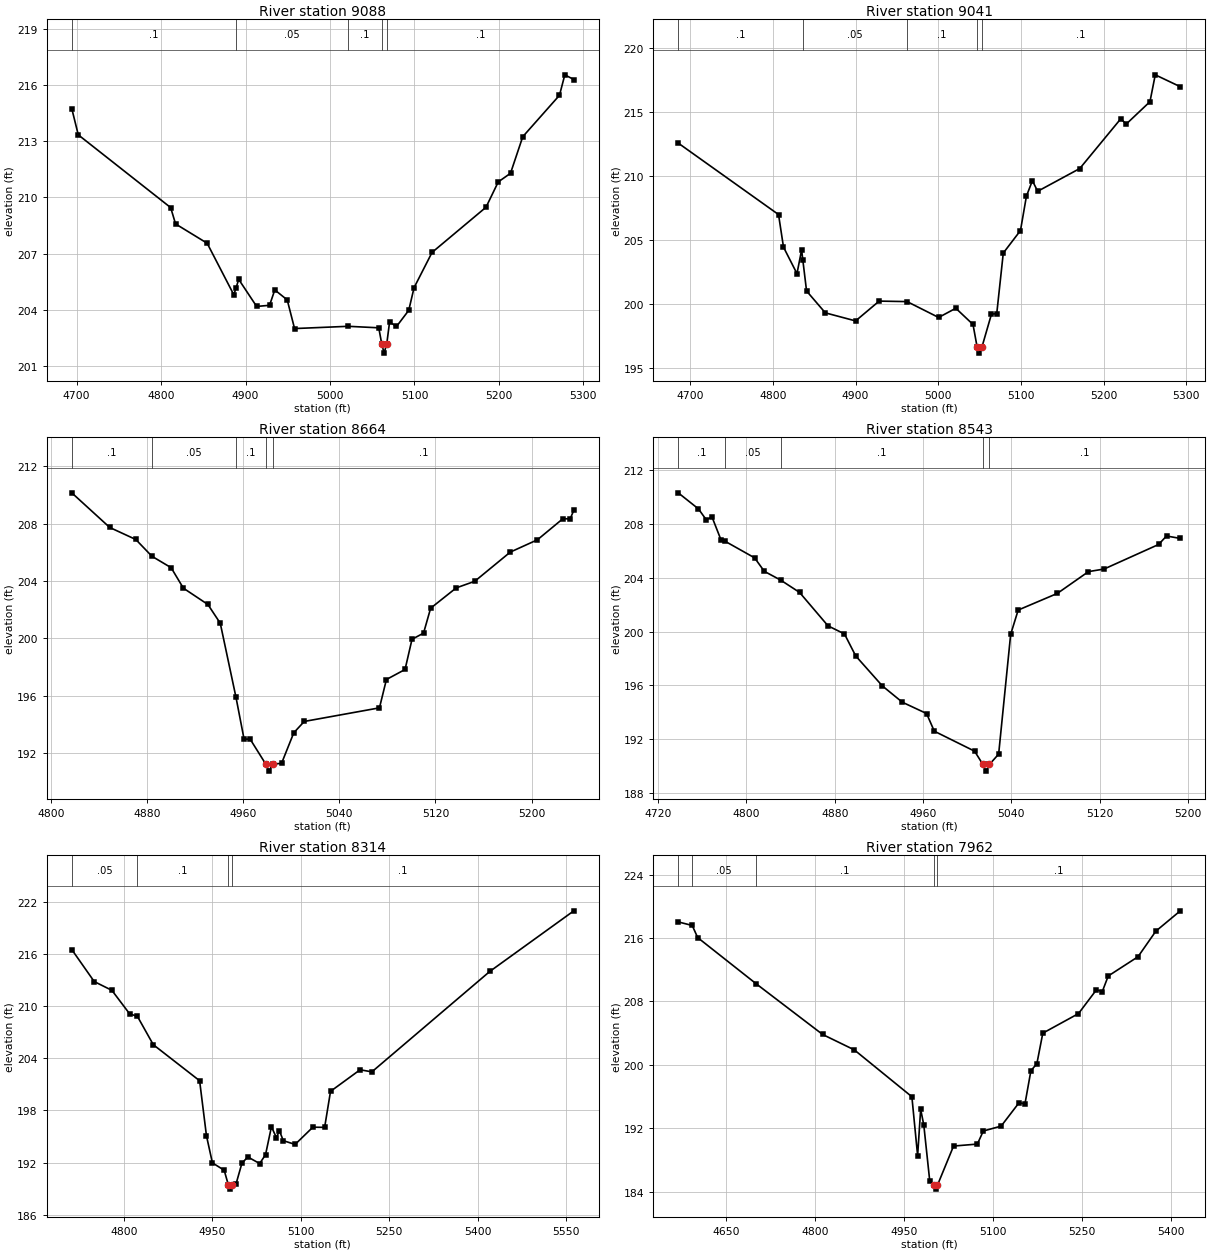
Type RM Length L Ch R = 1 ,9088    ,47,47,47
BEGIN DESCRIPTION:
Mapping XS c0f5705f
END DESCRIPTION:
XS GIS Cut Line= 4
      2287441.05     13216070.02      2287632.03     13215960.63
      2287703.21     13215910.29      2287930.68     13215734.91
#Sta/Elev= 30
  4694.2  214.74  4701.9  213.34  4811.3  209.46  4817.1  208.59  4854.5  207.56
  4886.1  204.81  4888.7  205.18  4891.9  205.63  4913.1  204.19  4928.4  204.25
  4934.6  205.07  4949.3  204.54    4958  203.01  5021.5  203.13  5057.7  203.05
  5061.2   202.2    5064   201.7  5067.2   202.2  5070.5  203.36  5078.7  203.12
  5093.2  203.98  5099.5  205.19  5120.8  207.07  5184.7  209.48  5199.2  210.83
  5213.7  211.29  5228.2  213.24  5271.7  215.45    5278  216.54  5288.7  216.29
#Mann= 5 ,-1 , 0
  4694.2      .1       0  4888.7     .05       0  5021.5      .1       0
  5061.2     .04       0  5067.2      .1       0
Bank Sta=5061.2,5067.2
XS Rating Curve= 0 ,0
Exp/Cntr=0.3,0.1

Type RM Length L Ch R = 1 ,9041    ,377,377,377
BEGIN DESCRIPTION:
UNT 069 IN LACR 16.0
END DESCRIPTION:
XS GIS Cut Line= 3
       2287470.6     13216111.66      2287640.71      13216021.4
      2287961.92     13215759.22
#Sta/Elev= 30
  4685.5  212.58  4806.8  206.99  4812.8  204.44  4829.1  202.37  4834.7  204.22
  4836.2  203.42  4840.7  201.01  4863.4   199.3    4900  198.67  4928.5  200.22
  4962.3  200.18  5000.4  198.94  5021.2  199.66    5042  198.39  5046.9  196.65
  5049.6  196.15  5052.9  196.65  5064.3   199.2  5070.7  199.24  5078.6  203.98
  5099.4  205.74  5106.6  208.43  5113.8  209.64  5120.2  208.81  5171.1  210.59
  5220.8  214.49  5227.2  214.06    5256  215.82  5262.4  217.92  5292.7  216.99
#Mann= 5 ,-1 , 0
  4685.5      .1       0  4836.2     .05       0  4962.3      .1       0
  5046.9     .07       0  5052.9      .1       0
Bank Sta=5046.9,5052.9
XS Rating Curve= 0 ,0
Exp/Cntr=0.3,0.1

Type RM Length L Ch R = 1 ,8664    ,121,121,121
BEGIN DESCRIPTION:
Mapping XS 135777ea
END DESCRIPTION:
XS GIS Cut Line= 3
      2287516.75      13216291.9      2287746.76     13216244.16
       2287902.9     13216148.74
#Sta/Elev= 30
  4817.3  210.16  4848.9  207.74  4870.6   206.9    4884  205.73    4900  204.93
  4910.2   203.5  4930.6  202.36  4940.9  201.05    4954  195.87  4960.7  192.96
  4965.8  192.95  4978.7  191.22  4981.5  190.72  4984.7  191.22  4991.9  191.26
  5002.1   193.4  5010.8  194.19  5073.4  195.14  5079.2  197.12  5094.7  197.82
  5100.5  199.93  5110.1  200.36    5116   202.1  5137.3  203.52  5152.7  203.98
  5182.3  206.02  5204.9  206.88  5226.2  208.36  5232.1  208.33  5235.2  208.95
#Mann= 5 ,-1 , 0
  4817.3      .1       0    4884     .05       0    4954      .1       0
  4978.7     .07       0  4984.7      .1       0
Bank Sta=4978.7,4984.7
XS Rating Curve= 0 ,0
Exp/Cntr=0.3,0.1

Type RM Length L Ch R = 1 ,8543    ,229,229,229
BEGIN DESCRIPTION:
UNT 069 IN LACR 15.0
END DESCRIPTION:
XS GIS Cut Line= 4
      2287529.71     13216406.93      2287703.35     13216374.37
      2287829.22     13216320.11      2287926.85     13216218.14
#Sta/Elev= 30
  4738.2  210.28  4756.5  209.09  4763.7  208.27  4768.7  208.51  4776.9   206.8
  4780.2  206.71  4807.4  205.46  4816.2  204.46    4831  203.81  4848.1   202.9
  4873.9  200.42  4888.8  199.82    4899  198.19  4923.1  195.97  4941.2  194.76
  4963.2  193.92  4970.2  192.61  5006.7  191.13  5014.2  190.15    5017  189.65
  5020.2  190.15  5028.5  190.91  5039.4  199.79  5046.2  201.59  5081.6  202.82
  5109.9  204.44    5124  204.63  5173.4  206.45  5180.6  207.08  5193.1   206.9
#Mann= 5 ,-1 , 0
  4738.2      .1       0  4780.2     .05       0    4831      .1       0
  5014.2     .07       0  5020.2      .1       0
Bank Sta=5014.2,5020.2
XS Rating Curve= 0 ,0
Exp/Cntr=0.3,0.1

Type RM Length L Ch R = 1 ,8314    ,352,352,352
BEGIN DESCRIPTION:
Mapping XS 0b9fa59c
END DESCRIPTION:
XS GIS Cut Line= 3
      2287449.77     13216538.76      2287968.84     13216498.83
      2288300.44     13216498.83
#Sta/Elev= 30
  4711.2  216.48  4749.3   212.8  4779.3  211.79  4809.4  209.09  4822.6   208.8
  4849.6  205.54  4928.2   201.4  4939.8  195.08  4949.9  191.96  4969.9  191.11
  4976.9  189.44  4979.7  188.94  4982.9  189.44    4990  189.53    5000  191.92
    5010  192.64  5030.1  191.88  5040.1   192.9  5050.1  196.11  5058.6  194.85
  5063.6  195.67  5070.2  194.51  5090.3  194.08  5120.4  196.06  5140.4  196.04
  5150.4  200.18  5200.6  202.66  5220.6  202.42  5420.7  213.96  5563.4  220.93
#Mann= 4 ,-1 , 0
  4711.2     .05       0  4822.6      .1       0  4976.9     .07       0
  4982.9      .1       0
Bank Sta=4976.9,4982.9
XS Rating Curve= 0 ,0
Exp/Cntr=0.3,0.1

Type RM Length L Ch R = 1 ,7962    ,264,264,264
BEGIN DESCRIPTION:
UNT 069 IN LACR 14.0
END DESCRIPTION:
XS GIS Cut Line= 2
      2287415.01     13216715.84      2288258.81      13216790.5
#Sta/Elev= 30
  4568.6  218.05  4592.2   217.6  4601.4  216.07  4700.2  210.23  4812.3  203.83
  4865.6  201.89  4962.8  195.97  4972.5  188.52  4977.6  194.38  4982.9   192.4
    4993  185.29    5000   184.8  5002.8   184.3    5006   184.8  5033.1  189.74
  5073.3  189.99  5083.3  191.64  5113.4  192.26  5143.6  195.21  5153.6  195.07
  5163.6  199.25  5173.7  200.15  5183.7     204  5243.9  206.47  5274.1  209.47
  5284.1  209.26  5294.1  211.22  5344.3  213.65  5374.4  216.88  5415.7  219.45
#Mann= 5 ,-1 , 0
  4568.6      .1       0  4592.2     .05       0  4700.2      .1       0
    5000     .07       0    5006      .1       0
Bank Sta=5000,5006
XS Rating Curve= 0 ,0
Exp/Cntr=0.3,0.1

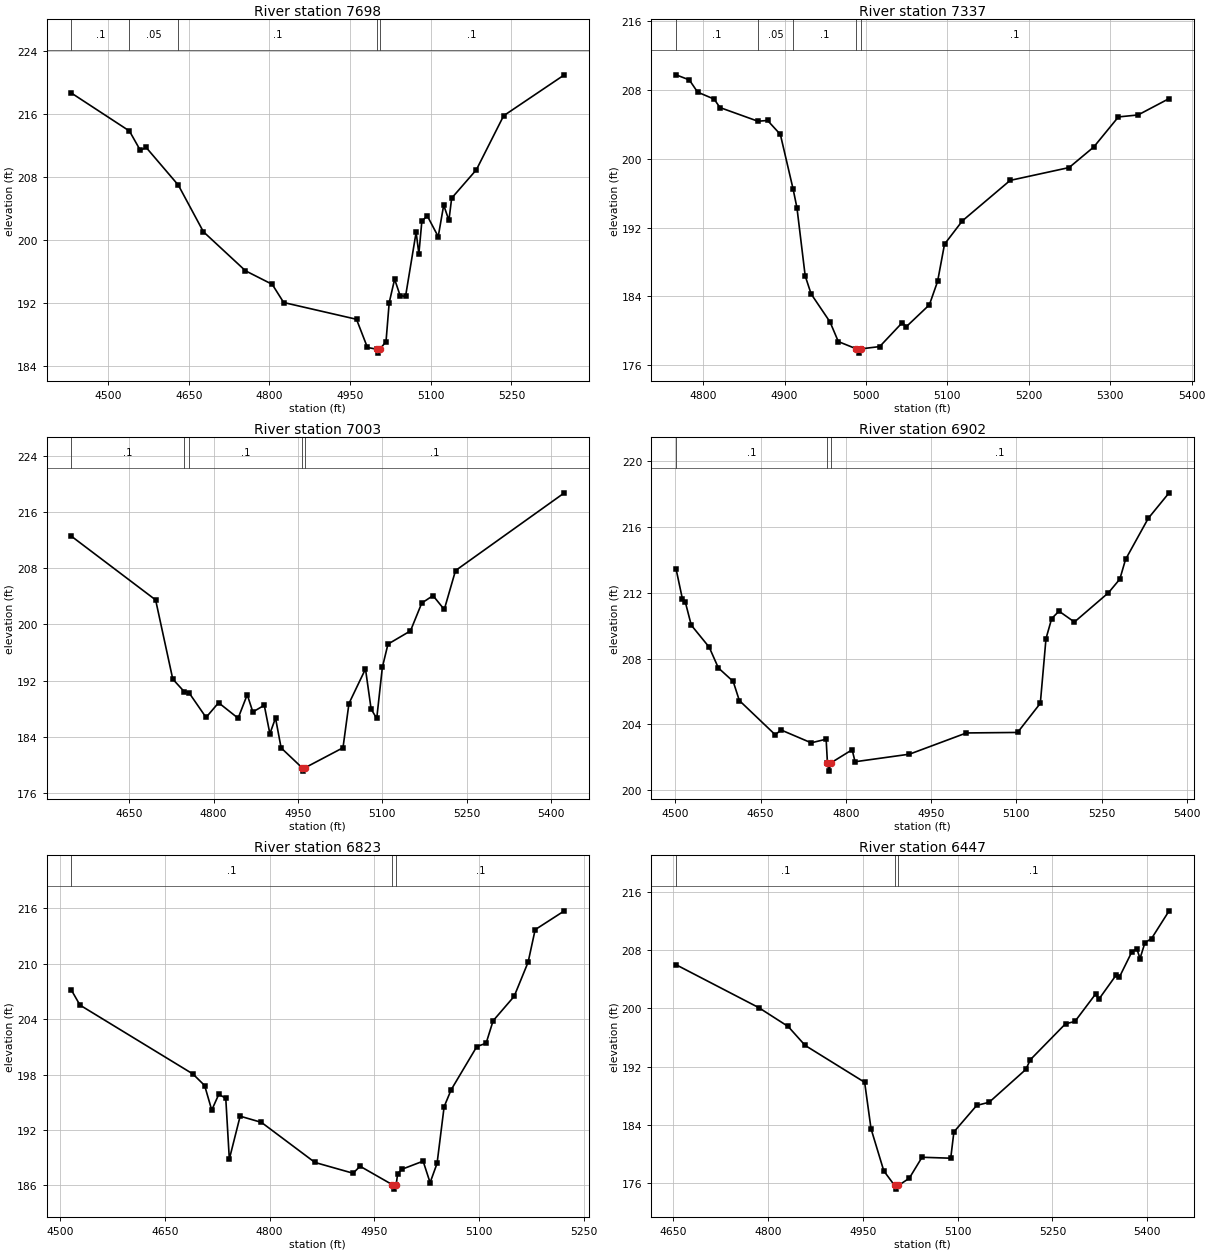
Type RM Length L Ch R = 1 ,7698    ,361,361,361
BEGIN DESCRIPTION:
UNT 069 IN LACR 13.0
END DESCRIPTION:
XS GIS Cut Line= 3
      2287347.27       13216820.      2287788.28      13216983.2
      2288229.25     13217056.12
#Sta/Elev= 30
  4431.4  218.64  4539.5  213.81  4559.8  211.35  4570.5  211.73  4630.5  206.93
  4677.1  201.01  4755.4  196.05  4805.1  194.33  4826.4  192.02  4961.9  189.89
  4982.2  186.31  4999.4  186.09  5002.2  185.59  5005.4  186.09  5016.8  187.06
  5022.7     192  5032.8  194.98    5043  192.91  5053.1  192.79  5072.8  200.95
  5077.9   198.2  5083.5  202.38  5093.7  203.01  5113.9  200.39  5124.1   204.4
  5133.8  202.45  5138.9  205.28  5184.9  208.89  5235.6  215.75  5348.6  220.95
#Mann= 5 ,-1 , 0
  4431.4      .1       0  4539.5     .05       0  4630.5      .1       0
  4999.4     .07       0  5005.4      .1       0
Bank Sta=4999.4,5005.4
XS Rating Curve= 0 ,0
Exp/Cntr=0.3,0.1

Type RM Length L Ch R = 1 ,7337    ,334,334,334
BEGIN DESCRIPTION:
Mapping XS 55bed9fb
END DESCRIPTION:
XS GIS Cut Line= 3
      2287371.63     13217141.87      2287699.44     13217201.32
      2287969.44     13217236.98
#Sta/Elev= 30
  4766.8  209.74  4783.1  209.15  4793.3  207.73  4813.6  206.92  4820.7  205.94
  4867.4  204.35  4879.2  204.44  4894.9  202.82  4910.6  196.46  4915.3  194.29
  4925.4  186.39  4932.7  184.29  4955.9  181.04  4966.1  178.76  4988.2  177.92
  4990.9  177.42  4994.2  177.92  5016.9  178.18  5044.6  180.96  5049.7   180.5
  5077.9  183.03    5088  185.75  5096.5  190.07  5118.4  192.78  5177.1  197.48
  5249.5  198.97  5279.8  201.36    5310  204.85  5334.2  205.08  5372.3  206.98
#Mann= 5 ,-1 , 0
  4766.8      .1       0  4867.4     .05       0  4910.6      .1       0
  4988.2     .07       0  4994.2      .1       0
Bank Sta=4988.2,4994.2
XS Rating Curve= 0 ,0
Exp/Cntr=0.3,0.1

Type RM Length L Ch R = 1 ,7003    ,101,101,101
BEGIN DESCRIPTION:
UNT 069 IN LACR 12.0
END DESCRIPTION:
XS GIS Cut Line= 3
      2287290.56     13217355.99       2287612.4     13217417.92
       2288161.3     13217431.28
#Sta/Elev= 30
  4546.9  212.54  4696.8  203.48  4727.3  192.23  4747.6  190.45  4756.2  190.29
  4786.5  186.78  4808.8  188.87  4843.5  186.67  4859.7  190.01  4869.7  187.56
    4890  188.51    4900  184.46    4910   186.7    4920  182.45    4957  179.65
  4959.7  179.15    4963  179.65    5030  182.47  5040.6  188.76    5070  193.67
    5080  187.98    5090  186.63    5100  193.91    5110   197.2    5150  199.08
  5170.1  203.04  5190.1  204.09  5210.1  202.12  5230.1  207.65  5423.7   218.7
#Mann= 5 ,-1 , 0
  4546.9      .1       0  4747.6     .05       0  4756.2      .1       0
    4957     .07       0    4963      .1       0
Bank Sta=4957,4963
XS Rating Curve= 0 ,0
Exp/Cntr=0.3,0.1

Type RM Length L Ch R = 1 ,6902    ,79,79,79
BEGIN DESCRIPTION:
Mapping XS 2a7410d7
END DESCRIPTION:
XS GIS Cut Line= 5
      2287272.32      13217408.2      2287541.96     13217498.08
      2287688.91      13217516.3      2287930.59     13217510.22
      2288124.37     13217505.41
#Sta/Elev= 30
  4501.1  213.45  4512.4  211.61  4517.6  211.41  4527.9  210.03  4559.5  208.69
  4575.6  207.43  4601.7  206.61  4612.5  205.45  4675.7  203.37    4686  203.66
    4739  202.88  4765.3   203.1  4767.6  201.66  4770.4  201.16  4773.6  201.66
  4811.1  202.46  4816.2  201.73    4912  202.19  5012.2  203.48  5102.3  203.51
  5142.3  205.28  5152.3  209.21  5162.3  210.43  5175.2  210.88  5202.3  210.22
  5262.3     212  5282.3  212.83  5292.3  214.02  5332.3  216.52    5369  218.07
#Mann= 3 ,-1 , 0
  4501.1      .1       0  4767.6     .07       0  4773.6      .1       0
Bank Sta=4767.6,4773.6
XS Rating Curve= 0 ,0
Exp/Cntr=0.3,0.1

Type RM Length L Ch R = 1 ,6823    ,376,376,376
BEGIN DESCRIPTION:
UNT 069 IN LACR 11.0
END DESCRIPTION:
XS GIS Cut Line= 3
        2287310.     13217529.65      2287642.76     13217592.81
       2288009.5     13217561.23
#Sta/Elev= 30
  4515.8  207.17  4528.2  205.53  4690.1  198.07  4706.9  196.82  4717.1  194.16
  4727.2  195.87  4737.2  195.44  4742.3  188.85  4757.8   193.5  4788.3  192.83
    4865  188.49  4919.7  187.32  4929.7  188.08  4975.5   186.1  4978.3   185.6
  4981.5   186.1  4983.6  187.28    4990  187.76  5020.1  188.63  5030.1   186.3
  5040.1  188.39  5050.2  194.52  5060.2  196.35  5097.1  201.04  5110.4   201.4
  5120.4  203.83  5150.6  206.48  5170.6  210.18  5180.7   213.7  5222.6  215.74
#Mann= 3 ,-1 , 0
  4515.8      .1       0  4975.5     .07       0  4981.5      .1       0
Bank Sta=4975.5,4981.5
XS Rating Curve= 0 ,0
Exp/Cntr=0.3,0.1

Type RM Length L Ch R = 1 ,6447    ,286,286,286
BEGIN DESCRIPTION:
Mapping XS d8468a9b
END DESCRIPTION:
XS GIS Cut Line= 3
      2287261.89     13217834.84      2287734.16     13217897.34
      2288024.29     13217807.54
#Sta/Elev= 30
  4654.5  205.97  4785.3  200.09  4831.9   197.5  4858.7  194.91  4952.9  189.85
    4963  183.48  4983.2   177.7  5000.3   175.7  5003.1   175.2  5006.3   175.7
  5023.5  176.69  5043.7  179.57  5089.1  179.44  5094.1  183.04  5130.2  186.68
  5149.9  187.11  5207.9  191.61  5215.1  192.95  5270.7  197.87  5285.6  198.19
  5318.2  201.94  5323.4  201.23  5350.8  204.55    5356  204.28  5375.4  207.69
  5383.4  208.18  5388.6  206.82  5396.3  208.98  5406.8  209.56  5434.6  213.36
#Mann= 3 ,-1 , 0
  4654.5      .1       0  5000.3     .07       0  5006.3      .1       0
Bank Sta=5000.3,5006.3
XS Rating Curve= 0 ,0
Exp/Cntr=0.3,0.1

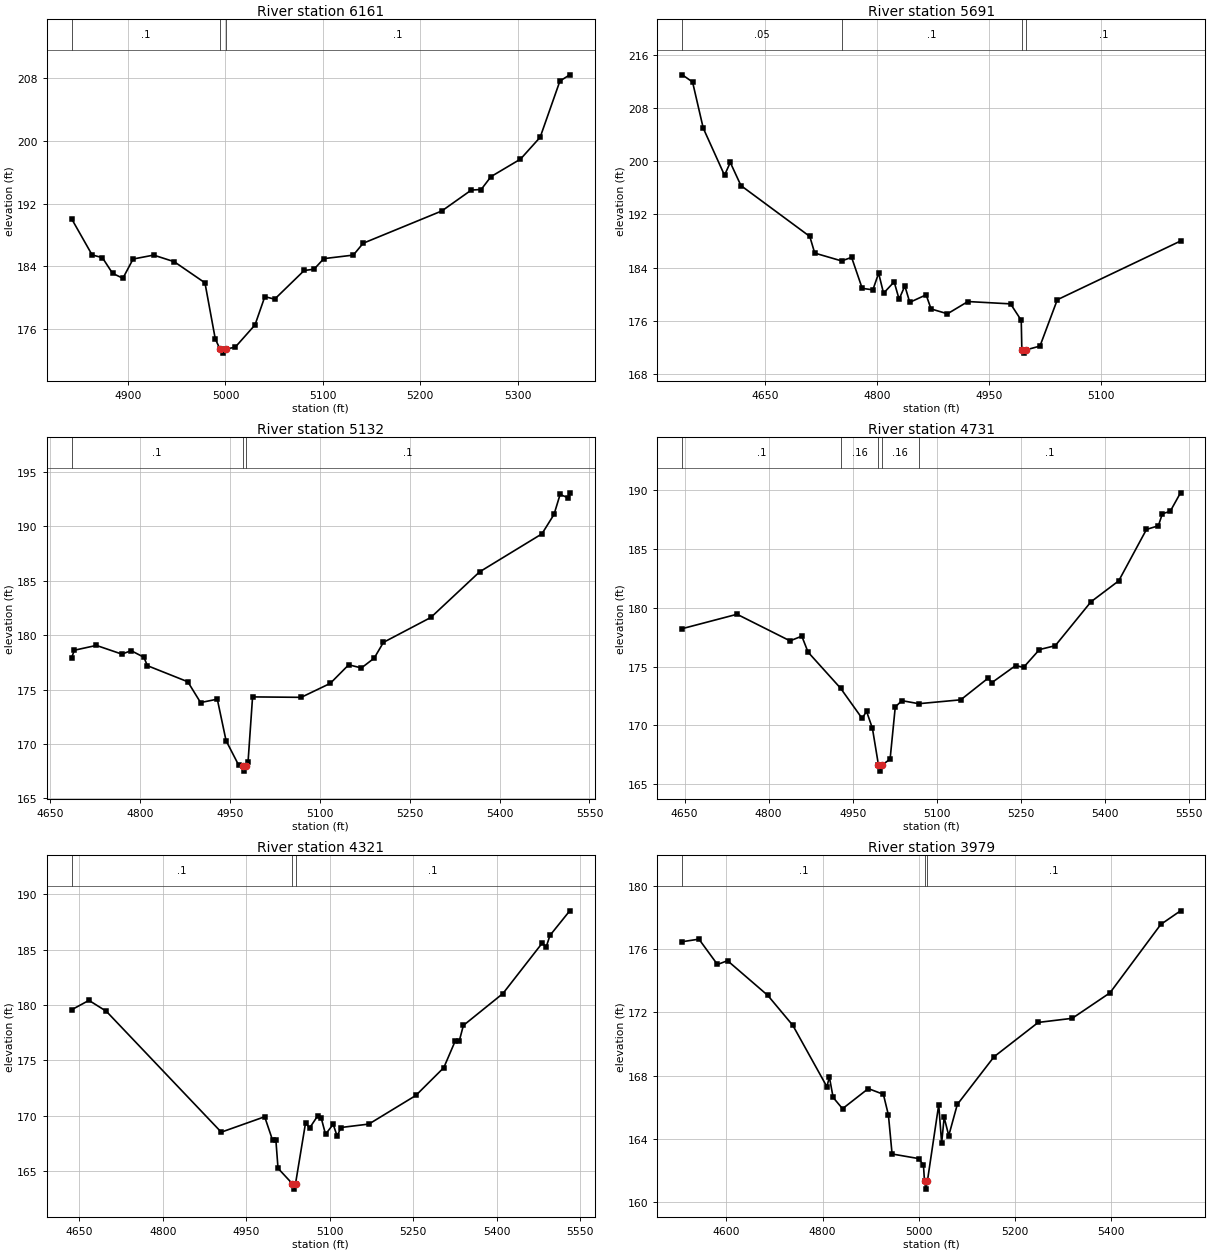
Type RM Length L Ch R = 1 ,6161    ,470,470,470
BEGIN DESCRIPTION:
UNT 069 IN LACR 10.0
END DESCRIPTION:
XS GIS Cut Line= 3
      2287487.73     13218046.86      2287637.72     13218096.85
      2287987.77     13218046.85
#Sta/Elev= 30
  4841.9  190.08    4863  185.47  4873.5  185.13    4884  183.13  4894.6   182.5
  4905.1  184.95  4926.2  185.45  4947.3  184.61  4978.9  181.92  4989.5  174.78
  4994.4  173.47  4997.1  172.97  5000.4  173.47  5010.1  173.74  5030.3  176.56
  5040.4  180.16  5050.5  179.84  5080.8  183.49  5090.9  183.65    5101     185
  5131.3  185.45  5141.4  186.96  5222.2  191.07  5252.5  193.73  5262.6   193.8
  5272.7  195.44    5303  197.67  5323.2  200.45  5343.5  207.61  5353.6   208.4
#Mann= 3 ,-1 , 0
  4841.9      .1       0  4994.4     .07       0  5000.4      .1       0
Bank Sta=4994.4,5000.4
XS Rating Curve= 0 ,0
Exp/Cntr=0.3,0.1

Type RM Length L Ch R = 1 ,5691    ,559,559,559
BEGIN DESCRIPTION:
UNT 069 IN LACR 9.0
END DESCRIPTION:
XS GIS Cut Line= 3
       2287387.7     13218796.87      2287737.72     13218496.85
      2287937.76     13218446.84
#Sta/Elev= 30
    4539  212.97  4552.7  211.89    4567  204.96  4595.5  197.88  4603.2  199.81
  4617.5  196.33  4709.7  188.69  4716.3  186.19  4752.4  185.01  4765.7  185.55
  4779.9  180.89  4794.2  180.67  4801.9  183.17  4808.5  180.16  4822.7  181.87
  4829.3  179.26    4837  181.25  4843.6  178.79  4865.5  179.92  4872.1   177.8
  4894.1  177.07  4921.5  178.91  4978.6  178.56  4992.9  176.09  4993.7  171.66
  4996.5  171.16  4999.7  171.66    5018  172.22  5041.2  179.18  5206.2     188
#Mann= 4 ,-1 , 0
    4539     .05       0  4752.4      .1       0  4993.7     .07       0
  4999.7      .1       0
Bank Sta=4993.7,4999.7
XS Rating Curve= 0 ,0
Exp/Cntr=0.3,0.1

Type RM Length L Ch R = 1 ,5132    ,401,401,401
BEGIN DESCRIPTION:
UNT 069 IN LACR 8.0
END DESCRIPTION:
XS GIS Cut Line= 3
      2287818.74      13219163.5      2288157.29      13218616.6
       2288183.2     13218430.91
#Sta/Elev= 30
  4686.4  177.93  4691.1  178.62  4727.8  179.06  4770.3  178.26  4785.7  178.58
    4807  177.97  4812.8   177.2  4880.2  175.72  4901.5  173.81  4929.4  174.12
    4944  170.31  4965.3  168.03  4971.8  168.01  4974.5  167.51  4977.8  168.01
  4980.7  168.38  4988.2  174.33  5069.3  174.29  5117.7  175.57  5148.5  177.28
  5169.7  176.99    5191  177.89  5206.4  179.34  5285.5  181.63  5366.8  185.82
  5470.7  189.31  5490.9   191.1    5501  192.93  5514.9  192.61  5517.1  193.08
#Mann= 3 ,-1 , 0
  4686.4      .1       0  4971.8     .07       0  4977.8      .1       0
Bank Sta=4971.8,4977.8
XS Rating Curve= 0 ,0
Exp/Cntr=0.3,0.1

Type RM Length L Ch R = 1 ,4731    ,410,410,410
BEGIN DESCRIPTION:
UNT 069 IN LACR 7.0
END DESCRIPTION:
XS GIS Cut Line= 3
      2288175.77     13219479.82      2288342.44     13218958.96
      2288584.07     13218717.33
#Sta/Elev= 30
  4646.1  178.23  4743.7  179.45  4838.2  177.19  4859.2  177.59  4870.4  176.23
  4928.3  173.17  4966.8   170.6  4974.7   171.2  4985.2  169.75    4996  166.62
  4998.7  166.12    5002  166.62  5016.7  167.14  5025.9  171.57  5037.7  172.11
  5067.8  171.85  5142.7  172.18  5191.5  174.02  5198.2  173.64  5240.6  175.09
  5254.8  174.94  5283.1  176.45  5311.3  176.78    5375  180.51  5424.5  182.29
    5474  186.66  5495.2  186.97  5502.3  187.99  5516.4   188.2  5534.7  189.77
#Mann= 5 ,-1 , 0
  4646.1      .1       0  4928.3     .16       0    4996     .07       0
    5002     .16       0  5067.8      .1       0
Bank Sta=4996,5002
XS Rating Curve= 0 ,0
Exp/Cntr=0.3,0.1

Type RM Length L Ch R = 1 ,4321    ,342,342,342
BEGIN DESCRIPTION:
UNT 069 IN LACR 6.0
END DESCRIPTION:
XS GIS Cut Line= 3
      2288237.73     13219496.85      2288587.72     13219396.86
      2288937.72     13218996.86
#Sta/Elev= 30
    4636  179.56  4667.2  180.41  4698.4  179.43  4905.1  168.52  4983.1  169.91
  4997.4  167.78  5003.3  167.78  5007.1  165.26  5032.6  163.88  5035.3  163.38
  5038.6  163.88  5056.5  169.33  5064.1  168.91  5078.3  169.98  5084.9  169.77
  5092.5  168.33  5106.3  169.23  5113.4  168.15  5120.1  168.94  5170.4  169.25
  5254.8  171.83  5305.1  174.34    5326  176.79  5332.7  176.71  5340.3  178.15
  5411.4  181.03  5481.7  185.56  5489.3  185.25  5495.9  186.27  5531.5  188.49
#Mann= 3 ,-1 , 0
    4636      .1       0  5032.6     .07       0  5038.6      .1       0
Bank Sta=5032.6,5038.6
XS Rating Curve= 0 ,0
Exp/Cntr=0.3,0.1

Type RM Length L Ch R = 1 ,3979    ,385,385,385
BEGIN DESCRIPTION:
UNT 069 IN LACR 5.0
END DESCRIPTION:
XS GIS Cut Line= 3
      2288317.85     13219801.51      2289034.03     13219580.15
      2289211.97     13219354.46
#Sta/Elev= 30
  4508.2  176.47  4542.8  176.63  4581.3  175.03  4602.3  175.27    4686  173.08
  4738.3  171.18  4809.1  167.31  4814.3  167.92  4822.1  166.63  4841.7  165.92
  4895.3  167.19  4926.7  166.83  4937.2  165.52  4944.8  163.06    5000  162.77
  5010.1  162.36  5012.3  161.34  5015.1  160.84  5018.3  161.34  5041.9  166.17
    5048  163.75  5053.2  165.37  5062.8  164.22  5080.6  166.19    5157   169.2
    5249  171.37  5319.8  171.63  5398.4  173.24  5504.1  177.56  5545.2  178.42
#Mann= 3 ,-1 , 0
  4508.2      .1       0  5012.3     .07       0  5018.3      .1       0
Bank Sta=5012.3,5018.3
XS Rating Curve= 0 ,0
Exp/Cntr=0.3,0.1

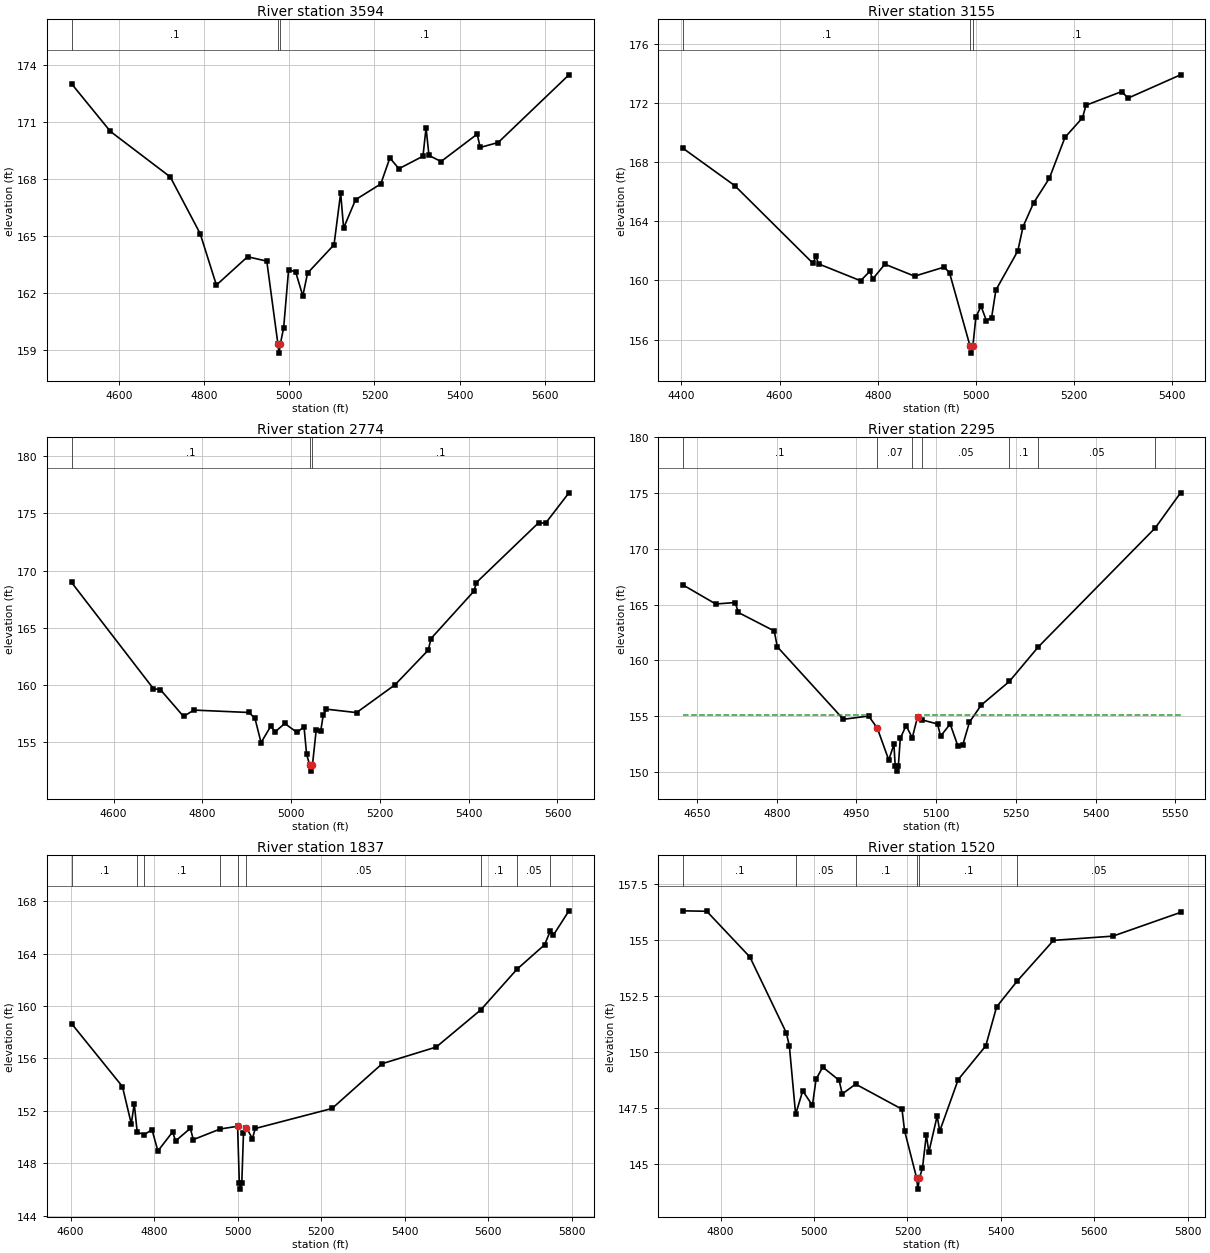
Type RM Length L Ch R = 1 ,3594    ,439,439,439
BEGIN DESCRIPTION:
Mapping XS bd2547f4
END DESCRIPTION:
XS GIS Cut Line= 4
       2288326.6     13220131.36      2288660.76     13220105.32
      2288981.94     13219949.07      2289311.78     13219606.22
#Sta/Elev= 30
  4488.7  173.03  4580.1  170.52  4720.5  168.13  4790.7  165.15  4828.9  162.44
  4902.1  163.93  4947.2   163.7  4973.2  159.36  4975.9  158.86  4979.2  159.36
  4986.8  160.19  4998.4  163.24  5014.9  163.14  5031.8  161.87    5043  163.07
  5105.1  164.56  5120.7  167.28  5127.6  165.44  5155.7  166.93  5214.9  167.76
  5236.3  169.13  5257.4  168.56    5314  169.22  5321.2  170.71  5328.1  169.26
  5356.4  168.94  5441.3  170.38  5448.3  169.68  5490.7  169.94  5656.8   173.5
#Mann= 3 ,-1 , 0
  4488.7      .1       0  4973.2     .07       0  4979.2      .1       0
Bank Sta=4973.2,4979.2
XS Rating Curve= 0 ,0
Exp/Cntr=0.3,0.1

Type RM Length L Ch R = 1 ,3155    ,381,381,381
BEGIN DESCRIPTION:
UNT 069 IN LACR 4.0
END DESCRIPTION:
XS GIS Cut Line= 2
      2288479.28     13220167.29      2289428.06     13220522.54
#Sta/Elev= 30
  4403.7  168.94  4508.8  166.42  4668.5  161.15  4673.9  161.65  4679.7  161.12
  4765.1  159.98  4784.3  160.63  4789.6  160.09  4814.6   161.1  4875.1  160.29
  4935.9  160.91  4946.6  160.48  4987.9  155.58  4990.6  155.08  4993.9  155.58
    5000  157.53  5010.5  158.25  5021.4  157.28    5032  157.49  5040.7  159.35
  5085.4     162    5096  163.64  5117.5  165.25  5149.5  166.91  5181.5  169.69
  5217.1  171.01  5224.2  171.86  5297.2  172.79  5309.7  172.34  5416.8  173.92
#Mann= 3 ,-1 , 0
  4403.7      .1       0  4987.9     .07       0  4993.9      .1       0
Bank Sta=4987.9,4993.9
XS Rating Curve= 0 ,0
Exp/Cntr=0.3,0.1

Type RM Length L Ch R = 1 ,2774    ,479,479,479
BEGIN DESCRIPTION:
UNT 069 IN LACR 3.0
END DESCRIPTION:
XS GIS Cut Line= 2
      2288357.93      13220353.6      2289333.54     13220904.69
#Sta/Elev= 30
  4505.4  168.97  4689.8  159.69  4705.7   159.6  4757.8  157.26  4780.8  157.82
    4905  157.61  4918.6   157.1  4932.3  154.98    4954   156.4  4964.2  155.93
  4985.8  156.65  5013.2  155.87  5029.1  156.36  5034.9  153.98    5042  152.99
  5044.7  152.49    5048  152.99  5056.5  156.06  5066.7  155.99  5072.4  157.38
  5079.4   157.9  5147.5   157.6  5234.1  160.03  5309.1  163.06    5315  164.06
  5411.8   168.2  5417.5  168.96  5557.6  174.18  5573.3  174.14  5625.9  176.79
#Mann= 3 ,-1 , 0
  4505.4      .1       0    5042     .07       0    5048      .1       0
Bank Sta=5042,5048
XS Rating Curve= 0 ,0
Exp/Cntr=0.3,0.1

Type RM Length L Ch R = 1 ,2295    ,458,458,458
BEGIN DESCRIPTION:
UNT 069 IN LACR 2.0
END DESCRIPTION:
XS GIS Cut Line= 3
       2288209.4     13220730.33      2288435.07     13220869.21
       2289054.2     13221128.98
#Sta/Elev= 30
  4623.7  166.75  4685.1  165.05  4721.8  165.18  4727.6  164.29  4795.2  162.63
    4801  161.21  4925.4  154.71    4973     155  4989.2  153.92  5010.8  151.06
  5020.5  152.45  5022.9  150.56  5025.7  150.06  5028.9  150.56  5032.5     153
  5043.4  154.14  5055.1  153.05  5065.1  154.95  5073.5  154.65  5102.7  154.29
  5108.4  153.19  5126.4  154.29    5141  152.31  5150.2  152.42  5162.7  154.45
  5184.8  155.98  5237.7   158.1  5292.3   161.2  5512.6  171.88  5560.1  175.02
#Mann= 7 ,-1 , 0
  4623.7      .1       0  4989.2     .07       0  5055.1      .1       0
  5073.5     .05       0  5237.7      .1       0  5292.3     .05       0
  5512.6      .1       0
#XS Ineff= 2 , 0
       0 4972.71   155.1 5065.06       0   155.1
Permanent Ineff=
       T       T
Bank Sta=4989.2,5065.1
XS Rating Curve= 0 ,0
Exp/Cntr=0.3,0.1

Type RM Length L Ch R = 1 ,1837    ,317,317,317
BEGIN DESCRIPTION:
Mapping XS 622ef2ae
END DESCRIPTION:
XS GIS Cut Line= 3
      2288014.91     13220957.25      2288561.77     13221512.78
      2288900.32      13221278.4
#Sta/Elev= 30
  4602.3  158.66  4724.2  153.85  4745.4  151.01  4752.5  152.54  4759.6  150.37
  4776.4  150.18    4795  150.56  4809.1  148.93  4844.4  150.39  4851.5   149.7
  4886.8  150.66    4894   149.8  4958.2  150.61    5000  150.82  5004.1  146.52
  5006.9  146.02  5010.1  146.52  5014.1  150.29  5021.3  150.71  5035.4  149.88
  5042.4  150.65  5226.3  152.18  5346.4   155.6  5475.8  156.87  5582.5  159.71
  5668.8   162.8  5735.3  164.68  5748.9  165.73  5756.2  165.41  5793.6  167.27
#Mann= 9 ,-1 , 0
  4602.3      .1       0  4759.6     .05       0  4776.4      .1       0
  4958.2     .05       0    5000     .03       0  5021.3     .05       0
  5582.5      .1       0  5668.8     .05       0  5748.9      .1       0
Bank Sta=5000,5021.3
XS Rating Curve= 0 ,0
Exp/Cntr=0.3,0.1

Type RM Length L Ch R = 1 ,1520    ,468,468,468
BEGIN DESCRIPTION:
Mapping XS ef9e4bf5
END DESCRIPTION:
XS GIS Cut Line= 3
      2287827.43     13221216.43      2288126.91     13221468.17
      2288742.97     13221741.49
#Sta/Elev= 30
  4719.6  156.31  4770.2  156.29  4862.5  154.25  4940.6  150.86  4947.1  150.27
  4960.5  147.22  4975.7  148.27  4996.5  147.62  5004.3  148.79  5018.6  149.33
  5053.7  148.74  5060.3  148.13    5089  148.57  5188.3  147.45  5193.8  146.49
  5219.6  144.38  5222.3  143.88  5225.6  144.38  5232.1  144.81  5240.4  146.31
  5245.8  145.53  5263.6  147.15  5269.1  146.47  5308.6  148.77  5367.7  150.28
  5390.9  152.02  5435.3  153.18  5512.7  154.99    5640  155.18  5784.8  156.24
#Mann= 6 ,-1 , 0
  4719.6      .1       0  4960.5     .05       0    5089      .1       0
  5219.6     .03       0  5225.6      .1       0  5435.3     .05       0
Bank Sta=5219.6,5225.6
XS Rating Curve= 0 ,0
Exp/Cntr=0.3,0.1

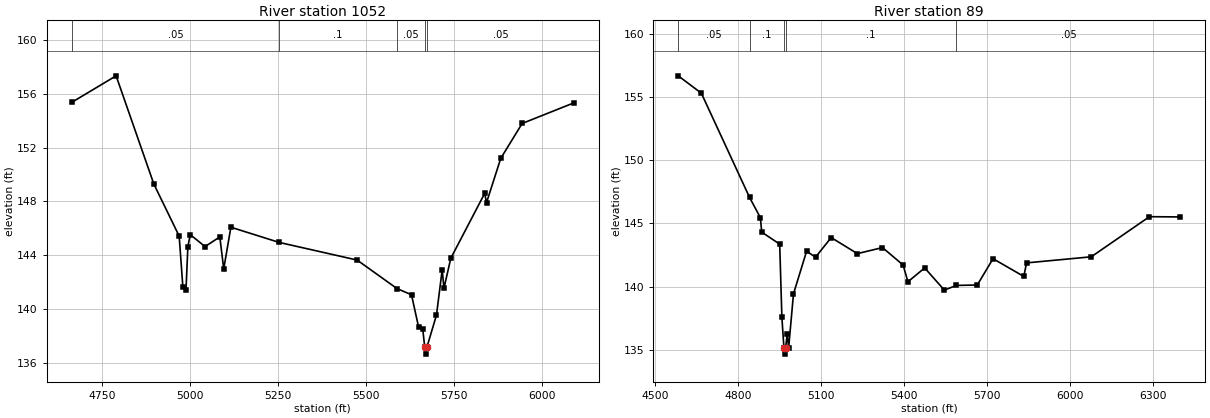
Type RM Length L Ch R = 1 ,1052    ,963,963,963
BEGIN DESCRIPTION:
Mapping XS 39f2e8a2
END DESCRIPTION:
XS GIS Cut Line= 3
      2287763.17       13221426.      2288006.21     13222189.86
      2288622.58     13222294.04
#Sta/Elev= 30
  4663.3  155.36  4789.3  157.33  4896.5  149.29  4968.5  145.42    4979  141.64
  4987.9  141.42  4993.2  144.64    5000  145.53    5042  144.64    5084  145.36
  5095.1  142.98  5115.4  146.08  5252.8  144.95  5474.2  143.64  5587.5  141.52
  5628.7  141.06    5649  138.64  5660.5  138.55  5666.3  137.15    5669  136.65
  5672.3  137.15  5699.7  139.56  5715.9  142.92  5720.9  141.54  5740.3  143.77
  5836.7   148.6  5841.8   147.9  5882.2  151.19  5943.1  153.79    6090  155.32
#Mann= 5 ,-1 , 0
  4663.3     .05       0  5252.8      .1       0  5587.5     .05       0
  5666.3     .03       0  5672.3     .05       0
Bank Sta=5666.3,5672.3
XS Rating Curve= 0 ,0
Exp/Cntr=0.3,0.1

Type RM Length L Ch R = 1 ,89      ,0,0,0
BEGIN DESCRIPTION:
UNT 069 IN LACR 1.0
END DESCRIPTION:
XS GIS Cut Line= 5
      2287580.85     13221460.73      2287471.49     13221705.49
       2287351.7      13222085.7       2287414.2     13222507.57
      2288127.77     13222606.54
#Sta/Elev= 30
  4583.7  156.66  4667.1  155.29  4841.4  147.05  4880.2  145.46  4885.4  144.31
  4950.2  143.36  4958.1  137.57  4965.5  135.17  4968.3  134.67  4971.5  135.17
  4977.3  136.24  4982.5  135.17    5000  139.43  5047.3   142.8  5079.6  142.33
  5136.3  143.88  5230.7  142.61  5321.5  143.09    5396  141.71  5413.3  140.39
    5474  141.48  5544.8  139.73  5588.7   140.1  5663.9  140.13  5720.8  142.21
  5831.9  140.81    5842  141.88  6075.6  142.36  6285.8  145.53  6397.3  145.51
#Mann= 5 ,-1 , 0
  4583.7     .05       0  4841.4      .1       0  4965.5     .07       0
  4971.5      .1       0  5588.7     .05       0
Bank Sta=4965.5,4971.5
XS Rating Curve= 0 ,0
Exp/Cntr=0.3,0.1

Chan Stop Cuts=-1
Use User Specified Reach Order=0
Composite Channel Slope=5