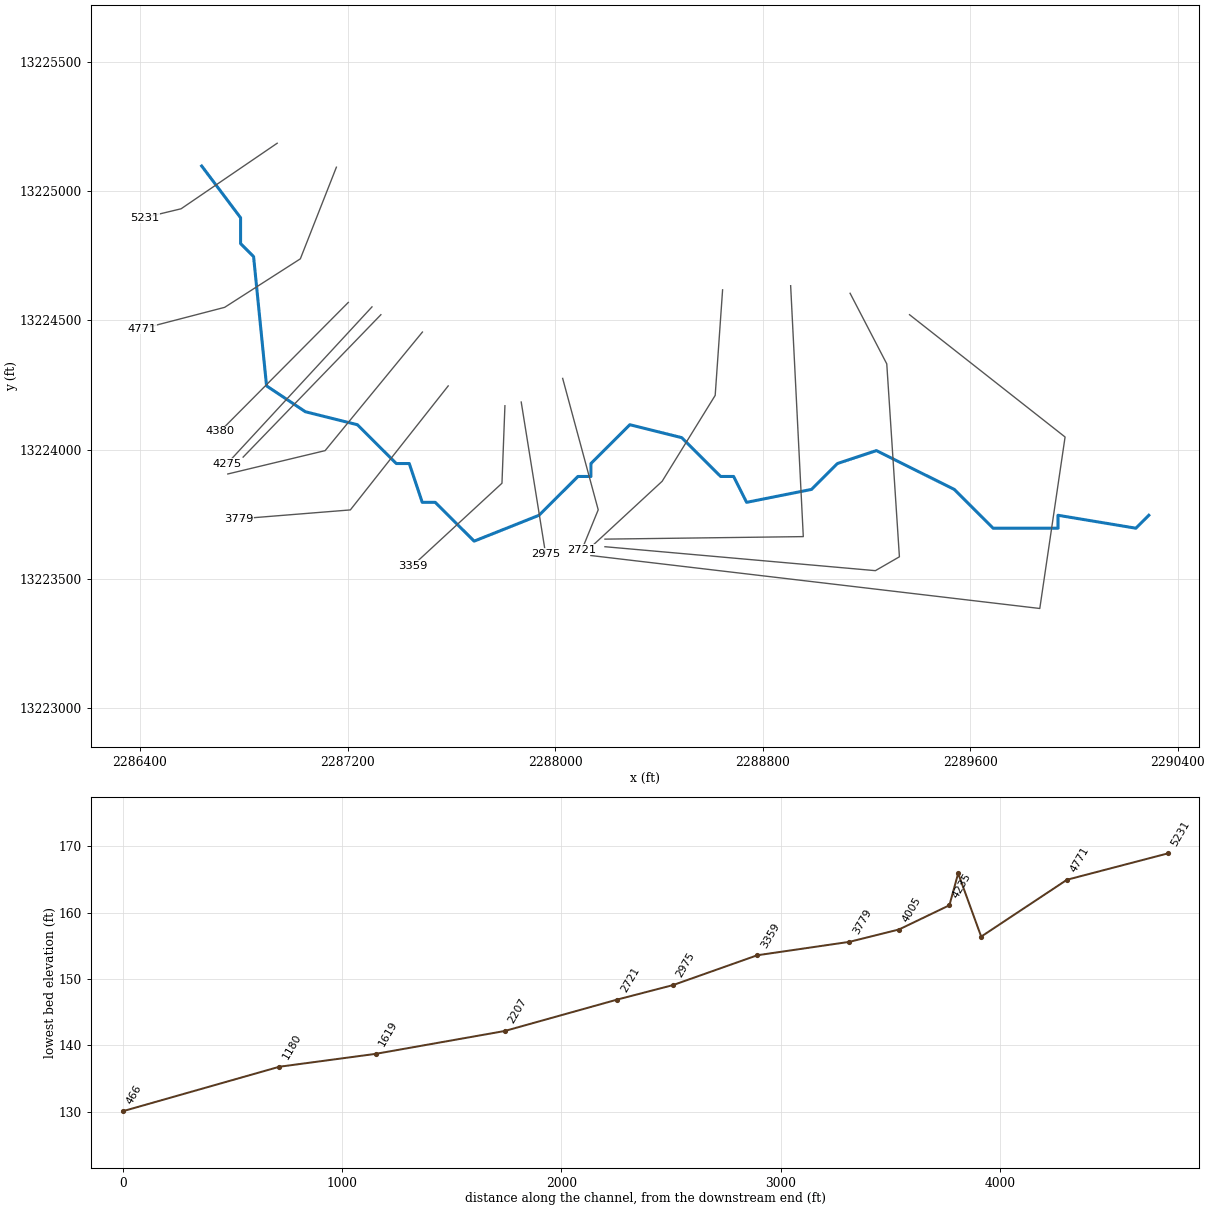
--- UNT 070 IN LACR.prj (project) ---

Proj Title=UNT 070 IN LACR Base Level Engineering
Current Plan=p01
Default Exp/Contr=0.3,0.1
English Units
Geom File=g01
Flow File=f01
Plan File=p01
Y Axis Title=Elevation
X Axis Title(PF)=Main Channel Distance
X Axis Title(XS)=Station
BEGIN DESCRIPTION:
UNT 070 IN LACR
END DESCRIPTION:
DSS Export Rating Curves= 0
DSS Export Rating Curve Sorted= 0
DSS Export Volume Flow Curves= 0
DXF OffsetX= 0
DXF OffsetY= 0
DXF ScaleX= 1
DXF ScaleY= 10

--- UNT 070 IN LACR.p01 (plan) ---

Plan Title=Multiple Run
Short Identifier=Multiple
Geom File=g01
Flow File=f01
Subcritical Flow
K Sum by GR= 0
Std Step Tol= 0.01
Critical Tol= 0.01
Num of Std Step Trials= 20
Max Error Tol= 0.3
Flow Tol Ratio= 0.001
Split Flow NTrial= 30
Split Flow Tol= 0.02
Split Flow Ratio= 0.02
Log Output Level= 0
Friction Slope Method= 1
Unsteady Friction Slope Method= 2
Unsteady Bridges Friction Slope Method= 1
Parabolic Critical Depth
Global Vel Dist=  1 , 1 , 1
Global Log Level= 0
CheckData=True
Encroach Param= -1, 0, 0, 0
BEGIN DESCRIPTION:
Multiple Run
END DESCRIPTION:

--- UNT 070 IN LACR.f01 (steady flow) ---

Flow Title=Multiple
Number of Profiles=7
Profile Names=10-year,25-year,50-year,1pct_min,100-year,1pct_plu,500-year
River Rch & RM= UNT 070 IN LACR,Reach-1,5231
     219     299     365     328     444     600     664
Boundary for River Rch & Prof#=UNT 070 IN LACR,Reach-1,1
Up Type=0
Dn Type=3
Dn Slope=0.005
Boundary for River Rch & Prof#=UNT 070 IN LACR,Reach-1,2
Up Type=0
Dn Type=3
Dn Slope=0.005
Boundary for River Rch & Prof#=UNT 070 IN LACR,Reach-1,3
Up Type=0
Dn Type=3
Dn Slope=0.005
Boundary for River Rch & Prof#=UNT 070 IN LACR,Reach-1,4
Up Type=0
Dn Type=3
Dn Slope=0.005
Boundary for River Rch & Prof#=UNT 070 IN LACR,Reach-1,5
Up Type=0
Dn Type=3
Dn Slope=0.005
Boundary for River Rch & Prof#=UNT 070 IN LACR,Reach-1,6
Up Type=0
Dn Type=3
Dn Slope=0.005
Boundary for River Rch & Prof#=UNT 070 IN LACR,Reach-1,7
Up Type=0
Dn Type=3
Dn Slope=0.005

--- UNT 070 IN LACR.g01 (geometry) ---

Geom Title=Existing Conditions
Program Version=4.10

River Reach=UNT 070 IN LACR ,Reach-1
Reach XY= 30
      2286637.72     13225096.85      2286787.72     13224896.85
      2286787.72     13224796.86      2286837.72     13224746.85
      2286887.72     13224246.85      2287037.72     13224146.86
      2287237.72     13224096.85      2287387.72     13223946.85
      2287437.72     13223946.85      2287487.72     13223796.86
      2287537.72     13223796.86      2287687.72     13223646.86
      2287937.72     13223746.85      2288087.72     13223896.85
      2288137.72     13223896.85      2288137.72     13223946.85
      2288287.72     13224096.85      2288487.72     13224046.85
      2288637.72     13223896.85      2288687.72     13223896.85
      2288737.72     13223796.86      2288987.72     13223846.85
      2289087.72     13223946.85      2289237.72     13223996.86
      2289537.72     13223846.85      2289687.72     13223696.85
      2289937.72     13223696.85      2289937.72     13223746.85
      2290237.72     13223696.85      2290287.72     13223746.85

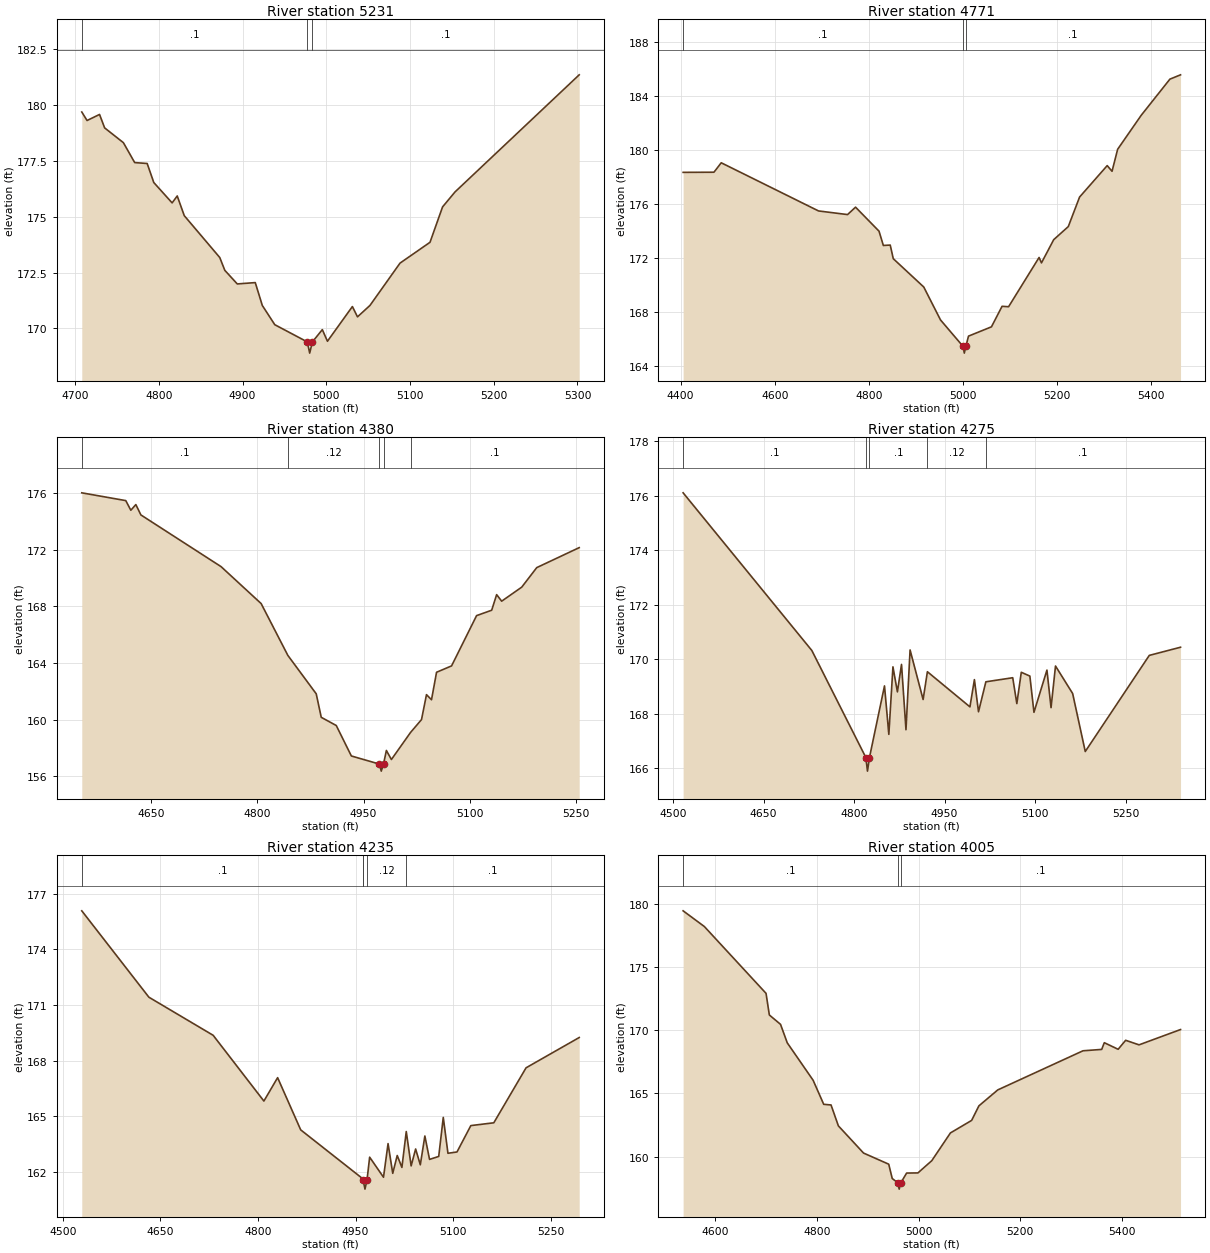
Type RM Length L Ch R = 1 ,5231    ,460,460,460
BEGIN DESCRIPTION:
UNT 070 IN LACR 5.0
END DESCRIPTION:
XS GIS Cut Line= 3
      2286928.71     13225184.88      2286558.36     13224931.48
      2286417.06     13224897.38
#Sta/Elev= 30
    4708  179.67  4714.3  179.29  4729.2  179.56  4735.3  178.96  4757.7   178.3
  4771.2  177.41  4786.1  177.37    4794  176.52  4815.9  175.61    4822  175.92
  4830.4  175.04  4872.8  173.17  4878.8   172.6  4893.7  171.99  4915.2  172.05
  4923.6  171.03  4938.5  170.17  4977.4   169.4  4980.2   168.9  4983.4   169.4
  4995.3  169.95  5001.4  169.43  5031.2  170.98  5037.3  170.52  5052.2  171.03
  5088.1  172.92  5123.9  173.85  5138.9  175.43  5153.8   176.1  5302.1  181.33
#Mann= 3 ,-1 , 0
    4708      .1       0  4977.4     .07       0  4983.4      .1       0
Bank Sta=4977.4,4983.4
XS Rating Curve= 0 ,0
Exp/Cntr=0.3,0.1

Type RM Length L Ch R = 1 ,4771    ,391,391,391
BEGIN DESCRIPTION:
UNT 070 IN LACR 4.0
END DESCRIPTION:
XS GIS Cut Line= 4
      2287156.83     13225092.24      2287017.93     13224738.04
      2286726.27     13224550.54      2286406.85     13224467.22
#Sta/Elev= 30
  4405.3  178.33  4470.8  178.34  4486.3  179.04  4693.1  175.47  4754.8   175.2
  4771.8  175.75  4821.7  173.97  4830.9  172.91  4845.5  172.94    4852  171.93
  4916.8  169.83  4952.4  167.39  5000.3  165.43    5003  164.93  5006.3  165.43
  5011.9  166.19  5060.7  166.88  5083.2   168.4  5097.1  168.37  5161.9  172.02
    5167  171.62    5193  173.34    5224  174.31    5248   176.5  5306.7  178.83
    5317  178.41  5328.9  180.04    5379  182.56    5440  185.24  5462.6  185.56
#Mann= 3 ,-1 , 0
  4405.3      .1       0  5000.3     .07       0  5006.3      .1       0
Bank Sta=5000.3,5006.3
XS Rating Curve= 0 ,0
Exp/Cntr=0.3,0.1

Type RM Length L Ch R = 1 ,4380    ,105,105,105
BEGIN DESCRIPTION:
Mapping XS b895c6cb
END DESCRIPTION:
XS GIS Cut Line= 2
      2287202.84     13224569.65      2286708.69     13224071.17
#Sta/Elev= 30
  4552.4  176.02  4614.5  175.47  4621.6  174.79  4628.7  175.19  4635.8  174.46
  4748.9  170.81  4805.5   168.2  4843.2  164.54  4883.2  161.83  4890.3  160.17
  4911.5  159.59  4932.8  157.44  4972.2  156.87    4975  156.37  4978.2  156.87
  4982.2  157.83  4989.3  157.19  5016.3   159.1  5031.8  160.01  5038.8  161.77
  5045.9  161.41    5053  163.35  5074.2   163.8  5109.5  167.35  5130.8  167.73
  5137.8  168.83  5144.9  168.37  5173.2  169.36  5194.4  170.74  5254.3  172.15
#Mann= 5 ,-1 , 0
  4552.4      .1       0  4843.2     .12       0  4972.2     .07       0
  4978.2     .12       0  5016.3      .1       0
Bank Sta=4972.2,4978.2
XS Rating Curve= 0 ,0
Exp/Cntr=0.3,0.1

Type RM Length L Ch R = 1 ,4275    ,40,40,40
BEGIN DESCRIPTION:
UNT 070 IN LACR 3.0
END DESCRIPTION:
XS GIS Cut Line= 2
        2287294.     13224552.31      2286735.49     13223946.06
#Sta/Elev= 30
  4516.7  176.11    4730  170.32  4819.5  166.39  4822.2  165.89  4825.5  166.39
  4850.4  169.02  4857.6  167.24  4864.4  169.72  4871.8   168.8  4878.6  169.81
    4886  167.41  4892.8  170.34  4914.4  168.52  4921.5  169.54    4992  168.25
  4999.4  169.25  5006.2  168.07  5018.4  169.17  5062.9  169.32  5069.7  168.37
  5077.1  169.52  5091.3  169.38  5098.1  168.05  5119.6   169.6  5126.4  168.22
  5133.8  169.75  5162.2  168.74  5183.1  166.61  5289.2  170.14    5341  170.44
#Mann= 5 ,-1 , 0
  4516.7      .1       0  4819.5     .07       0  4825.5      .1       0
  4921.5     .12       0  5018.4      .1       0
Bank Sta=4819.5,4825.5
XS Rating Curve= 0 ,0
Exp/Cntr=0.3,0.1

Type RM Length L Ch R = 1 ,4235    ,230,230,230
BEGIN DESCRIPTION:
Mapping XS 89cd88bf
END DESCRIPTION:
XS GIS Cut Line= 2
      2287328.34     13224522.08      2286797.38     13223971.63
#Sta/Elev= 30
  4529.1  176.07  4632.3  171.42  4731.1  169.37  4809.1  165.83  4830.2  167.09
  4865.7  164.28  4961.1  161.65  4961.7  161.59  4964.5  161.09  4967.7  161.59
  4971.7  162.81    4993  161.73    5000  163.54  5007.2  161.94  5014.1   162.9
  5021.3  162.26    5028  164.19  5035.5  162.34  5042.4  163.25  5049.6   162.4
  5056.6  163.95  5063.8  162.69  5077.9  162.85  5084.9  164.95  5092.1  163.02
    5106  163.09  5127.3  164.51  5162.6  164.66  5212.2  167.62  5293.9  169.25
#Mann= 5 ,-1 , 0
  4529.1      .1       0  4961.1     .12       0  4961.7     .07       0
  4967.7     .12       0    5028      .1       0
Bank Sta=4961.7,4967.7
XS Rating Curve= 0 ,0
Exp/Cntr=0.3,0.1

Type RM Length L Ch R = 1 ,4005    ,226,226,226
BEGIN DESCRIPTION:
Mapping XS e4143504
END DESCRIPTION:
XS GIS Cut Line= 3
      2287488.41     13224455.04      2287113.42     13223996.72
      2286738.41     13223906.44
#Sta/Elev= 30
  4537.2  179.43  4578.9  178.19  4700.2  172.91  4706.7   171.2  4728.7  170.46
  4741.9     169  4792.8  166.04  4813.6  164.14    4828  164.09  4842.4  162.44
  4891.9  160.29  4941.4  159.41  4948.3  158.28  4959.2  157.94    4962  157.44
  4965.2  157.94  4976.6  158.71  4998.8  158.72  5026.1  159.69  5062.7  161.88
  5104.4  162.87  5118.7  164.02  5155.8  165.28  5323.3  168.37  5360.1  168.48
  5365.2  169.01  5392.4  168.49  5407.2   169.2  5433.5  168.84  5515.1  170.05
#Mann= 3 ,-1 , 0
  4537.2      .1       0  4959.2     .07       0  4965.2      .1       0
Bank Sta=4959.2,4965.2
XS Rating Curve= 0 ,0
Exp/Cntr=0.3,0.1

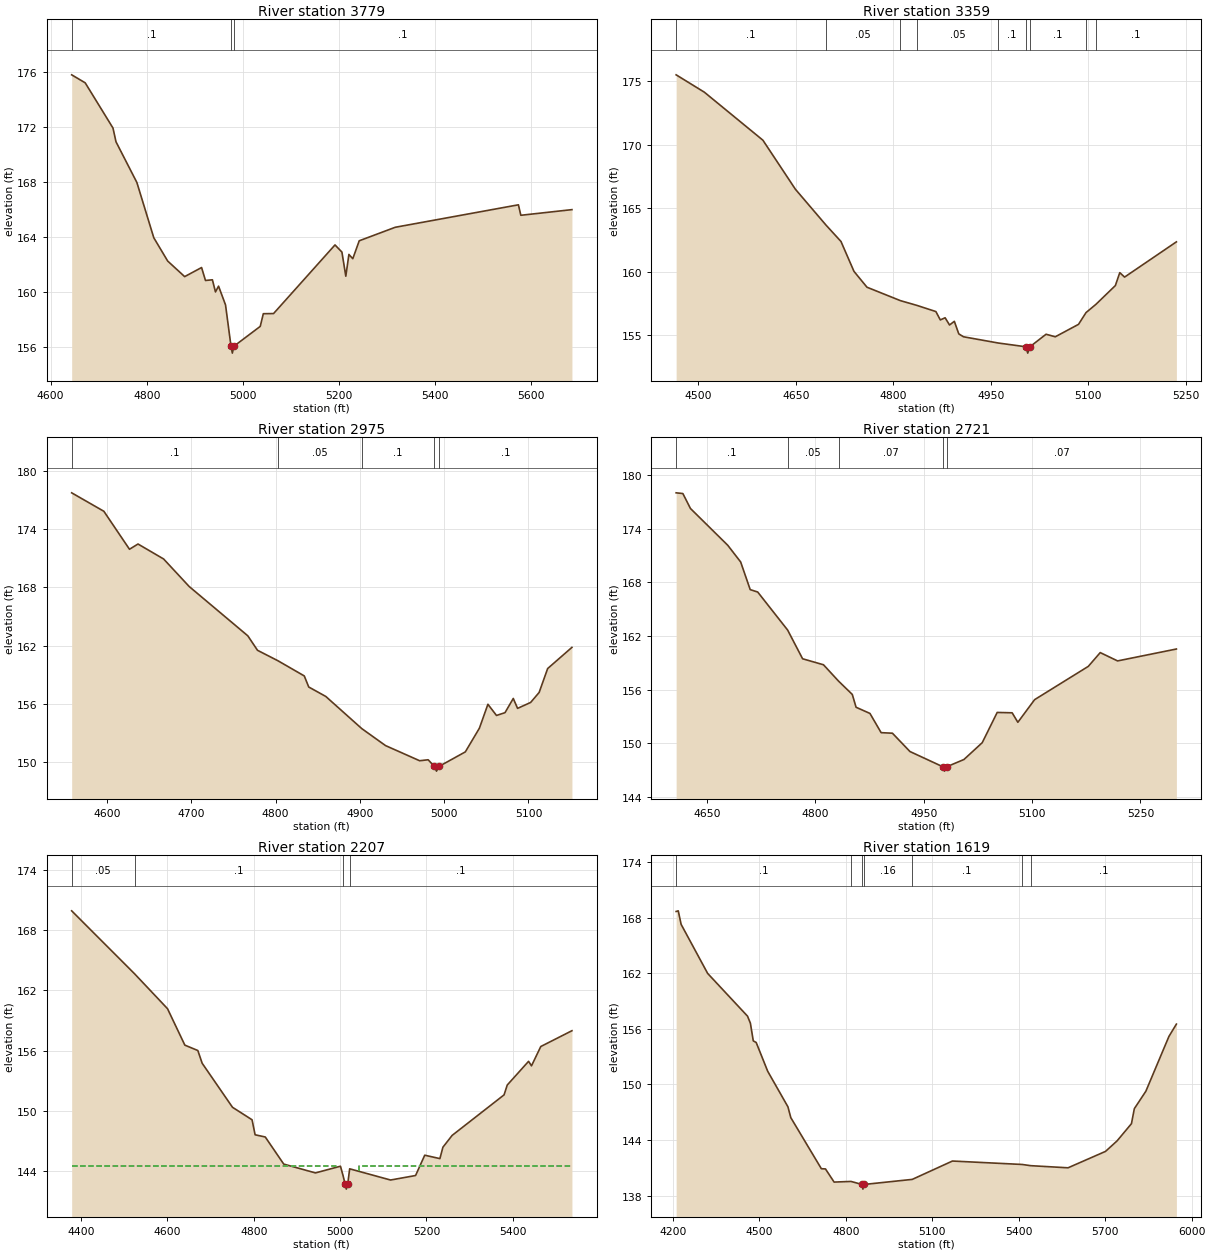
Type RM Length L Ch R = 1 ,3779    ,420,420,420
BEGIN DESCRIPTION:
UNT 070 IN LACR 2.0
END DESCRIPTION:
XS GIS Cut Line= 3
      2287587.74     13224246.88      2287210.64     13223767.56
      2286781.42     13223732.94
#Sta/Elev= 30
  4643.9  175.77    4672  175.19  4729.8  171.91  4736.1  170.91  4779.5  167.96
  4814.7  163.95  4843.6  162.26  4878.9  161.13  4914.1  161.79  4922.2  160.85
  4936.6   160.9    4943  160.02  4949.4  160.44  4963.9  159.08  4975.3  156.08
  4978.1  155.58  4981.3  156.08  5036.1  157.52  5042.5  158.44  5063.8  158.45
  5191.6  163.43    5206  162.91  5214.1  161.16  5220.5  162.74  5228.6  162.43
    5242  163.73  5316.9  164.71  5573.1  166.34  5578.1  165.58  5684.4  165.99
#Mann= 3 ,-1 , 0
  4643.9      .1       0  4975.3     .07       0  4981.3      .1       0
Bank Sta=4975.3,4981.3
XS Rating Curve= 0 ,0
Exp/Cntr=0.3,0.1

Type RM Length L Ch R = 1 ,3359    ,384,384,384
BEGIN DESCRIPTION:
Mapping XS 6769e067
END DESCRIPTION:
XS GIS Cut Line= 3
      2287806.32     13224170.23      2287794.91      13223870.7
       2287450.1     13223551.54
#Sta/Elev= 30
    4466  175.52  4509.4  174.15  4599.5  170.36  4649.5  166.49  4696.6  163.66
  4719.6  162.37  4739.6  160.01  4759.6  158.76  4811.1   157.7  4836.2  157.33
  4865.6  156.84  4872.4  156.18  4879.8  156.35  4886.6  155.78    4894  156.07
  4900.8  155.08  4908.1  154.85  4961.3  154.36  5004.2  154.06  5006.9  153.56
  5010.2  154.06  5035.1  155.05  5049.3  154.85    5085  155.83  5096.6  156.76
  5111.6   157.4  5141.7  158.89  5148.5  159.91  5155.9  159.56  5235.6  162.34
#Mann= 9 ,-1 , 0
    4466      .1       0  4696.6     .05       0  4811.1      .1       0
  4836.2     .05       0  4961.3      .1       0  5004.2     .07       0
  5010.2      .1       0  5096.6     .08       0  5111.6      .1       0
Bank Sta=5004.2,5010.2
XS Rating Curve= 0 ,0
Exp/Cntr=0.3,0.1

Type RM Length L Ch R = 1 ,2975    ,254,254,254
BEGIN DESCRIPTION:
Mapping XS c8871b68
END DESCRIPTION:
XS GIS Cut Line= 2
      2287869.08     13224184.57      2287962.98     13223598.44
#Sta/Elev= 30
    4558  177.72  4596.2  175.82  4626.6  171.91  4636.7  172.45  4667.1  170.91
  4697.5  168.07    4767     163  4778.5  161.51  4802.6  160.44    4834  158.87
  4839.3  157.73  4859.5  156.76  4902.2  153.45  4930.4   151.7  4970.9  150.14
    4981  150.24  4988.2  149.57  4990.9  149.07  4994.2  149.57  5025.1  151.05
  5041.8  153.49  5051.9  155.95  5062.1   154.8  5072.2  155.09    5082  156.55
  5087.1  155.53  5102.6  156.14  5112.7  157.17  5122.8  159.63  5151.6  161.81
#Mann= 5 ,-1 , 0
    4558      .1       0  4802.6     .05       0  4902.2      .1       0
  4988.2     .07       0  4994.2      .1       0
Bank Sta=4988.2,4994.2
XS Rating Curve= 0 ,0
Exp/Cntr=0.3,0.1

Type RM Length L Ch R = 1 ,2721    ,514,514,514
BEGIN DESCRIPTION:
Mapping XS e52fcf8d
END DESCRIPTION:
XS GIS Cut Line= 3
      2288028.86     13224275.82       2288165.8     13223767.99
      2288103.05     13223613.95
#Sta/Elev= 30
  4607.5     178  4616.8  177.92  4627.3  176.25  4678.9  172.14  4696.8  170.27
    4710  167.18  4720.4  166.91  4761.8  162.66  4782.5  159.45  4811.4  158.78
  4832.3  156.95  4851.3  155.46  4856.5  154.03  4875.7  153.34  4891.2  151.19
  4906.8  151.13  4931.1  149.08  4976.3  147.39    4979  146.89  4982.3  147.39
  5005.8  148.19  5031.1  150.07  5051.8  153.45  5072.5  153.41  5080.4  152.35
  5103.6  154.88  5177.9   158.6  5194.4  160.14  5218.4  159.21  5299.8  160.54
#Mann= 5 ,-1 , 0
  4607.5      .1       0  4761.8     .05       0  4832.3     .07       0
  4976.3    .035       0  4982.3     .07       0
Bank Sta=4976.3,4982.3
XS Rating Curve= 0 ,0
Exp/Cntr=0.3,0.1

Type RM Length L Ch R = 1 ,2207    ,588,588,588
BEGIN DESCRIPTION:
Mapping XS 66671951
END DESCRIPTION:
XS GIS Cut Line= 4
      2288645.12     13224618.22      2288616.59     13224210.21
      2288412.26     13223878.34      2288148.69      13223633.9
#Sta/Elev= 30
  4378.6  169.96  4524.4  163.66  4600.5  160.18  4640.6  156.54  4670.7     156
  4680.7  154.73  4750.9  150.33  4796.2  149.08  4803.3  147.58  4826.8  147.36
  4869.6  144.65    4943  143.77  5000.9  144.44  5006.8  143.52  5011.7  142.65
  5014.4  142.15  5017.7  142.65  5022.2  144.18  5116.9  143.06  5174.8  143.51
    5196  145.54  5231.1   145.2  5238.1  146.34  5259.5  147.52  5379.7  151.57
    5387  152.55  5436.4  154.92  5443.2  154.47  5464.7   156.4  5536.8  157.98
#Mann= 4 ,-1 , 0
  4378.6     .05       0  4524.4      .1       0  5006.8     .07       0
  5022.2      .1       0
#XS Ineff= 2 , 0
         4991.03  144.46 5044.09          144.45
Permanent Ineff=
       F       F
Bank Sta=5011.7,5017.7
XS Rating Curve= 0 ,0
Exp/Cntr=0.3,0.1

Type RM Length L Ch R = 1 ,1619    ,439,439,439
BEGIN DESCRIPTION:
Mapping XS 2d9547ad
END DESCRIPTION:
XS GIS Cut Line= 3
      2288907.39     13224634.16      2288956.13     13223664.37
       2288191.8     13223654.63
#Sta/Elev= 30
  4211.7  168.66    4219  168.73    4229  167.27    4321  161.98  4459.3  157.37
  4469.3  156.61  4479.3   154.7  4489.4  154.53  4529.4  151.42  4599.5  147.59
  4609.5  146.42  4715.5  140.91  4729.7  140.89  4759.7  139.47  4818.3  139.54
  4856.8  139.21  4859.6  138.71  4862.8  139.21  5030.8  139.76  5170.2  141.74
    5412  141.37  5441.5  141.24  5571.2  141.01  5701.2  142.78  5741.2  143.91
  5791.2  145.77  5801.2  147.39  5841.2  149.27  5921.2  155.18  5947.1  156.51
#Mann= 7 ,-1 , 0
  4211.7      .1       0  4818.3     .16       0  4856.8     .07       0
  4862.8     .16       0  5030.8      .1       0    5412     .16       0
  5441.5      .1       0
Bank Sta=4856.8,4862.8
XS Rating Curve= 0 ,0
Exp/Cntr=0.3,0.1

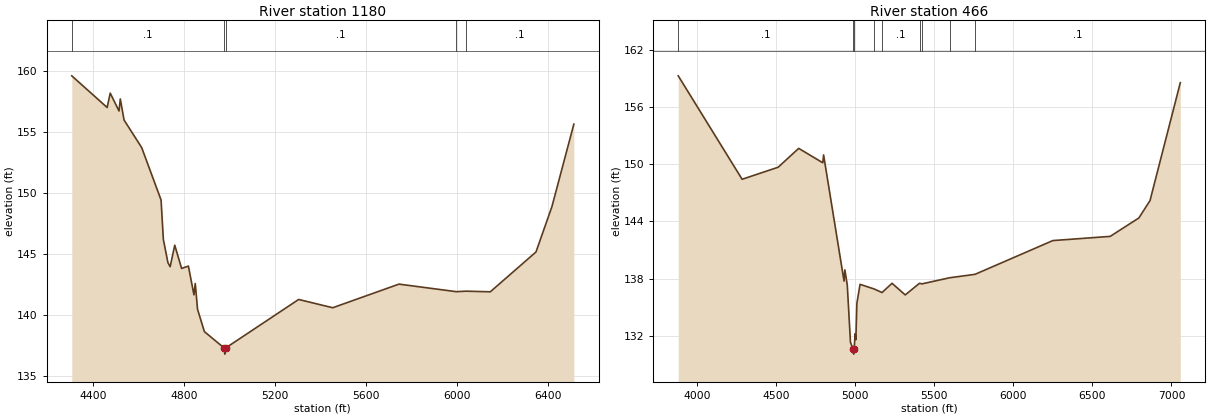
Type RM Length L Ch R = 1 ,1180    ,714,714,714
BEGIN DESCRIPTION:
Mapping XS d8cb3607
END DESCRIPTION:
XS GIS Cut Line= 5
      2289136.47     13224604.91      2289277.78     13224332.04
      2289326.51     13223586.39      2289233.92     13223532.78
      2288191.84      13223625.3
#Sta/Elev= 30
  4306.7  159.63  4462.2  157.03  4475.8  158.21  4514.4  156.74  4520.1  157.73
  4536.6     156    4614  153.74  4699.4  149.43  4709.4   146.2  4729.4  144.29
  4739.4  143.95  4759.5  145.72  4789.6  143.81  4819.6     144  4843.9  141.64
  4849.7  142.57  4859.7  140.46  4889.8  138.62    4977  137.27  4979.7  136.77
    4983  137.27  5304.4  141.26  5454.1  140.58  5745.5  142.52  5997.6   141.9
  6040.6  141.94  6147.1  141.89  6347.9  145.16  6418.1  148.89  6514.4  155.66
#Mann= 5 ,-1 , 0
  4306.7      .1       0    4977     .07       0    4983      .1       0
  5997.6     .16       0  6040.6      .1       0
Bank Sta=4977,4983
XS Rating Curve= 0 ,0
Exp/Cntr=0.3,0.1

Type RM Length L Ch R = 1 ,466     ,0,0,0
BEGIN DESCRIPTION:
UNT 070 IN LACR 1.0
END DESCRIPTION:
XS GIS Cut Line= 4
      2289365.52     13224522.09      2289964.94     13224049.38
      2289867.47     13223386.58      2288137.35     13223591.27
#Sta/Elev= 30
  3880.3  159.26  4284.3  148.41    4512  149.67  4642.3  151.65  4794.6  150.14
  4799.7  150.96    4929  137.73  4934.1  138.91  4949.5  137.31  4969.7  131.31
  4986.9  130.57  4989.6  130.07  4992.9  130.57  4998.8  132.21  5003.8  131.59
  5010.1  135.39  5030.3  137.39  5120.1   136.9  5169.4  136.53  5232.5   137.5
    5316  136.28  5406.3   137.5  5422.4  137.44  5596.7  138.08  5757.5  138.44
  6249.8  141.98  6612.4  142.42  6793.6  144.35  6864.1  146.17  7055.8  158.54
#Mann= 9 ,-1 , 0
  3880.3      .1       0  4986.9     .07       0  4992.9      .1       0
  5120.1     .16       0  5169.4      .1       0  5406.3     .16       0
  5422.4      .1       0  5596.7     .16       0  5757.5      .1       0
Bank Sta=4986.9,4992.9
XS Rating Curve= 0 ,0
Exp/Cntr=0.3,0.1

Chan Stop Cuts=-1
Use User Specified Reach Order=0
Composite Channel Slope=5