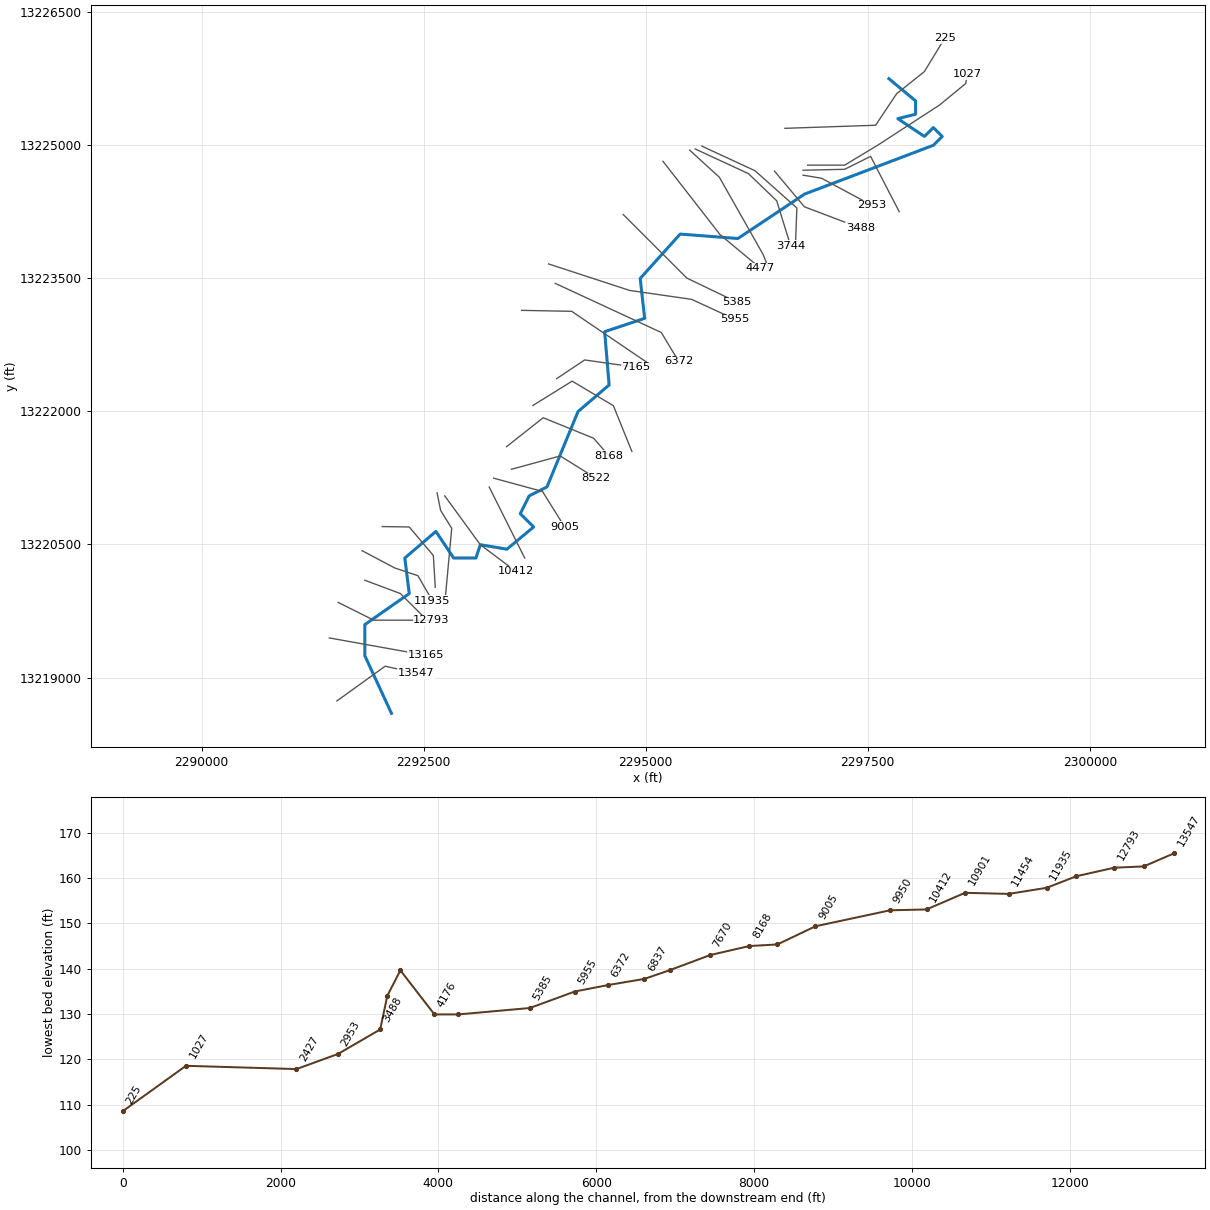
--- UNT 072 IN LACR.prj (project) ---

Proj Title=UNT 072 IN LACR Base Level Engineering
Current Plan=p01
Default Exp/Contr=0.3,0.1
English Units
Geom File=g01
Flow File=f01
Plan File=p01
Y Axis Title=Elevation
X Axis Title(PF)=Main Channel Distance
X Axis Title(XS)=Station
BEGIN DESCRIPTION:
UNT 072 IN LACR
END DESCRIPTION:
DSS Export Rating Curves= 0
DSS Export Rating Curve Sorted= 0
DSS Export Volume Flow Curves= 0
DXF OffsetX= 0
DXF OffsetY= 0
DXF ScaleX= 1
DXF ScaleY= 10

--- UNT 072 IN LACR.p01 (plan) ---

Plan Title=Multiple Run
Short Identifier=Multiple
Geom File=g01
Flow File=f01
Subcritical Flow
K Sum by GR= 0
Std Step Tol= 0.01
Critical Tol= 0.01
Num of Std Step Trials= 20
Max Error Tol= 0.3
Flow Tol Ratio= 0.001
Split Flow NTrial= 30
Split Flow Tol= 0.02
Split Flow Ratio= 0.02
Log Output Level= 0
Friction Slope Method= 1
Unsteady Friction Slope Method= 2
Unsteady Bridges Friction Slope Method= 1
Parabolic Critical Depth
Global Vel Dist=  1 , 1 , 1
Global Log Level= 0
CheckData=True
Encroach Param= -1, 0, 0, 0
BEGIN DESCRIPTION:
Multiple Run
END DESCRIPTION:

--- UNT 072 IN LACR.f01 (steady flow) ---

Flow Title=Multiple
Program Version=4.10
Number of Profiles= 7
Profile Names=10-year,25-year,50-year,1pct_min,100-year,1pct_plu,500-year
River Rch & RM=UNT 072 IN LACR,Reach-1         ,13547
     431     597     734     660     893    1208    1330
River Rch & RM=UNT 072 IN LACR,Reach-1         ,5955
     611     861    1070     971    1313    1775    1990
River Rch & RM=UNT 072 IN LACR,Reach-1         ,3488
     759    1082    1354    1237    1673    2262    2570
River Rch & RM=UNT 072 IN LACR,Reach-1         ,2953
     892    1283    1615    1483    2005    2712    3112
Boundary for River Rch & Prof#=UNT 072 IN LACR,Reach-1         , 1
Up Type= 0
Dn Type= 3
Dn Slope=0.01
Boundary for River Rch & Prof#=UNT 072 IN LACR,Reach-1         , 2
Up Type= 0
Dn Type= 3
Dn Slope=0.01
Boundary for River Rch & Prof#=UNT 072 IN LACR,Reach-1         , 3
Up Type= 0
Dn Type= 3
Dn Slope=0.01
Boundary for River Rch & Prof#=UNT 072 IN LACR,Reach-1         , 4
Up Type= 0
Dn Type= 3
Dn Slope=0.01
Boundary for River Rch & Prof#=UNT 072 IN LACR,Reach-1         , 5
Up Type= 0
Dn Type= 3
Dn Slope=0.01
Boundary for River Rch & Prof#=UNT 072 IN LACR,Reach-1         , 6
Up Type= 0
Dn Type= 3
Dn Slope=0.01
Boundary for River Rch & Prof#=UNT 072 IN LACR,Reach-1         , 7
Up Type= 0
Dn Type= 3
Dn Slope=0.01
DSS Import GetInterval= 0
DSS Import GetPeak= 0
DSS Import FillOption= 0

--- UNT 072 IN LACR.g01 (geometry) ---

Geom Title=Existing Conditions
Program Version=4.10

River Reach=UNT 072 IN LACR ,Reach-1
Reach XY= 30
      2292137.72     13218596.85      2291837.72     13219246.85
      2291837.72     13219596.85      2292337.72     13219946.85
      2292287.72     13220346.86      2292637.72     13220646.85
      2292837.72     13220346.86      2293087.72     13220346.86
      2293137.72     13220496.85      2293437.72     13220446.85
      2293737.72     13220696.86      2293587.72     13220846.86
      2293687.72     13221046.85      2293887.72     13221146.85
      2294237.72     13221996.86      2294587.72     13222296.85
      2294537.72     13222896.85      2294987.72     13223046.85
      2294937.72     13223496.86      2295387.72     13223996.86
      2296037.72     13223946.85      2296787.72     13224446.85
      2298237.72     13224996.85      2298337.72     13225096.85
      2298237.72     13225196.85      2298137.72     13225096.85
      2297837.72     13225296.86      2298037.72     13225346.85
      2298037.72     13225496.85      2297737.72     13225746.85

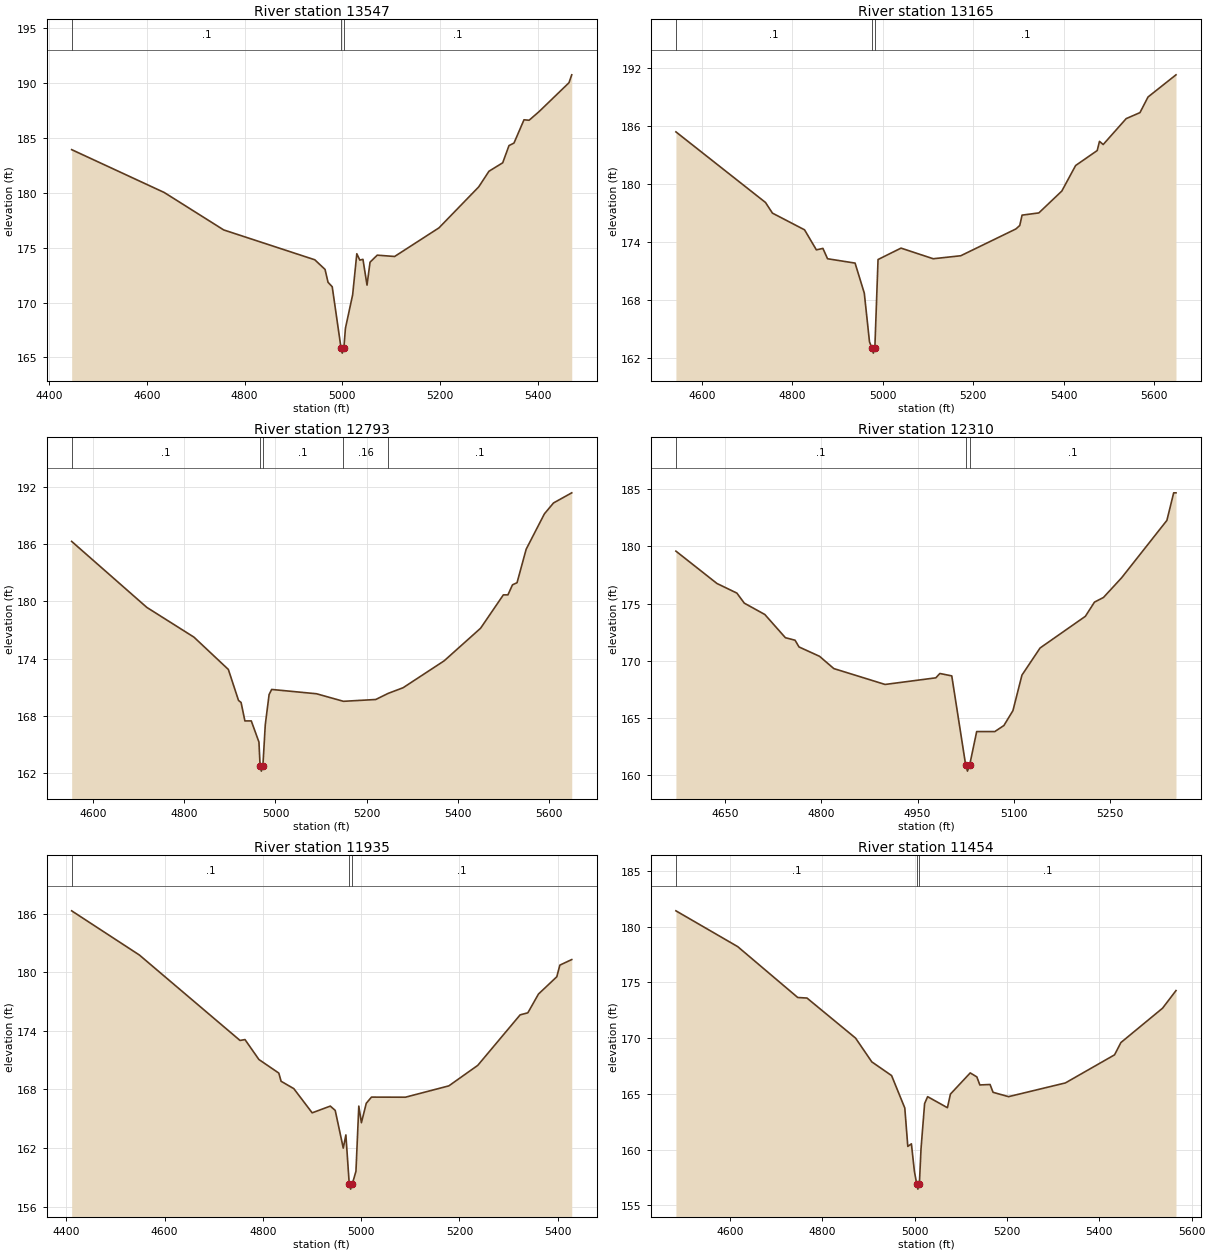
Type RM Length L Ch R = 1 ,13547   ,382,382,382
BEGIN DESCRIPTION:
UNT 072 IN LACR 19.0
END DESCRIPTION:
XS GIS Cut Line= 3
      2291523.89     13218737.39      2292066.46     13219128.03
      2292413.19     13219052.18
#Sta/Elev= 30
    4446  183.94  4635.6  180.03  4757.2  176.62  4943.6   173.9  4964.6  173.02
  4970.7  171.85  4979.3  171.44  4997.2  165.89  4999.9  165.39  5003.2  165.89
  5006.3  167.65  5021.1  170.71  5029.6  174.45  5035.8  173.87  5042.2  173.94
  5050.5  171.59  5056.7  173.68  5071.4  174.32    5107   174.2  5197.8  176.81
  5279.2  180.55  5300.1  181.97  5328.2  182.74  5341.1  184.31  5351.3  184.54
  5371.8  186.66  5382.3  186.62  5402.5   187.4  5463.9  190.04  5469.5  190.76
#Mann= 3 ,-1 , 0
    4446      .1       0  4997.2     .07       0  5003.2      .1       0
Bank Sta=4997.2,5003.2
XS Rating Curve= 0 ,0
Exp/Cntr=0.3,0.1

Type RM Length L Ch R = 1 ,13165   ,372,372,372
BEGIN DESCRIPTION:
UNT 072 IN LACR 18.0
END DESCRIPTION:
XS GIS Cut Line= 2
      2291437.72     13219446.86      2292526.21     13219251.42
#Sta/Elev= 30
  4542.8   185.4  4740.9   178.1  4756.2     177  4827.3  175.27  4853.4   173.2
  4867.9  173.35  4878.1  172.28    4939  171.83  4959.4  168.72  4970.9  163.68
  4976.7  163.02  4979.4  162.52  4982.7  163.02  4989.8   172.2  5040.6  173.38
  5111.8  172.28  5172.7  172.59  5294.6  175.36  5303.2  175.72  5308.3  176.79
  5345.4  177.02  5396.2  179.28  5426.7  181.92  5474.5  183.47  5479.5  184.42
  5487.7  184.09  5538.5  186.77    5569  187.39  5586.9  189.01  5648.7   191.3
#Mann= 3 ,-1 , 0
  4542.8      .1       0  4976.7     .07       0  4982.7      .1       0
Bank Sta=4976.7,4982.7
XS Rating Curve= 0 ,0
Exp/Cntr=0.3,0.1

Type RM Length L Ch R = 1 ,12793   ,483,483,483
BEGIN DESCRIPTION:
UNT 072 IN LACR 17.0
END DESCRIPTION:
XS GIS Cut Line= 3
      2291537.73     13219846.85      2291937.72     13219646.85
      2292587.72     13219646.85
#Sta/Elev= 30
  4552.8  186.26  4717.7  179.36  4821.1  176.25  4896.6  172.87  4918.9  169.63
  4924.5  169.42  4932.9  167.49  4946.9  167.49  4963.7  165.28  4966.3  162.74
    4969  162.24  4972.3  162.74  4977.6  167.09    4986  170.25  4991.6  170.78
    5090  170.33  5149.1  169.54    5220  169.73  5247.3  170.37    5280  170.96
    5370  173.77    5450  177.18    5500  180.67    5510  180.67    5520  181.72
    5530  181.94    5550  185.44    5590  189.14    5610  190.28    5650  191.34
#Mann= 5 ,-1 , 0
  4552.8      .1       0  4966.3     .07       0  4972.3      .1       0
  5149.1     .16       0  5247.3      .1       0
Bank Sta=4966.3,4972.3
XS Rating Curve= 0 ,0
Exp/Cntr=0.3,0.1

Type RM Length L Ch R = 1 ,12310   ,375,375,375
BEGIN DESCRIPTION:
UNT 072 IN LACR 16.0
END DESCRIPTION:
XS GIS Cut Line= 3
      2291837.72     13220096.85      2292237.72     13219946.85
      2292487.75     13219696.82
#Sta/Elev= 30
  4572.8  179.59  4636.9  176.76    4668  175.92  4679.6  175.04  4711.6  174.05
  4743.7  172.02  4758.8   171.8    4765  171.21  4797.1  170.39  4819.3  169.32
  4899.4  167.93  4978.6  168.51  4984.9  168.89  5003.5  168.68  5025.3  160.85
    5028  160.35  5031.3  160.85  5042.4  163.81  5070.7  163.81  5084.9  164.34
    5099  165.64  5113.1  168.75  5141.4  171.12  5212.1  173.89  5226.3  175.13
  5240.4  175.54  5268.7  177.26  5339.4  182.28    5350  184.69  5353.6  184.69
#Mann= 3 ,-1 , 0
  4572.8      .1       0  5025.3     .07       0  5031.3      .1       0
Bank Sta=5025.3,5031.3
XS Rating Curve= 0 ,0
Exp/Cntr=0.3,0.1

Type RM Length L Ch R = 1 ,11935   ,481,481,481
BEGIN DESCRIPTION:
Mapping XS db7f1d96
END DESCRIPTION:
XS GIS Cut Line= 4
      2291806.04     13220430.12      2292174.96      13220234.8
      2292435.38       13220148.      2292598.12     13219865.92
#Sta/Elev= 30
    4411  186.29  4548.7  181.77  4753.6  173.02  4763.7  173.11    4792  171.07
  4832.5  169.68  4837.2  168.84    4863  168.09  4900.4  165.61  4937.3   166.3
  4947.3  165.86  4963.7     162    4969  163.35  4975.9   158.3  4978.7   157.8
  4981.9   158.3  4989.5  159.63  4995.3   166.3  5000.6   164.6  5010.5  166.59
  5021.1  167.22  5090.2  167.21  5178.5  168.37  5237.4  170.47  5323.6  175.64
  5339.3  175.85  5360.9  177.77  5398.2  179.54  5404.4  180.73  5428.6   181.3
#Mann= 3 ,-1 , 0
    4411      .1       0  4975.9     .07       0  4981.9      .1       0
Bank Sta=4975.9,4981.9
XS Rating Curve= 0 ,0
Exp/Cntr=0.3,0.1

Type RM Length L Ch R = 1 ,11454   ,553,553,553
BEGIN DESCRIPTION:
UNT 072 IN LACR 15.0
END DESCRIPTION:
XS GIS Cut Line= 4
      2292033.93     13220701.38      2292337.72     13220696.85
      2292608.99     13220375.86      2292630.69     13220017.81
#Sta/Elev= 30
  4483.3  181.41  4617.1   178.2  4747.1  173.64  4767.1  173.59  4872.3     170
  4907.4  167.87  4950.3  166.64  4978.9  163.73  4985.4  160.29  4993.2  160.52
  4999.7  158.05  5004.5  156.96  5007.2  156.46  5010.5  156.96    5014  160.07
  5021.8  164.13  5028.3  164.75  5071.2  163.76  5077.7  164.98  5120.6  166.88
  5134.9  166.52  5141.4   165.8  5163.5  165.84    5170  165.14  5203.5  164.75
  5326.6  165.98  5433.1   168.5  5446.8   169.6    5537  172.68  5566.1  174.26
#Mann= 3 ,-1 , 0
  4483.3      .1       0  5004.5     .07       0  5010.5      .1       0
Bank Sta=5004.5,5010.5
XS Rating Curve= 0 ,0
Exp/Cntr=0.3,0.1

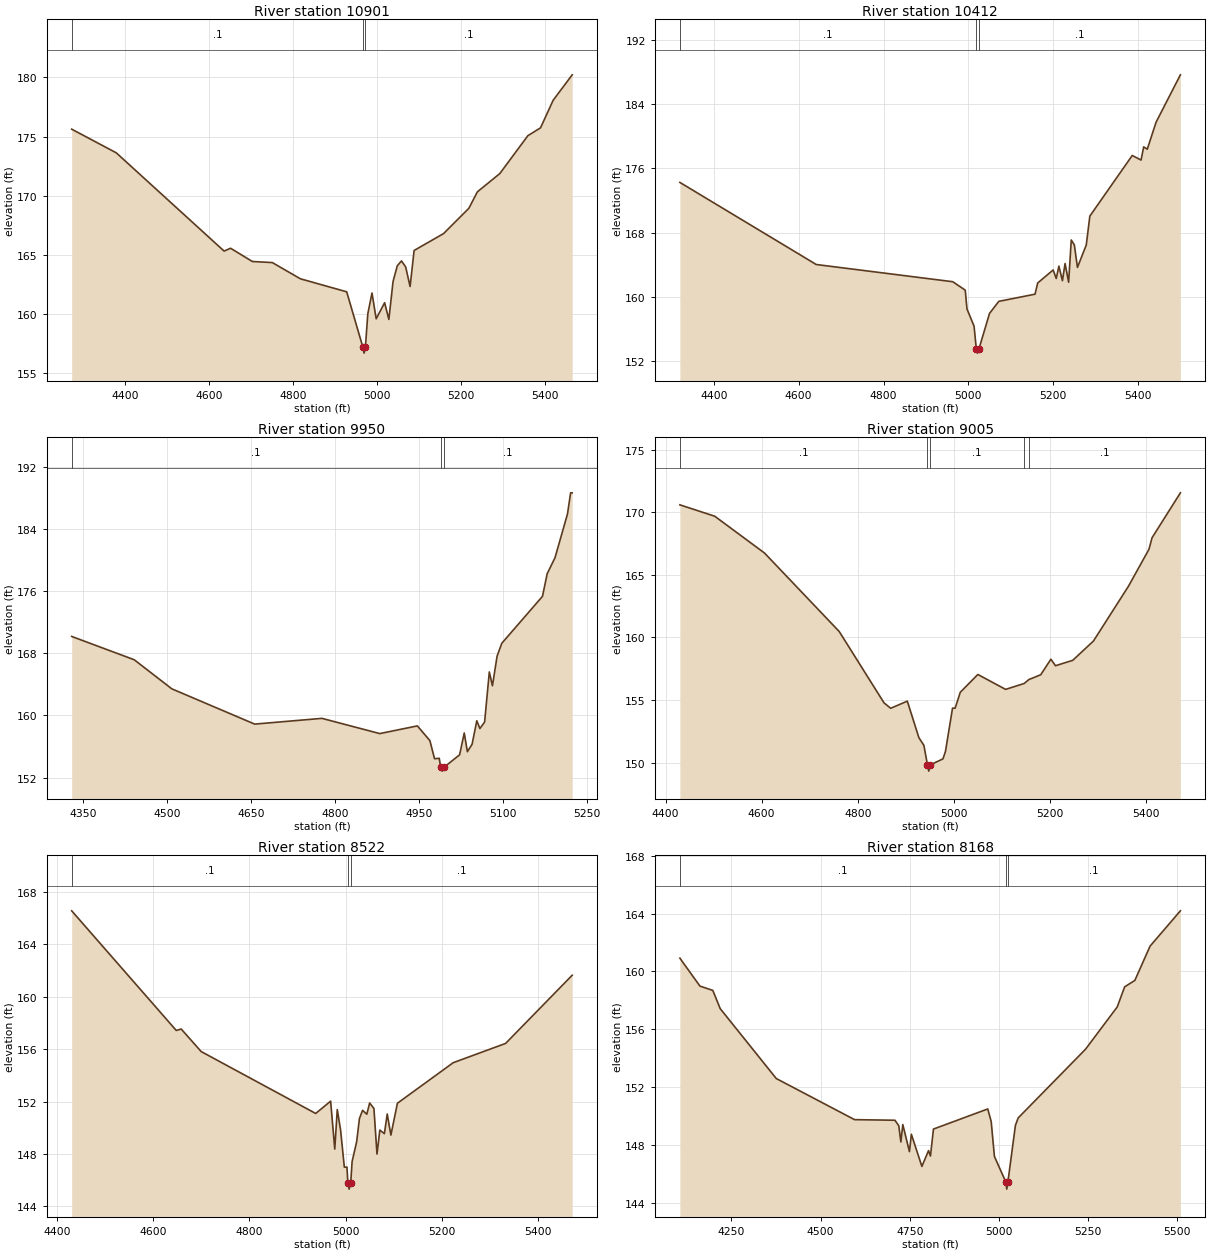
Type RM Length L Ch R = 1 ,10901   ,489,489,489
BEGIN DESCRIPTION:
UNT 072 IN LACR 14.0
END DESCRIPTION:
XS GIS Cut Line= 4
      2292650.73     13221081.79       2292691.1     13220882.94
       2292816.1     13220681.55      2292746.66     13219931.69
#Sta/Elev= 30
  4272.3  175.62  4378.6  173.62  4635.6  165.32    4651  165.56    4703  164.44
  4750.5  164.35  4817.4  162.98  4927.8  161.88  4966.4   157.2  4969.2   156.7
  4972.4   157.2  4978.1  160.01  4988.1  161.78  4998.1   159.6  5018.2  160.96
  5028.3  159.55  5038.3  162.75  5048.4  164.08  5058.4  164.49  5068.4  163.98
  5078.9  162.33  5088.5  165.37  5158.8   166.8  5219.1  168.94  5239.2  170.32
  5292.8  171.87  5359.7  175.07  5389.8  175.73  5419.9  178.06  5465.3  180.21
#Mann= 3 ,-1 , 0
  4272.3      .1       0  4966.4     .07       0  4972.4      .1       0
Bank Sta=4966.4,4972.4
XS Rating Curve= 0 ,0
Exp/Cntr=0.3,0.1

Type RM Length L Ch R = 1 ,10412   ,462,462,462
BEGIN DESCRIPTION:
UNT 072 IN LACR 13.0
END DESCRIPTION:
XS GIS Cut Line= 3
       2292737.7     13221046.88      2293137.72     13220496.85
      2293537.72     13220196.85
#Sta/Elev= 30
  4319.9  174.26  4641.4  164.05  4963.3  161.91  4992.7  160.86  4996.9  158.51
  5013.5  156.39  5018.9  153.53  5021.6  153.03  5024.9  153.53    5050  157.97
  5071.9  159.47  5157.3  160.36  5163.5  161.75    5200  163.37  5207.3  162.31
  5213.5  163.85  5221.9  162.04  5228.1  164.17  5236.5  161.85  5242.7   167.1
    5250  166.48  5257.3  163.69  5278.1  166.48  5286.5  170.07  5386.5  177.61
  5407.3  177.04  5413.5  178.68  5421.9  178.39  5442.7  181.75    5500  187.64
#Mann= 3 ,-1 , 0
  4319.9      .1       0  5018.9     .07       0  5024.9      .1       0
Bank Sta=5018.9,5024.9
XS Rating Curve= 0 ,0
Exp/Cntr=0.3,0.1

Type RM Length L Ch R = 1 ,9950    ,945,945,945
BEGIN DESCRIPTION:
UNT 072 IN LACR 12.0
END DESCRIPTION:
XS GIS Cut Line= 3
      2293237.73     13221146.84      2293537.72     13220546.86
      2293637.72     13220346.86
#Sta/Elev= 30
  4329.2  170.17    4441  167.17  4508.1  163.43  4656.2  158.89  4776.4  159.63
  4879.8  157.67  4946.9  158.66  4969.3  156.77  4977.6  154.44    4986  154.49
  4988.6  153.34  4991.4  152.84  4994.6  153.34  5022.4  154.94  5030.7  157.75
  5036.3  155.34  5044.7   156.3  5053.1  159.32  5058.7  158.32  5067.1  159.16
  5075.5   165.6  5081.1  163.83  5089.4  167.64  5097.8  169.29  5170.5  175.33
  5178.9  178.24  5192.9   180.3  5215.2  185.93  5220.8  188.65  5223.6  188.65
#Mann= 3 ,-1 , 0
  4329.2      .1       0  4988.6     .07       0  4994.6      .1       0
Bank Sta=4988.6,4994.6
XS Rating Curve= 0 ,0
Exp/Cntr=0.3,0.1

Type RM Length L Ch R = 1 ,9005    ,483,483,483
BEGIN DESCRIPTION:
UNT 072 IN LACR 11.0
END DESCRIPTION:
XS GIS Cut Line= 3
      2293287.71     13221246.86      2293837.72     13221096.85
      2294087.72     13220696.85
#Sta/Elev= 30
  4429.9  170.59  4502.5  169.68  4606.1  166.74  4761.6  160.47  4854.9  154.77
  4868.7  154.34  4903.3  154.91  4927.4  151.99  4937.8  151.38  4945.2  149.82
  4947.9  149.32  4951.2  149.82  4977.5   150.3  4982.7  150.89  4997.4  154.35
  5002.9  154.35  5013.6  155.62  5050.1  157.04  5107.9  155.85  5146.5  156.32
  5156.2  156.63    5181  157.02  5202.2  158.26  5211.7  157.74  5247.6  158.17
  5290.7  159.71  5363.8   164.1  5406.3  167.04  5412.7  167.96  5471.7  171.55
#Mann= 5 ,-1 , 0
  4429.9      .1       0  4945.2     .07       0  4951.2      .1       0
  5146.5     .16       0  5156.2      .1       0
Bank Sta=4945.2,4951.2
XS Rating Curve= 0 ,0
Exp/Cntr=0.3,0.1

Type RM Length L Ch R = 1 ,8522    ,354,354,354
BEGIN DESCRIPTION:
UNT 072 IN LACR 10.0
END DESCRIPTION:
XS GIS Cut Line= 3
      2293487.71     13221346.85      2294037.72     13221496.86
      2294437.72     13221246.85
#Sta/Elev= 30
  4429.9  166.57  4647.6  157.43  4657.9  157.54  4699.4  155.82  4937.8  151.09
  4968.9  152.03  4977.5  148.37  4982.7  151.39  4989.6  149.83  4997.4  146.99
  5002.9  146.99  5004.7  145.81  5007.4  145.31  5010.7  145.81  5013.6  147.42
    5023  148.92  5028.9  150.71  5035.4  151.33  5044.2  151.03  5050.1  151.89
    5059  151.47  5065.4  147.99  5071.3  149.82  5080.8  149.55  5086.7  151.05
  5094.3  149.44  5107.9  151.87  5224.1  154.97  5333.1  156.44  5471.7  161.65
#Mann= 3 ,-1 , 0
  4429.9      .1       0  5004.7     .07       0  5010.7      .1       0
Bank Sta=5004.7,5010.7
XS Rating Curve= 0 ,0
Exp/Cntr=0.3,0.1

Type RM Length L Ch R = 1 ,8168    ,498,498,498
BEGIN DESCRIPTION:
UNT 072 IN LACR 9.0
END DESCRIPTION:
XS GIS Cut Line= 4
      2293433.65     13221601.99      2293845.97     13221927.51
      2294412.72     13221696.85      2294587.74     13221496.84
#Sta/Elev= 30
  4105.7  160.92  4161.9  158.99    4198  158.69  4218.8  157.43    4376   152.6
  4595.5  149.76  4708.5  149.72  4719.3  149.34  4725.2  148.22  4730.6  149.42
  4749.2  147.55  4754.6  148.75  4784.1  146.53  4802.7  147.62  4808.1  147.25
  4816.5  149.11  4968.7   150.5  4978.4  149.63  4987.4  147.22  5019.2  145.46
    5022  144.96  5025.2  145.46  5046.3  149.37    5054  149.88  5242.9  154.63
  5331.7  157.55  5352.5  158.94    5381  159.38  5423.7  161.75  5508.7  164.19
#Mann= 3 ,-1 , 0
  4105.7      .1       0  5019.2     .07       0  5025.2      .1       0
Bank Sta=5019.2,5025.2
XS Rating Curve= 0 ,0
Exp/Cntr=0.3,0.1

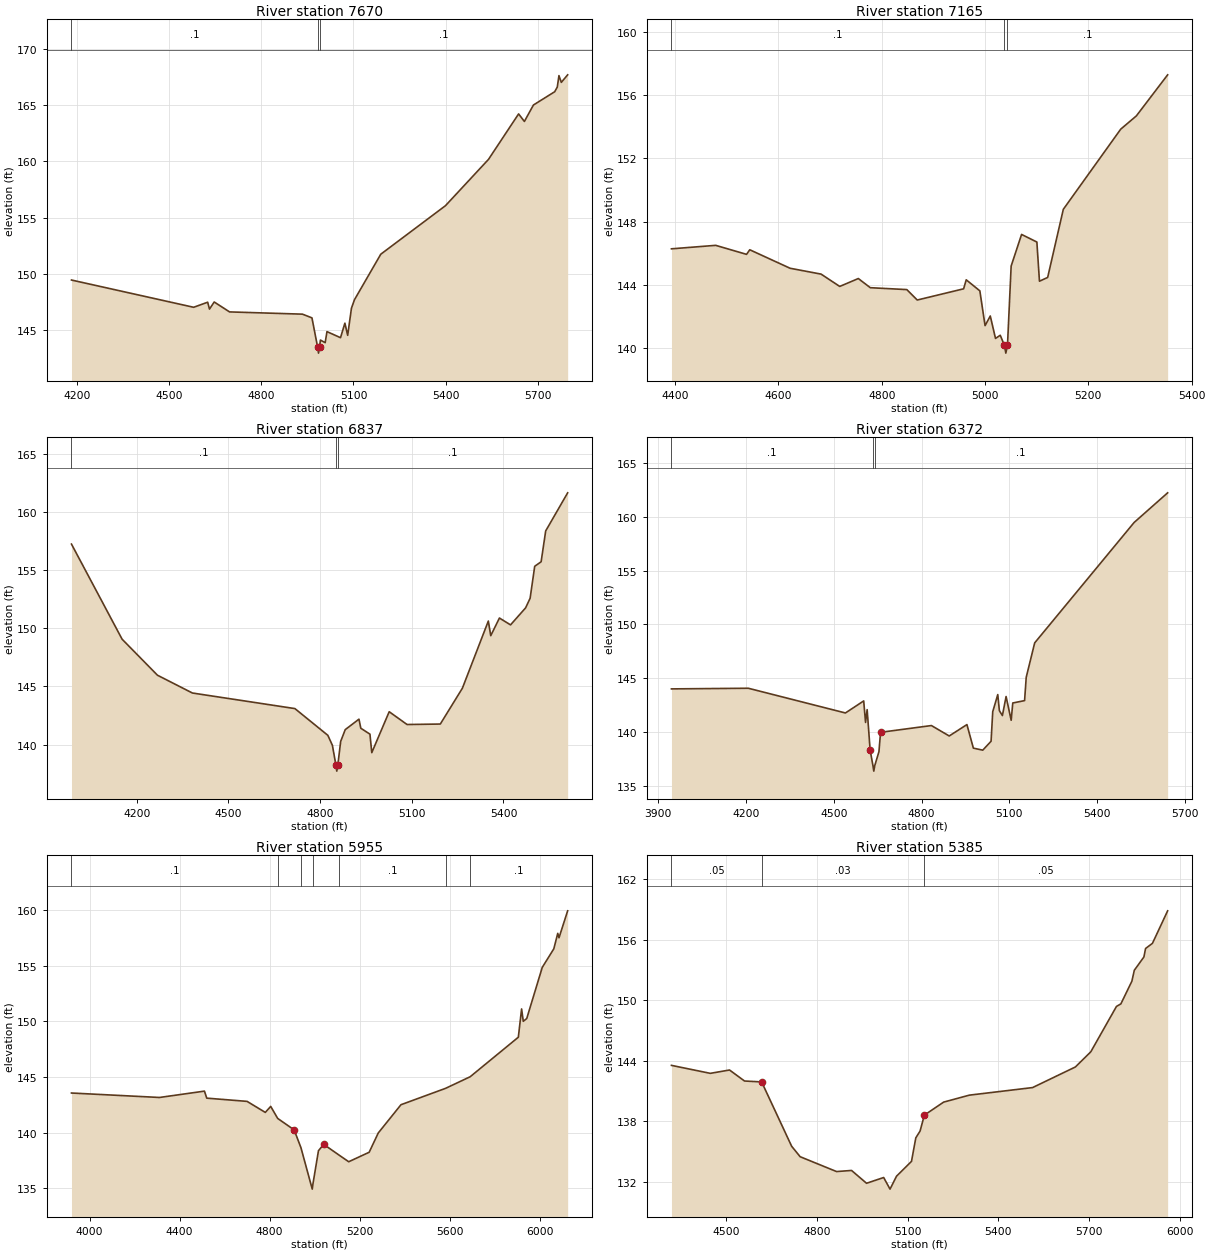
Type RM Length L Ch R = 1 ,7670    ,505,505,505
BEGIN DESCRIPTION:
UNT 072 IN LACR 8.0
END DESCRIPTION:
XS GIS Cut Line= 4
      2293729.49     13222065.36      2294171.49     13222339.84
      2294635.54     13222063.49      2294844.25     13221547.71
#Sta/Elev= 30
  4181.2  149.46  4579.3  147.04    4625  147.49  4630.9  146.88  4646.3  147.51
  4696.3  146.63  4933.9  146.43  4964.8   146.1  4983.5  143.47  4986.2  142.97
  4989.5  143.47  4992.3  144.13  5007.9   143.9  5013.7  144.88  5057.9  144.34
  5072.1  145.63  5081.2  144.55  5093.5  146.96  5103.3  147.71    5189  151.75
  5399.8  156.06    5540  160.17  5638.2  164.21    5657  163.54  5686.5     165
  5755.8  166.18  5764.2  166.59  5769.6  167.61  5777.3  167.01    5798  167.68
#Mann= 3 ,-1 , 0
  4181.2      .1       0  4983.5     .07       0  4989.5      .1       0
Bank Sta=4983.5,4989.5
XS Rating Curve= 0 ,0
Exp/Cntr=0.3,0.1

Type RM Length L Ch R = 1 ,7165    ,328,328,328
BEGIN DESCRIPTION:
UNT 072 IN LACR 7.0
END DESCRIPTION:
XS GIS Cut Line= 3
      2293996.86     13222367.45      2294312.55     13222578.55
      2294887.71     13222496.86
#Sta/Elev= 30
  4392.8  146.28  4478.4   146.5  4538.2  145.93  4544.4  146.22  4622.5  145.05
  4682.5  144.68  4718.6   143.9  4754.6   144.4  4777.8  143.82  4848.5   143.7
  4868.7  143.04  4958.5  143.75  4963.5  144.32  4989.9  143.62    5000  141.42
  5010.1  142.03  5020.2  140.61  5029.4  140.81  5037.4  140.18  5040.2  139.68
  5043.4  140.18  5050.5  145.19  5070.7  147.19  5100.3  146.71  5105.3  144.23
  5121.2  144.47  5151.5  148.78  5262.6  153.85  5292.9  154.69  5353.5  157.29
#Mann= 3 ,-1 , 0
  4392.8      .1       0  5037.4     .07       0  5043.4      .1       0
Bank Sta=5037.4,5043.4
XS Rating Curve= 0 ,0
Exp/Cntr=0.3,0.1

Type RM Length L Ch R = 1 ,6837    ,465,465,465
BEGIN DESCRIPTION:
UNT 072 IN LACR 6.0
END DESCRIPTION:
XS GIS Cut Line= 3
      2293602.14     13223137.28      2294166.36     13223126.43
      2295042.38      13222531.6
#Sta/Elev= 30
  3986.8  157.24  4152.4  149.06  4268.1  145.96  4382.4  144.43  4717.7  143.09
  4825.5  140.79  4840.4  139.93    4852  138.21  4854.7  137.71    4858  138.21
  4867.5  140.27  4882.4  141.28  4927.3  142.18  4933.3   141.4  4963.2  140.89
  4969.2   139.3  5026.2  142.82  5084.6  141.72  5193.4  141.76  5265.6  144.84
  5350.5  150.62  5358.4  149.36  5386.8  150.88  5423.1  150.29  5472.3  151.75
  5487.2  152.58  5502.2  155.33  5523.2  155.72  5538.1  158.37    5610  161.65
#Mann= 3 ,-1 , 0
  3986.8      .1       0    4852     .07       0    4858      .1       0
Bank Sta=4852,4858
XS Rating Curve= 0 ,0
Exp/Cntr=0.3,0.1

Type RM Length L Ch R = 1 ,6372    ,417,417,417
BEGIN DESCRIPTION:
UNT 072 IN LACR 5.0
END DESCRIPTION:
XS GIS Cut Line= 3
      2293981.87      13223441.1      2295175.47     13222887.71
       2295370.8     13222562.16
#Sta/Elev= 30
  3945.6  143.99  4208.2  144.05    4540  141.75  4602.4  142.87  4608.7  140.87
  4614.2  142.06  4624.4   138.3  4634.1  136.84  4636.9  136.34  4640.1  136.84
  4654.5  138.15    4660  139.95  4833.8  140.58  4894.6  139.61  4955.1  140.67
  4977.1  138.48  5009.2  138.29  5037.6  139.12  5043.3  141.87  5060.5  143.46
    5066  141.96  5076.3  141.51  5088.9  143.28  5106.3  141.07  5111.8  142.68
  5152.1   142.9  5157.7  145.07  5186.6  148.27  5526.3  159.47  5640.9  162.23
#Mann= 3 ,-1 , 0
  3945.6      .1       0  4634.1     .07       0  4640.1      .1       0
Bank Sta=4624.4,4660
XS Rating Curve= 0 ,0
Exp/Cntr=0.3,0.1

Type RM Length L Ch R = 1 ,5955    ,570,570,570
BEGIN DESCRIPTION:
UNT 072 IN LACR 4.0
END DESCRIPTION:
XS GIS Cut Line= 4
      2293906.13     13223660.31      2294819.32      13223361.7
      2295517.23       13223261.       2296006.8     13223035.32
#Sta/Elev= 30
  3919.6  143.56  4310.6  143.16  4510.5  143.73  4520.8   143.1  4699.8  142.81
    4781  141.82    4805  142.36  4835.9  141.28  4909.1  140.25  4939.4  138.65
  4989.6  134.93  4992.9  135.43  5017.2  138.38  5040.4  138.95  5109.9  137.97
  5151.6  137.39  5242.5  138.24  5282.9  139.97  5383.9  142.51  5582.1  143.98
  5691.3  145.02  5905.4  148.57  5919.9  151.11  5927.4     150  5942.8  150.25
  6011.7  154.84  6063.1  156.51  6080.6   157.9  6086.1   157.5  6124.6  159.92
#Mann= 7 ,-1 , 0
  3919.6      .1       0  4835.9     .05       0  4939.4    .035       0
  4992.9     .05       0  5109.9      .1       0  5582.1     .05       0
  5691.3      .1       0
Bank Sta=4909.1,5040.4
XS Rating Curve= 0 ,0
Exp/Cntr=0.3,0.1

Type RM Length L Ch R = 1 ,5385    ,908,908,908
BEGIN DESCRIPTION:
UNT 072 IN LACR 3.0
END DESCRIPTION:
XS GIS Cut Line= 3
      2294746.61     13224216.98      2295462.72     13223500.86
      2296026.96      13223229.6
#Sta/Elev= 30
  4320.3  143.55  4448.5  142.76  4512.1  143.09  4561.6     142  4618.2  141.91
  4717.2  135.54  4745.4   134.5  4865.6  133.03  4915.1  133.14  4964.6  131.87
  5021.2  132.44  5042.2  131.29  5063.6  132.57  5113.1  134.04  5127.3  136.37
  5141.4  137.04  5155.6  138.62  5219.2  139.91  5304.1   140.6    5513  141.35
  5654.3  143.39  5705.2  144.89  5790.1  149.39  5804.6  149.64    5841  151.89
    5849  152.97  5880.7  154.29  5886.2  155.13  5908.9  155.64  5959.1  158.86
#Mann= 3 , 0 , 0
  4320.3     .05       0  4618.2     .03       0  5155.6     .05       0
Bank Sta=4618.2,5155.6
XS Rating Curve= 0 ,0
Exp/Cntr=0.3,0.1

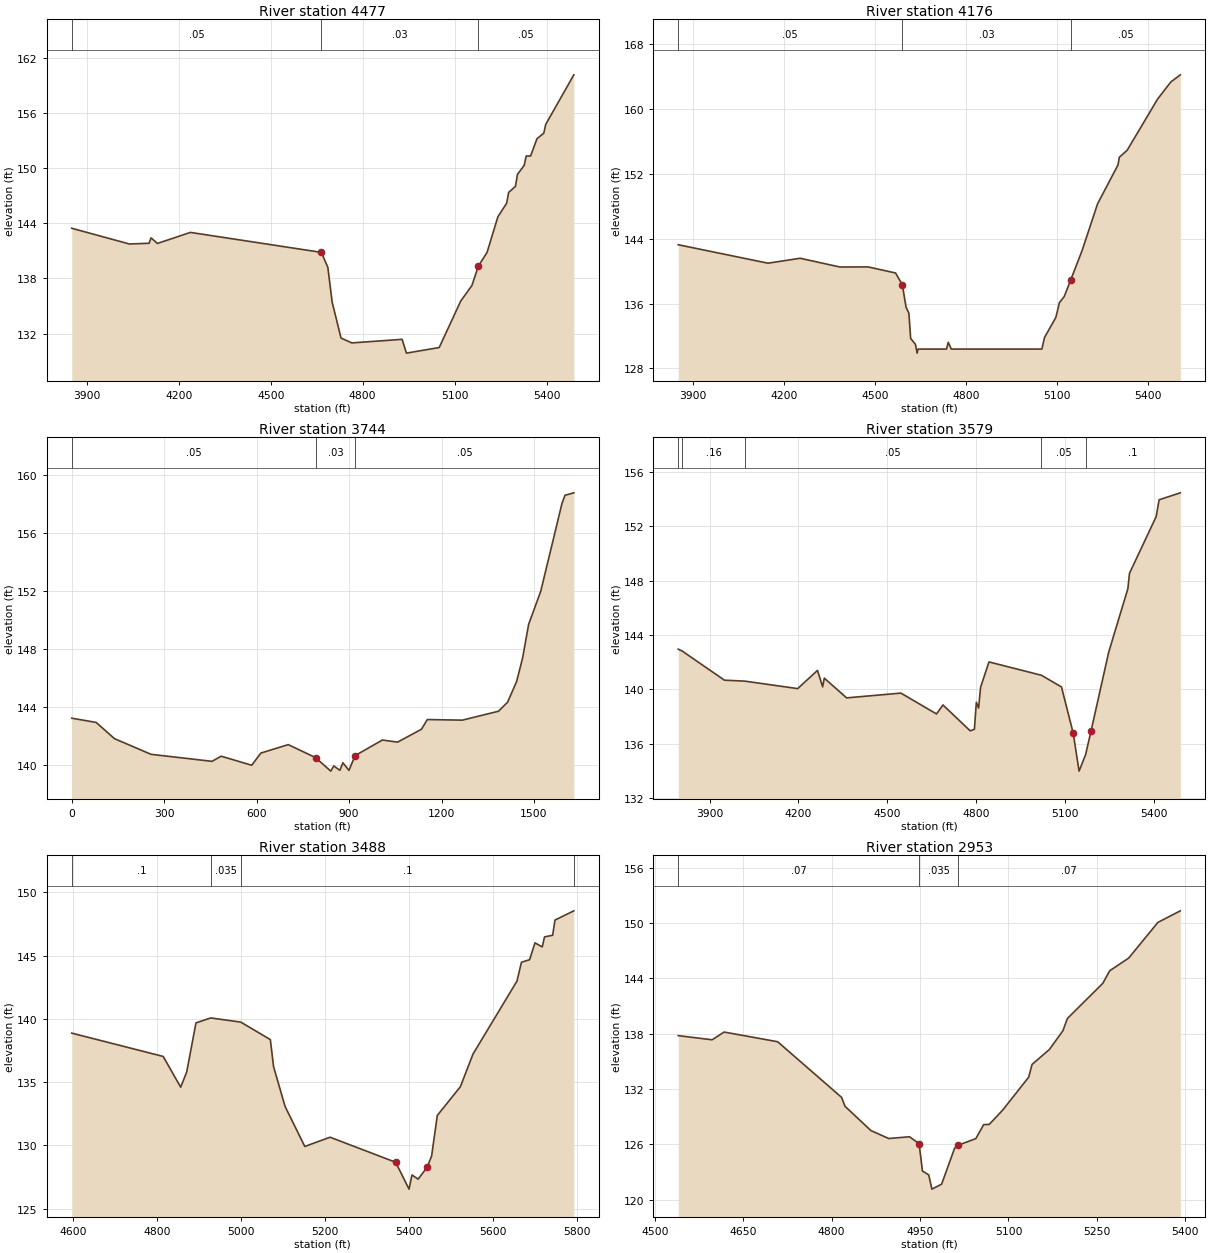
Type RM Length L Ch R = 1 ,4477    ,301,301,301
BEGIN DESCRIPTION:
UNT 072 IN LACR 2.0
END DESCRIPTION:
XS GIS Cut Line= 3
      2295194.31     13224816.57      2295836.68     13223990.17
      2296291.45     13223611.78
#Sta/Elev= 30
  3850.8  143.45  4038.9  141.74  4103.2  141.82  4109.5  142.41  4130.3   141.8
    4238     143  4665.2  140.83  4686.4   139.2  4700.4  135.43  4729.4  131.51
  4764.7  130.98  4928.8  131.37  4942.8  129.87  5049.8  130.48  5120.1  135.54
  5156.6  137.23  5177.4  139.32  5206.1  140.84  5241.2   144.7  5269.8  146.17
  5276.4  147.35  5298.5     148    5305   149.3  5327.1  150.29  5333.6  151.31
    5348  151.31  5368.8  153.19  5390.9  153.79  5397.4  154.75  5489.1  160.14
#Mann= 3 , 0 , 0
  3850.8     .05       0  4665.2     .03       0  5177.4     .05       0
Bank Sta=4665.2,5177.4
XS Rating Curve= 0 ,0
Exp/Cntr=0.3,0.1

Type RM Length L Ch R = 1 ,4176    ,432,432,432
BEGIN DESCRIPTION:
Mapping XS b5c3bed8
END DESCRIPTION:
XS GIS Cut Line= 4
       2295494.7     13224942.07      2295829.54     13224636.21
      2296322.79     13223764.48      2296395.71     13223576.97
#Sta/Elev= 30
  3851.2  143.26  4147.3  140.98  4253.4  141.59  4384.4  140.51  4477.8  140.52
  4568.2  139.77  4590.5  138.31  4602.7  135.56  4612.1  134.79  4617.9  131.69
  4633.8  130.95  4639.2  129.87  4642.5  130.37  4736.2  130.37    4742   131.2
  4752.1  130.37  5050.8  130.37  5059.5   131.8  5096.8  134.27  5108.6   136.1
  5124.5  136.86  5146.1  138.92  5183.6  142.55  5234.6  148.32    5302  153.12
  5306.2  154.06  5332.2  154.93  5432.5  161.25  5476.2  163.37  5507.5  164.25
#Mann= 3 , 0 , 0
  3851.2     .05       0  4590.5     .03       0  5146.1     .05       0
Bank Sta=4590.5,5146.1
XS Rating Curve= 0 ,0
Exp/Cntr=0.3,0.1

Type RM Length L Ch R = 1 ,3744    ,165,165,165
BEGIN DESCRIPTION:
Mapping XS 18ca4053
END DESCRIPTION:
XS GIS Cut Line= 4
      2295557.57     13224955.03      2296156.55     13224677.67
       2296474.1     13224372.16      2296630.36      13223866.9
#Sta/Elev= 30
       0143.2396   79.18142.9498  138.56141.8336  257.33140.7553  455.28140.2729
  484.97140.6265  583.94140.0039  613.63140.8403  702.55141.4229  791.27140.5301
  840.56139.5994  850.42139.9554  870.13139.6558  879.99140.1742  899.71139.6505
  919.42140.6635 1008.15 141.738 1057.44141.5941 1135.06142.4816 1153.95143.1476
 1267.62 143.106    1385143.7187 1414.34144.3361 1443.68145.7554 1463.25147.3818
 1482.81 149.694 1522.12151.9716 1591.01158.0124 1600.85158.5741 1629.52 158.742
#Mann= 3 , 0 , 0
       0     .05       0  791.27     .03       0  919.42     .05       0
Bank Sta=791.27,919.42
XS Rating Curve= 0 ,0
Exp/Cntr=0.3,0.1

Type RM Length L Ch R = 1 ,3579    ,91,91,91
BEGIN DESCRIPTION:
Mapping XS 18ca40531
END DESCRIPTION:
XS GIS Cut Line= 4
      2295631.36     13224987.58      2296230.34     13224710.22
      2296701.26     13224291.06      2296686.07     13223885.27
#Sta/Elev= 30
    3794  142.96  3807.4  142.82  3950.1  140.68  4018.9  140.61  4197.7  140.06
  4264.6   141.4    4282  140.19  4287.5  140.83    4363  139.38  4546.4  139.73
  4666.8   138.2  4688.6  138.86  4780.5  136.96  4794.8  137.07  4801.4  139.06
    4809  138.63  4815.7  140.16  4844.1  142.02  5021.4  141.04  5089.1  140.18
  5128.8  136.78  5148.5     134  5170.4   135.2  5188.8  136.93  5248.8  142.75
  5313.4   147.4  5318.9  148.53    5409  152.69    5419  153.93  5490.6  154.44
#Mann= 5 ,-1 , 0
    3794      .1       0  3807.4     .16       0  4018.9     .05       0
  5021.4     .05       0  5170.4      .1       0
Bank Sta=5128.8,5188.8
XS Rating Curve= 0 ,0
Exp/Cntr=0.3,0.1

Type RM Length L Ch R = 1 ,3488    ,535,535,535
BEGIN DESCRIPTION:
Mapping XS 8d57cd98
END DESCRIPTION:
XS GIS Cut Line= 3
      2296450.13      13224705.3      2296786.51     13224303.81
      2297414.28     13224065.69
#Sta/Elev= 30
  4597.6  138.87  4815.2  137.03  4856.9   134.6  4871.2   135.8  4893.3  139.68
  4928.4  140.07    5000  139.74  5070.3  138.36    5078  136.22  5105.4  133.08
  5152.3  129.92  5212.5  130.65  5368.7  128.67  5400.5  126.55  5407.5  127.67
  5422.1  127.34  5443.5  128.27  5454.2  129.16  5467.8  132.37  5522.7  134.64
  5552.8  137.22  5657.4  142.98  5668.1  144.47  5687.5  144.67  5700.2     146
  5717.6  145.68    5723  146.47  5742.4   146.6  5747.8   147.8  5792.8  148.53
#Mann= 4 ,-1 , 0
  4597.6      .1       0  4928.4    .035       0    5000      .1       0
  5792.8      .1       0
Bank Sta=5368.7,5443.5
XS Rating Curve= 0 ,0
Exp/Cntr=0.3,0.1

Type RM Length L Ch R = 1 ,2953    ,526,526,526
BEGIN DESCRIPTION:
Mapping XS e61c6f5e
END DESCRIPTION:
XS GIS Cut Line= 3
        2296771.     13224660.35       2296979.3     13224625.63
      2297543.09     13224322.05
#Sta/Elev= 30
  4539.9   137.8  4597.4  137.35  4617.7  138.19  4708.5  137.14    4817   131.1
  4822.7  130.14  4866.5  127.51  4896.9  126.64  4932.2  126.83  4948.4  126.08
  4954.1  123.11  4964.7   122.7  4970.1  121.15  4986.6  121.69  5008.5  125.57
  5014.2   125.9  5044.6  126.63    5058  128.15  5067.3  128.17    5090  129.71
  5134.2  133.29  5139.9  134.67  5169.5  136.31  5192.2  138.32  5199.9  139.66
    5260  143.48  5271.7  144.84  5303.8  146.21  5353.3  150.08  5391.4  151.34
#Mann= 3 , 0 , 0
  4539.9     .07       0  4948.4    .035       0  5014.2     .07       0
Bank Sta=4948.4,5014.2
XS Rating Curve= 0 ,0
Exp/Cntr=0.3,0.1

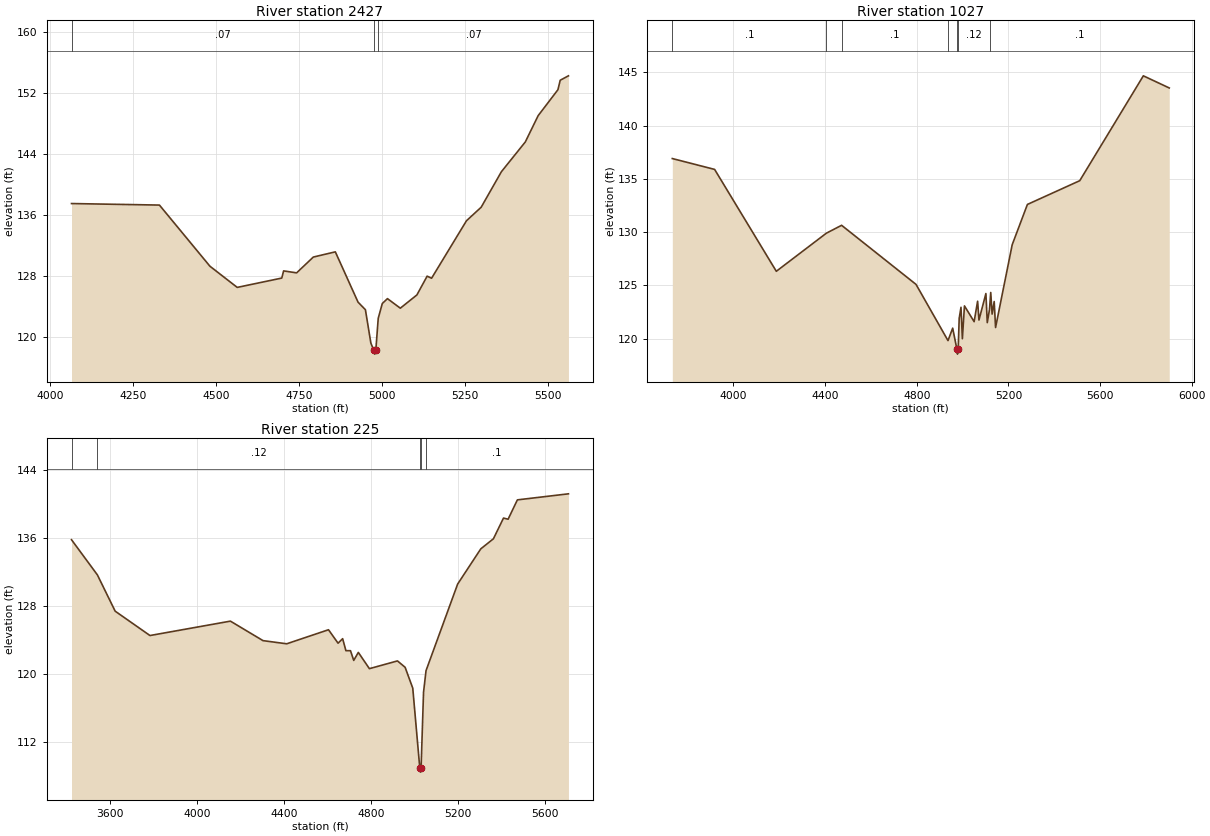
Type RM Length L Ch R = 1 ,2427    ,1400,1400,1400
BEGIN DESCRIPTION:
Mapping XS f54f0a98
END DESCRIPTION:
XS GIS Cut Line= 4
      2296770.97     13224715.91      2297239.72     13224726.32
      2297531.39     13224872.16       2297853.5     13224248.71
#Sta/Elev= 30
    4064  137.52  4328.8  137.32  4480.9  129.32  4563.1  126.55  4697.3  127.77
  4702.8  128.71    4742  128.45  4792.3  130.52  4858.6   131.2    4927  124.62
  4949.2  123.63  4965.7  119.25  4974.5  118.32  4977.2  117.82  4980.5  118.32
  4987.8   122.5    5000  124.44  5015.6  125.08  5054.3  123.83  5104.2  125.56
  5135.1  128.02  5148.5  127.75  5253.6  135.27  5297.9  137.04  5358.7  141.68
  5430.8  145.58  5469.5  149.02    5529  152.41  5535.9  153.65  5560.7  154.23
#Mann= 3 ,-1 , 0
    4064     .07       0  4974.5    .035       0  4987.8     .07       0
Bank Sta=4974.5,4980.5
XS Rating Curve= 0 ,0
Exp/Cntr=0.3,0.1

Type RM Length L Ch R = 1 ,1027    ,802,802,802
BEGIN DESCRIPTION:
Mapping XS 095bf61a
END DESCRIPTION:
XS GIS Cut Line= 6
      2296823.08      13224773.2      2297239.72      13224773.2
      2297612.98     13224998.89      2298307.43     13225450.28
      2298602.57     13225693.34      2298619.92     13225797.48
#Sta/Elev= 30
  3733.2  136.91  3917.8  135.89  4187.1  126.32  4405.6   129.9  4472.1  130.64
  4796.9  125.09  4936.5  119.81  4956.9  120.98    4975  119.04  4977.8  118.54
    4981  119.04  4985.3   121.9  4993.2  122.94  4999.2  119.99  5008.3  123.07
  5050.5  121.59  5065.7  123.51  5071.6  121.74  5101.9  124.23  5107.9   121.5
  5117.6  122.73    5123  124.33    5129   122.3  5138.1  123.48  5144.1  121.04
  5216.6  128.81  5283.1   132.6  5511.5  134.83  5789.1  144.68  5902.2  143.54
#Mann= 7 ,-1 , 0
  3733.2      .1       0  4405.6     .16       0  4472.1      .1       0
  4936.5     .12       0    4975     .07       0    4981     .12       0
  5117.6      .1       0
Bank Sta=4975,4981
XS Rating Curve= 0 ,0
Exp/Cntr=0.3,0.1

Type RM Length L Ch R = 1 ,225     ,0,0,0
BEGIN DESCRIPTION:
UNT 072 IN LACR 1.0
END DESCRIPTION:
XS GIS Cut Line= 5
      2296566.95     13225188.06       2297587.8     13225222.78
      2297823.91     13225576.95      2298136.41     13225826.95
      2298365.54     13226201.89
#Sta/Elev= 30
  3422.2  135.81  3541.3  131.68  3623.1  127.42  3783.2  124.56  4153.4  126.25
  4303.5  123.96  4412.5  123.59  4604.8  125.24  4648.8  123.66  4669.9  124.19
  4684.9  122.78  4705.9  122.78  4720.9  121.64    4742  122.58    4793  120.67
  4922.1  121.58  4957.3  120.83  4992.5  118.38  5024.8  109.02  5027.6  108.52
  5030.8  109.02  5042.1   117.9  5053.6  120.44    5199   130.6  5305.6  134.74
  5363.6  135.92    5410  138.35  5431.3  138.22  5473.9  140.49  5708.9   141.2
#Mann= 5 ,-1 , 0
  3422.2     .16       0  3541.3     .12       0  5024.8     .07       0
  5030.8     .12       0  5053.6      .1       0
Bank Sta=5024.8,5030.8
XS Rating Curve= 0 ,0
Exp/Cntr=0.3,0.1

Chan Stop Cuts=-1
Use User Specified Reach Order=0
Composite Channel Slope=5