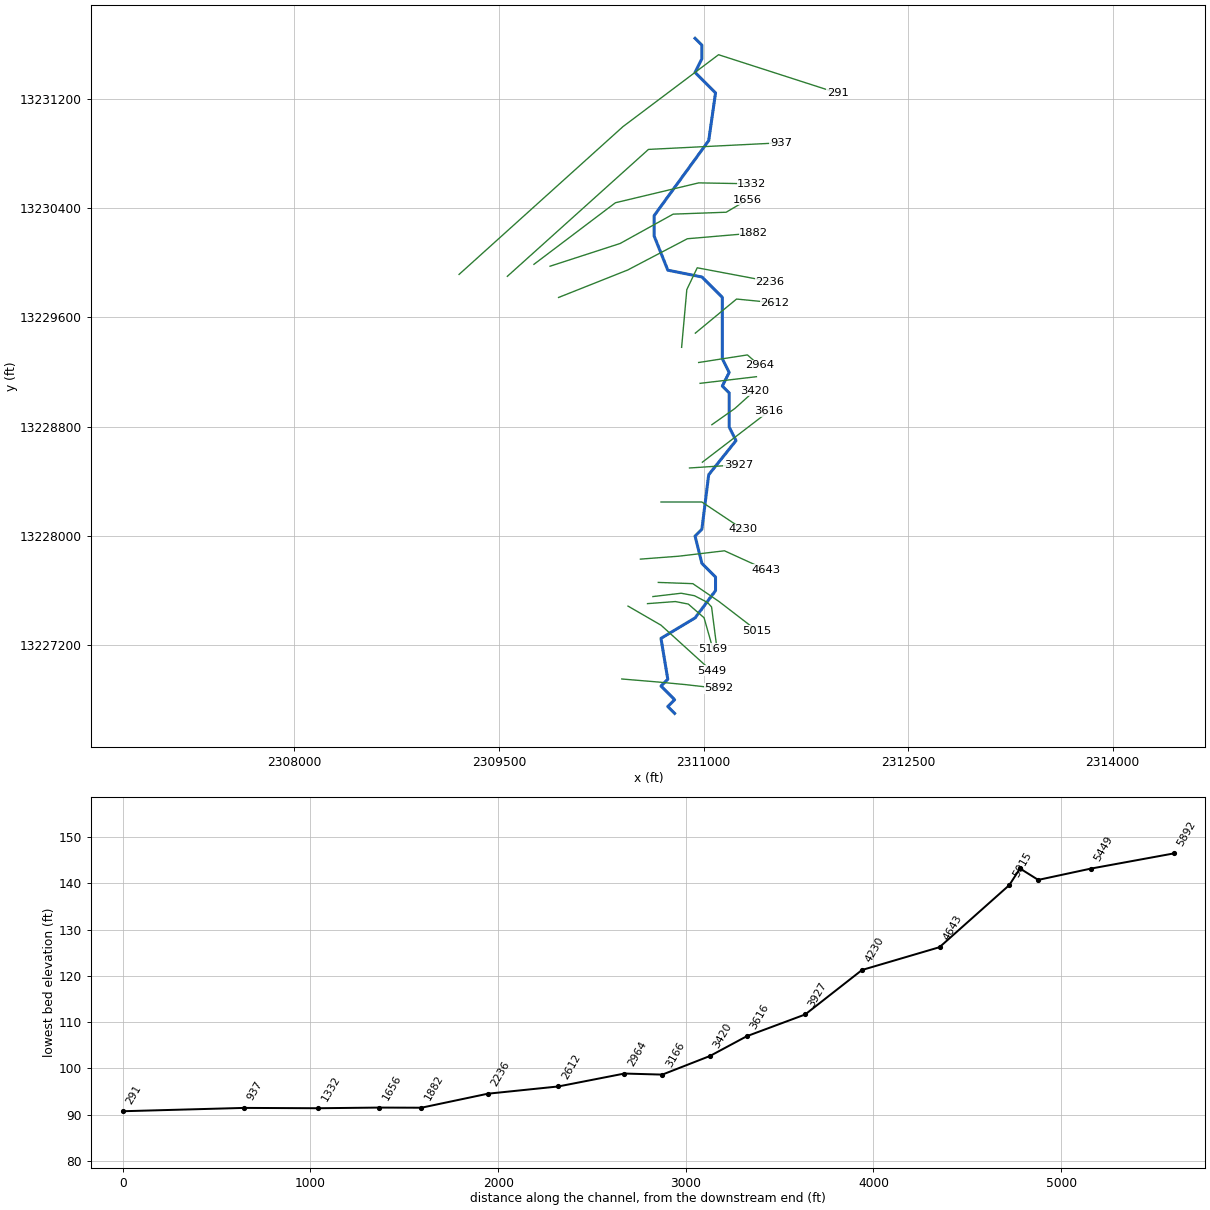
--- UNT 073 IN LACR.prj (project) ---

Proj Title=UNT 073 IN LACR Base Level Engineering
Current Plan=p01
Default Exp/Contr=0.3,0.1
English Units
Geom File=g01
Flow File=f01
Plan File=p01
Y Axis Title=Elevation
X Axis Title(PF)=Main Channel Distance
X Axis Title(XS)=Station
BEGIN DESCRIPTION:
UNT 073 IN LACR
END DESCRIPTION:
DSS Export Rating Curves= 0
DSS Export Rating Curve Sorted= 0
DSS Export Volume Flow Curves= 0
DXF OffsetX= 0
DXF OffsetY= 0
DXF ScaleX= 1
DXF ScaleY= 10

--- UNT 073 IN LACR.p01 (plan) ---

Plan Title=Multiple Run
Short Identifier=Multiple
Geom File=g01
Flow File=f01
Subcritical Flow
K Sum by GR= 0
Std Step Tol= 0.01
Critical Tol= 0.01
Num of Std Step Trials= 20
Max Error Tol= 0.3
Flow Tol Ratio= 0.001
Split Flow NTrial= 30
Split Flow Tol= 0.02
Split Flow Ratio= 0.02
Log Output Level= 0
Friction Slope Method= 1
Unsteady Friction Slope Method= 2
Unsteady Bridges Friction Slope Method= 1
Parabolic Critical Depth
Global Vel Dist=  1 , 1 , 1
Global Log Level= 0
CheckData=True
Encroach Param= -1, 0, 0, 0
BEGIN DESCRIPTION:
Multiple Run
END DESCRIPTION:

--- UNT 073 IN LACR.f01 (steady flow) ---

Flow Title=Multiple
Program Version=4.10
Number of Profiles= 7
Profile Names=10-year,25-year,50-year,1pct_min,100-year,1pct_plu,500-year
River Rch & RM=UNT 073 IN LACR,Reach-1         ,5892
     464     634     770     683     924    1249    1333
River Rch & RM=UNT 073 IN LACR,Reach-1         ,3420
     583     814    1005     905    1224    1655    1824
River Rch & RM=UNT 073 IN LACR,Reach-1         ,1882
     993    1435    1813    1670    2259    3055    3521
River Rch & RM=UNT 073 IN LACR,Reach-1         ,1656
    1116    1621    2056    1900    2569    3474    4029
Boundary for River Rch & Prof#=UNT 073 IN LACR,Reach-1         , 1
Up Type= 0
Dn Type= 3
Dn Slope=0.001
Boundary for River Rch & Prof#=UNT 073 IN LACR,Reach-1         , 2
Up Type= 0
Dn Type= 3
Dn Slope=0.001
Boundary for River Rch & Prof#=UNT 073 IN LACR,Reach-1         , 3
Up Type= 0
Dn Type= 3
Dn Slope=0.001
Boundary for River Rch & Prof#=UNT 073 IN LACR,Reach-1         , 4
Up Type= 0
Dn Type= 3
Dn Slope=0.001
Boundary for River Rch & Prof#=UNT 073 IN LACR,Reach-1         , 5
Up Type= 0
Dn Type= 3
Dn Slope=0.001
Boundary for River Rch & Prof#=UNT 073 IN LACR,Reach-1         , 6
Up Type= 0
Dn Type= 3
Dn Slope=0.001
Boundary for River Rch & Prof#=UNT 073 IN LACR,Reach-1         , 7
Up Type= 0
Dn Type= 3
Dn Slope=0.001
DSS Import GetInterval= 0
DSS Import GetPeak= 0
DSS Import FillOption= 0

--- UNT 073 IN LACR.g01 (geometry) ---

Geom Title=Existing Conditions
Program Version=4.10

River Reach=UNT 073 IN LACR ,Reach-1
Reach XY= 30
      2310787.72     13226696.85      2310737.72     13226746.86
      2310787.72     13226796.85      2310687.72     13226896.85
      2310737.72     13226946.86      2310687.72     13227246.86
      2310937.72     13227396.85      2311087.72     13227596.86
      2311087.72     13227696.85      2310987.72     13227796.85
      2310937.72     13227996.85      2310987.72     13228046.85
      2311037.72     13228446.85      2311237.72     13228696.85
      2311187.72     13228796.85      2311187.72     13229046.86
      2311137.72     13229096.85      2311187.72     13229196.85
      2311137.72     13229296.85      2311137.72     13229746.85
      2310987.72     13229896.86      2310737.72     13229946.85
      2310637.72     13230196.86      2310637.72     13230346.85
      2311037.72     13230896.85      2311087.72     13231246.85
      2310937.72     13231396.85      2310987.72     13231496.85
      2310987.72     13231596.85      2310937.72     13231646.85

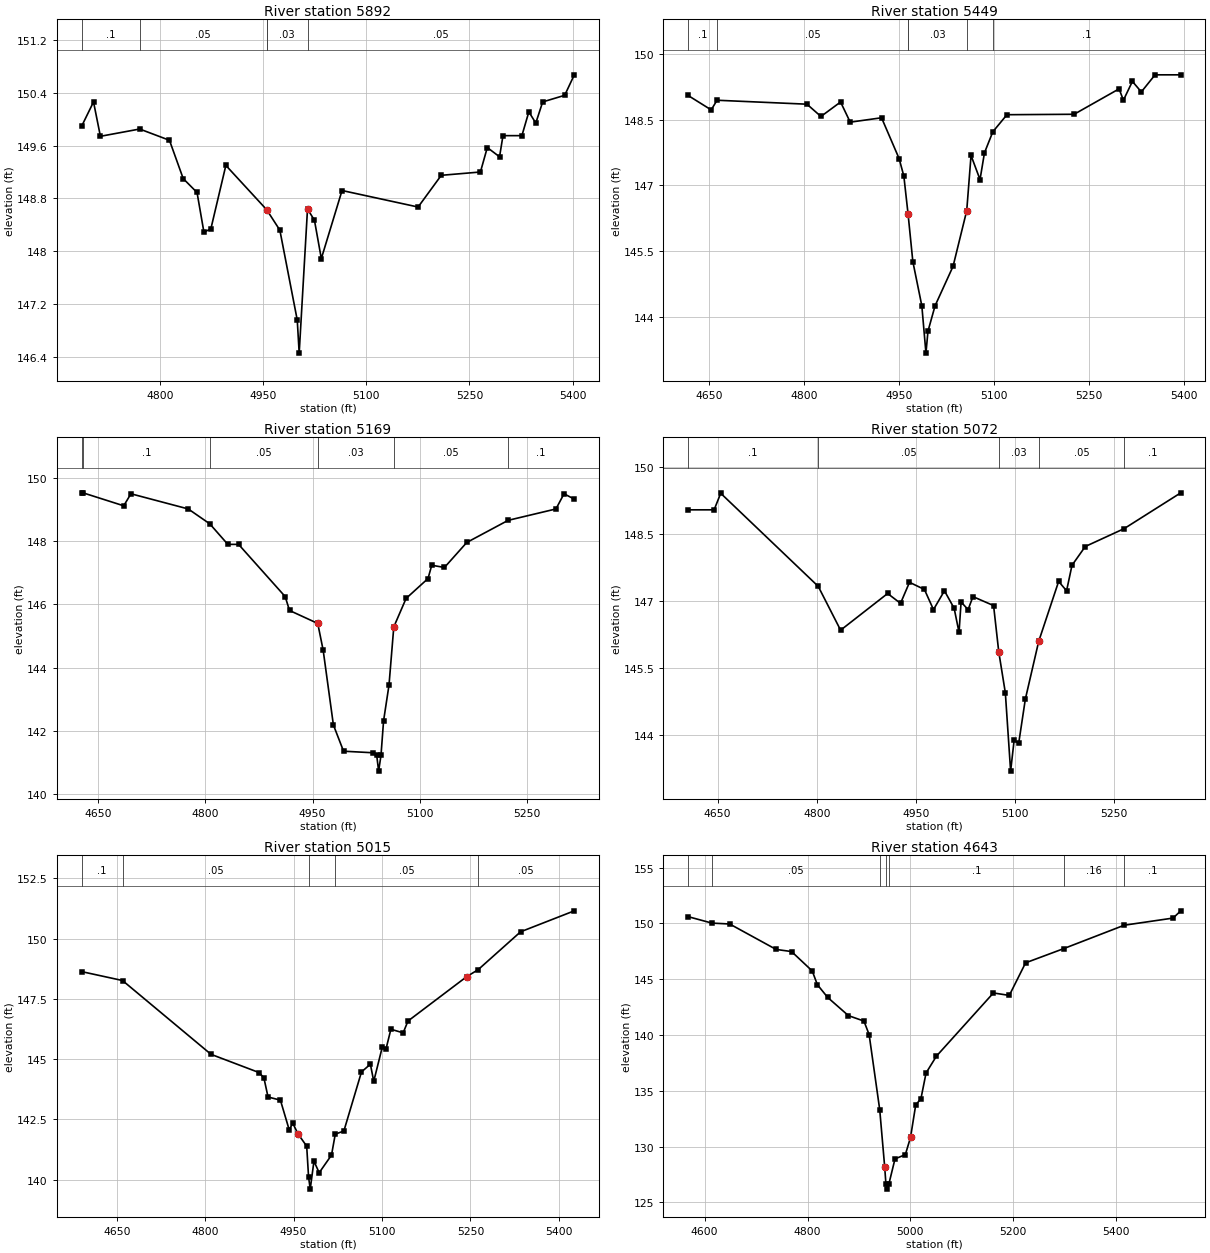
Type RM Length L Ch R = 1 ,5892    ,443,443,443
BEGIN DESCRIPTION:
UNT 073 IN LACR 10.0
END DESCRIPTION:
XS GIS Cut Line= 4
       2310400.4     13226949.02      2310664.49     13226927.01
      2310864.12     13226908.14       2311113.4     13226879.92
#Sta/Elev= 30
    4686  149.89  4703.4  150.26  4713.4  149.74  4770.5  149.85  4813.8  149.68
  4833.8   149.1  4853.9  148.89  4863.9  148.29    4874  148.34  4895.8   149.3
  4955.1  148.63  4974.3  148.32  4999.6  146.96  5002.4  146.46  5014.5  148.64
  5024.6  148.47  5034.6  147.89  5064.7  148.92  5175.3  148.67    5209  149.15
  5265.9   149.2  5275.9  149.57  5293.7  149.43  5298.7  149.75  5326.2  149.75
  5336.3  150.11  5346.4  149.94  5356.4  150.26  5388.4  150.36  5402.4  150.67
#Mann= 5 ,-1 , 0
    4686      .1       0  4770.5     .05       0  4955.1      .1       0
  4955.1     .03       0  5014.5     .05       0
Bank Sta=4955.1,5014.5
XS Rating Curve= 0 ,0
Exp/Cntr=0.3,0.1

Type RM Length L Ch R = 1 ,5449    ,280,280,280
BEGIN DESCRIPTION:
Mapping XS 04d181f0
END DESCRIPTION:
XS GIS Cut Line= 3
        2310446.     13227483.46      2310688.07     13227343.56
      2311057.44     13227008.77
#Sta/Elev= 30
  4616.8  149.05  4653.4  148.72  4662.6  148.94  4804.6  148.85  4826.7  148.57
  4857.7   148.9  4872.9  148.44  4922.4  148.54  4950.1  147.61  4957.6  147.21
  4964.3  146.34  4971.8  145.26    4986  144.25  4992.5  143.17  4995.7  143.67
  5006.9  144.25  5035.3  145.15  5056.9  146.42  5063.7  147.68  5077.9  147.13
  5084.9  147.74  5098.1  148.22  5120.4  148.61  5226.5  148.62  5297.5   149.2
  5304.3  148.94  5318.5  149.37  5332.6  149.13  5354.3  149.52  5394.9  149.52
#Mann= 6 ,-1 , 0
  4616.8      .1       0  4662.6     .05       0  4964.3      .1       0
  4964.3     .03       0  5056.9     .05       0  5098.1      .1       0
Bank Sta=4964.3,5056.9
XS Rating Curve= 0 ,0
Exp/Cntr=0.3,0.1

Type RM Length L Ch R = 1 ,5169    ,97,97,97
BEGIN DESCRIPTION:
Mapping XS 242c7e21
END DESCRIPTION:
XS GIS Cut Line= 5
      2310588.85     13227501.59      2310793.25     13227516.84
      2310887.81     13227498.54      2311003.74     13227397.87
      2311067.81      13227172.1
#Sta/Elev= 30
  4626.7  149.51  4628.7  149.53  4685.7  149.12  4695.8   149.5    4776  149.02
  4806.1  148.55  4831.4   147.9  4846.4   147.9  4911.6  146.25  4917.7  145.81
  4957.2   145.4  4964.8  144.55  4979.1  142.19  4993.3  141.36  5035.1  141.31
  5039.7  141.23  5042.4  140.73  5045.7  141.23  5049.3  142.32  5056.9  143.45
  5063.6  145.29  5080.8  146.19  5111.5  146.82  5116.7  147.24  5134.5  147.17
  5165.7  147.96  5223.6  148.66  5290.5  149.02  5301.8   149.5  5316.2  149.33
#Mann= 6 ,-1 , 0
  4626.7     .05       0  4628.7      .1       0  4806.1     .05       0
  4957.2     .03       0  5063.6     .05       0  5223.6      .1       0
Bank Sta=4957.2,5063.6
XS Rating Curve= 0 ,0
Exp/Cntr=0.3,0.1

Type RM Length L Ch R = 1 ,5072    ,57,57,57
BEGIN DESCRIPTION:
Mapping XS 8045929a
END DESCRIPTION:
XS GIS Cut Line= 6
      2310628.53     13227553.45      2310835.95     13227577.85
      2310933.57     13227559.55      2311028.14     13227510.74
      2311058.65     13227477.18      2311095.25     13227193.48
#Sta/Elev= 30
  4605.1  149.04  4644.6  149.04  4654.6  149.41  4802.2  147.33  4836.1  146.35
  4907.3  147.17  4926.8  146.95  4940.4  147.42    4963  147.26  4976.7  146.81
  4993.3  147.23    5008  146.84  5015.4   146.3  5018.5  146.98  5029.1  146.81
  5036.5   147.1  5067.7   146.9  5075.5  145.87  5085.5  144.95  5093.5   143.2
  5098.8  143.89  5105.7  143.82  5115.8  144.81    5136   146.1  5166.2  147.44
  5178.2  147.23  5186.4   147.8  5206.5  148.22  5265.4  148.62  5351.1  149.42
#Mann= 5 ,-1 , 0
  4605.1      .1       0  4802.2     .05       0  5075.5     .03       0
    5136     .05       0  5265.4      .1       0
Bank Sta=5075.5,5136
XS Rating Curve= 0 ,0
Exp/Cntr=0.3,0.1

Type RM Length L Ch R = 1 ,5015    ,372,372,372
BEGIN DESCRIPTION:
Mapping XS 347f88ed
END DESCRIPTION:
XS GIS Cut Line= 4
      2310668.15     13227657.17      2310921.37     13227648.02
      2311113.56     13227516.84      2311391.16      13227303.3
#Sta/Elev= 30
  4590.1  148.63  4659.6  148.26  4809.8   145.2  4891.7  144.44  4899.6  144.22
  4906.6  143.43  4927.6   143.3  4942.5  142.07  4948.6  142.34  4957.5   141.9
  4972.2  141.39  4975.4  140.11  4978.2  139.61  4984.5  140.77  4993.4  140.29
  5014.3  141.02  5020.7  141.89  5035.3  142.02  5065.2  144.47  5080.3  144.79
    5086  144.08  5100.5   145.5  5106.9  145.43  5115.1  146.24  5135.9  146.09
  5144.1  146.58  5243.7  148.42  5263.2  148.71  5335.2  150.28  5426.4  151.15
#Mann= 5 ,-1 , 0
  4590.1      .1       0  4659.6     .05       0  4975.4     .03       0
  5020.7     .05       0  5263.2     .05       0
Bank Sta=4957.5,5243.7
XS Rating Curve= 0 ,0
Exp/Cntr=0.3,0.1

Type RM Length L Ch R = 1 ,4643    ,413,413,413
BEGIN DESCRIPTION:
UNT 073 IN LACR 9.0
END DESCRIPTION:
XS GIS Cut Line= 4
      2310536.96       13227828.      2310817.65     13227849.36
      2311153.22     13227889.01      2311461.36     13227748.67
#Sta/Elev= 30
  4567.6   150.6  4614.1  150.02  4648.6  149.94  4738.9  147.66  4768.9  147.47
  4809.1  145.73  4819.1   144.5  4839.1  143.36  4879.4  141.73  4909.6  141.24
  4919.7  140.03  4940.3   133.3  4949.9   128.2  4952.3  126.68    4955  126.18
  4958.3  126.68    4970  128.89  4990.1  129.27  5000.2  130.82  5010.3  133.73
  5020.4  134.28  5030.4  136.59  5050.6   138.1  5161.3  143.76  5192.2  143.54
  5223.9  146.46  5297.8  147.73  5415.6  149.83  5510.6  150.47  5525.6  151.12
#Mann= 7 ,-1 , 0
  4567.6      .1       0  4614.1     .05       0  4940.3      .1       0
  4952.3     .07       0  4958.3      .1       0  5297.8     .16       0
  5415.6      .1       0
Bank Sta=4949.9,5000.2
XS Rating Curve= 0 ,0
Exp/Cntr=0.3,0.1

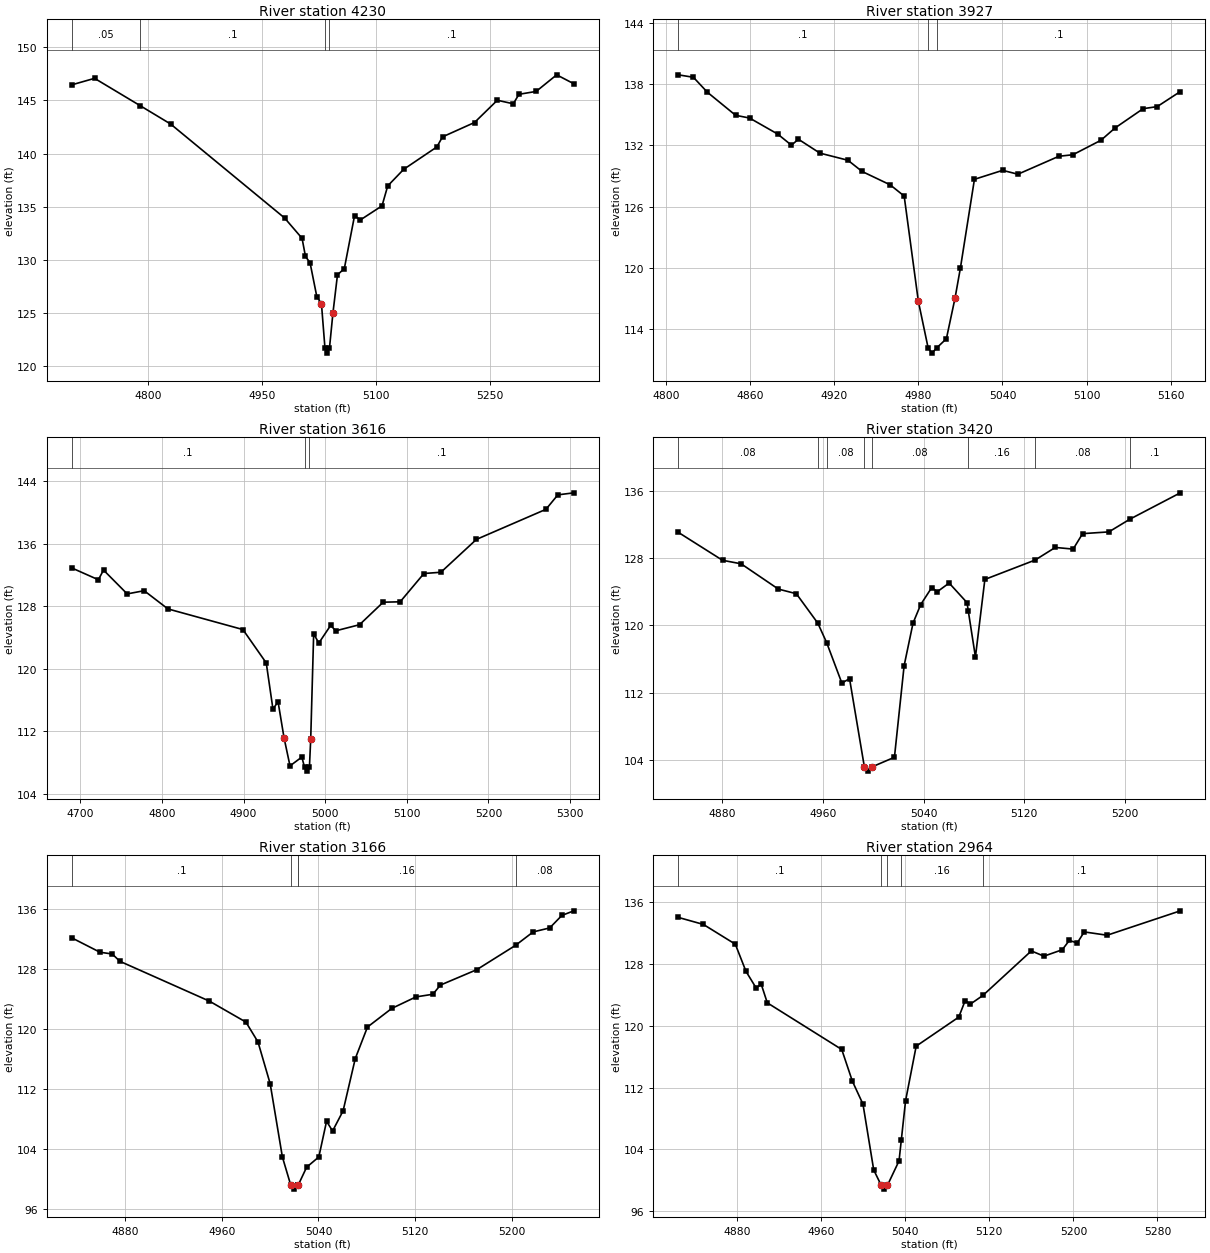
Type RM Length L Ch R = 1 ,4230    ,303,303,303
BEGIN DESCRIPTION:
UNT 073 IN LACR 8.0
END DESCRIPTION:
XS GIS Cut Line= 3
      2310687.72     13228246.85      2310987.72     13228246.86
      2311287.76     13228046.83
#Sta/Elev= 30
    4700  146.46    4730  147.07  4789.8  144.51    4830  142.78    4980  133.95
    5003  132.04  5007.5  130.33  5013.5  129.75  5022.5  126.53  5028.5  125.91
  5033.1  121.75  5035.8  121.25  5039.1  121.75  5043.6     125  5049.6  128.61
  5058.6  129.19  5072.1  134.18  5079.6  133.76  5108.2  135.09  5115.7  136.96
  5136.7  138.52  5180.3  140.62  5187.8  141.57  5229.9  142.92  5259.9  145.01
  5280.9  144.68  5288.4  145.57    5311  145.84    5338   147.4  5360.6  146.56
#Mann= 4 ,-1 , 0
    4700     .05       0  4789.8      .1       0  5033.1     .07       0
  5039.1      .1       0
Bank Sta=5028.5,5043.6
XS Rating Curve= 0 ,0
Exp/Cntr=0.3,0.1

Type RM Length L Ch R = 1 ,3927    ,311,311,311
BEGIN DESCRIPTION:
UNT 073 IN LACR 7.0
END DESCRIPTION:
XS GIS Cut Line= 2
      2310896.93     13228496.25      2311254.16     13228519.71
#Sta/Elev= 30
  4808.8  138.93  4819.6  138.69  4829.6  137.22  4849.7  134.96  4859.7  134.69
  4879.7  133.12  4889.5  132.03  4894.5  132.61  4909.8  131.25  4929.8  130.55
  4939.9  129.45  4959.9  128.14  4969.9  127.04    4980  116.72    4987  112.13
  4989.7  111.63    4993  112.13    5000  113.04 5006.14  117.01    5010  119.98
    5020  128.68  5040.1  129.56    5051  129.18  5080.2  130.94  5090.2  131.09
  5110.2  132.51  5120.3  133.72  5140.3  135.61  5150.3  135.81  5166.8  137.29
#Mann= 3 ,-1 , 0
  4808.8      .1       0    4987     .07       0    4993      .1       0
Bank Sta=4980,5006.14
XS Rating Curve= 0 ,0
Exp/Cntr=0.3,0.1

Type RM Length L Ch R = 1 ,3616    ,196,196,196
BEGIN DESCRIPTION:
Mapping XS 7e864c15
END DESCRIPTION:
XS GIS Cut Line= 2
      2310991.22      13228538.7      2311479.62     13228912.79
#Sta/Elev= 30
  4689.5  132.92  4722.1  131.41  4728.4  132.65  4757.4   129.6  4778.2  130.01
  4807.3  127.68  4899.2  125.04  4927.8  120.77    4936  114.88  4942.3  115.79
  4949.6  111.19  4956.9   107.6  4971.4  108.73  4974.7  107.43  4977.4  106.93
  4980.7  107.43 4982.27  111.01  4985.9   124.5  4992.2  123.31  5006.7  125.57
    5013  124.88  5042.1  125.66  5071.1  128.54  5091.9  128.59    5121  132.21
  5141.8  132.37  5185.3  136.57  5270.5  140.42  5285.1  142.27  5304.7  142.53
#Mann= 3 ,-1 , 0
  4689.5      .1       0  4974.7     .07       0  4980.7      .1       0
Bank Sta=4949.6,4982.27
XS Rating Curve= 0 ,0
Exp/Cntr=0.3,0.1

Type RM Length L Ch R = 1 ,3420    ,254,254,254
BEGIN DESCRIPTION:
Mapping XS 935272bf
END DESCRIPTION:
XS GIS Cut Line= 3
      2311060.94     13228813.72      2311230.11     13228932.94
        2311373.     13229061.54
#Sta/Elev= 30
  4844.9  131.09  4880.1  127.76  4894.9  127.34  4924.5  124.33  4938.8  123.78
  4955.9  120.27  4962.9  117.96    4975  113.14  4981.1  113.67  4992.9  103.16
  4995.6  102.66  4998.9  103.16  5016.8  104.31  5024.5  115.21  5031.6  120.29
  5037.7  122.49  5046.4   124.5  5050.9  124.02  5060.3  125.05  5074.5  122.72
  5075.5  121.75  5081.2  116.25  5088.7  125.48  5128.7  127.79  5144.7  129.29
  5158.9  129.09  5166.4  130.93  5187.3  131.14  5204.2  132.67  5244.1  135.79
#Mann= 8 ,-1 , 0
  4844.9     .08       0  4955.9     .16       0  4962.9     .08       0
  4992.9     .07       0  4998.9     .08       0  5075.5     .16       0
  5128.7     .08       0  5204.2      .1       0
Bank Sta=4992.9,4998.9
XS Rating Curve= 0 ,0
Exp/Cntr=0.3,0.1

Type RM Length L Ch R = 1 ,3166    ,202,202,202
BEGIN DESCRIPTION:
UNT 073 IN LACR 6.0
END DESCRIPTION:
XS GIS Cut Line= 2
      2310974.45     13229117.03       2311387.6     13229165.64
#Sta/Elev= 30
  4835.6  132.12    4859   130.2  4869.1  129.97  4875.5  128.99  4949.7  123.68
  4979.9  120.89  4989.9  118.24    5000  112.67  5010.1  102.92  5017.1   99.13
  5019.9   98.63  5023.1   99.13  5023.4   99.23  5030.2  101.55  5040.3  102.92
  5046.7  107.67  5051.7  106.38  5060.4  109.06  5070.5  116.03  5080.6  120.23
  5100.7  122.71  5120.8  124.25  5134.8   124.6    5141  125.82  5171.2  127.88
  5203.3  131.12  5217.9  132.91  5231.6  133.44  5241.7  135.11  5251.6  135.72
#Mann= 5 ,-1 , 0
  4835.6      .1       0  5017.1     .07       0  5023.1      .1       0
  5023.4     .16       0  5203.3     .08       0
Bank Sta=5017.1,5023.1
XS Rating Curve= 0 ,0
Exp/Cntr=0.3,0.1

Type RM Length L Ch R = 1 ,2964    ,352,352,352
BEGIN DESCRIPTION:
Mapping XS 57b8919f
END DESCRIPTION:
XS GIS Cut Line= 3
      2310964.06     13229269.81      2311321.67     13229325.36
      2311408.45     13229248.99
#Sta/Elev= 30
  4824.2  134.04  4848.1  133.13  4878.5  130.57  4888.6  127.06  4898.2  124.92
  4903.2  125.36  4908.9  122.98  4979.7  116.94  4989.8  112.84  4999.9  109.86
  5010.1  101.35  5017.2   99.36  5019.9   98.86  5023.2   99.36  5034.2  102.52
  5036.4  105.28  5040.4   110.3  5050.5  117.37    5091  121.13  5097.1  123.27
  5102.1  122.82  5113.9  123.93    5160   129.7    5172  129.02  5189.4  129.85
  5196.1  131.05  5203.7  130.73  5210.3  132.16  5232.1  131.73  5301.7  134.89
#Mann= 5 ,-1 , 0
  4824.2      .1       0  5017.2     .07       0  5023.2      .1       0
  5036.4     .16       0  5113.9      .1       0
Bank Sta=5017.2,5023.2
XS Rating Curve= 0 ,0
Exp/Cntr=0.3,0.1

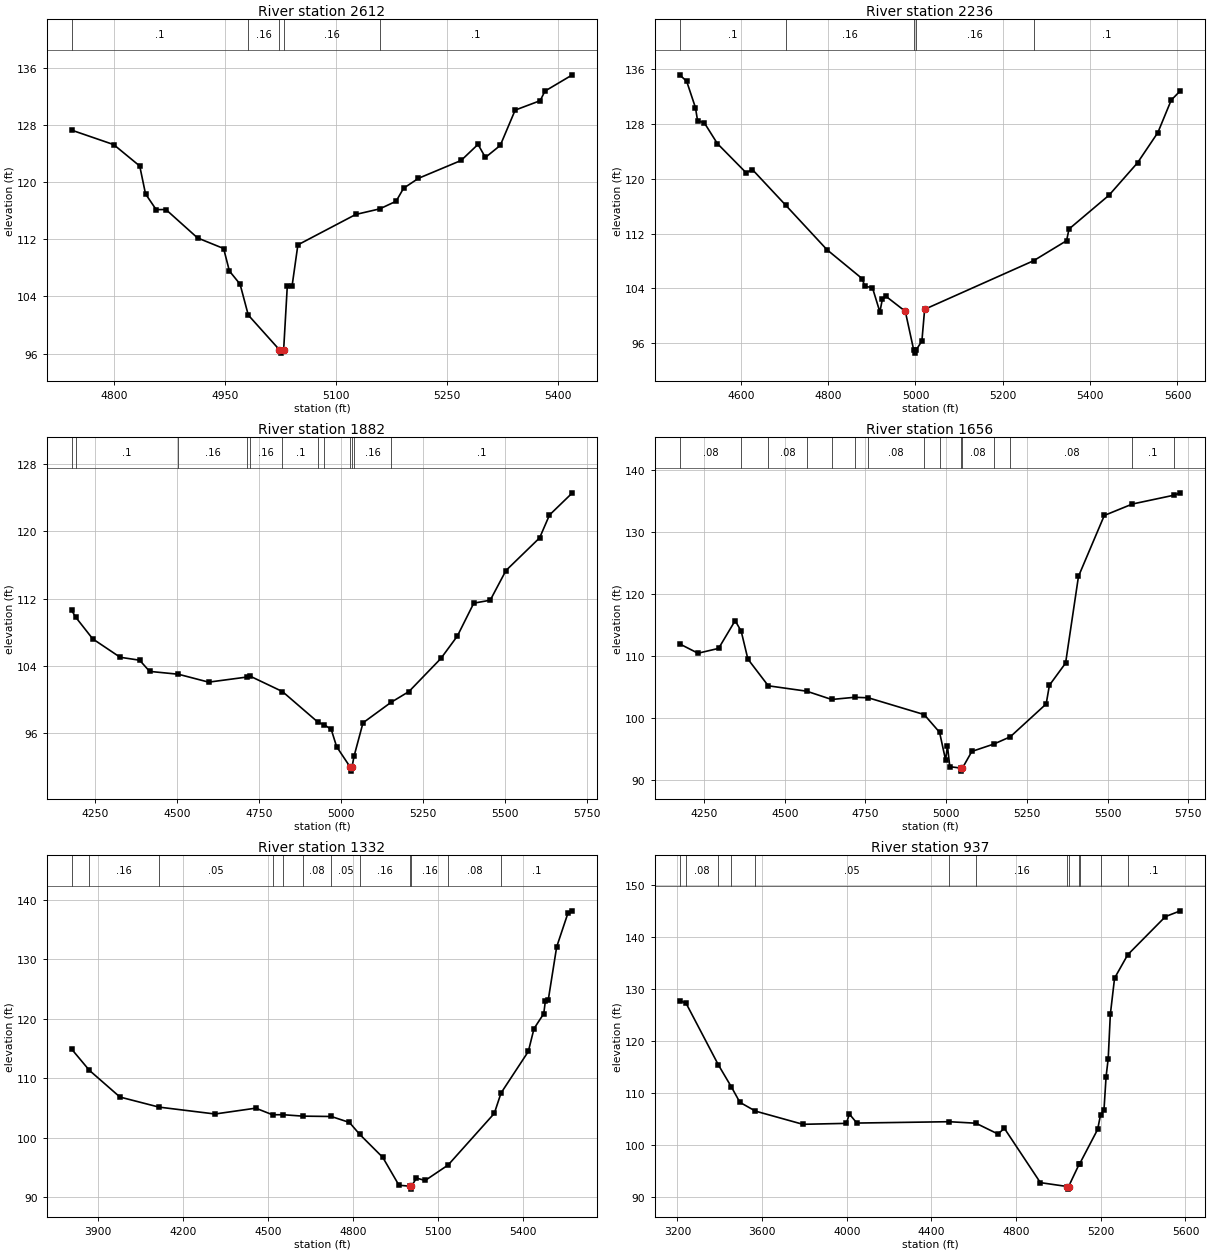
Type RM Length L Ch R = 1 ,2612    ,376,376,376
BEGIN DESCRIPTION:
UNT 073 IN LACR 5.0
END DESCRIPTION:
XS GIS Cut Line= 3
      2310939.73     13229485.09       2311241.8     13229735.08
      2311524.66     13229707.49
#Sta/Elev= 30
    4743  127.29  4799.7  125.27  4834.9  122.27  4842.7  118.37  4857.1  116.16
  4870.2  116.18    4913   112.2  4948.2  110.72    4956  107.57  4970.4  105.73
  4981.5   101.4  5023.3   96.57  5026.1   96.07  5029.3   96.57  5034.2  105.46
  5040.7  105.49  5048.5  111.23  5126.7  115.49  5159.1  116.27  5181.2  117.34
  5191.3  119.16  5211.4  120.55    5269  123.05  5291.8   125.3  5301.8  123.47
  5321.9  125.16    5342   130.1  5375.8  131.42  5382.2  132.76  5419.3  135.04
#Mann= 5 ,-1 , 0
    4743      .1       0  4981.5     .16       0  5023.3     .07       0
  5029.3     .16       0  5159.1      .1       0
Bank Sta=5023.3,5029.3
XS Rating Curve= 0 ,0
Exp/Cntr=0.3,0.1

Type RM Length L Ch R = 1 ,2236    ,354,354,354
BEGIN DESCRIPTION:
UNT 073 IN LACR 4.0
END DESCRIPTION:
XS GIS Cut Line= 4
      2310839.03     13229380.94      2310877.22     13229804.53
      2310953.61     13229964.25      2311488.36     13229863.55
#Sta/Elev= 30
  4460.1  135.22  4476.1  134.27  4496.2  130.42  4501.2  128.46  4516.2  128.23
  4546.4  125.16  4612.1   120.9  4626.7  121.35  4702.5  116.17  4797.4  109.63
  4877.7  105.41  4884.1  104.27  4901.4  104.09  4918.5  100.53  4924.1  102.35
  4932.3  102.82  4976.7  100.62  4995.8      95  4998.6    94.5  5001.8      95
  5014.7   96.26    5021  100.91  5270.5  108.02    5346  110.95  5351.6  112.66
  5443.1   117.6  5508.5  122.35  5555.1  126.78  5585.6  131.52  5606.6  132.89
#Mann= 5 ,-1 , 0
  4460.1      .1       0  4702.5     .16       0  4995.8     .07       0
  5001.8     .16       0  5270.5      .1       0
Bank Sta=4976.7,5021
XS Rating Curve= 0 ,0
Exp/Cntr=0.3,0.1

Type RM Length L Ch R = 1 ,1882    ,226,226,226
BEGIN DESCRIPTION:
UNT 073 IN LACR 3.0
END DESCRIPTION:
XS GIS Cut Line= 4
       2309936.8      13229746.7      2310443.74     13229948.09
      2310881.24     13230177.26       2311367.4     13230218.93
#Sta/Elev= 30
  4179.1  110.59  4191.3  109.79  4243.2  107.21  4326.9  105.02  4386.3  104.67
  4416.8  103.34  4504.5     103  4596.9  102.06  4714.4  102.67  4722.4  102.79
  4821.9  100.94    4931   97.27  4948.5   97.01  4970.8   96.43  4987.2   94.38
  5028.3   91.97  5031.1   91.47  5034.3   91.97  5040.2   93.22  5067.7   97.22
    5153   99.65  5207.8  100.94  5305.3  104.88  5355.4  107.54  5405.6  111.46
  5455.8  111.81  5503.7  115.34  5606.4  119.23  5636.5  121.95  5706.4  124.59
#Mann= 12 ,-1 , 0
  4179.1     .16       0  4191.3      .1       0  4504.5     .16       0
  4714.4      .1       0  4722.4     .16       0  4821.9      .1       0
    4931     .16       0  4948.5      .1       0  5028.3     .07       0
  5034.3      .1       0  5040.2     .16       0    5153      .1       0
Bank Sta=5028.3,5034.3
XS Rating Curve= 0 ,0
Exp/Cntr=0.3,0.1

Type RM Length L Ch R = 1 ,1656    ,324,324,324
BEGIN DESCRIPTION:
UNT 073 IN LACR 2.0
END DESCRIPTION:
XS GIS Cut Line= 5
      2309874.26     13229975.85      2310388.19     13230142.53
      2310777.08     13230357.81      2311165.96      13230371.7
      2311318.68     13230461.94
#Sta/Elev= 30
  4174.5  111.97  4231.2  110.47  4295.1  111.25  4346.3  115.71    4365  114.03
  4385.8  109.53    4449  105.23  4568.1  104.36  4645.3  103.03  4716.4  103.38
  4758.9   103.3    4932   100.6  4979.7   97.75  4998.4   93.27  5004.1   95.56
  5011.4   92.21  5044.6      92  5047.3    91.5  5050.6      92  5079.7   94.67
  5147.5   95.85  5198.7   97.02    5310  102.31    5320  105.32  5370.1  108.88
  5410.1  122.84  5490.1  132.64  5577.2  134.48  5706.1   135.9  5725.8  136.28
#Mann= 15 ,-1 , 0
  4174.5     .08       0    4365     .16       0    4449     .08       0
  4568.1     .05       0  4645.3     .08       0  4716.4     .16       0
  4758.9     .08       0    4932     .16       0  4979.7     .08       0
  5044.6     .07       0  5050.6     .08       0  5147.5     .16       0
  5198.7     .08       0  5577.2      .1       0  5706.1     .16       0
Bank Sta=5044.6,5050.6
XS Rating Curve= 0 ,0
Exp/Cntr=0.3,0.1

Type RM Length L Ch R = 1 ,1332    ,395,395,395
BEGIN DESCRIPTION:
Mapping XS 2334665f
END DESCRIPTION:
XS GIS Cut Line= 4
      2309756.21     13229989.73      2310353.46     13230441.15
      2310964.58     13230586.98      2311353.08     13230580.04
#Sta/Elev= 30
  3807.7   114.9  3869.9  111.35  3977.9  106.85  4115.3  105.16    4313     104
  4456.6  104.98  4515.9  103.87  4552.1  103.88  4622.9  103.64  4723.1  103.58
  4786.9  102.58  4823.3  100.57  4904.6    96.7  4961.7   92.01  4999.8   91.86
  5002.6   91.36  5005.8   91.86  5023.4   93.21  5054.2   92.82  5135.1   95.42
  5297.8   104.1  5321.6  107.53  5417.8  114.52  5437.8  118.36  5472.2  120.88
  5477.8  122.99  5487.8   123.1  5517.8  132.12  5557.8  137.84  5573.2  138.18
#Mann= 12 ,-1 , 0
  3807.7     .08       0  3869.9     .16       0  4115.3     .05       0
  4515.9     .16       0  4552.1     .05       0  4622.9     .08       0
  4723.1     .05       0  4823.3     .16       0  4999.8     .07       0
  5005.8     .16       0  5135.1     .08       0  5321.6      .1       0
Bank Sta=4999.8,5005.8
XS Rating Curve= 0 ,0
Exp/Cntr=0.3,0.1

Type RM Length L Ch R = 1 ,937     ,646,646,646
BEGIN DESCRIPTION:
Mapping XS 4ea35fd0
END DESCRIPTION:
XS GIS Cut Line= 3
      2309561.22     13229901.73      2310595.97     13230832.31
      2311568.21     13230880.92
#Sta/Elev= 30
  3210.8  127.73  3240.9  127.22  3393.7  115.34  3454.8  111.12  3495.2  108.14
  3568.7  106.45  3792.7  103.91  3998.2  104.09  4012.4  105.89  4047.6  104.15
  4483.7  104.41    4610  104.12  4714.3  102.04  4744.4  103.14  4914.6   92.68
  5041.8   91.93  5044.5   91.43  5047.8   91.93  5098.5   96.29  5100.6   96.34
  5184.9  102.91  5198.8  105.73    5215  106.69    5225  113.11    5235  116.56
    5245  125.06    5265  132.05  5327.3  136.56  5505.3   143.9  5575.9  145.01
#Mann= 13 ,-1 , 0
  3210.8      .1       0  3240.9     .08       0  3393.7      .1       0
  3454.8     .16       0  3568.7     .05       0  4483.7     .08       0
    4610     .16       0  5041.8     .07       0  5047.8     .16       0
  5098.5     .12       0  5100.6     .08       0  5198.8     .16       0
  5327.3      .1       0
Bank Sta=5041.8,5047.8
XS Rating Curve= 0 ,0
Exp/Cntr=0.3,0.1

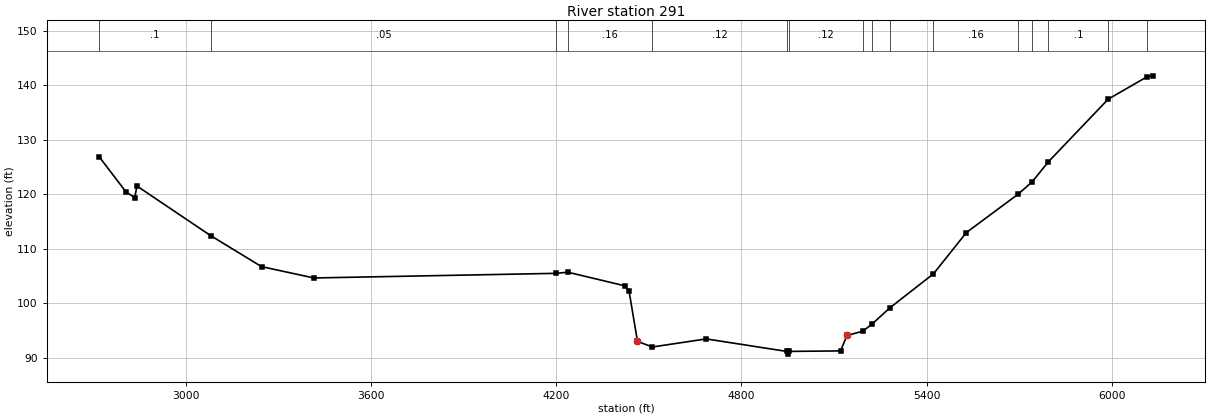
Type RM Length L Ch R = 1 ,291     ,0,0,0
BEGIN DESCRIPTION:
UNT 073 IN LACR 1.0
END DESCRIPTION:
XS GIS Cut Line= 4
      2309207.12     13229915.67      2310408.47     13230998.97
      2311109.86     13231526.75      2311983.14     13231245.44
#Sta/Elev= 30
    2720  126.88  2806.1  120.48  2834.5  119.42    2842  121.54  3080.3  112.46
  3245.6  106.76  3415.2  104.68  4200.8  105.53  4237.7  105.74  4421.8  103.25
  4436.4  102.21  4463.5   93.05  4511.8   92.02  4686.3    93.5  4946.9   91.21
  4949.7   90.71  4952.9   91.21  5121.5    91.3  5142.3   94.14  5192.9    94.9
  5222.6   96.17  5281.4   99.21  5422.4  105.44  5529.3  113.02  5697.8   120.1
  5742.7  122.34  5794.8  125.99  5988.6  137.48  6114.3  141.58  6132.9  141.76
#Mann= 16 ,-1 , 0
    2720      .1       0  3080.3     .05       0  4200.8     .08       0
  4237.7     .16       0  4511.8     .12       0  4946.9     .07       0
  4952.9     .12       0  5192.9     .07       0  5222.6     .12       0
  5281.4     .08       0  5422.4     .16       0  5697.8      .1       0
  5742.7     .16       0  5794.8      .1       0  5988.6     .08       0
  6114.3      .1       0
Bank Sta=4463.5,5142.3
XS Rating Curve= 0 ,0
Exp/Cntr=0.3,0.1

Chan Stop Cuts=-1
Use User Specified Reach Order=0
Composite Channel Slope=5