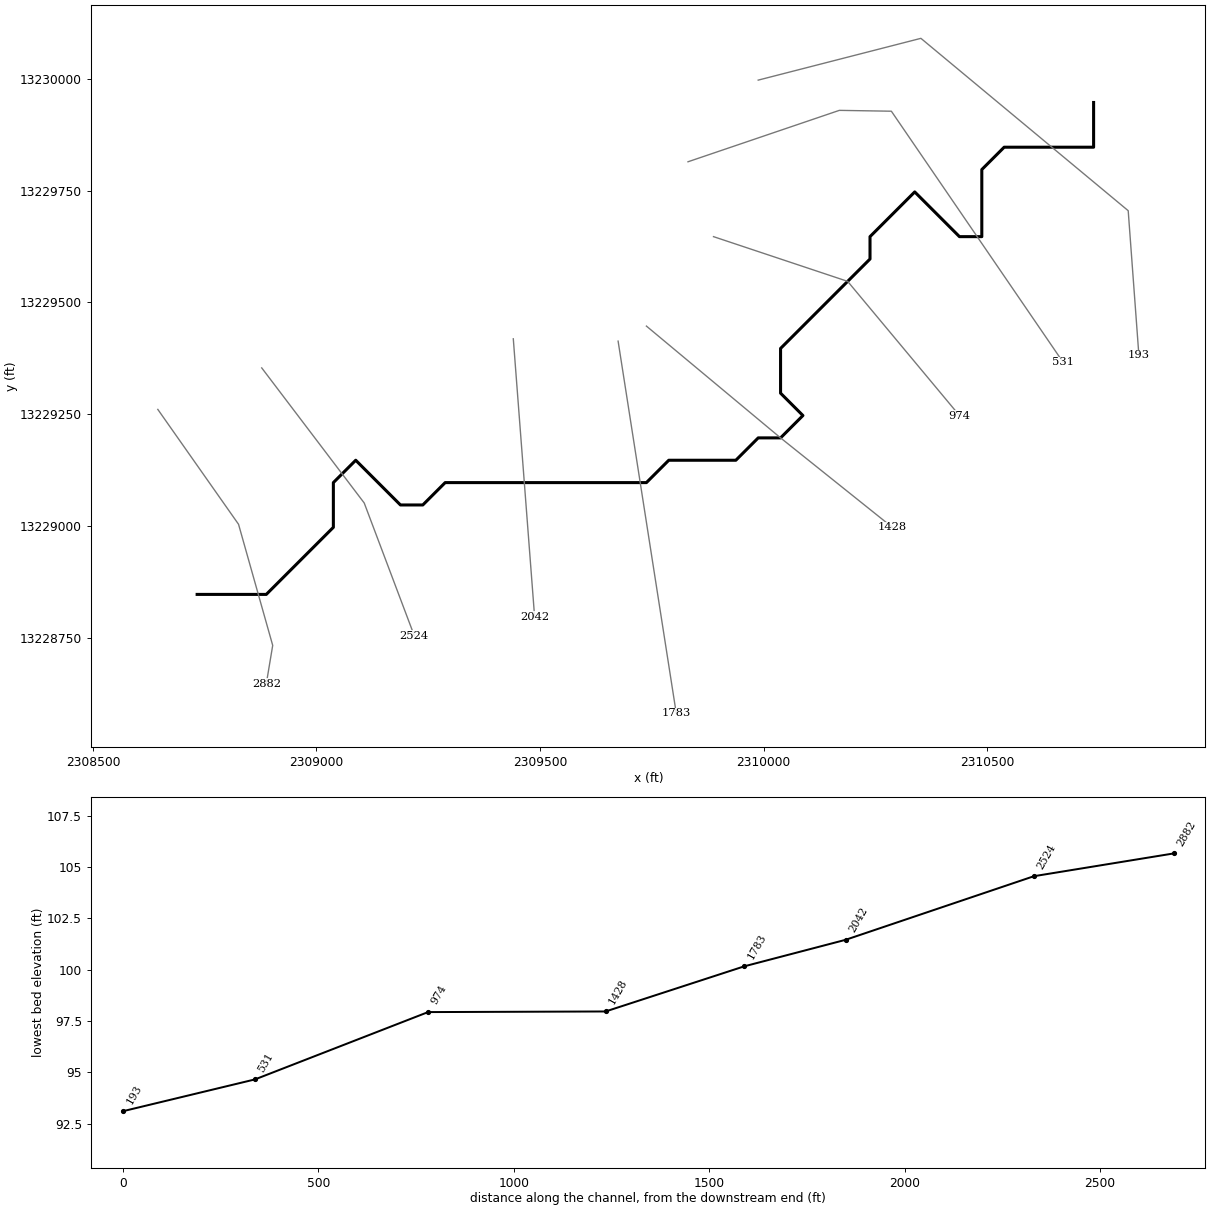
--- UNT 074 IN LACR.prj (project) ---

Proj Title=UNT 074 IN LACR Base Level Engineering
Current Plan=p01
Default Exp/Contr=0.3,0.1
English Units
Geom File=g01
Flow File=f01
Plan File=p01
BEGIN DESCRIPTION:
UNT 074 IN LACR
END DESCRIPTION:

--- UNT 074 IN LACR.p01 (plan) ---

Plan Title=Multiple Run
Short Identifier=Multiple
Geom File=g01
Flow File=f01
Subcritical Flow
K Sum by GR= 0
Std Step Tol= 0.01
Critical Tol= 0.01
Num of Std Step Trials= 20
Max Error Tol= 0.3
Flow Tol Ratio= 0.001
Split Flow NTrial= 30
Split Flow Tol= 0.02
Split Flow Ratio= 0.02
Log Output Level= 0
Friction Slope Method= 1
Unsteady Friction Slope Method= 2
Unsteady Bridges Friction Slope Method= 1
Parabolic Critical Depth
Global Vel Dist=  1 , 1 , 1
Global Log Level= 0
CheckData=True
Encroach Param= -1, 0, 0, 0
BEGIN DESCRIPTION:
Multiple Run
END DESCRIPTION:

--- UNT 074 IN LACR.f01 (steady flow) ---

Flow Title=Multiple
Number of Profiles=7
Profile Names=10-year,25-year,50-year,1pct_min,100-year,1pct_plu,500-year
River Rch & RM= UNT 074 IN LACR,Reach-1,2882
     519     723     892     804    1087    1470    1620
Boundary for River Rch & Prof#=UNT 074 IN LACR,Reach-1,1
Up Type=0
Dn Type=3
Dn Slope=0.005
Boundary for River Rch & Prof#=UNT 074 IN LACR,Reach-1,2
Up Type=0
Dn Type=3
Dn Slope=0.005
Boundary for River Rch & Prof#=UNT 074 IN LACR,Reach-1,3
Up Type=0
Dn Type=3
Dn Slope=0.005
Boundary for River Rch & Prof#=UNT 074 IN LACR,Reach-1,4
Up Type=0
Dn Type=3
Dn Slope=0.005
Boundary for River Rch & Prof#=UNT 074 IN LACR,Reach-1,5
Up Type=0
Dn Type=3
Dn Slope=0.005
Boundary for River Rch & Prof#=UNT 074 IN LACR,Reach-1,6
Up Type=0
Dn Type=3
Dn Slope=0.005
Boundary for River Rch & Prof#=UNT 074 IN LACR,Reach-1,7
Up Type=0
Dn Type=3
Dn Slope=0.005

--- UNT 074 IN LACR.g01 (geometry) ---

Geom Title=Existing Conditions

River Reach=UNT 074 IN LACR,Reach-1
Reach XY= 30
      2308733.08     13228846.85      2308887.72     13228846.85
      2308937.72     13228896.86      2309037.72     13228996.85
      2309037.72     13229096.85      2309087.72     13229146.85
      2309187.72     13229046.86      2309237.72     13229046.86
      2309287.72     13229096.85      2309737.72     13229096.85
      2309787.72     13229146.85      2309937.72     13229146.85
      2309987.72     13229196.85      2310037.72     13229196.85
      2310087.72     13229246.85      2310037.72     13229296.85
      2310037.72     13229396.86      2310087.72     13229446.85
      2310187.72     13229546.86      2310237.72     13229596.85
      2310237.72     13229646.85      2310287.72     13229696.86
      2310337.72     13229746.85      2310387.72     13229696.86
      2310437.72     13229646.85      2310487.72     13229646.85
      2310487.72     13229796.85      2310537.72     13229846.85
      2310737.72     13229846.85      2310737.72     13229946.85

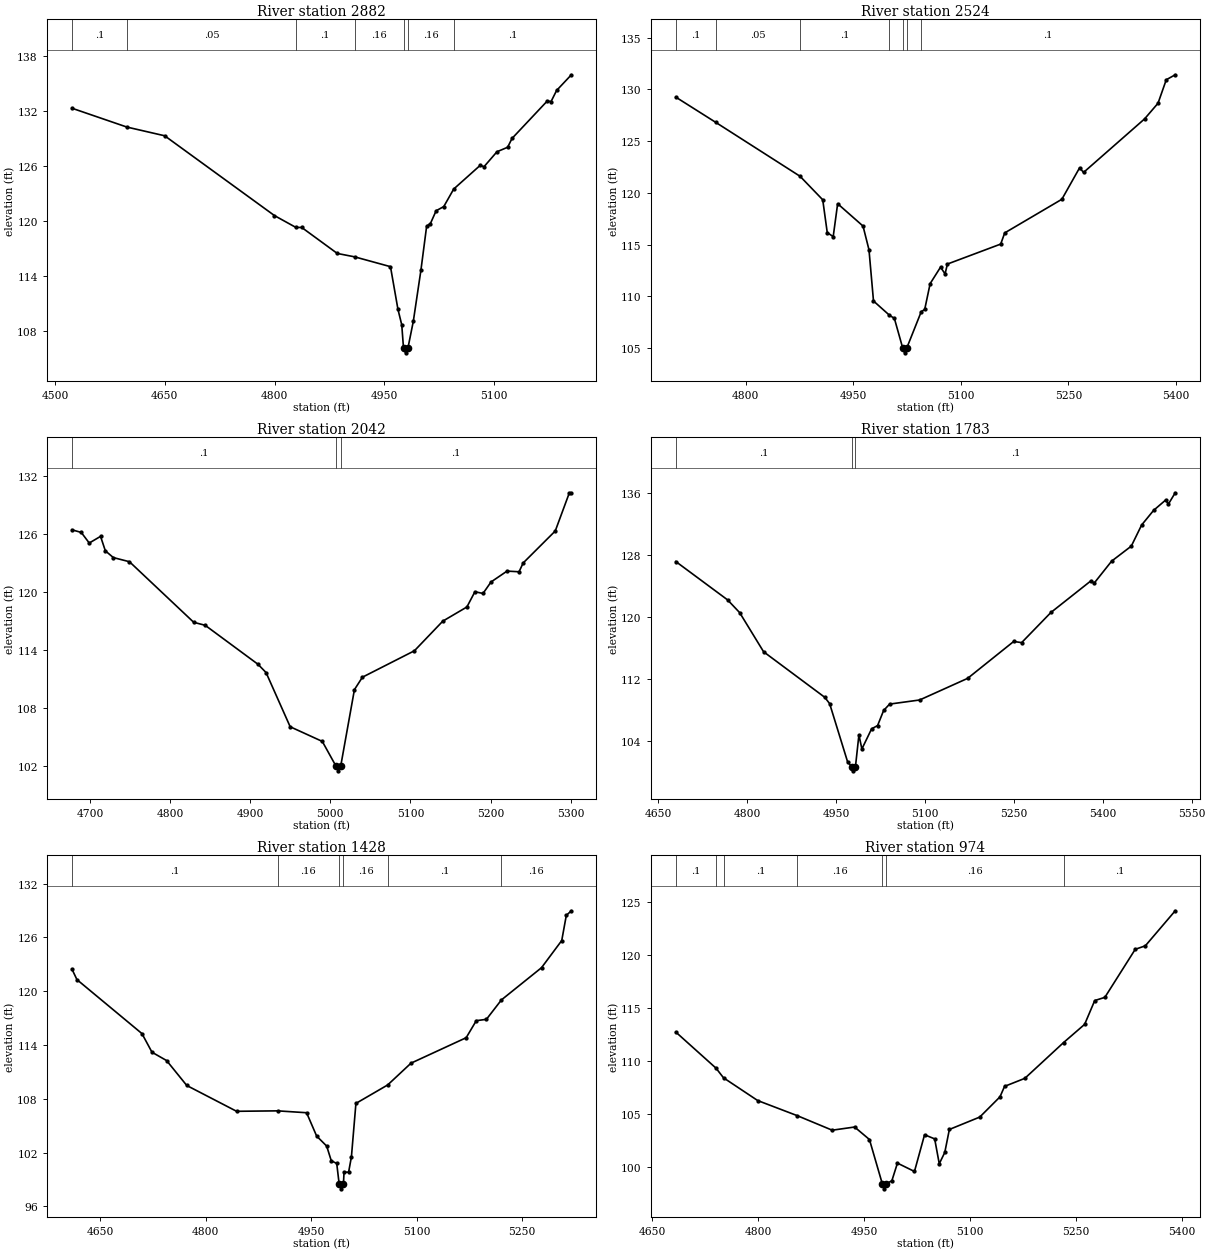
Type RM Length L Ch R = 1,2882,358,358,358
BEGIN DESCRIPTION:
UNT 074 IN LACR 6.0
END DESCRIPTION:
XS GIS Cut Line= 4
      2308645.16     13229260.55      2308825.69     13229003.65
      2308902.08     13228732.81      2308887.73     13228646.89
#Sta/Elev= 30
  4523.1  132.29  4598.1  130.24  4649.8  129.29  4799.9  120.60  4829.2  119.31
  4837.1  119.31  4885.7  116.48  4909.4  116.11  4958.4  115.04  4968.6  110.40
  4973.8  108.71  4976.2  106.16  4979.0  105.66  4982.2  106.16  4989.6  109.09
  5000.0  114.66  5007.8  119.44  5013.0  119.74  5020.8  121.13  5031.2  121.58
  5044.8  123.49  5081.0  126.07  5086.2  125.92  5103.9  127.55  5118.5  128.04
  5124.5  129.00  5172.7  133.08  5177.8  133.01  5185.4  134.22  5205.6  135.93
#Mann=7,-1,0
  4523.1     0.1       0  4598.1    0.05       0  4829.2     0.1       0
  4909.4    0.16       0  4976.2    0.07       0  4982.2    0.16       0
  5044.8     0.1       0
Bank Sta=4976.2,4982.2
Exp/Cntr=0.3,0.1

Type RM Length L Ch R = 1,2524,482,482,482
BEGIN DESCRIPTION:
UNT 074 IN LACR 5.0
END DESCRIPTION:
XS GIS Cut Line= 3
      2308877.54     13229353.35      2309106.74     13229051.23
      2309218.71     13228754.37
#Sta/Elev= 30
  4702.6  129.26  4758.1  126.83  4875.9  121.61  4907.5  119.34  4913.8  116.17
  4922.1  115.78  4928.3  118.96  4963.7  116.80  4972.0  114.51  4978.3  109.56
  5000.6  108.18  5007.4  107.88  5018.9  105.05  5021.7  104.55  5024.9  105.05
  5044.9  108.53  5049.7  108.74  5057.3  111.24  5071.8  112.83  5078.1  112.18
  5081.4  113.13  5155.7  115.06  5161.3  116.14  5241.0  119.39  5265.8  122.44
  5271.2  121.98  5356.4  127.16  5375.1  128.67  5386.6  130.94  5399.1  131.42
#Mann=7,-1,0
  4702.6     0.1       0  4758.1    0.05       0  4875.9     0.1       0
  5000.6    0.16       0  5018.9    0.07       0  5024.9    0.16       0
  5044.9     0.1       0
Bank Sta=5018.9,5024.9
Exp/Cntr=0.3,0.1

Type RM Length L Ch R = 1,2042,259,259,259
BEGIN DESCRIPTION:
UNT 074 IN LACR 4.0
END DESCRIPTION:
XS GIS Cut Line= 2
      2309440.07     13229418.41      2309487.72     13228796.84
#Sta/Elev= 30
  4677.5  126.44  4689.1  126.17  4699.1  125.07  4713.2  125.76  4719.2  124.26
  4729.2  123.56  4749.3  123.13  4829.5  116.85  4843.8  116.54  4909.7  112.50
  4919.8  111.64  4949.9  106.02  4990.0  104.50  5007.0  101.95  5009.8  101.45
  5013.0  101.95  5030.1  109.87  5040.1  111.16  5105.0  113.90  5140.4  116.97
  5170.5  118.44  5180.5  120.02  5190.6  119.84  5200.6  121.03  5220.6  122.16
  5235.6  122.09  5240.7  123.00  5280.8  126.32  5298.4  130.28  5300.9  130.28
#Mann=3,-1,0
  4677.5     0.1       0  5007.0    0.07       0  5013.0     0.1       0
Bank Sta=5007,5013
Exp/Cntr=0.3,0.1

Type RM Length L Ch R = 1,1783,355,355,355
BEGIN DESCRIPTION:
Mapping XS e4eb64c0
END DESCRIPTION:
XS GIS Cut Line= 2
      2309674.44     13229413.22      2309804.51     13228580.82
#Sta/Elev= 30
  4679.8  127.16  4767.2  122.21  4787.5  120.57  4827.9  115.52  4931.0  109.65
  4939.3  108.83  4969.6  101.32  4976.8  100.66  4979.5  100.16  4982.8  100.66
  4988.7  104.80  4993.7  102.98  5010.1  105.58  5020.2  106.00  5030.4  107.95
  5040.5  108.77  5091.1  109.30  5172.1  112.09  5249.8  116.85  5263.2  116.70
  5312.6  120.59  5380.4  124.69  5385.4  124.36  5415.0  127.21  5448.2  129.15
  5465.6  131.87  5485.8  133.76  5505.9  135.08  5510.9  134.59  5522.3  136.03
#Mann=3,-1,0
  4679.8     0.1       0  4976.8    0.07       0  4982.8     0.1       0
Bank Sta=4976.8,4982.8
Exp/Cntr=0.3,0.1

Type RM Length L Ch R = 1,1428,454,454,454
BEGIN DESCRIPTION:
UNT 074 IN LACR 3.0
END DESCRIPTION:
XS GIS Cut Line= 3
      2309737.73     13229446.85      2310037.72     13229196.85
      2310287.75     13228996.83
#Sta/Elev= 30
  4609.5  122.47  4616.6  121.30  4709.1  115.28  4723.4  113.20  4744.2  112.27
  4772.9  109.49  4843.8  106.61  4902.2  106.66  4943.4  106.45  4957.7  103.85
  4972.0  102.73  4978.5  101.10  4986.3  100.79  4989.8   98.46  4992.6   97.96
  4995.8   98.46  4996.7   99.82  5003.2   99.82  5007.2  101.53  5013.6  107.49
  5058.8  109.55  5092.0  111.98  5170.5  114.82  5184.9  116.72  5199.3  116.87
  5220.7  119.04  5277.7  122.63  5306.5  125.66  5313.0  128.47  5320.2  128.98
#Mann=6,-1,0
  4609.5     0.1       0  4902.2    0.16       0  4989.8    0.07       0
  4995.8    0.16       0  5058.8     0.1       0  5220.7    0.16       0
Bank Sta=4989.8,4995.8
Exp/Cntr=0.3,0.1

Type RM Length L Ch R = 1,974,443,443,443
BEGIN DESCRIPTION:
UNT 074 IN LACR 2.0
END DESCRIPTION:
XS GIS Cut Line= 3
      2309887.75     13229646.85      2310187.72     13229546.86
      2310437.71     13229246.86
#Sta/Elev= 30
  4683.8  112.74  4740.7  109.33  4751.3  108.42  4799.7  106.27  4855.8  104.84
  4905.1  103.47  4936.8  103.77  4957.8  102.59  4975.9   98.43  4978.7   97.93
  4981.9   98.43  4989.5   98.69  4997.4  100.36  5021.5   99.57  5035.8  103.04
  5050.1  102.65  5056.6  100.30  5064.4  101.37  5070.9  103.54  5113.9  104.71
  5142.5  106.62  5149.0  107.61  5177.7  108.37  5232.5  111.75  5262.3  113.47
  5276.6  115.72  5290.9  116.02  5333.9  120.56  5348.2  120.89  5390.5  124.20
#Mann=7,-1,0
  4683.8     0.1       0  4740.7    0.16       0  4751.3     0.1       0
  4855.8    0.16       0  4975.9    0.07       0  4981.9    0.16       0
  5232.5     0.1       0
Bank Sta=4975.9,4981.9
Exp/Cntr=0.3,0.1

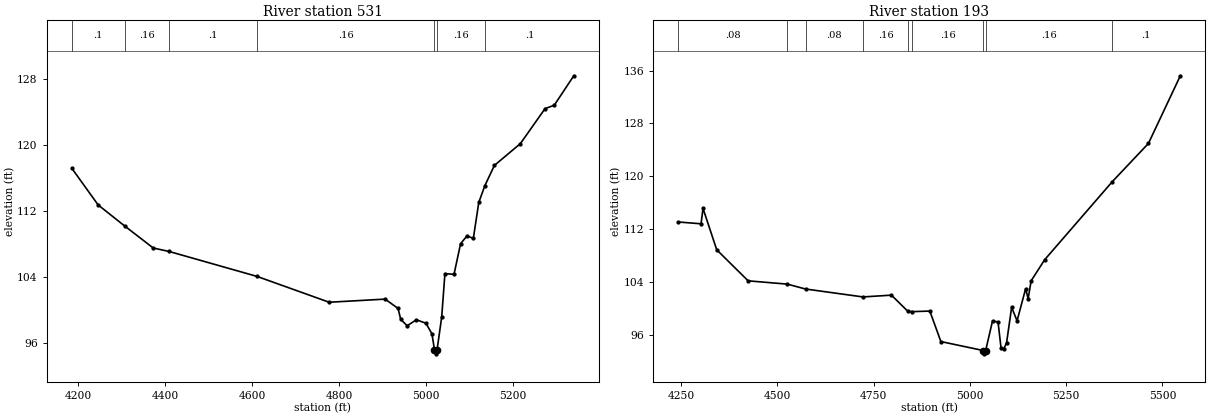
Type RM Length L Ch R = 1,531,338,338,338
BEGIN DESCRIPTION:
Mapping XS 8ef57e6a
END DESCRIPTION:
XS GIS Cut Line= 4
      2309830.72     13229814.26      2310169.16     13229929.23
      2310285.50     13229927.33      2310669.25     13229366.31
#Sta/Elev= 30
  4186.4  117.14  4246.6  112.72  4307.2  110.18  4373.3  107.49  4409.9  107.07
  4612.1  104.04  4777.6  100.91  4906.2  101.29  4936.0  100.16  4942.1   98.82
  4957.0   98.06  4978.0   98.78  5000.0   98.37  5013.8   97.08  5019.7   95.15
  5022.4   94.65  5025.7   95.15  5036.3   99.13  5043.7  104.38  5064.6  104.30
  5079.6  108.00  5094.5  108.97  5109.0  108.65  5121.5  113.02  5135.5  115.06
  5157.5  117.52  5217.0  120.15  5273.9  124.41  5294.9  124.81  5339.9  128.39
#Mann=7,-1,0
  4186.4     0.1       0  4307.2    0.16       0  4409.9     0.1       0
  4612.1    0.16       0  5019.7    0.07       0  5025.7    0.16       0
  5135.5     0.1       0
Bank Sta=5019.7,5025.7
Exp/Cntr=0.3,0.1

Type RM Length L Ch R = 1,193,0,0,0
BEGIN DESCRIPTION:
UNT 074 IN LACR 1.0
END DESCRIPTION:
XS GIS Cut Line= 4
      2309987.70     13229996.85      2310351.53     13230090.29
      2310815.07     13229704.88      2310838.99     13229381.43
#Sta/Elev= 30
  4243.6  113.07  4302.2  112.80  4307.3  115.13  4342.9  108.86  4424.4  104.16
  4526.2  103.66  4573.4  102.92  4722.5  101.72  4796.4  101.99  4839.3   99.53
  4849.7   99.49  4896.1   99.58  4924.8   94.96  5035.0   93.60  5037.8   93.10
  5041.0   93.60  5058.9   98.09  5073.2   97.92  5081.0   93.98  5087.5   93.78
  5095.3   94.75  5108.5  100.15  5122.6   98.10  5144.8  102.96  5151.3  101.44
  5159.1  104.16  5194.3  107.36  5369.8  119.18  5463.6  124.97  5546.4  135.22
#Mann=9,-1,0
  4243.6    0.08       0  4526.2    0.05       0  4573.4    0.08       0
  4722.5    0.16       0  4839.3     0.1       0  4849.7    0.16       0
  5035.0    0.07       0  5041.0    0.16       0  5369.8     0.1       0
Bank Sta=5035,5041
Exp/Cntr=0.3,0.1

Chan Stop Cuts=-1