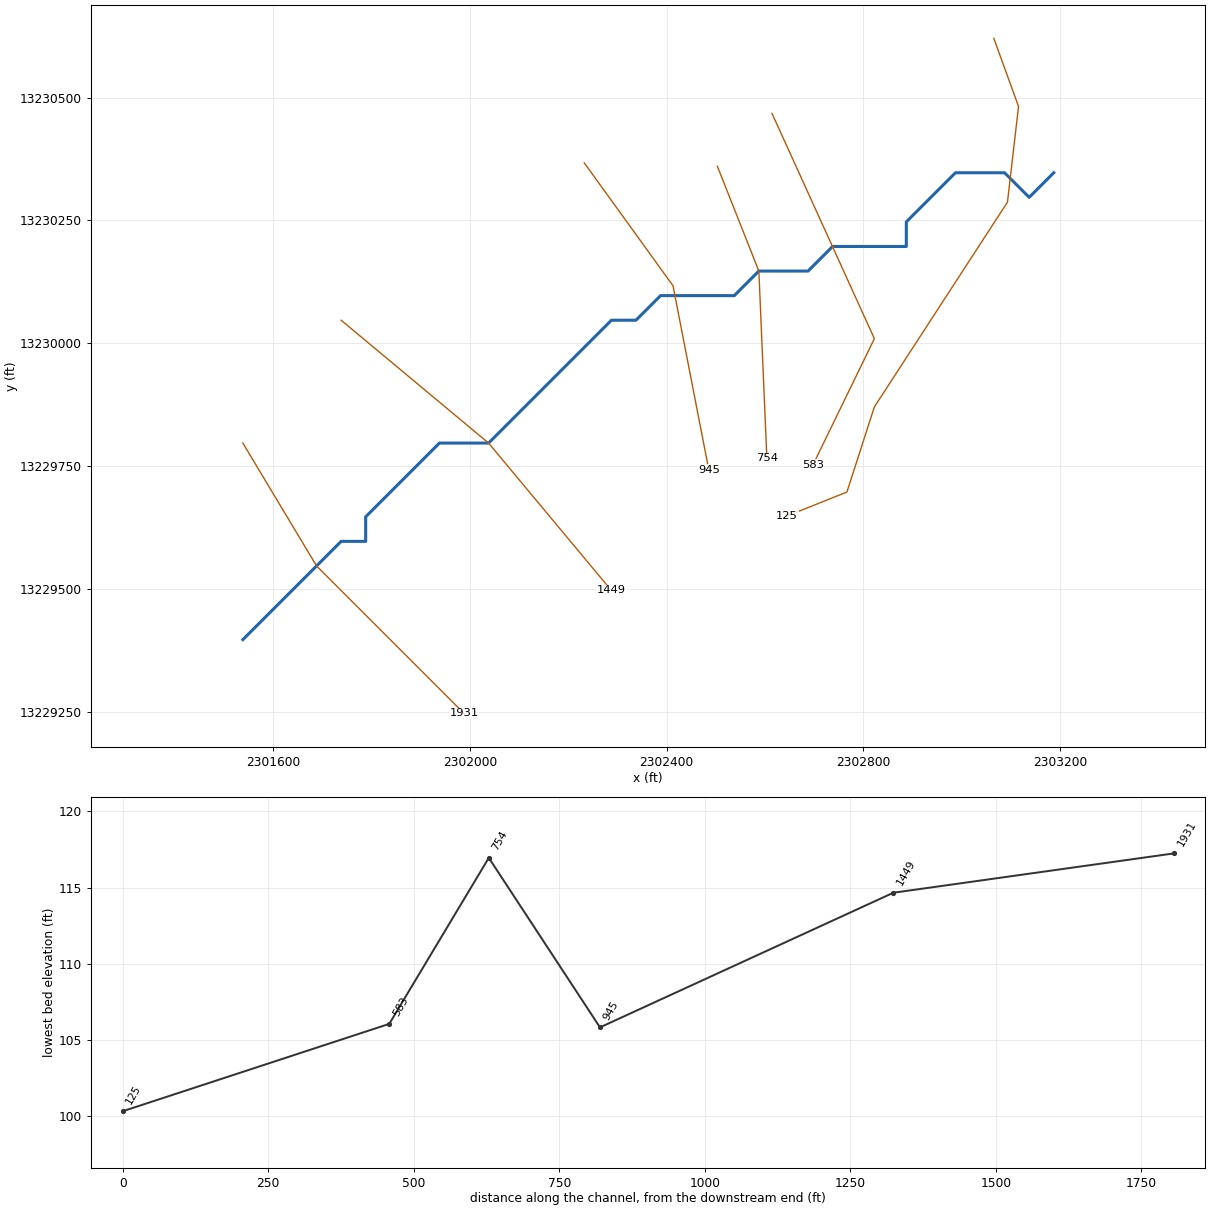
--- UNT 075 IN LACR.prj (project) ---

Proj Title=UNT 075 IN LACR Base Level Engineering
Current Plan=p01
Default Exp/Contr=0.3,0.1
English Units
Geom File=g01
Flow File=f01
Plan File=p01
Y Axis Title=Elevation
X Axis Title(PF)=Main Channel Distance
X Axis Title(XS)=Station
BEGIN DESCRIPTION:
UNT 075 IN LACR
END DESCRIPTION:
DSS Export Rating Curves= 0
DSS Export Rating Curve Sorted= 0
DSS Export Volume Flow Curves= 0
DXF OffsetX= 0
DXF OffsetY= 0
DXF ScaleX= 1
DXF ScaleY= 10

--- UNT 075 IN LACR.p01 (plan) ---

Plan Title=Multiple Run
Short Identifier=Multiple
Geom File=g01
Flow File=f01
Subcritical Flow
K Sum by GR= 0
Std Step Tol= 0.01
Critical Tol= 0.01
Num of Std Step Trials= 20
Max Error Tol= 0.3
Flow Tol Ratio= 0.001
Split Flow NTrial= 30
Split Flow Tol= 0.02
Split Flow Ratio= 0.02
Log Output Level= 0
Friction Slope Method= 1
Unsteady Friction Slope Method= 2
Unsteady Bridges Friction Slope Method= 1
Parabolic Critical Depth
Global Vel Dist=  1 , 1 , 1
Global Log Level= 0
CheckData=True
Encroach Param= -1, 0, 0, 0
BEGIN DESCRIPTION:
Multiple Run
END DESCRIPTION:

--- UNT 075 IN LACR.f01 (steady flow) ---

Flow Title=Multiple
Number of Profiles=7
Profile Names=10-year,25-year,50-year,1pct_min,100-year,1pct_plu,500-year
River Rch & RM= UNT 075 IN LACR,Reach-1,1931
     424     582     711     634     857    1159    1251
River Rch & RM= UNT 075 IN LACR,Reach-1,125
    5047    7553    9794    9264   12528   16943   20782
Boundary for River Rch & Prof#=UNT 075 IN LACR,Reach-1,1
Up Type=0
Dn Type=3
Dn Slope=0.005
Boundary for River Rch & Prof#=UNT 075 IN LACR,Reach-1,2
Up Type=0
Dn Type=3
Dn Slope=0.005
Boundary for River Rch & Prof#=UNT 075 IN LACR,Reach-1,3
Up Type=0
Dn Type=3
Dn Slope=0.005
Boundary for River Rch & Prof#=UNT 075 IN LACR,Reach-1,4
Up Type=0
Dn Type=3
Dn Slope=0.005
Boundary for River Rch & Prof#=UNT 075 IN LACR,Reach-1,5
Up Type=0
Dn Type=3
Dn Slope=0.005
Boundary for River Rch & Prof#=UNT 075 IN LACR,Reach-1,6
Up Type=0
Dn Type=3
Dn Slope=0.005
Boundary for River Rch & Prof#=UNT 075 IN LACR,Reach-1,7
Up Type=0
Dn Type=3
Dn Slope=0.005

--- UNT 075 IN LACR.g01 (geometry) ---

Geom Title=Existing Conditions
Program Version=4.10

River Reach=UNT 075 IN LACR ,Reach-1
Reach XY= 28
      2301537.72     13229396.86      2301587.72     13229446.85
      2301637.72     13229496.85      2301687.72     13229546.86
      2301737.72     13229596.85      2301787.72     13229596.85
      2301787.72     13229646.85      2301837.72     13229696.86
      2301887.72     13229746.85      2301937.72     13229796.85
      2302037.72     13229796.85      2302087.72     13229846.85
      2302137.72     13229896.86      2302187.72     13229946.85
      2302237.72     13229996.85      2302287.72     13230046.86
      2302337.72     13230046.86      2302387.72     13230096.85
      2302537.72     13230096.85      2302587.72     13230146.85
      2302687.72     13230146.85      2302737.72     13230196.86
      2302887.72     13230196.86      2302887.72     13230246.85
      2302987.72     13230346.85      2303087.72     13230346.85
      2303137.72     13230296.85      2303187.72     13230346.85

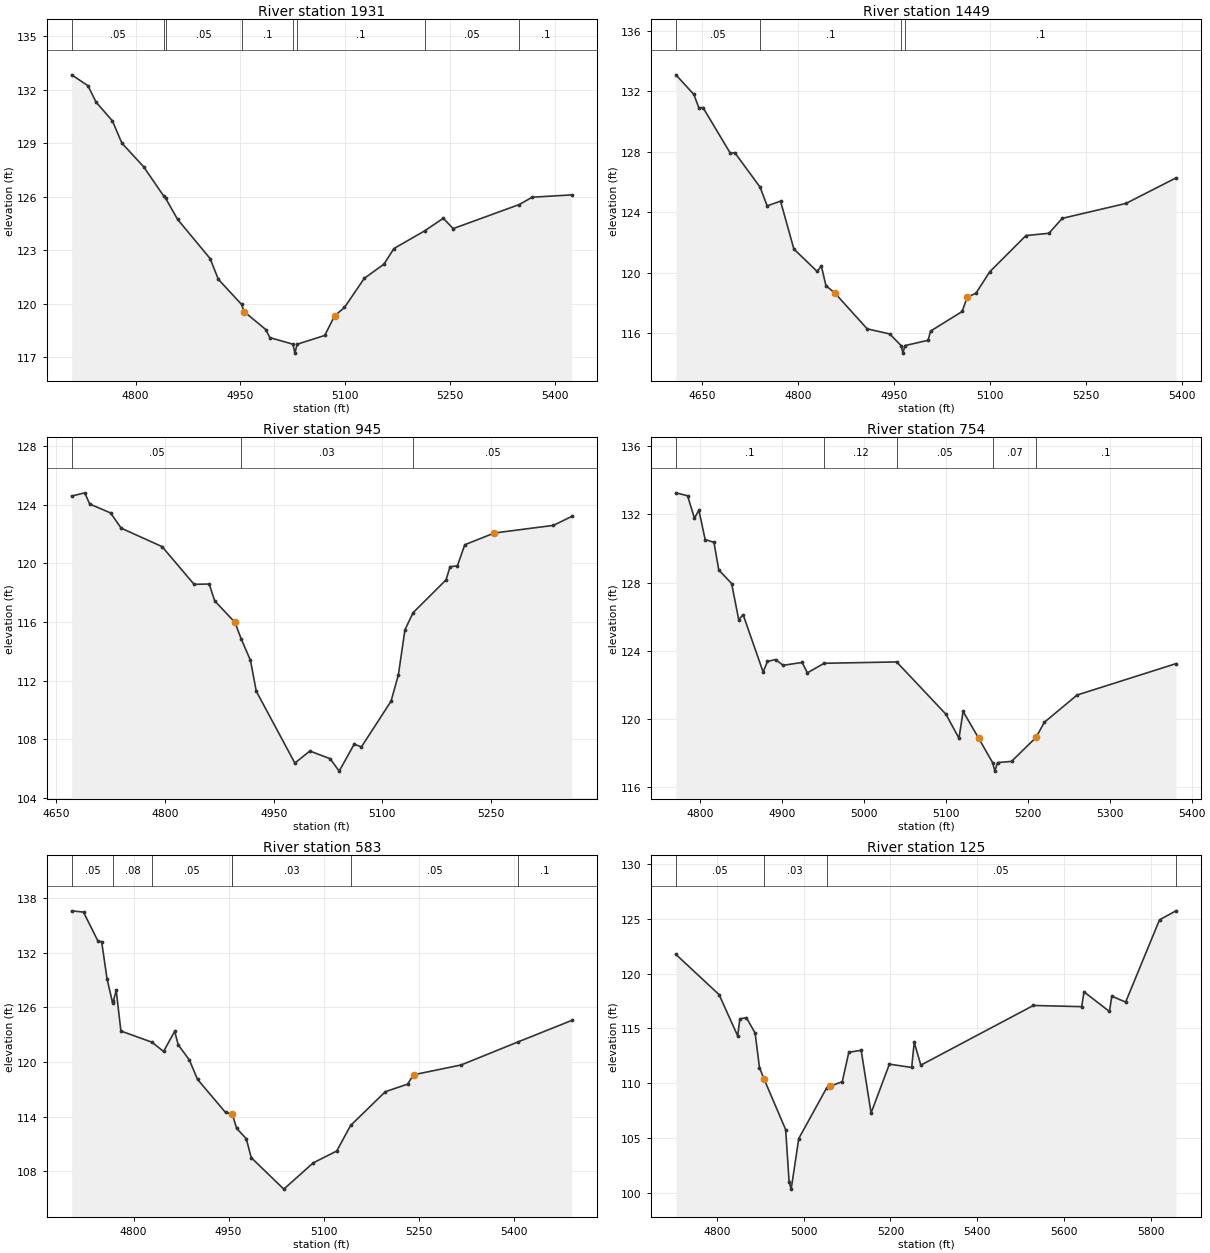
Type RM Length L Ch R = 1 ,1931    ,482,482,482
BEGIN DESCRIPTION:
UNT 075 IN LACR 3.0
END DESCRIPTION:
XS GIS Cut Line= 3
      2301537.74     13229796.81      2301687.72     13229546.86
      2301987.75     13229246.83
#Sta/Elev= 30
  4708.5  132.84  4731.8  132.23  4743.4  131.31  4766.8  130.26  4780.4  129.01
  4811.5  127.69    4840  126.06  4842.9  125.93  4860.1  124.74  4906.7  122.54
  4918.4  121.38  4951.7  119.97  4955.3  119.57  4986.4  118.56  4992.2  118.11
  5025.3  117.74    5028  117.24  5031.3  117.74  5070.7  118.23  5084.9  119.33
    5099   119.8  5127.3  121.43  5155.6  122.23  5169.7   123.1  5213.6  124.09
  5240.4   124.8  5254.6  124.22  5349.2  125.57  5367.7  125.98  5424.3  126.11
#Mann= 8 ,-1 , 0
  4708.5     .05       0    4840      .1       0  4842.9     .05       0
  4951.7      .1       0  5025.3     .07       0  5031.3      .1       0
  5213.6     .05       0  5349.2      .1       0
Bank Sta=4955.3,5084.9
XS Rating Curve= 0 ,0
Exp/Cntr=0.3,0.1

Type RM Length L Ch R = 1 ,1449    ,504,504,504
BEGIN DESCRIPTION:
UNT 075 IN LACR 2.0
END DESCRIPTION:
XS GIS Cut Line= 3
      2301737.73     13230046.85      2302037.72     13229796.85
      2302287.71     13229496.86
#Sta/Elev= 30
  4609.5   133.1  4637.5   131.8  4645.3  130.92  4651.8  130.93  4694.7  127.89
  4701.3  127.95  4740.9  125.66    4752  124.42  4772.9  124.73  4793.7  121.56
  4830.1  120.07  4836.6  120.44  4843.8  119.13  4857.5  118.65  4908.2  116.27
  4943.4  115.93  4961.2  115.16    4964  114.66  4967.2  115.16  5003.3  115.51
  5007.2  116.12  5056.6  117.42  5064.4  118.37  5078.1  118.63  5099.6  120.05
  5156.2  122.45    5192   122.6  5212.8  123.59  5312.4  124.58  5390.5  126.27
#Mann= 4 ,-1 , 0
  4609.5     .05       0  4740.9      .1       0  4961.2     .07       0
  4967.2      .1       0
Bank Sta=4857.5,5064.4
XS Rating Curve= 0 ,0
Exp/Cntr=0.3,0.1

Type RM Length L Ch R = 1 ,945     ,191,191,191
BEGIN DESCRIPTION:
Mapping XS fc73aab2
END DESCRIPTION:
XS GIS Cut Line= 3
      2302232.43     13230366.99      2302413.01     13230116.95
      2302485.94      13229741.9
#Sta/Elev= 30
  4671.1  124.59  4689.2  124.81  4695.9  124.05  4724.8  123.44  4739.5   122.4
    4796  121.14  4840.1  118.57    4861  118.59  4868.6  117.44  4896.5  115.98
  4905.1  114.86    4918  113.38    4926  111.28  4979.3  106.38    5000   107.2
  5027.9  106.68  5040.5  105.83  5061.1  107.66  5071.3  107.49  5112.1   110.6
  5122.2  112.39  5131.3  115.47  5142.6  116.64    5188  118.87  5193.6  119.77
  5203.7  119.83  5213.9  121.27  5254.7  122.07  5336.2  122.59  5361.6   123.2
#Mann= 3 ,-1 , 0
  4671.1     .05       0  4905.1     .03       0  5142.6     .05       0
Bank Sta=4896.5,5254.7
XS Rating Curve= 0 ,0
Exp/Cntr=0.3,0.1

Type RM Length L Ch R = 1 ,754     ,171,171,171
BEGIN DESCRIPTION:
Mapping XS 95959b87
END DESCRIPTION:
XS GIS Cut Line= 3
      2302503.28     13230360.04      2302587.72     13230146.85
      2302603.98      13229766.3
#Sta/Elev= 30
  4770.7  133.26  4784.9  133.09  4793.3  131.77  4798.7  132.24  4806.4  130.52
  4817.1  130.36    4823  128.74  4838.7  127.94  4847.3  125.83  4852.7  126.12
  4877.1  122.76  4882.4  123.38  4892.4  123.49  4901.4  123.15  4924.7  123.32
  4931.1  122.71  4951.6  123.27    5040  123.35  5100.1  120.29  5116.1  118.88
  5121.1  120.45  5140.1  118.88  5157.1  117.45  5159.9  116.95  5163.1  117.45
  5180.2  117.52  5210.2  118.93  5220.2  119.81  5260.2  121.41  5380.9  123.25
#Mann= 5 ,-1 , 0
  4770.7      .1       0  4951.6     .12       0    5040     .05       0
  5157.1     .07       0  5210.2      .1       0
Bank Sta=5140.1,5210.2
XS Rating Curve= 0 ,0
Exp/Cntr=0.3,0.1

Type RM Length L Ch R = 1 ,583     ,458,458,458
BEGIN DESCRIPTION:
Mapping XS 3a421e63
END DESCRIPTION:
XS GIS Cut Line= 3
      2302614.41     13230467.62      2302822.74     13230009.31
      2302697.72     13229752.34
#Sta/Elev= 30
  4702.4  136.58  4721.1  136.44  4744.2  133.22  4749.7  133.21  4758.2  129.13
  4767.2  126.43  4768.3  126.71  4772.7  127.85  4780.1   123.4  4829.2  122.17
  4847.4  121.16    4865  123.37  4870.5  121.89  4888.1  120.23    4901   118.1
  4945.2  114.47  4955.9  114.27  4962.8  112.72  4977.9   111.6  4985.8  109.51
  5037.2  106.06  5083.6  108.94  5120.7  110.24  5142.6  113.04  5197.5  116.75
  5232.5  117.57  5241.9   118.6  5317.2  119.68  5407.4  122.22  5491.6  124.56
#Mann= 7 ,-1 , 0
  4702.4     .05       0  4768.3     .08       0  4829.2     .05       0
  4955.9      .1       0  4955.9     .03       0  5142.6     .05       0
  5407.4      .1       0
Bank Sta=4955.9,5241.9
XS Rating Curve= 0 ,0
Exp/Cntr=0.3,0.1

Type RM Length L Ch R = 1 ,125     ,0,0,0
BEGIN DESCRIPTION:
UNT 075 IN LACR 1.0
END DESCRIPTION:
XS GIS Cut Line= 6
       2303065.8     13230620.39       2303116.1      13230481.8
      2303093.57     13230287.09      2302822.74     13229870.42
      2302766.87      13229697.2      2302645.34     13229648.59
#Sta/Elev= 30
  4705.2  121.76  4804.7  118.09  4847.7  114.32  4852.6  115.87  4867.7  115.99
  4887.8  114.58  4897.9  111.43  4907.9  110.43  4958.3  105.76  4966.2  101.01
    4971  100.33  4988.5  104.95  5052.5  109.55  5060.9  109.73  5088.8  110.14
  5103.9  112.82  5132.4  113.01  5155.3  107.28  5197.5  111.74  5248.9  111.44
  5254.8  113.74    5270  111.65  5529.6   117.1    5641  116.99  5646.3  118.34
  5705.1  116.55  5710.4  117.95  5742.4  117.41  5820.5  124.92  5858.5  125.74
#Mann= 4 ,-1 , 0
  4705.2     .05       0  4907.9     .03       0  5052.5     .05       0
  5858.5      .1       0
Bank Sta=4907.9,5060.9
XS Rating Curve= 0 ,0
Exp/Cntr=0.3,0.1

Chan Stop Cuts=-1
Use User Specified Reach Order=0
Composite Channel Slope=5