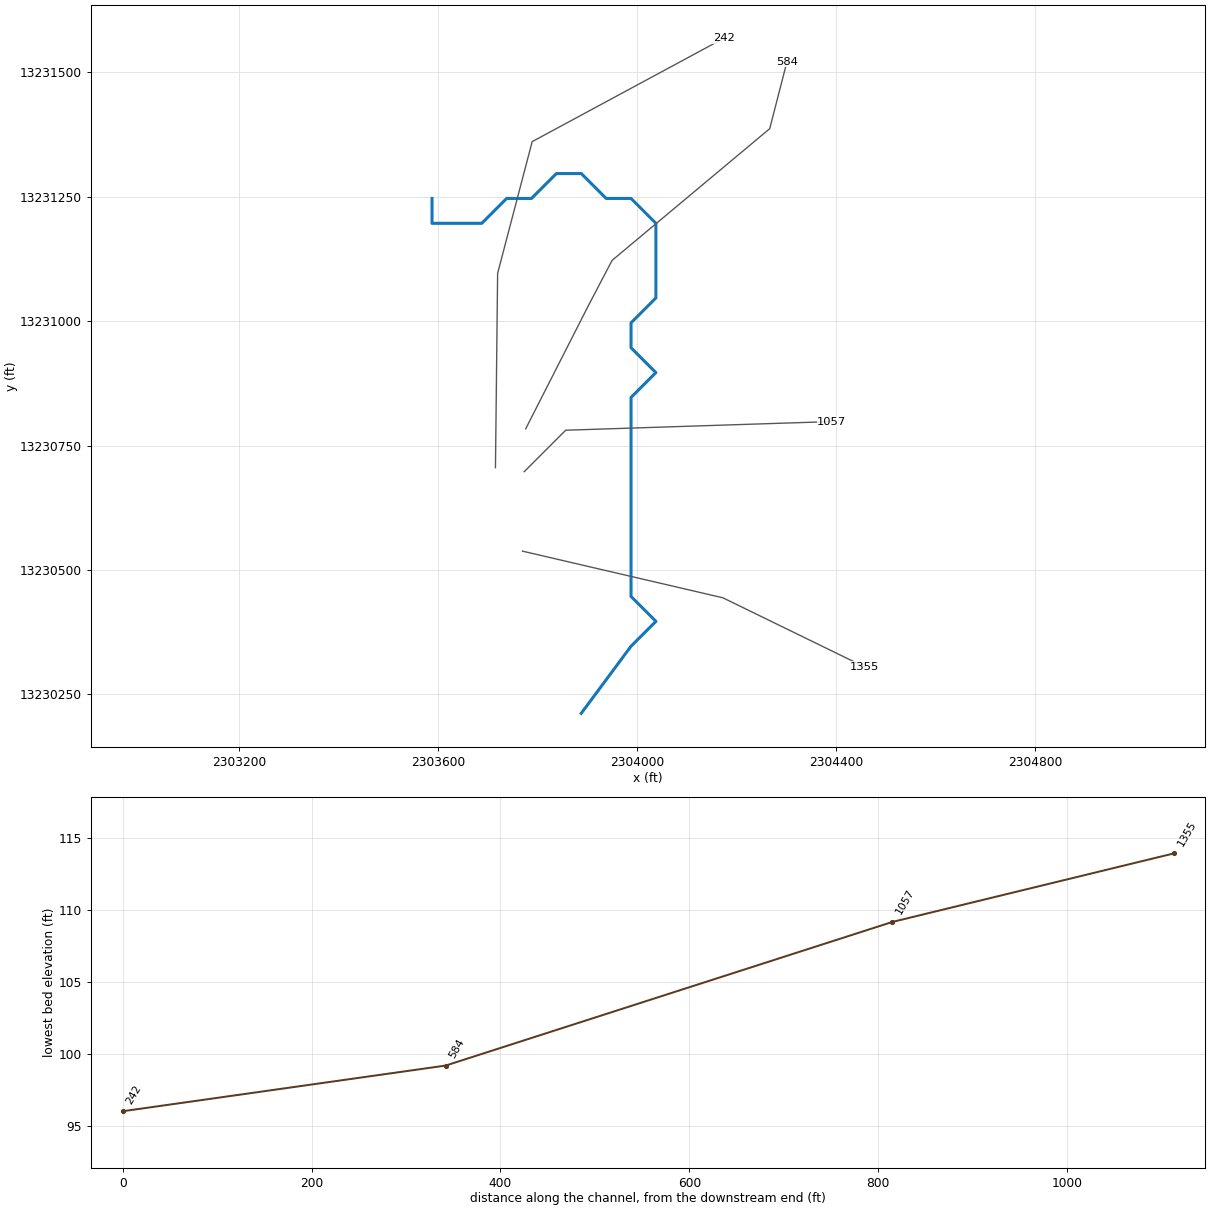
--- UNT 076 IN LACR.prj (project) ---

Proj Title=UNT 076 IN LACR Base Level Engineering
Current Plan=p01
Default Exp/Contr=0.3,0.1
English Units
Geom File=g01
Flow File=f01
Plan File=p01
BEGIN DESCRIPTION:
UNT 076 IN LACR
END DESCRIPTION:

--- UNT 076 IN LACR.p01 (plan) ---

Plan Title=Multiple Run
Short Identifier=Multiple
Geom File=g01
Flow File=f01
Subcritical Flow
K Sum by GR= 0
Std Step Tol= 0.01
Critical Tol= 0.01
Num of Std Step Trials= 20
Max Error Tol= 0.3
Flow Tol Ratio= 0.001
Split Flow NTrial= 30
Split Flow Tol= 0.02
Split Flow Ratio= 0.02
Log Output Level= 0
Friction Slope Method= 1
Unsteady Friction Slope Method= 2
Unsteady Bridges Friction Slope Method= 1
Parabolic Critical Depth
Global Vel Dist=  1 , 1 , 1
Global Log Level= 0
CheckData=True
Encroach Param= -1, 0, 0, 0
BEGIN DESCRIPTION:
Multiple Run
END DESCRIPTION:

--- UNT 076 IN LACR.f01 (steady flow) ---

Flow Title=Multiple
Number of Profiles=7
Profile Names=10-year,25-year,50-year,1pct_min,100-year,1pct_plu,500-year
River Rch & RM= UNT 076 IN LACR,Reach-1,1355
     162     211     248     216     291     394     401
Boundary for River Rch & Prof#=UNT 076 IN LACR,Reach-1,1
Up Type=0
Dn Type=3
Dn Slope=0.005
Boundary for River Rch & Prof#=UNT 076 IN LACR,Reach-1,2
Up Type=0
Dn Type=3
Dn Slope=0.005
Boundary for River Rch & Prof#=UNT 076 IN LACR,Reach-1,3
Up Type=0
Dn Type=3
Dn Slope=0.005
Boundary for River Rch & Prof#=UNT 076 IN LACR,Reach-1,4
Up Type=0
Dn Type=3
Dn Slope=0.005
Boundary for River Rch & Prof#=UNT 076 IN LACR,Reach-1,5
Up Type=0
Dn Type=3
Dn Slope=0.005
Boundary for River Rch & Prof#=UNT 076 IN LACR,Reach-1,6
Up Type=0
Dn Type=3
Dn Slope=0.005
Boundary for River Rch & Prof#=UNT 076 IN LACR,Reach-1,7
Up Type=0
Dn Type=3
Dn Slope=0.005

--- UNT 076 IN LACR.g01 (geometry) ---

Geom Title=Existing Conditions

River Reach=UNT 076 IN LACR,Reach-1
Reach XY= 29
      2303887.60     13230211.85      2303987.72     13230346.85
      2304037.72     13230396.85      2303987.72     13230446.85
      2303987.72     13230496.85      2303987.72     13230546.86
      2303987.72     13230596.85      2303987.72     13230646.85
      2303987.72     13230696.86      2303987.72     13230746.85
      2303987.72     13230796.85      2303987.72     13230846.86
      2304037.72     13230896.85      2303987.72     13230946.85
      2303987.72     13230996.85      2304037.72     13231046.86
      2304037.72     13231096.85      2304037.72     13231146.85
      2304037.72     13231196.86      2303987.72     13231246.85
      2303937.72     13231246.85      2303887.72     13231296.85
      2303837.72     13231296.85      2303787.72     13231246.85
      2303737.72     13231246.85      2303687.72     13231196.86
      2303637.72     13231196.86      2303587.72     13231196.86
      2303587.72     13231246.85

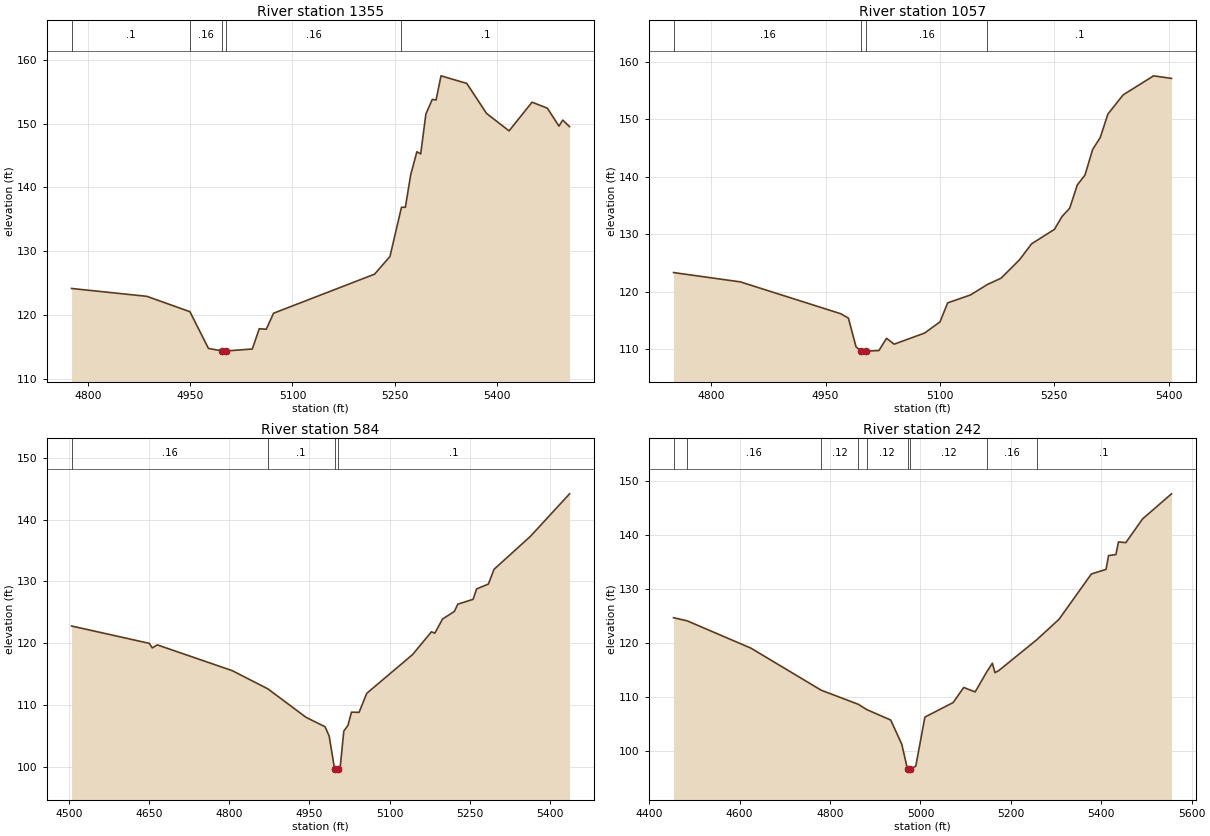
Type RM Length L Ch R = 1,1355,298,298,298
BEGIN DESCRIPTION:
UNT 076 IN LACR 2.0
END DESCRIPTION:
XS GIS Cut Line= 3
      2303769.55     13230537.93      2304172.36     13230444.18
      2304457.11     13230305.27
#Sta/Elev= 30
  4776.0  124.22  4886.5  122.99  4949.6  120.59  4976.8  114.85  4997.0  114.46
  4999.8  113.96  5003.0  114.46  5041.1  114.76  5051.3  117.93  5061.6  117.85
  5072.2  120.35  5220.5  126.46  5243.0  129.22  5259.9  136.91  5265.6  136.91
  5273.4  141.98  5282.5  145.59  5288.1  145.25  5295.7  151.48  5305.1  153.77
  5310.6  153.67  5317.9  157.45  5355.7  156.26  5384.7  151.57  5417.7  148.85
  5451.4  153.33  5473.9  152.39  5490.9  149.59  5496.4  150.53  5506.4  149.51
#Mann=5,-1,0
  4776.0     0.1       0  4949.6    0.16       0  4997.0    0.07       0
  5003.0    0.16       0  5259.9     0.1       0
Bank Sta=4997,5003
Exp/Cntr=0.3,0.1

Type RM Length L Ch R = 1,1057,473,473,473
BEGIN DESCRIPTION:
Mapping XS f9dc13c0
END DESCRIPTION:
XS GIS Cut Line= 3
      2303773.02     13230697.62      2303856.38     13230780.98
      2304391.11     13230798.34
#Sta/Elev= 30
  4750.7  123.37  4838.3  121.75  4970.0  116.21  4980.0  115.45  4990.0  110.45
  4997.0  109.69  4999.7  109.19  5003.0  109.69  5020.0  109.82  5030.0  111.94
  5040.0  110.92  5080.0  112.86  5100.1  114.80  5110.1  118.10  5140.1  119.48
  5162.3  121.30  5180.1  122.39  5204.4  125.60  5220.1  128.36  5250.1  130.88
  5260.1  133.12  5270.1  134.55  5280.1  138.60  5290.2  140.32  5300.2  144.76
  5310.2  146.85  5320.2  150.92  5340.2  154.26  5380.2  157.57  5403.6  157.12
#Mann=4,-1,0
  4750.7    0.16       0  4997.0    0.07       0  5003.0    0.16       0
  5162.3     0.1       0
Bank Sta=4997,5003
Exp/Cntr=0.3,0.1

Type RM Length L Ch R = 1,584,342,342,342
BEGIN DESCRIPTION:
Mapping XS 3b17872b
END DESCRIPTION:
XS GIS Cut Line= 5
      2303776.00     13230783.74      2303901.87     13231031.16
      2303949.62     13231122.30      2304266.46     13231387.06
      2304301.17     13231521.57
#Sta/Elev= 30
  4504.7  122.80  4650.1  120.00  4655.8  119.27  4665.3  119.75  4805.7  115.58
  4872.3  112.64  4944.1  108.02  4979.3  106.53  4987.0  105.02  4997.1   99.69
  4999.8   99.19  5003.1   99.69  5007.9  100.23  5014.4  105.82  5022.2  106.75
  5028.7  108.88  5043.0  108.85  5057.3  111.92  5143.2  118.19  5178.4  121.86
  5184.9  121.65  5199.2  123.93  5221.3  125.15  5227.8  126.33  5256.4  127.11
  5263.0  128.79  5285.1  129.58  5295.6  131.96  5364.1  137.32  5437.0  144.16
#Mann=4,-1,0
  4504.7    0.16       0  4872.3     0.1       0  4997.1    0.07       0
  5003.1     0.1       0
Bank Sta=4997.1,5003.1
Exp/Cntr=0.3,0.1

Type RM Length L Ch R = 1,242,0,0,0
BEGIN DESCRIPTION:
UNT 076 IN LACR 1.0
END DESCRIPTION:
XS GIS Cut Line= 4
      2303715.24     13230705.67      2303719.58     13231096.26
      2303789.03     13231361.02      2304173.98     13231568.64
#Sta/Elev= 30
  4453.7  124.68  4483.9  124.10  4624.9  119.03  4780.4  111.22  4862.6  108.60
  4880.7  107.64  4934.2  105.68  4958.6  101.21  4971.5   96.51  4974.3   96.01
  4977.5   96.51  4989.7   97.13  5009.8  106.23  5072.4  108.93  5095.7  111.73
  5121.0  110.90  5147.2  114.70  5159.1  116.23  5164.8  114.48  5173.3  114.86
  5257.0  120.57  5306.7  124.40  5378.1  132.80  5410.5  133.65  5416.2  136.22
  5432.4  136.40  5438.1  138.75  5454.3  138.62  5491.5  143.03  5555.4  147.68
#Mann=9,-1,0
  4453.7     0.1       0  4483.9    0.16       0  4780.4    0.12       0
  4862.6    0.16       0  4880.7    0.12       0  4971.5    0.07       0
  4977.5    0.12       0  5147.2    0.16       0  5257.0     0.1       0
Bank Sta=4971.5,4977.5
Exp/Cntr=0.3,0.1

Chan Stop Cuts=-1