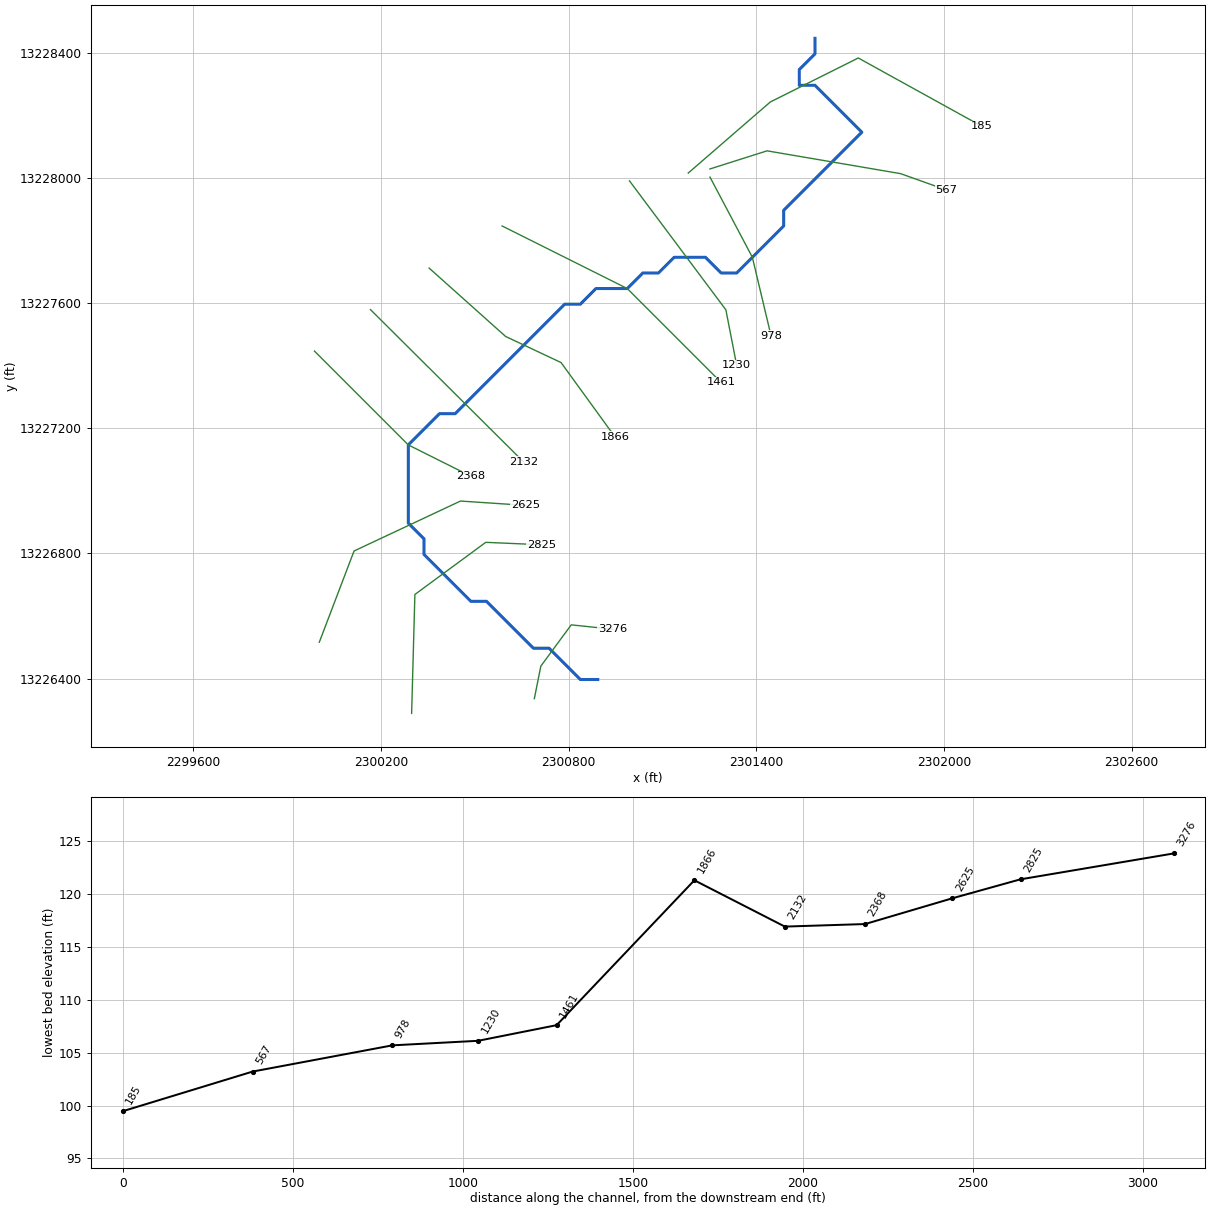
--- UNT 082 IN LACR.prj (project) ---

Proj Title=UNT 082 IN LACR Base Level Engineering
Current Plan=p01
Default Exp/Contr=0.3,0.1
English Units
Geom File=g01
Flow File=f01
Plan File=p01
BEGIN DESCRIPTION:
UNT 082 IN LACR
END DESCRIPTION:

--- UNT 082 IN LACR.p01 (plan) ---

Plan Title=Multiple Run
Short Identifier=Multiple
Geom File=g01
Flow File=f01
Subcritical Flow
K Sum by GR= 0
Std Step Tol= 0.01
Critical Tol= 0.01
Num of Std Step Trials= 20
Max Error Tol= 0.3
Flow Tol Ratio= 0.001
Split Flow NTrial= 30
Split Flow Tol= 0.02
Split Flow Ratio= 0.02
Log Output Level= 0
Friction Slope Method= 1
Unsteady Friction Slope Method= 2
Unsteady Bridges Friction Slope Method= 1
Parabolic Critical Depth
Global Vel Dist=  1 , 1 , 1
Global Log Level= 0
CheckData=True
Encroach Param= -1, 0, 0, 0
BEGIN DESCRIPTION:
Multiple Run
END DESCRIPTION:

--- UNT 082 IN LACR.f01 (steady flow) ---

Flow Title=Multiple
Number of Profiles=7
Profile Names=10-year,25-year,50-year,1pct_min,100-year,1pct_plu,500-year
River Rch & RM= UNT 082 IN LACR,Reach-1,3276
     386     530     648     579     783    1059    1148
River Rch & RM= UNT 082 IN LACR,Reach-1,567
     446     618     760     683     923    1249    1368
Boundary for River Rch & Prof#=UNT 082 IN LACR,Reach-1,1
Up Type=0
Dn Type=3
Dn Slope=0.005
Boundary for River Rch & Prof#=UNT 082 IN LACR,Reach-1,2
Up Type=0
Dn Type=3
Dn Slope=0.005
Boundary for River Rch & Prof#=UNT 082 IN LACR,Reach-1,3
Up Type=0
Dn Type=3
Dn Slope=0.005
Boundary for River Rch & Prof#=UNT 082 IN LACR,Reach-1,4
Up Type=0
Dn Type=3
Dn Slope=0.005
Boundary for River Rch & Prof#=UNT 082 IN LACR,Reach-1,5
Up Type=0
Dn Type=3
Dn Slope=0.005
Boundary for River Rch & Prof#=UNT 082 IN LACR,Reach-1,6
Up Type=0
Dn Type=3
Dn Slope=0.005
Boundary for River Rch & Prof#=UNT 082 IN LACR,Reach-1,7
Up Type=0
Dn Type=3
Dn Slope=0.005

--- UNT 082 IN LACR.g01 (geometry) ---

Geom Title=Existing Conditions

River Reach=UNT 082 IN LACR,Reach-1
Reach XY= 30
      2300893.54     13226396.85      2300837.72     13226396.85
      2300737.72     13226496.85      2300687.72     13226496.85
      2300537.72     13226646.85      2300487.72     13226646.85
      2300337.72     13226796.85      2300337.72     13226846.85
      2300287.72     13226896.85      2300287.72     13227146.85
      2300387.72     13227246.86      2300437.72     13227246.86
      2300787.72     13227596.86      2300837.72     13227596.86
      2300887.72     13227646.85      2300987.72     13227646.85
      2301037.72     13227696.85      2301087.72     13227696.85
      2301137.72     13227746.86      2301237.72     13227746.86
      2301287.72     13227696.85      2301337.72     13227696.85
      2301487.72     13227846.85      2301487.72     13227896.86
      2301737.72     13228146.85      2301587.72     13228296.85
      2301537.72     13228296.85      2301537.72     13228346.85
      2301587.72     13228396.86      2301587.72     13228446.85

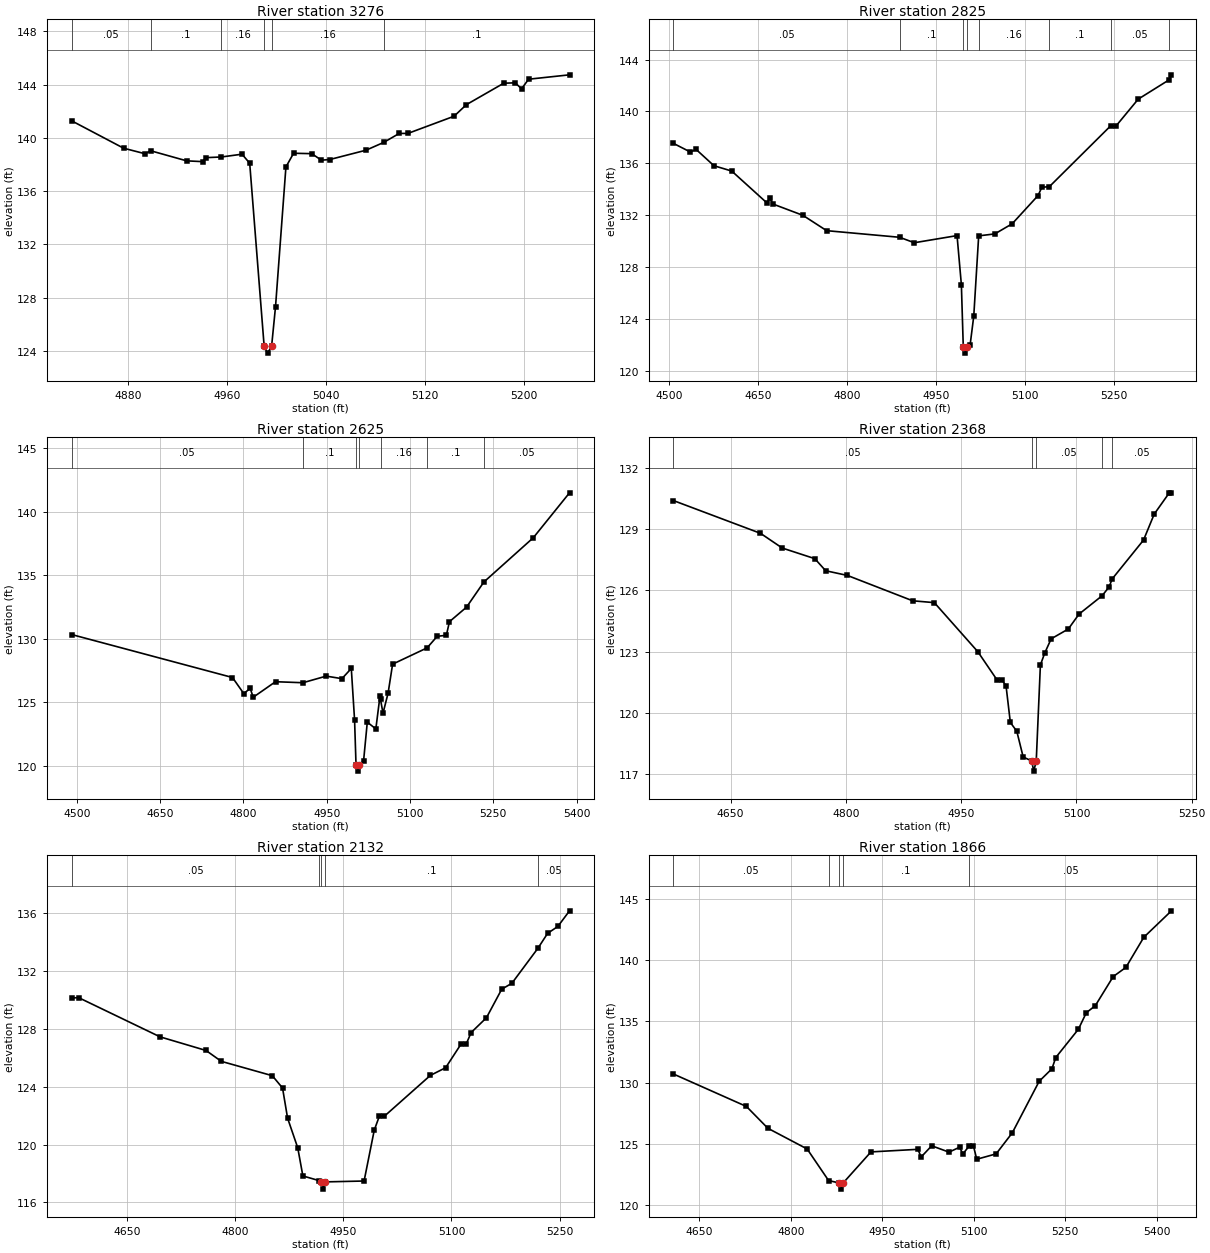
Type RM Length L Ch R = 1,3276,451,451,451
BEGIN DESCRIPTION:
UNT 082 IN LACR 7.0
END DESCRIPTION:
XS GIS Cut Line= 4
      2300690.60     13226335.54      2300711.42     13226439.67
      2300808.64     13226571.61      2300940.63     13226557.72
#Sta/Elev= 30
  4834.1  141.29  4876.2  139.23  4893.7  138.81  4898.0  139.04  4927.2  138.28
  4940.3  138.22  4942.7  138.52  4955.3  138.57  4972.0  138.78  4978.2  138.10
  4989.9  124.34  4992.6  123.84  4995.9  124.34  4999.1  127.34  5007.5  137.82
  5013.7  138.85  5028.4  138.82  5036.2  138.33  5043.0  138.38  5072.3  139.08
  5086.5  139.66  5099.2  140.34  5106.2  140.34  5143.5  141.63  5153.5  142.50
  5183.7  144.11  5193.0  144.14  5198.1  143.69  5203.8  144.41  5236.9  144.74
#Mann=6,-1,0
  4834.1    0.05       0  4898.0     0.1       0  4955.3    0.16       0
  4989.9    0.07       0  4995.9    0.16       0  5086.5     0.1       0
Bank Sta=4989.9,4995.9
Exp/Cntr=0.3,0.1

Type RM Length L Ch R = 1,2825,200,200,200
BEGIN DESCRIPTION:
UNT 082 IN LACR 6.0
END DESCRIPTION:
XS GIS Cut Line= 4
      2300298.30     13226288.56      2300308.72     13226668.74
      2300535.28     13226835.41      2300713.63     13226827.71
#Sta/Elev= 30
  4507.3  137.54  4535.6  136.88  4545.6  137.07  4575.6  135.82  4605.6  135.41
  4664.6  132.97  4669.7  133.30  4675.7  132.86  4725.7  132.00  4765.7  130.82
  4888.8  130.31  4913.6  129.89  4985.7  130.44  4993.0  126.66  4996.2  121.89
  4999.0  121.39  5002.2  121.89  5007.7  122.00  5013.9  124.24  5022.2  130.42
  5049.4  130.57  5078.7  131.35  5122.3  133.52  5128.8  134.16  5141.5  134.21
  5244.6  138.88  5253.9  138.88  5291.4  140.95  5343.0  142.42  5347.4  142.82
#Mann=8,-1,0
  4507.3    0.05       0  4888.8     0.1       0  4996.2    0.07       0
  5002.2     0.1       0  5022.2    0.16       0  5141.5     0.1       0
  5244.6    0.05       0  5343.0    0.08       0
Bank Sta=4996.2,5002.2
Exp/Cntr=0.3,0.1

Type RM Length L Ch R = 1,2625,257,257,257
BEGIN DESCRIPTION:
Mapping XS 95f0db6c
END DESCRIPTION:
XS GIS Cut Line= 4
      2300003.08     13226516.03      2300114.20     13226807.72
      2300454.48     13226967.44      2300662.78     13226953.56
#Sta/Elev= 30
  4490.4  130.34  4780.2  126.96  4800.5  125.70  4812.1  126.10  4817.6  125.41
  4857.7  126.63  4907.1  126.55  4949.0  127.07  4977.3  126.87  4994.2  127.67
  5000.1  123.62  5002.7  120.10  5005.4  119.60  5008.7  120.10  5016.3  120.40
  5023.0  123.45  5038.4  122.92  5045.8  125.48  5046.8  125.24  5051.3  124.15
  5060.5  125.74  5068.6  128.01  5130.7  129.29  5148.9  130.20  5165.4  130.28
  5171.0  131.35  5201.7  132.49  5233.0  134.47  5322.0  137.95  5387.2  141.48
#Mann=7,-1,0
  4490.4    0.05       0  4907.1     0.1       0  5002.7    0.07       0
  5008.7     0.1       0  5046.8    0.16       0  5130.7     0.1       0
  5233.0    0.05       0
Bank Sta=5002.7,5008.7
Exp/Cntr=0.3,0.1

Type RM Length L Ch R = 1,2368,236,236,236
BEGIN DESCRIPTION:
UNT 082 IN LACR 5.0
END DESCRIPTION:
XS GIS Cut Line= 3
      2299987.70     13227446.88      2300287.72     13227146.85
      2300487.71     13227046.86
#Sta/Elev= 30
  4575.7  130.39  4688.9  128.79  4717.2  128.07  4759.6  127.55  4773.7  126.96
  4802.0  126.73  4886.9  125.49  4915.1  125.40  4971.7  123.00  4996.5  121.63
  5002.8  121.63  5008.4  121.33  5014.0  119.54  5022.4  119.11  5030.7  117.85
  5041.7  117.66  5044.5  117.16  5047.7  117.66  5053.1  122.35  5058.7  122.93
  5067.1  123.63  5089.4  124.11  5103.4  124.84  5133.5  125.74  5142.5  126.17
  5146.5  126.56  5187.3  128.46  5201.2  129.73  5220.8  130.77  5223.6  130.77
#Mann=5,-1,0
  4575.7    0.05       0  5041.7    0.04       0  5047.7    0.05       0
  5133.5     0.1       0  5146.5    0.05       0
Bank Sta=5041.7,5047.7
Exp/Cntr=0.3,0.1

Type RM Length L Ch R = 1,2132,266,266,266
BEGIN DESCRIPTION:
Mapping XS 4e46ab0d
END DESCRIPTION:
XS GIS Cut Line= 2
      2300166.68     13227579.54      2300656.30     13227092.51
#Sta/Elev= 30
  4573.1  130.11  4582.8  130.14  4695.9  127.43  4759.6  126.49  4780.8  125.74
  4851.5  124.75  4865.7  123.90  4872.7  121.82  4886.8  119.77  4893.9  117.83
  4916.9  117.50  4919.2  117.42  4922.0  116.92  4925.2  117.42  4978.8  117.48
  4992.9  120.99  5000.0  121.96  5007.1  121.96  5070.7  124.77  5091.9  125.30
  5113.1  126.92  5120.2  126.91  5127.3  127.73  5148.5  128.75  5169.7  130.72
  5183.8  131.13  5219.8  133.54  5233.4  134.58  5247.5  135.05  5263.7  136.13
#Mann=5,-1,0
  4573.1    0.05       0  4916.9     0.1       0  4919.2    0.07       0
  4925.2     0.1       0  5219.8    0.05       0
Bank Sta=4919.2,4925.2
Exp/Cntr=0.3,0.1

Type RM Length L Ch R = 1,1866,405,405,405
BEGIN DESCRIPTION:
UNT 082 IN LACR 4.0
END DESCRIPTION:
XS GIS Cut Line= 4
      2300354.22     13227712.31      2300598.66     13227493.73
      2300776.08     13227410.24      2300947.93     13227173.29
#Sta/Elev= 30
  4607.5  130.70  4727.2  128.05  4762.3  126.27  4826.7  124.58  4861.9  122.00
  4879.7  121.80  4882.5  121.30  4885.7  121.80  4931.4  124.34  5008.2  124.55
  5013.8  123.93  5031.0  124.84  5059.4  124.32  5076.6  124.72  5082.2  124.18
  5092.8  124.84  5099.4  124.84  5104.9  123.74  5136.7  124.18  5163.2  125.90
  5207.3  130.11  5228.2  131.13  5234.5  132.05  5271.6  134.36  5284.6  135.71
  5299.3  136.28  5328.7  138.66  5349.5  139.41  5378.9  141.87  5424.2  144.03
#Mann=5,-1,0
  4607.5    0.05       0  4861.9     0.1       0  4879.7    0.07       0
  4885.7     0.1       0  5092.8    0.05       0
Bank Sta=4879.7,4885.7
Exp/Cntr=0.3,0.1

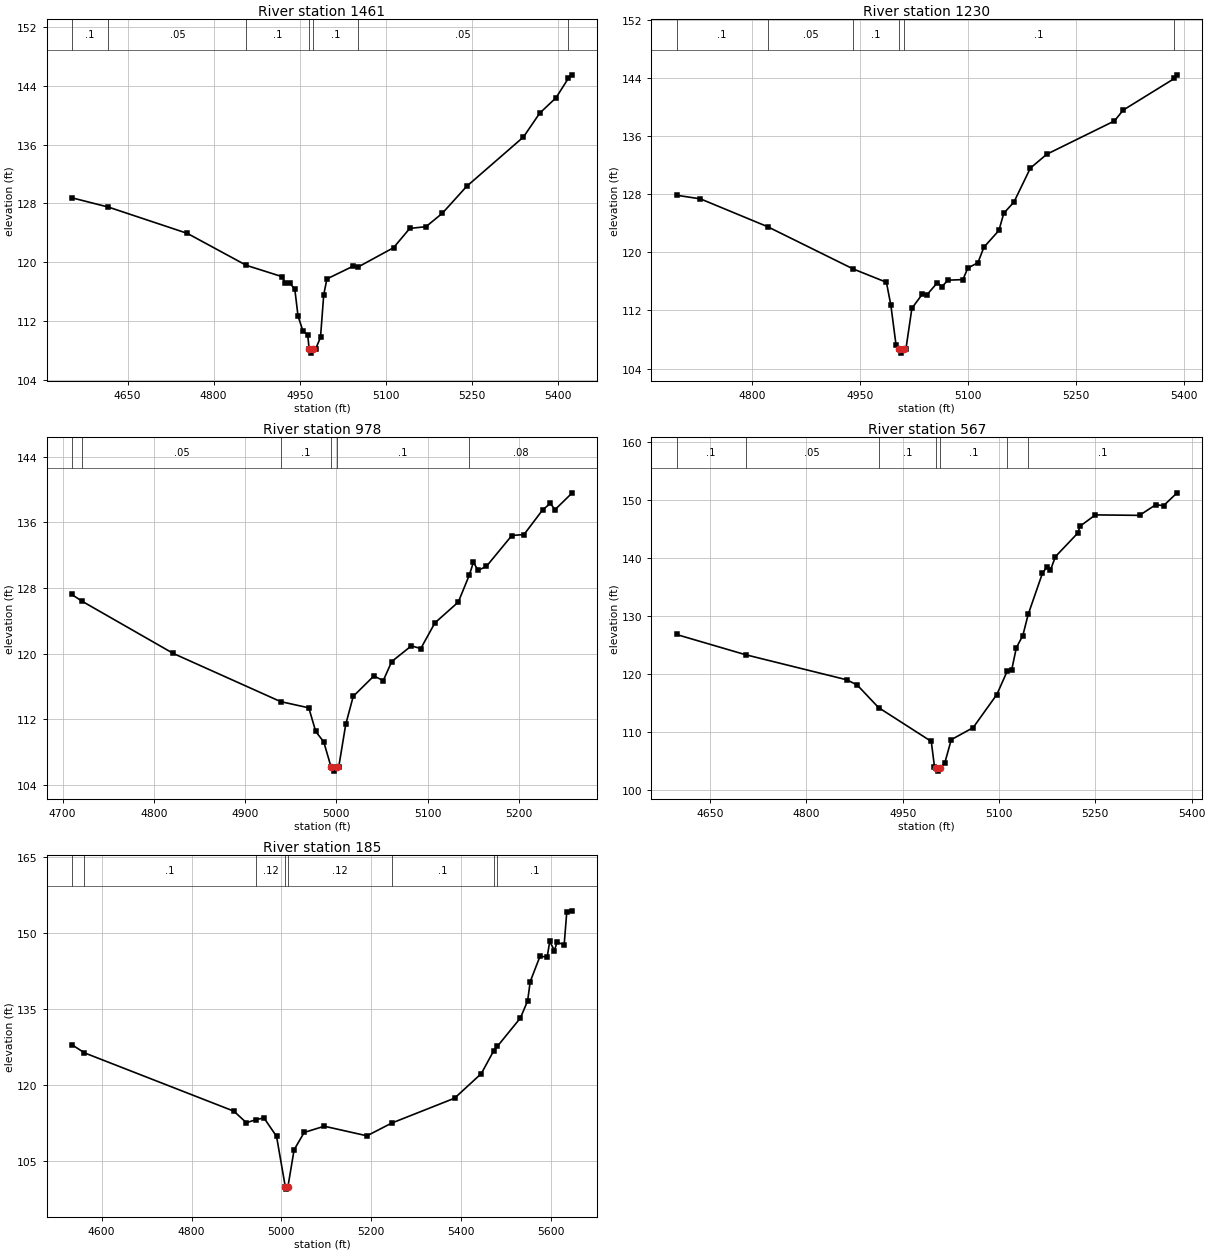
Type RM Length L Ch R = 1,1461,231,231,231
BEGIN DESCRIPTION:
UNT 082 IN LACR 3.0
END DESCRIPTION:
XS GIS Cut Line= 3
      2300587.73     13227846.85      2300987.72     13227646.85
      2301287.75     13227346.83
#Sta/Elev= 30
  4552.8  128.78  4616.7  127.51  4754.0  123.93  4856.8  119.57  4918.9  118.03
  4924.5  117.22  4932.9  117.15  4941.3  116.28  4946.9  112.63  4955.3  110.65
  4963.7  110.07  4966.3  108.10  4969.0  107.60  4972.3  108.10  4977.6  108.18
  4986.0  109.76  4991.6  115.57  4997.2  117.72  5042.4  119.44  5051.6  119.35
  5113.1  121.97  5141.4  124.60  5169.7  124.84  5198.0  126.66  5240.4  130.33
  5339.4  137.07  5367.7  140.32  5396.0  142.41  5417.3  145.04  5424.3  145.54
#Mann=7,-1,0
  4552.8     0.1       0  4616.7    0.05       0  4856.8     0.1       0
  4966.3    0.07       0  4972.3     0.1       0  5051.6    0.05       0
  5417.3    0.08       0
Bank Sta=4966.3,4972.3
Exp/Cntr=0.3,0.1

Type RM Length L Ch R = 1,1230,252,252,252
BEGIN DESCRIPTION:
Mapping XS 39917bab
END DESCRIPTION:
XS GIS Cut Line= 3
      2300994.84     13227991.16      2301302.99     13227578.86
      2301337.63     13227401.34
#Sta/Elev= 30
  4695.0  127.85  4728.2  127.35  4821.6  123.52  4940.6  117.70  4986.7  115.87
  4992.9  112.70  5000.0  107.29  5004.5  106.62  5007.3  106.12  5010.5  106.62
  5013.8  106.68  5022.1  112.29  5036.7  114.25  5043.0  114.15  5057.6  115.82
  5063.8  115.27  5072.2  116.16  5093.0  116.24  5099.9  117.84  5113.8  118.55
  5122.2  120.70  5143.0  123.00  5149.8  125.37  5163.9  126.91  5186.8  131.59
  5209.7  133.50  5303.5  138.07  5315.8  139.57  5386.9  143.92  5390.6  144.42
#Mann=6,-1,0
  4695.0     0.1       0  4821.6    0.05       0  4940.6     0.1       0
  5004.5    0.07       0  5010.5     0.1       0  5386.9    0.08       0
Bank Sta=5004.5,5010.5
Exp/Cntr=0.3,0.1

Type RM Length L Ch R = 1,978,411,411,411
BEGIN DESCRIPTION:
UNT 082 IN LACR 2.0
END DESCRIPTION:
XS GIS Cut Line= 3
      2301252.20     13228003.24      2301387.72     13227746.86
      2301447.53     13227495.37
#Sta/Elev= 30
  4710.0  127.21  4721.6  126.37  4821.4  120.02  4938.9  114.16  4969.8  113.40
  4977.4  110.52  4986.2  109.25  4994.2  106.19  4996.9  105.69  5000.2  106.19
  5002.6  106.19  5010.3  111.39  5018.5  114.80  5041.1  117.28  5051.4  116.72
  5060.7  119.04  5082.2  120.95  5092.5  120.62  5108.0  123.75  5133.6  126.28
  5145.7  129.57  5150.2  131.14  5155.3  130.14  5164.5  130.64  5192.3  134.39
  5205.6  134.51  5226.1  137.52  5234.5  138.30  5239.6  137.54  5258.5  139.59
#Mann=6,-1,0
  4710.0     0.1       0  4721.6    0.05       0  4938.9     0.1       0
  4994.2    0.07       0  5000.2     0.1       0  5145.7    0.08       0
Bank Sta=4994.2,5000.2
Exp/Cntr=0.3,0.1

Type RM Length L Ch R = 1,567,382,382,382
BEGIN DESCRIPTION:
Mapping XS 7b3d7bcc
END DESCRIPTION:
XS GIS Cut Line= 4
      2301252.20     13228029.24      2301434.72     13228087.15
      2301861.80     13228014.23      2302007.64     13227962.14
#Sta/Elev= 30
  4597.7  126.80  4705.2  123.31  4863.2  118.97  4879.2  118.07  4912.4  114.18
  4994.5  108.34  4999.5  103.94  5002.3  103.71  5005.0  103.21  5008.3  103.71
  5015.4  104.56  5025.6  108.64  5059.7  110.72  5096.6  116.44  5112.6  120.43
  5119.8  120.72  5127.0  124.53  5137.1  126.62  5145.4  130.26  5167.6  137.37
  5174.9  138.52  5180.0  137.89  5187.9  140.25  5222.4  144.28  5226.5  145.52
  5250.0  147.45  5318.8  147.37  5344.3  149.22  5356.2  149.03  5377.3  151.26
#Mann=7,-1,0
  4597.7     0.1       0  4705.2    0.05       0  4912.4     0.1       0
  5002.3    0.07       0  5008.3     0.1       0  5112.6    0.16       0
  5145.4     0.1       0
Bank Sta=5002.3,5008.3
Exp/Cntr=0.3,0.1

Type RM Length L Ch R = 1,185,0,0,0
BEGIN DESCRIPTION:
UNT 082 IN LACR 1.0
END DESCRIPTION:
XS GIS Cut Line= 4
      2301182.76     13228016.21      2301445.13     13228243.40
      2301726.38     13228384.02      2302122.25     13228165.25
#Sta/Elev= 30
  4533.4  127.96  4561.8  126.32  4894.2  114.83  4922.1  112.55  4943.3  113.15
  4961.2  113.50  4989.2  109.86  5008.6   99.96  5011.3   99.46  5014.6   99.96
  5028.3  107.22  5050.7  110.63  5095.4  111.86  5190.4  109.97  5245.2  112.47
  5385.2  117.38  5444.8  122.23  5472.0  126.66  5480.3  127.58  5531.8  133.19
  5547.9  136.57  5553.6  140.36  5575.4  145.35  5591.4  145.23  5597.1  148.31
  5607.5  146.48  5613.2  148.13  5629.2  147.64  5634.9  154.02  5647.2  154.32
#Mann=8,-1,0
  4533.4    0.05       0  4561.8     0.1       0  4943.3    0.12       0
  5008.6    0.07       0  5014.6    0.12       0  5245.2     0.1       0
  5472.0    0.16       0  5480.3     0.1       0
Bank Sta=5008.6,5014.6
Exp/Cntr=0.3,0.1

Chan Stop Cuts=-1