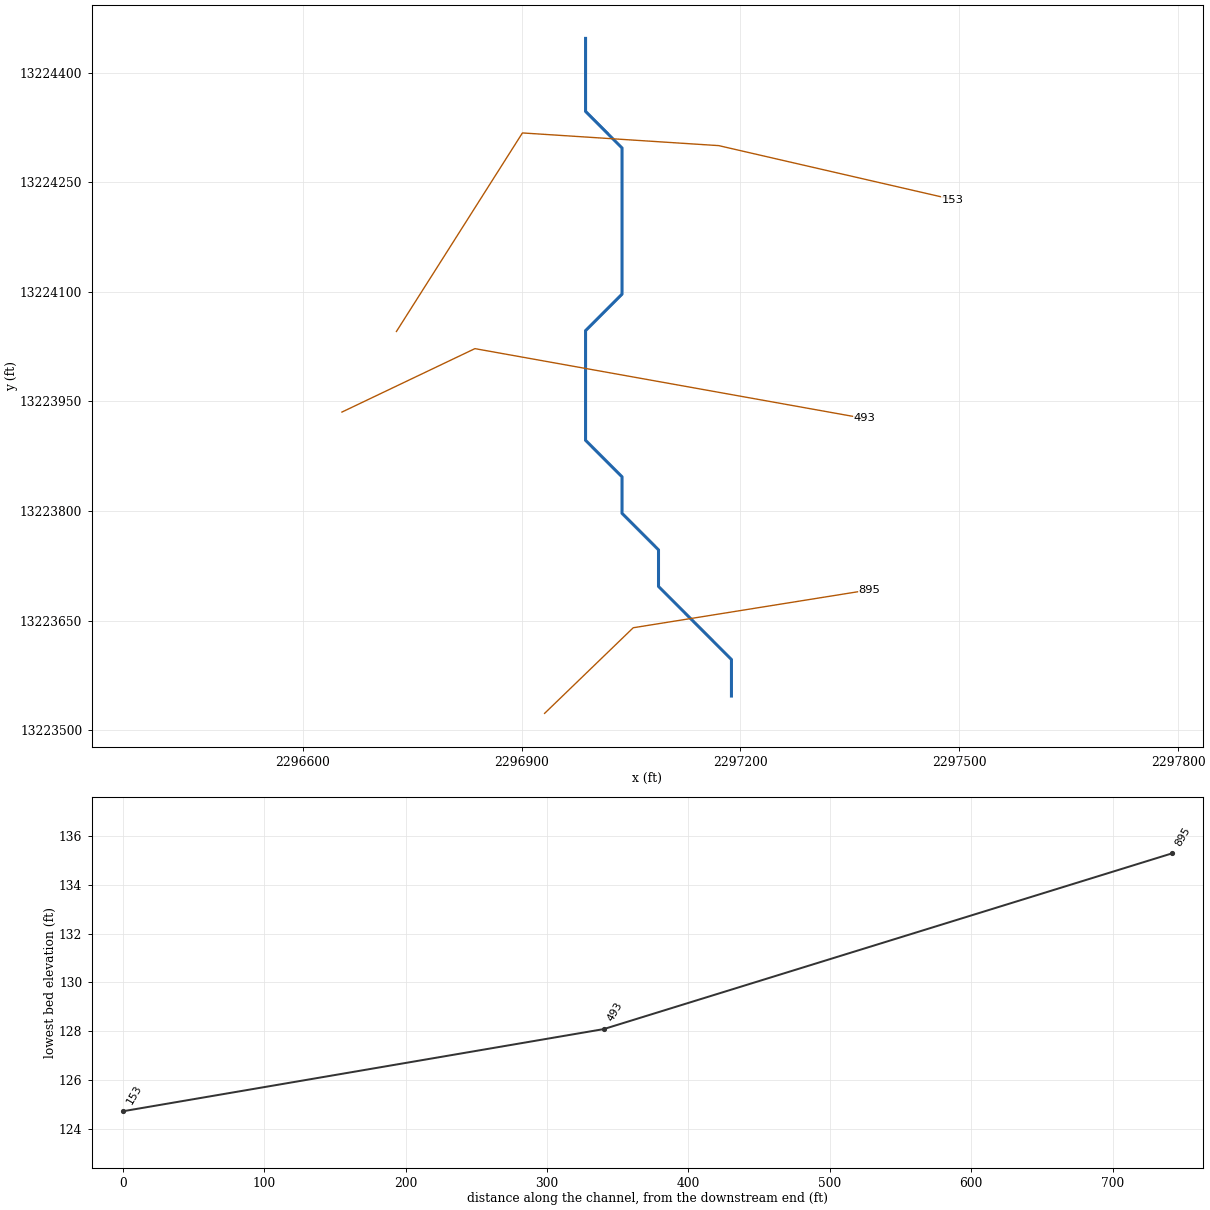
--- UNT 083 IN LACR.prj (project) ---

Proj Title=UNT 083 IN LACR Base Level Engineering
Current Plan=p01
Default Exp/Contr=0.3,0.1
English Units
Geom File=g01
Flow File=f01
Plan File=p01
Y Axis Title=Elevation
X Axis Title(PF)=Main Channel Distance
X Axis Title(XS)=Station
BEGIN DESCRIPTION:
UNT 083 IN LACR
END DESCRIPTION:
DSS Export Rating Curves= 0
DSS Export Rating Curve Sorted= 0
DSS Export Volume Flow Curves= 0
DXF OffsetX= 0
DXF OffsetY= 0
DXF ScaleX= 1
DXF ScaleY= 10

--- UNT 083 IN LACR.p01 (plan) ---

Plan Title=Multiple Run
Short Identifier=Multiple
Geom File=g01
Flow File=f01
Subcritical Flow
K Sum by GR= 0
Std Step Tol= 0.01
Critical Tol= 0.01
Num of Std Step Trials= 20
Max Error Tol= 0.3
Flow Tol Ratio= 0.001
Split Flow NTrial= 30
Split Flow Tol= 0.02
Split Flow Ratio= 0.02
Log Output Level= 0
Friction Slope Method= 1
Unsteady Friction Slope Method= 2
Unsteady Bridges Friction Slope Method= 1
Parabolic Critical Depth
Global Vel Dist=  1 , 1 , 1
Global Log Level= 0
CheckData=True
Encroach Param= -1, 0, 0, 0
BEGIN DESCRIPTION:
Multiple Run
END DESCRIPTION:

--- UNT 083 IN LACR.f01 (steady flow) ---

Flow Title=Multiple
Number of Profiles=7
Profile Names=10-year,25-year,50-year,1pct_min,100-year,1pct_plu,500-year
River Rch & RM= UNT 083 IN LACR,Reach-1,895
     200     265     317     278     376     508     529
Boundary for River Rch & Prof#=UNT 083 IN LACR,Reach-1,1
Up Type=0
Dn Type=3
Dn Slope=0.005
Boundary for River Rch & Prof#=UNT 083 IN LACR,Reach-1,2
Up Type=0
Dn Type=3
Dn Slope=0.005
Boundary for River Rch & Prof#=UNT 083 IN LACR,Reach-1,3
Up Type=0
Dn Type=3
Dn Slope=0.005
Boundary for River Rch & Prof#=UNT 083 IN LACR,Reach-1,4
Up Type=0
Dn Type=3
Dn Slope=0.005
Boundary for River Rch & Prof#=UNT 083 IN LACR,Reach-1,5
Up Type=0
Dn Type=3
Dn Slope=0.005
Boundary for River Rch & Prof#=UNT 083 IN LACR,Reach-1,6
Up Type=0
Dn Type=3
Dn Slope=0.005
Boundary for River Rch & Prof#=UNT 083 IN LACR,Reach-1,7
Up Type=0
Dn Type=3
Dn Slope=0.005

--- UNT 083 IN LACR.g01 (geometry) ---

Geom Title=Existing Conditions
Program Version=4.10

River Reach=UNT 083 IN LACR ,Reach-1
Reach XY= 19
      2297187.72     13223546.85      2297187.72     13223596.85
      2297137.72     13223646.86      2297087.72     13223696.85
      2297087.72     13223746.85      2297037.72     13223796.86
      2297037.72     13223846.85      2296987.72     13223896.85
      2296987.72     13223946.85      2296987.72     13223996.86
      2296987.72     13224046.85      2297037.72     13224096.85
      2297037.72     13224146.86      2297037.72     13224196.85
      2297037.72     13224246.85      2297037.72     13224296.86
      2296987.72     13224346.85      2296987.72     13224396.85
      2296987.72     13224446.85

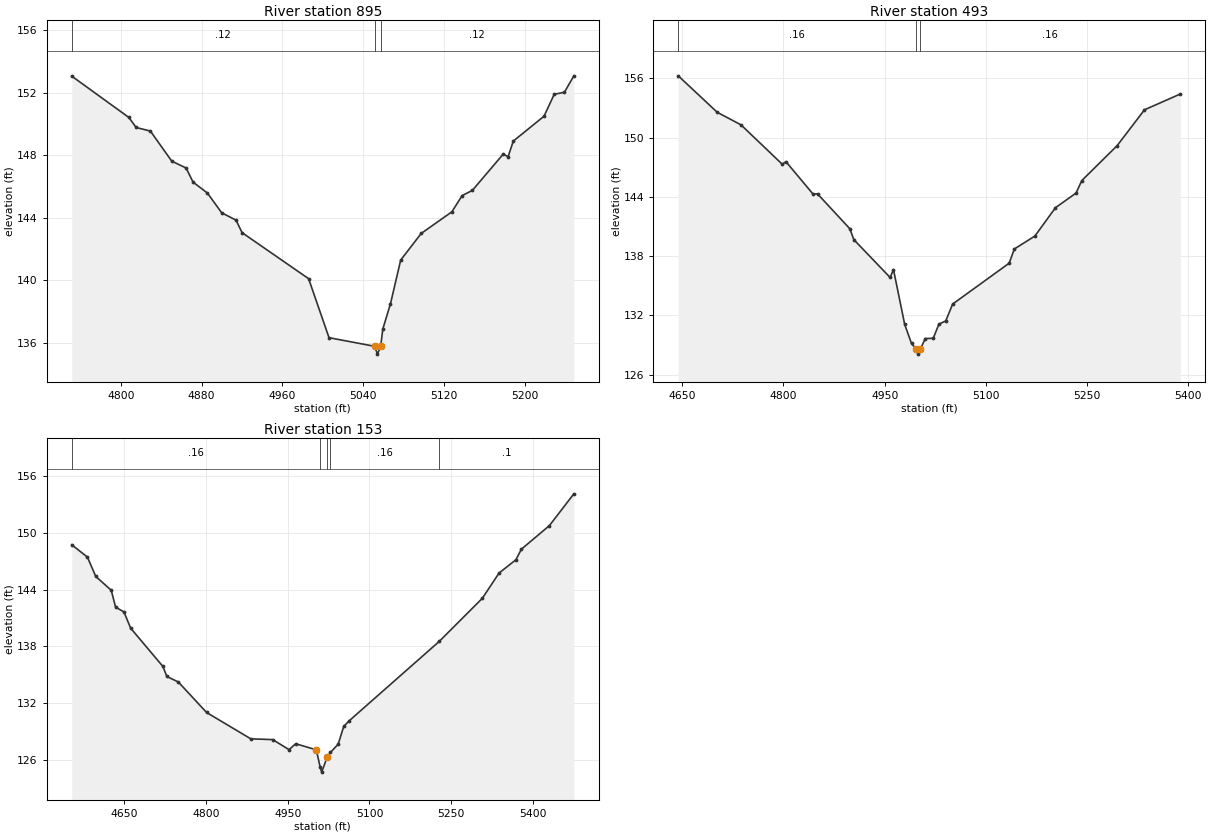
Type RM Length L Ch R = 1 ,895     ,402,402,402
BEGIN DESCRIPTION:
UNT 083 IN LACR 2.0
END DESCRIPTION:
XS GIS Cut Line= 3
      2296931.57     13223523.15      2297053.07     13223640.31
      2297376.87     13223692.12
#Sta/Elev= 30
  4751.6  153.05  4808.1  150.41  4815.3  149.77  4829.4  149.54  4850.5  147.62
  4864.7  147.18  4871.6  146.28  4885.8  145.58  4899.9  144.32  4914.1  143.85
  4920.1  143.05  4985.9  140.11  5006.1  136.34  5051.2  135.79    5054  135.29
  5057.2  135.79  5059.3  136.89  5066.9  138.51    5077   141.3  5097.3     143
  5127.6  144.38  5137.8  145.42  5147.9  145.75  5178.3  148.06  5183.3  147.91
  5188.4   148.9  5218.8  150.49  5228.9  151.89    5239  152.02  5248.3  153.07
#Mann= 3 ,-1 , 0
  4751.6     .12       0  5051.2     .07       0  5057.2     .12       0
Bank Sta=5051.2,5057.2
XS Rating Curve= 0 ,0
Exp/Cntr=0.3,0.1

Type RM Length L Ch R = 1 ,493     ,340,340,340
BEGIN DESCRIPTION:
Mapping XS 7a99f919
END DESCRIPTION:
XS GIS Cut Line= 3
      2296653.74     13223935.44      2296836.06     13224022.26
      2297369.95     13223926.77
#Sta/Elev= 30
    4644  156.25  4701.8  152.56    4737  151.29  4798.2   147.3  4803.7  147.56
  4843.6   144.3  4850.5   144.3  4898.4  140.77  4904.3  139.67  4958.1  135.84
  4963.1  136.64  4979.7  131.09  4989.8  129.16    4997  128.58  4999.8  128.08
    5003  128.58  5010.2  129.66    5022  129.68  5030.5  131.12  5040.6  131.44
  5050.8  133.15  5134.7  137.29  5142.2  138.72  5172.7  140.03  5203.2   142.9
  5233.7  144.38  5242.3  145.65  5294.6  149.18  5335.2  152.81  5388.3  154.41
#Mann= 3 ,-1 , 0
    4644     .16       0    4997     .07       0    5003     .16       0
Bank Sta=4997,5003
XS Rating Curve= 0 ,0
Exp/Cntr=0.3,0.1

Type RM Length L Ch R = 1 ,153     ,0,0,0
BEGIN DESCRIPTION:
UNT 083 IN LACR 1.0
END DESCRIPTION:
XS GIS Cut Line= 4
      2296728.44     13224045.73      2296901.17      13224317.4
      2297170.26     13224300.04      2297491.41     13224226.26
#Sta/Elev= 30
  4553.8  148.76  4582.6  147.45  4597.8  145.41  4626.2  143.95  4634.2  142.16
  4649.5  141.66  4661.8  139.94    4721  135.89  4728.2  134.83  4749.4  134.24
  4801.1  131.02  4882.3  128.23  4922.4  128.15  4952.4  127.09  4964.7  127.71
  5002.5  127.07  5009.6  125.21  5012.3  124.71  5022.6  126.35  5028.4  126.79
  5042.6  127.67  5052.7  129.54  5062.7  130.14  5227.8  138.53  5306.9  143.09
  5337.7  145.77  5368.5  147.17  5378.8   148.3  5430.1  150.79  5474.9  154.15
#Mann= 5 ,-1 , 0
  4553.8     .16       0  5009.6     .07       0  5022.6      .1       0
  5028.4     .16       0  5227.8      .1       0
Bank Sta=5002.5,5022.6
XS Rating Curve= 0 ,0
Exp/Cntr=0.3,0.1

Chan Stop Cuts=-1
Use User Specified Reach Order=0
Composite Channel Slope=5