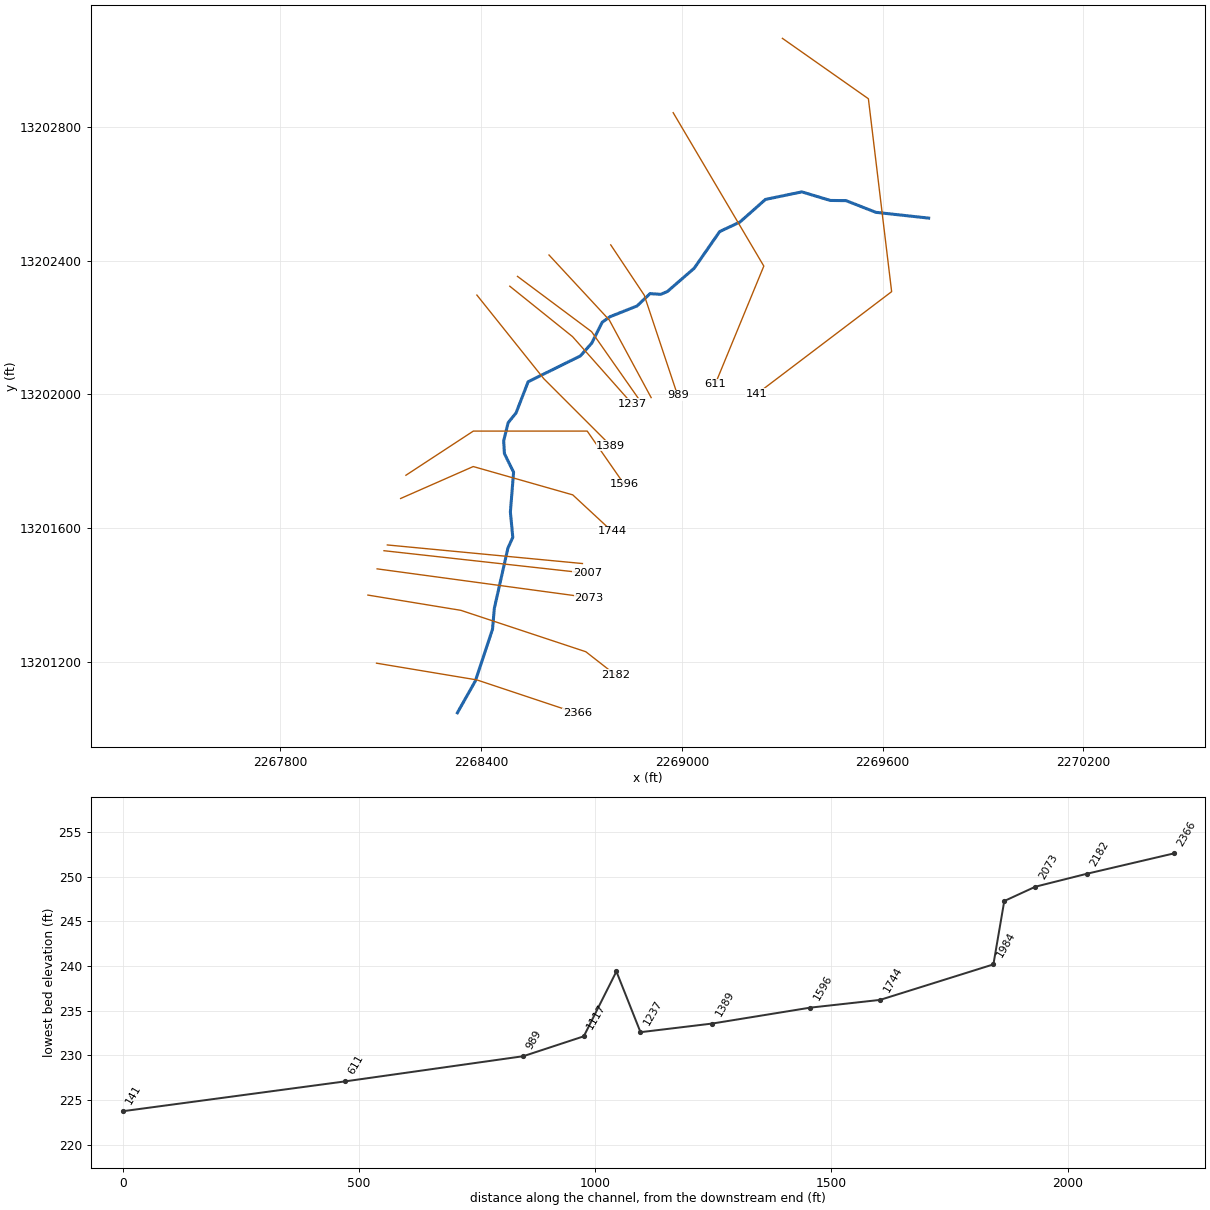
--- UNT 085 IN LACR.prj (project) ---

Proj Title=UNT 085 IN LACR Base Level Engineering
Current Plan=p01
Default Exp/Contr=0.3,0.1
English Units
Geom File=g01
Geom File=g02
Flow File=f01
Plan File=p01
Y Axis Title=Elevation
X Axis Title(PF)=Main Channel Distance
X Axis Title(XS)=Station
BEGIN DESCRIPTION:
UNT 085 IN LACR
END DESCRIPTION:
DSS Export Rating Curves= 0
DSS Export Rating Curve Sorted= 0
DSS Export Volume Flow Curves= 0
DXF OffsetX= 0
DXF OffsetY= 0
DXF ScaleX= 1
DXF ScaleY= 10

--- UNT 085 IN LACR.p01 (plan) ---

Plan Title=Multiple Run
Short Identifier=Multiple
Geom File=g01
Flow File=f01
Subcritical Flow
K Sum by GR= 0
Std Step Tol= 0.01
Critical Tol= 0.01
Num of Std Step Trials= 20
Max Error Tol= 0.3
Flow Tol Ratio= 0.001
Split Flow NTrial= 30
Split Flow Tol= 0.02
Split Flow Ratio= 0.02
Log Output Level= 0
Friction Slope Method= 1
Unsteady Friction Slope Method= 2
Unsteady Bridges Friction Slope Method= 1
Parabolic Critical Depth
Global Vel Dist=  1 , 1 , 1
Global Log Level= 0
CheckData=True
Encroach Param= -1, 0, 0, 0
BEGIN DESCRIPTION:
Multiple Run
END DESCRIPTION:

--- UNT 085 IN LACR.f01 (steady flow) ---

Flow Title=Multiple
Number of Profiles=7
Profile Names=10-year,25-year,50-year,1pct_min,100-year,1pct_plu,500-year
River Rch & RM= UNT 085 IN LACR,Reach-1,2366
      66      84      97      84     114     154     156
River Rch & RM= UNT 085 IN LACR,Reach-1,1389
     123     164     196     174     236     318     343
Boundary for River Rch & Prof#=UNT 085 IN LACR,Reach-1,1
Up Type=0
Dn Type=3
Dn Slope=0.005
Boundary for River Rch & Prof#=UNT 085 IN LACR,Reach-1,2
Up Type=0
Dn Type=3
Dn Slope=0.005
Boundary for River Rch & Prof#=UNT 085 IN LACR,Reach-1,3
Up Type=0
Dn Type=3
Dn Slope=0.005
Boundary for River Rch & Prof#=UNT 085 IN LACR,Reach-1,4
Up Type=0
Dn Type=3
Dn Slope=0.005
Boundary for River Rch & Prof#=UNT 085 IN LACR,Reach-1,5
Up Type=0
Dn Type=3
Dn Slope=0.005
Boundary for River Rch & Prof#=UNT 085 IN LACR,Reach-1,6
Up Type=0
Dn Type=3
Dn Slope=0.005
Boundary for River Rch & Prof#=UNT 085 IN LACR,Reach-1,7
Up Type=0
Dn Type=3
Dn Slope=0.005

--- UNT 085 IN LACR.g01 (geometry) ---

Geom Title=Existing Conditions
Program Version=4.10

River Reach=UNT 085 IN LACR ,Reach-1
Reach XY= 30
      2268329.44     13201048.59      2268383.32     13201143.96
      2268434.42     13201298.23      2268439.94       13201361.
      2268480.46      13201540.8      2268495.06     13201572.78
      2268487.82     13201648.73      2268497.42     13201767.64
      2268470.03     13201822.98      2268467.82     13201861.53
      2268481.11      13201915.4       2268504.8     13201944.64
      2268540.87     13202037.82      2268697.02     13202114.96
      2268730.88     13202153.15      2268762.13     13202215.65
      2268785.56     13202232.14      2268866.29     13202264.26
      2268905.18     13202301.22      2268936.99     13202298.97
      2268957.18      13202307.6      2269037.13       13202377.
      2269113.29     13202486.66      2269173.65     13202514.98
      2269250.06      13202582.7      2269358.74      13202605.2
      2269443.79     13202579.61      2269490.89       13202579.
      2269580.13     13202544.07      2269737.72     13202526.85

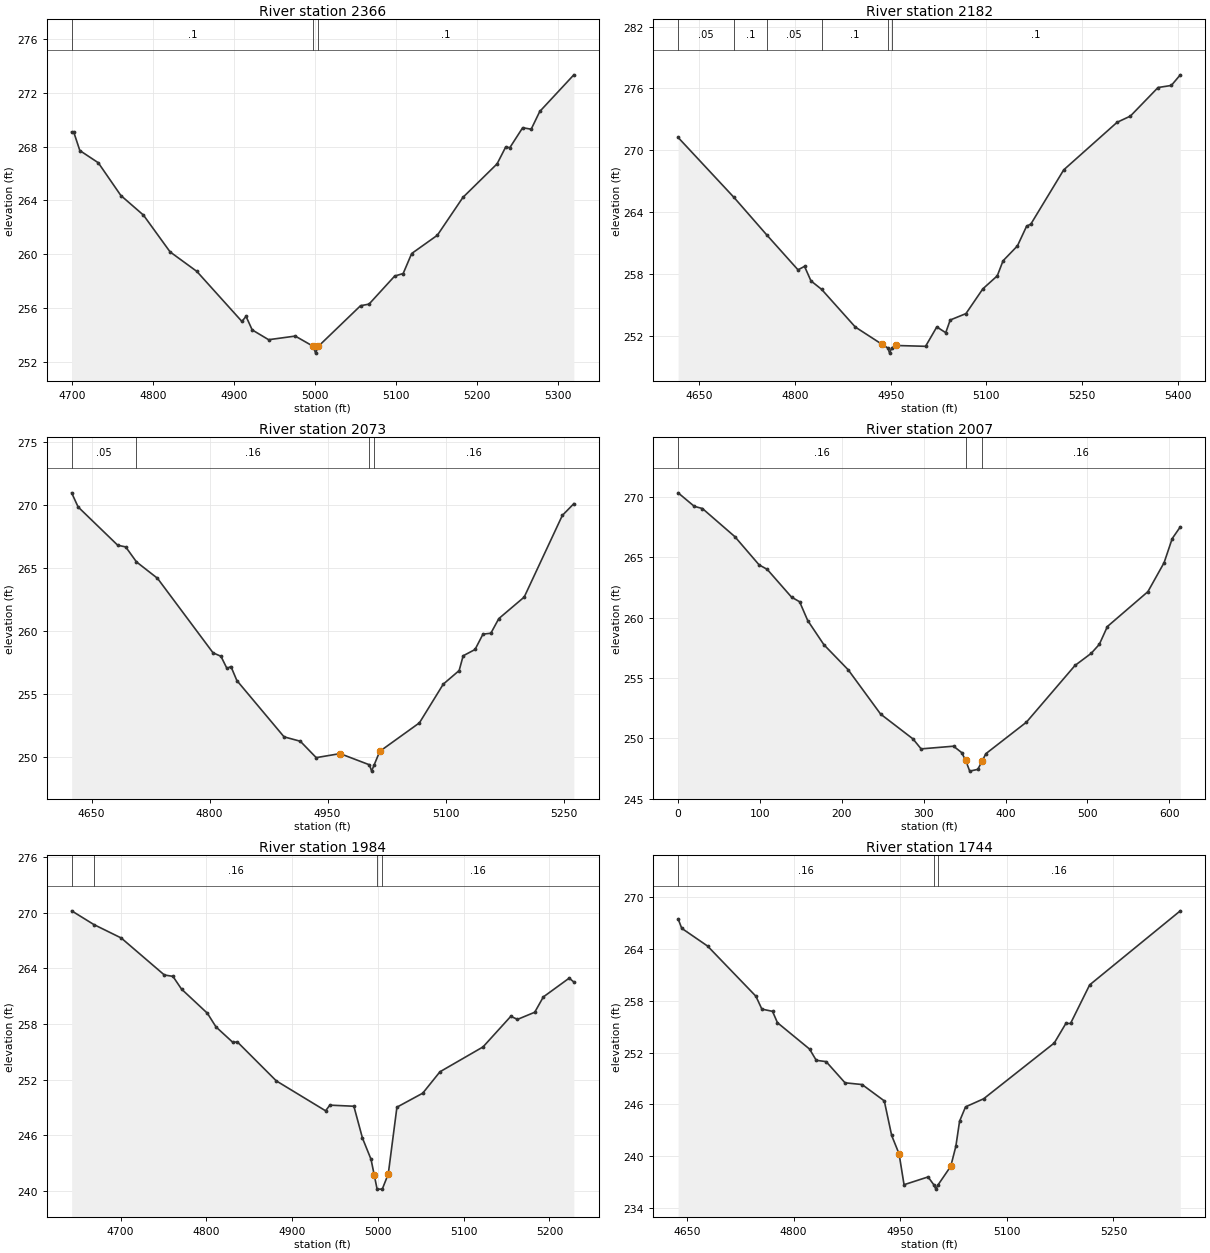
Type RM Length L Ch R = 1 ,2366    ,184,184,184
BEGIN DESCRIPTION:
UNT 085 IN LACR 5.0
END DESCRIPTION:
XS GIS Cut Line= 3
      2268087.76     13201196.85      2268387.72     13201146.85
       2268687.7     13201046.86
#Sta/Elev= 30
  4699.2  269.11  4701.7  269.11  4709.3  267.72  4732.1  266.81    4760  264.37
  4787.9  262.91  4820.8  260.17  4853.8  258.72  4909.5  254.99  4914.6  255.37
  4922.2  254.36  4942.5  253.63  4975.4   253.9  4997.8  253.13  5000.5  252.63
  5003.8  253.13    5056  256.16  5066.5  256.28  5098.2  258.37  5108.7  258.56
  5119.2  260.05  5150.9  261.41  5182.5  264.23  5224.7  266.73  5235.2  267.97
  5240.5  267.94  5256.3  269.42  5266.8  269.31  5277.4  270.63  5319.5  273.36
#Mann= 3 ,-1 , 0
  4699.2      .1       0  4997.8     .07       0  5003.8      .1       0
Bank Sta=4997.8,5003.8
XS Rating Curve= 0 ,0
Exp/Cntr=0.3,0.1

Type RM Length L Ch R = 1 ,2182    ,109,109,109
BEGIN DESCRIPTION:
Mapping XS dbc82982
END DESCRIPTION:
XS GIS Cut Line= 4
      2268062.15     13201400.34      2268339.95     13201354.76
      2268713.22     13201231.07      2268802.03     13201161.75
#Sta/Elev= 30
  4616.7  271.25  4704.3  265.44  4755.9  261.79  4804.7  258.42  4814.9  258.76
    4825  257.35  4841.7  256.53  4894.5  252.88    4936  251.22  4945.5  250.85
  4948.3  250.35  4951.5  250.85  4959.1  251.09  5004.7  251.01  5022.3  252.89
  5036.3  252.33  5043.3  253.56    5068  254.18  5094.5  256.58  5117.1  257.84
  5126.2   259.3  5148.7  260.74  5163.1  262.65  5169.8  262.86  5221.3  268.11
    5305  272.72  5325.8  273.32  5369.2  276.09    5390  276.29  5404.1  277.32
#Mann= 6 ,-1 , 0
  4616.7     .05       0  4704.3      .1       0  4755.9     .05       0
  4841.7      .1       0  4945.5     .07       0  4951.5      .1       0
Bank Sta=4936,4959.1
XS Rating Curve= 0 ,0
Exp/Cntr=0.3,0.1

Type RM Length L Ch R = 1 ,2073    ,66,66,66
BEGIN DESCRIPTION:
Mapping XS 26be40ad
END DESCRIPTION:
XS GIS Cut Line= 2
      2268089.61      13201478.7      2268722.22     13201392.98
#Sta/Elev= 30
  4624.7  270.98  4632.9  269.86  4683.3  266.82  4693.4  266.69  4707.1   265.5
  4733.8   264.2  4804.4  258.29  4814.5  258.01  4822.1  257.05  4827.2   257.2
  4834.7  256.09  4894.7  251.62  4915.4  251.27  4935.6  249.97  4965.9  250.29
  5003.3   249.4    5006   248.9  5009.3   249.4  5016.4  250.47  5066.8  252.73
  5097.1   255.8  5117.3  256.88  5122.4  258.05  5137.5  258.55  5147.6  259.77
  5157.6  259.84  5167.7     261    5200  262.71  5248.5  269.19  5263.1  270.12
#Mann= 4 ,-1 , 0
  4624.7     .05       0  4707.1     .16       0  5003.3     .07       0
  5009.3     .16       0
Bank Sta=4965.9,5016.4
XS Rating Curve= 0 ,0
Exp/Cntr=0.3,0.1

Type RM Length L Ch R = 1 ,2007    ,23,23,23
BEGIN DESCRIPTION:
Mapping XS 5bbe7898
END DESCRIPTION:
XS GIS Cut Line= 2
     2268110.149    13201532.933     2268717.788    13201465.572
#Sta/Elev= 30
       0270.3456   19.79269.2243   29.68269.0456   69.25266.7185   98.93264.3774
  108.82264.0061   138.5261.7086  148.39261.3228  158.29259.7666  178.07257.7629
  207.75255.6858  247.32252.0183  286.89249.9595  296.79249.1349  336.36249.3582
  346.25248.8334  351.19  248.19  356.14 247.293  366.04247.4395  371.48  248.15
  375.93248.7407  425.39251.3463  484.75256.0459  504.53257.0487  514.43257.7935
  524.32259.2722  573.78 262.159  593.57264.5609  603.46 266.555  613.36267.5258
#Mann= 3 , 0 , 0
       0     .16       0  351.19     .07       0  371.48     .16       0
Bank Sta=351.19,371.48
XS Rating Curve= 0 ,0
Exp/Cntr=0.3,0.1

Type RM Length L Ch R = 1 ,1984    ,240,240,240
BEGIN DESCRIPTION:
Mapping XS 2f186675
END DESCRIPTION:
XS GIS Cut Line= 2
      2268120.15     13201550.14      2268703.11     13201494.62
#Sta/Elev= 30
  4642.9  270.21  4668.8  268.73  4700.7  267.28    4751  263.29    4761  263.14
    4771  261.77  4801.2  259.16  4811.2  257.69    4831  256.01    4836  256.08
  4881.5  251.87    4939  248.64    4944  249.25    4972  249.13    4982   245.7
    4992  243.41 4995.74  241.71  4999.1  240.19  5005.1  240.19  5012.1  241.82
  5022.2  249.03  5052.3  250.54  5072.4  252.85  5122.6  255.53    5155  258.83
  5162.8   258.5  5182.9  259.27  5192.9  260.92  5223.1  262.95  5228.5  262.53
#Mann= 4 ,-1 , 0
  4642.9     .05       0  4668.8     .16       0  4999.1     .07       0
  5005.1     .16       0
Bank Sta=4995.74,5012.1
XS Rating Curve= 0 ,0
Exp/Cntr=0.3,0.1

Type RM Length L Ch R = 1 ,1744    ,148,148,148
BEGIN DESCRIPTION:
Mapping XS 7ee62bb3
END DESCRIPTION:
XS GIS Cut Line= 4
      2268159.86     13201688.98      2268376.84     13201784.45
      2268674.15     13201699.82      2268791.64     13201590.88
#Sta/Elev= 30
  4637.6  267.45  4642.7  266.36    4679  264.31    4747  258.51  4755.4  257.02
  4770.4  256.76  4777.3  255.45  4822.5   252.4  4831.9   251.1  4845.8  250.95
  4872.4   248.5  4896.4   248.3  4927.6  246.41    4938  242.41  4948.4  240.29
  4955.4  236.72  4989.2  237.62  4997.3  236.71  5000.1  236.21  5003.3  236.71
  5021.1  238.85  5028.3  241.17  5033.5  244.06  5041.9  245.72  5067.3  246.65
  5166.7   253.1    5183  255.36  5189.6  255.36  5216.5  259.82    5344  268.38
#Mann= 3 ,-1 , 0
  4637.6     .16       0  4997.3     .07       0  5003.3     .16       0
Bank Sta=4948.4,5021.1
XS Rating Curve= 0 ,0
Exp/Cntr=0.3,0.1

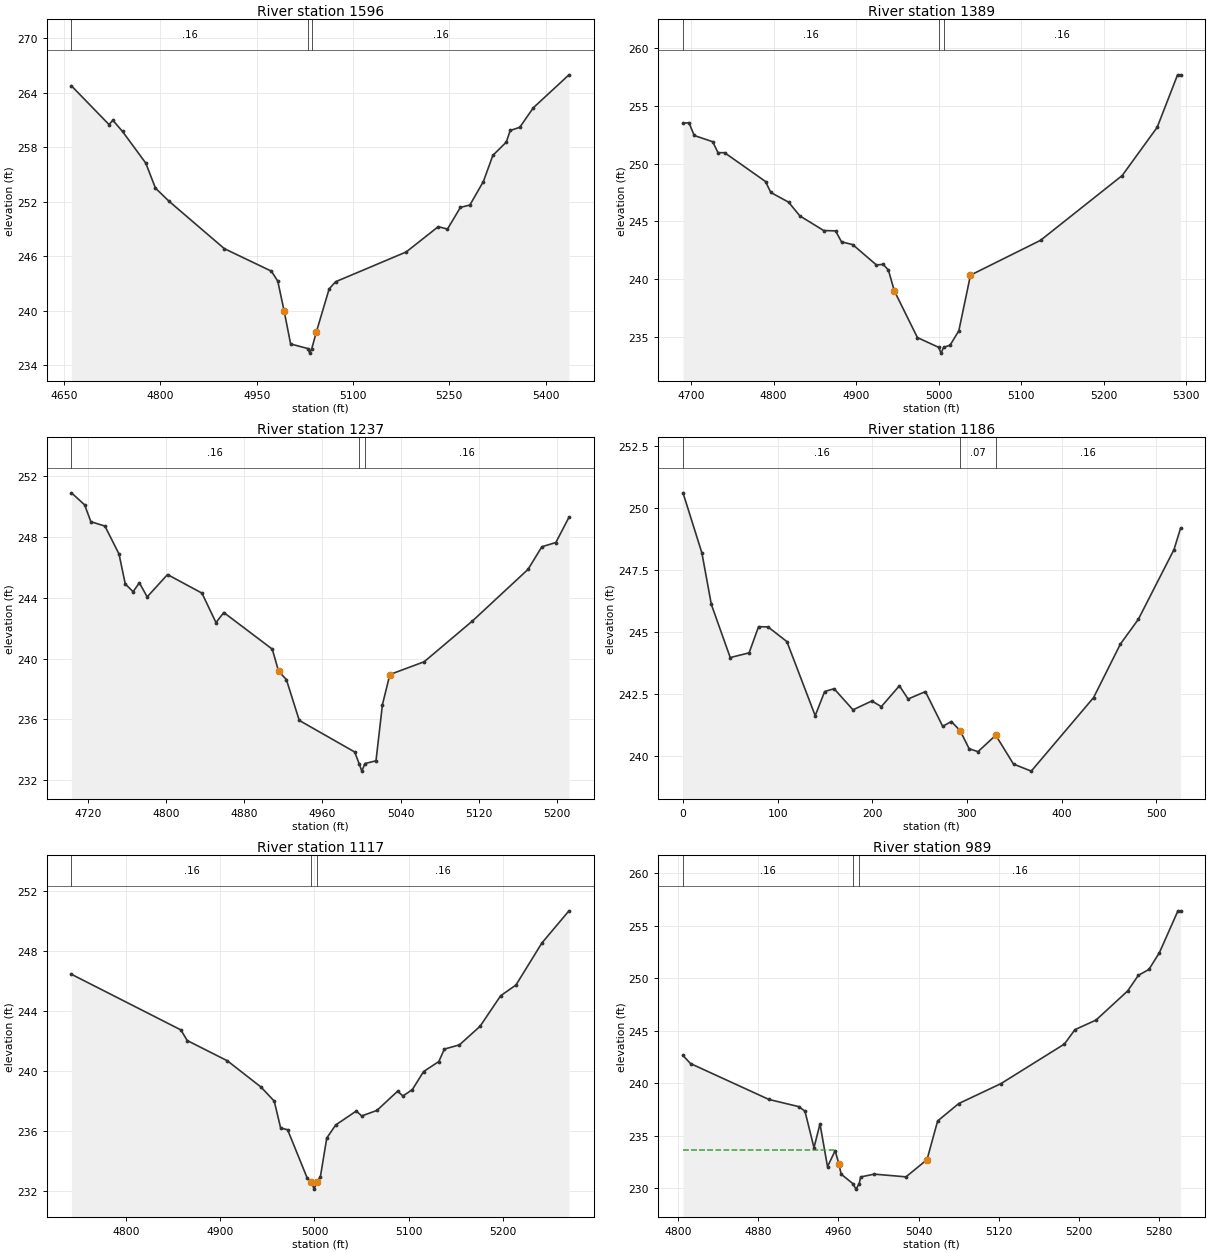
Type RM Length L Ch R = 1 ,1596    ,207,207,207
BEGIN DESCRIPTION:
UNT 085 IN LACR 4.0
END DESCRIPTION:
XS GIS Cut Line= 4
      2268175.72     13201758.47      2268377.11     13201890.41
      2268717.38     13201890.41      2268828.09     13201731.27
#Sta/Elev= 30
  4661.4  264.78    4720  260.51  4725.9  260.99    4741  259.75  4777.2  256.27
  4792.3  253.51  4813.4  252.07  4899.5  246.85  4972.8  244.37  4982.8  243.27
  4992.8  239.95  5002.8  236.35  5029.8  235.84  5032.5  235.34  5035.8  235.84
  5042.8  237.65  5062.8  242.41  5072.8   243.2  5182.8  246.48  5232.8  249.27
  5247.1     249  5267.2  251.39    5282  251.65    5303  254.24  5317.8  257.12
  5338.7  258.58  5344.8  259.86  5359.7  260.21  5380.8  262.36  5436.3  265.99
#Mann= 3 ,-1 , 0
  4661.4     .16       0  5029.8     .07       0  5035.8     .16       0
Bank Sta=4992.8,5042.8
XS Rating Curve= 0 ,0
Exp/Cntr=0.3,0.1

Type RM Length L Ch R = 1 ,1389    ,152,152,152
BEGIN DESCRIPTION:
UNT 085 IN LACR 3.0
END DESCRIPTION:
XS GIS Cut Line= 3
      2268387.74     13202296.84      2268587.72     13202046.85
      2268787.74     13201846.84
#Sta/Elev= 30
  4690.2  253.49  4697.4  253.54  4703.8  252.43  4726.2  251.89  4732.6  250.94
  4740.6  250.94  4790.2  248.44  4796.6  247.49  4818.2  246.65  4831.8  245.46
  4860.7  244.19  4875.1  244.16  4882.3  243.21  4895.9  242.97  4924.7   241.2
  4932.7  241.26  4939.1  240.77  4946.3  238.96  4974.3  234.91  5000.1  234.06
  5002.9  233.56  5006.1  234.06  5013.9  234.25  5024.5   235.5  5038.6  240.32
  5123.5  243.34  5222.5  248.96  5264.9  253.14  5289.6  257.69  5293.2  257.69
#Mann= 3 ,-1 , 0
  4690.2     .16       0  5000.1     .07       0  5006.1     .16       0
Bank Sta=4946.3,5038.6
XS Rating Curve= 0 ,0
Exp/Cntr=0.3,0.1

Type RM Length L Ch R = 1 ,1237    ,51,51,51
BEGIN DESCRIPTION:
Mapping XS c864fd54
END DESCRIPTION:
XS GIS Cut Line= 3
      2268486.02     13202323.32      2268673.77     13202172.47
      2268851.65     13201971.81
#Sta/Elev= 30
  4703.2  250.91  4716.7  250.12  4723.1  249.01  4737.5  248.72  4751.9  246.88
  4758.3  244.91  4766.3   244.4  4772.7  244.99  4780.7  244.06  4801.5  245.53
  4836.7  244.31  4851.1  242.37  4859.1  243.03  4908.7  240.62  4915.1  239.17
  4923.1  238.62  4936.3  235.93    4993  233.85  4997.5  233.09  5000.3  232.59
  5003.5  233.09  5014.8  233.27  5021.4  236.97    5029  238.95  5064.1  239.79
  5113.4  242.47  5170.3  245.87  5184.5  247.36  5198.8  247.64  5212.2   249.3
#Mann= 3 ,-1 , 0
  4703.2     .16       0  4997.5     .07       0  5003.5     .16       0
Bank Sta=4915.1,5029
XS Rating Curve= 0 ,0
Exp/Cntr=0.3,0.1

Type RM Length L Ch R = 1 ,1186    ,69,69,69
BEGIN DESCRIPTION:
Mapping XS 7ffc21f3
END DESCRIPTION:
XS GIS Cut Line= 3
      2268509.04     13202352.73      2268730.54     13202187.48
      2268873.17     13201983.92
#Sta/Elev= 30
       0250.6293   19.95248.2039   29.93246.1265   49.89 243.981   69.84244.1708
   79.82245.2276    89.8245.2189  109.75244.6262  139.68241.6349  149.66242.6096
  159.64242.7236  179.59 241.872  199.55242.2282  209.52242.0004  228.65242.8422
   237.8242.3085   256.1242.6067  274.39241.2055  283.54241.4001  292.92241.0235
   302.3240.3008  311.67240.1835  330.43240.8452  349.19239.6818  367.94239.3976
  433.83242.3666  462.15244.5279  481.02245.5204  518.78248.3414  525.68249.1982
#Mann= 3 , 0 , 0
       0     .16       0  292.92     .07       0  330.43     .16       0
#XS Ineff= 2 , 0
       0                     330       0  240.79
Permanent Ineff=
       F       T
Bank Sta=292.92,330.43
XS Rating Curve= 0 ,0
Exp/Cntr=0.3,0.1

Type RM Length L Ch R = 1 ,1117    ,128,128,128
BEGIN DESCRIPTION:
Mapping XS 4f01a8e0
END DESCRIPTION:
XS GIS Cut Line= 3
      2268603.25      13202416.6      2268783.36     13202222.38
      2268908.49     13201990.46
#Sta/Elev= 30
  4741.9  246.46  4858.1  242.75  4864.9  242.04  4907.5  240.69  4943.2  238.94
  4957.3     238  4964.1  236.21  4971.5  236.09  4992.5  232.84  4996.8  232.63
  4999.6  232.13  5002.8  232.63  5006.3  232.95  5013.1  235.54  5022.6  236.41
  5044.5  237.34  5050.2  237.01  5066.4  237.38  5088.3  238.66    5094  238.34
    5104  238.77  5115.9  239.97  5132.1  240.64    5138  241.47    5154  241.75
  5175.9  242.99  5197.8  245.03    5214  245.74  5241.5  248.54  5270.3  250.69
#Mann= 3 ,-1 , 0
  4741.9     .16       0  4996.8     .07       0  5002.8     .16       0
Bank Sta=4996.8,5002.8
XS Rating Curve= 0 ,0
Exp/Cntr=0.3,0.1

Type RM Length L Ch R = 1 ,989     ,378,378,378
BEGIN DESCRIPTION:
UNT 085 IN LACR 2.0
END DESCRIPTION:
XS GIS Cut Line= 3
      2268787.71     13202446.87      2268887.72     13202296.85
      2268987.71     13201996.88
#Sta/Elev= 30
  4804.9  242.64  4812.4  241.87  4890.6  238.45  4920.6  237.76  4926.6  237.33
  4935.6  233.85  4941.6  236.12  4949.1  232.04  4956.7  233.56 4960.57  232.27
  4962.7  231.33  4974.7   230.4  4977.4   229.9  4980.7   230.4  4982.2  231.06
  4995.7  231.33  5027.4  231.07  5048.4  232.71    5059   236.4  5080.1  238.06
  5122.2  239.96  5185.5  243.73    5196   245.1  5217.1  246.02  5248.7   248.8
  5259.3  250.28  5269.8  250.84  5280.3  252.44  5298.8  256.43  5301.4  256.43
#Mann= 3 ,-1 , 0
  4804.9     .16       0  4974.7     .07       0  4980.7     .16       0
#XS Ineff= 2 , 0
         4956.82  233.59
Permanent Ineff=
       F       F
Bank Sta=4960.57,5048.4
XS Rating Curve= 0 ,0
Exp/Cntr=0.3,0.1

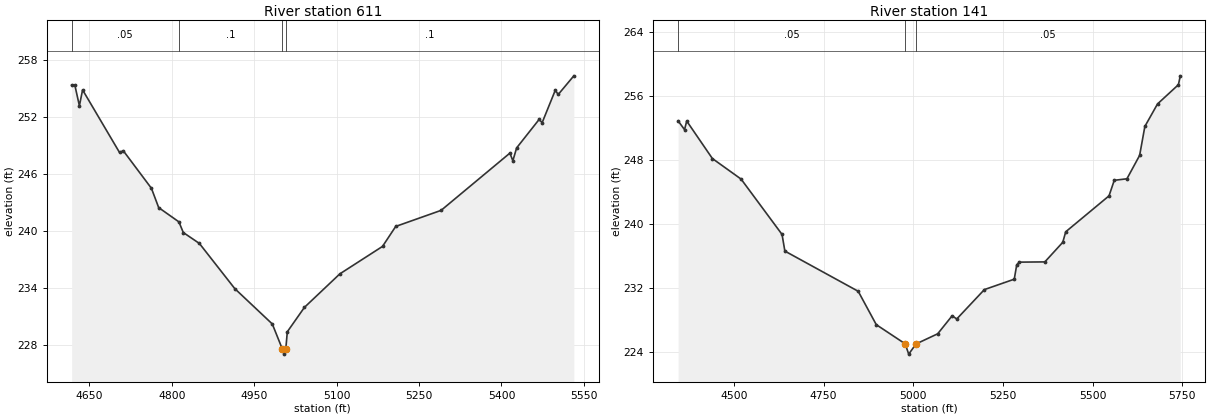
Type RM Length L Ch R = 1 ,611     ,470,470,470
BEGIN DESCRIPTION:
Mapping XS 682d6f25
END DESCRIPTION:
XS GIS Cut Line= 3
      2268974.31     13202841.84      2269245.16     13202383.47
      2269099.87     13202030.62
#Sta/Elev= 30
  4617.7  255.36  4623.5  255.36  4631.8  253.19  4637.6  254.86  4704.8  248.28
  4711.7  248.46  4762.9  244.51  4776.1  242.48  4812.9  240.98  4820.9  239.86
  4850.2  238.71  4914.6  233.96  4982.9  230.24  5001.4  227.57  5004.1  227.07
  5007.4  227.57  5010.2  229.42  5041.4  231.99  5105.8  235.51  5183.5   238.4
  5207.5   240.5  5290.1  242.19  5415.3  248.21  5420.7  247.41  5427.6  248.76
  5468.6  251.76    5474  251.41  5497.9  254.82  5503.3  254.38  5531.7  256.34
#Mann= 4 ,-1 , 0
  4617.7     .05       0  4812.9      .1       0  5001.4     .07       0
  5007.4      .1       0
Bank Sta=5001.4,5007.4
XS Rating Curve= 0 ,0
Exp/Cntr=0.3,0.1

Type RM Length L Ch R = 1 ,141     ,0,0,0
BEGIN DESCRIPTION:
UNT 085 IN LACR 1.0
END DESCRIPTION:
XS GIS Cut Line= 4
      2269300.71     13203064.03      2269557.66     13202883.47
      2269627.11     13202307.08      2269224.54     13202001.68
#Sta/Elev= 30
  4344.6  252.86  4362.5  251.77  4368.6  252.84  4440.1  248.16  4520.2  245.59
  4634.3  238.68  4642.2   236.6  4846.6  231.58    4897  227.41  4977.5  225.02
  4987.4  223.73  5007.8     225  5068.2  226.27  5108.5  228.52  5121.3  228.12
  5198.3  231.79  5281.6  233.09  5288.6   234.9  5296.2  235.22  5366.9  235.25
  5416.9   237.7  5425.1  239.01  5545.8   243.5  5560.4  245.44  5595.7  245.63
  5631.1  248.55  5645.7  252.17    5681  254.98  5739.2  257.38  5744.5  258.49
#Mann= 3 , 0 , 0
  4344.6     .05       0  4977.5    .035       0  5007.8     .05       0
Bank Sta=4977.5,5007.8
XS Rating Curve= 0 ,0
Exp/Cntr=0.3,0.1

Chan Stop Cuts=-1
Use User Specified Reach Order=0
Composite Channel Slope=5

--- UNT 085 IN LACR.g02 (geometry) ---

Geom Title=Dummy
Program Version=4.10

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
River Reach=UNT 085 IN LACR ,Reach-1
Reach XY= 25
      2268337.72     13201046.85      2268387.72     13201096.85
      2268387.72     13201196.85      2268437.72     13201246.85
      2268437.72     13201396.85      2268487.72     13201446.85
      2268487.72     13201896.85      2268537.72     13201946.85
      2268537.72     13201996.86      2268587.72     13202046.85
      2268637.72     13202096.85      2268687.72     13202096.85
      2268687.72     13202146.86      2268737.72     13202196.85
      2268787.72     13202246.85      2268837.72     13202246.85
      2268887.72     13202296.85      2268937.72     13202296.85
      2269087.72     13202446.85      2269137.72     13202496.86
      2269187.72     13202546.85      2269237.72     13202596.85
      2269487.72     13202596.85      2269537.72     13202546.85
      2269737.72     13202546.85

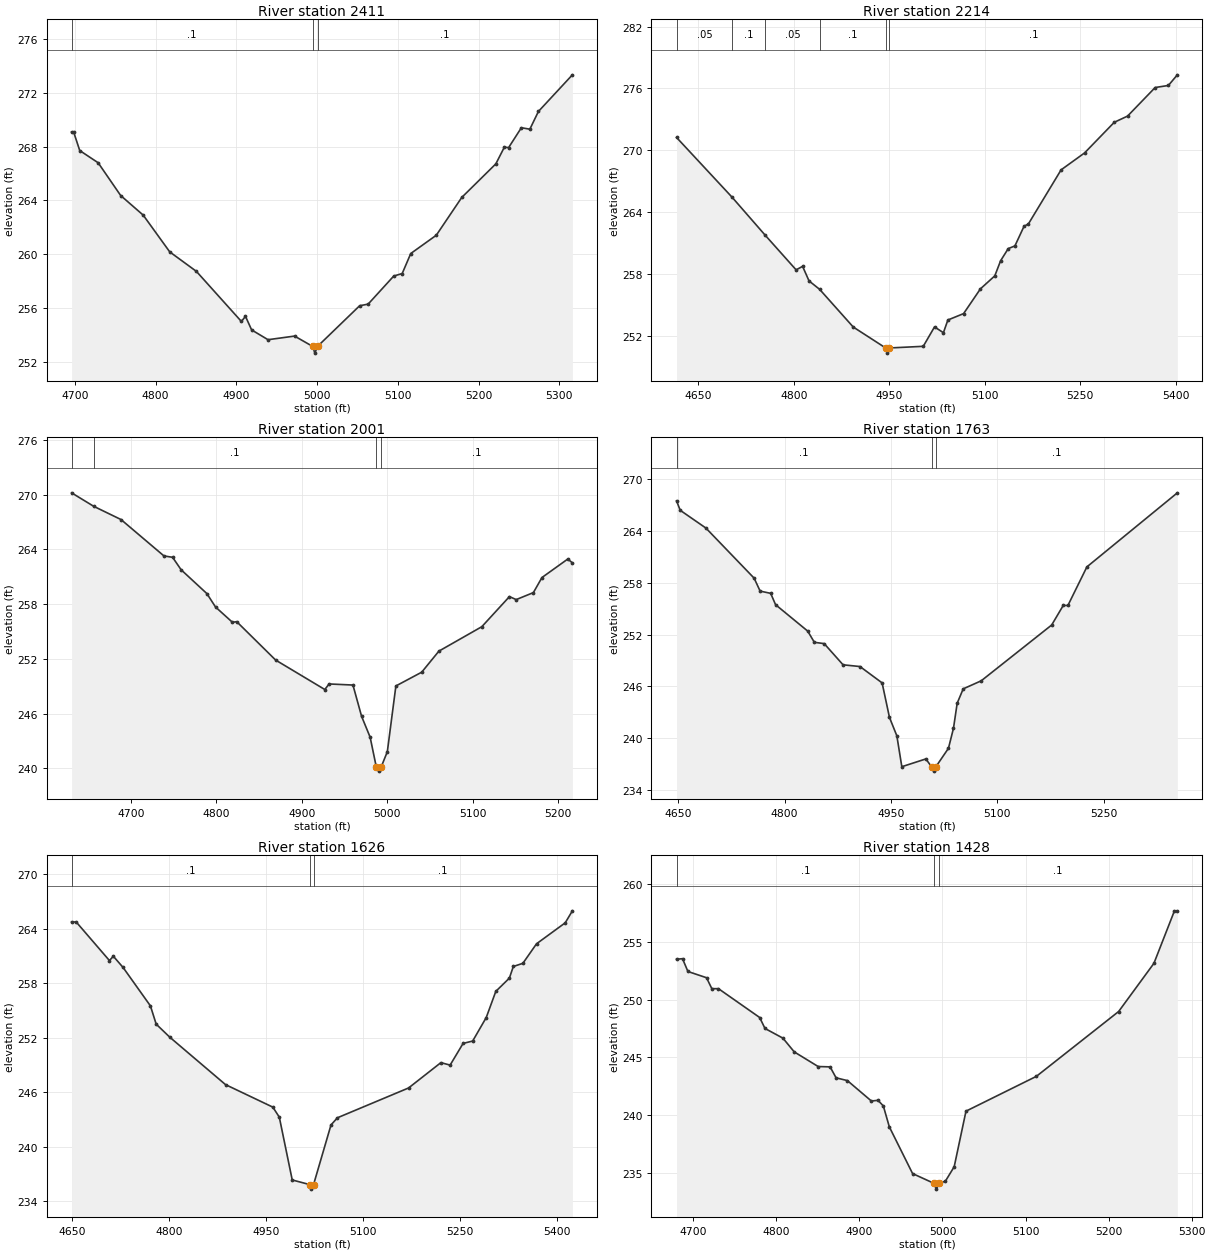
Type RM Length L Ch R = 1 ,2411    ,197,197,197
BEGIN DESCRIPTION:
UNT 085 IN LACR 5.0
END DESCRIPTION:
XS GIS Cut Line= 3
      2268087.76     13201196.85      2268387.72     13201146.85
      2268687.69     13201046.86
#Sta/Elev= 30
  4695.9  269.11  4698.4  269.11    4706  267.72  4728.8  266.81  4756.7  264.37
  4784.6  262.91  4817.5  260.17  4850.5  258.72  4906.2  254.99  4911.3  255.37
  4918.9  254.36  4939.2  253.63  4972.1   253.9  4994.5  253.13  4997.2  252.63
  5000.5  253.13  5052.7  256.16  5063.2  256.28  5094.9  258.37  5105.4  258.56
    5116  260.05  5147.6  261.41  5179.2  264.23  5221.4  266.73  5231.9  267.97
  5237.2  267.94    5253  269.42  5263.5  269.31  5274.1  270.63  5316.2  273.36
#Mann= 3 ,-1 , 0
  4695.9      .1       0  4994.5     .07       0  5000.5      .1       0
Bank Sta=4994.5,5000.5
XS Rating Curve= 0 ,0
Exp/Cntr=0.3,0.1

Type RM Length L Ch R = 1 ,2214    ,213,213,213
BEGIN DESCRIPTION:
Mapping XS dbc82982
END DESCRIPTION:
XS GIS Cut Line= 4
      2268062.16     13201400.34      2268339.95     13201354.76
      2268713.22     13201231.07      2268802.04     13201161.74
#Sta/Elev= 30
  4615.5  271.25  4703.1  265.44  4754.7  261.79  4803.5  258.42  4813.7  258.76
  4823.8  257.35  4840.5  256.53  4893.3  252.88  4944.3  250.85  4947.1  250.35
  4950.3  250.85  5003.4  251.01  5021.1  252.89  5035.1  252.33  5042.1  253.56
  5066.8  254.18  5093.3  256.58  5115.9  257.84    5125   259.3    5137  260.48
  5147.5  260.74  5161.9  262.65  5168.6  262.86  5220.1  268.11    5257  269.75
  5303.7  272.72  5324.6  273.32    5368  276.09  5388.8  276.29  5402.9  277.32
#Mann= 6 ,-1 , 0
  4615.5     .05       0  4703.1      .1       0  4754.7     .05       0
  4840.5      .1       0  4944.3     .07       0  4950.3      .1       0
Bank Sta=4944.3,4950.3
XS Rating Curve= 0 ,0
Exp/Cntr=0.3,0.1

Type RM Length L Ch R = 1 ,2001    ,238,238,238
BEGIN DESCRIPTION:
Mapping XS 2f186675
END DESCRIPTION:
XS GIS Cut Line= 2
      2268120.18     13201550.13      2268703.15     13201494.61
#Sta/Elev= 30
  4630.8  270.21  4656.7  268.73  4688.6  267.28  4738.8  263.29  4748.9  263.14
  4758.9  261.77    4789  259.16  4799.1  257.69  4818.9  256.01  4823.9  256.08
  4869.4  251.87  4926.9  248.64  4931.9  249.25  4959.8  249.13  4969.9   245.7
  4979.9  243.41    4987  240.19  4989.7  239.69    4993  240.19    5000  241.82
    5010  249.03  5040.2  250.54  5060.3  252.85  5110.5  255.53  5142.8  258.83
  5150.7   258.5  5170.8  259.27  5180.8  260.92    5211  262.95  5216.4  262.53
#Mann= 4 ,-1 , 0
  4630.8     .05       0  4656.7      .1       0    4987     .07       0
    4993      .1       0
Bank Sta=4987,4993
XS Rating Curve= 0 ,0
Exp/Cntr=0.3,0.1

Type RM Length L Ch R = 1 ,1763    ,137,137,137
BEGIN DESCRIPTION:
Mapping XS 7ee62bb3
END DESCRIPTION:
XS GIS Cut Line= 4
      2268159.81     13201688.95      2268376.84     13201784.45
      2268674.15     13201699.82      2268791.67     13201590.85
#Sta/Elev= 30
  4647.6  267.45  4652.8  266.36    4689  264.31  4757.1  258.51  4765.5  257.02
  4780.4  256.76  4787.3  255.45  4832.6   252.4    4842   251.1  4855.9  250.95
  4882.5   248.5  4906.4   248.3  4937.6  246.41    4948  242.41  4958.4  240.29
  4965.4  236.72  4999.3  237.62  5007.4  236.71  5010.1  236.21  5013.4  236.71
  5031.2  238.85  5038.3  241.17  5043.5  244.06    5052  245.72  5077.4  246.65
  5176.8   253.1  5193.1  255.36  5199.7  255.36  5226.5  259.82  5354.1  268.38
#Mann= 3 ,-1 , 0
  4647.6      .1       0  5007.4     .07       0  5013.4      .1       0
Bank Sta=5007.4,5013.4
XS Rating Curve= 0 ,0
Exp/Cntr=0.3,0.1

Type RM Length L Ch R = 1 ,1626    ,198,198,198
BEGIN DESCRIPTION:
UNT 085 IN LACR 4.0
END DESCRIPTION:
XS GIS Cut Line= 4
       2268175.7     13201758.46      2268377.11     13201890.41
      2268717.38     13201890.41      2268828.08     13201731.29
#Sta/Elev= 30
  4648.6  264.78  4655.9  264.75  4707.2  260.51  4713.2  260.99  4728.3  259.75
  4770.6  255.52  4779.5  253.51  4800.6  252.07  4886.8  246.85    4960  244.37
    4970  243.27    4990  236.35    5017  235.84  5019.7  235.34    5023  235.84
    5050  242.41    5060   243.2    5170  246.48    5220  249.27  5234.3     249
  5254.4  251.39  5269.2  251.65  5290.2  254.24    5305  257.12    5326  258.58
  5332.1  259.86  5346.9  260.21    5368  262.36  5412.4  264.67  5423.5  265.99
#Mann= 3 ,-1 , 0
  4648.6      .1       0    5017     .07       0    5023      .1       0
Bank Sta=5017,5023
XS Rating Curve= 0 ,0
Exp/Cntr=0.3,0.1

Type RM Length L Ch R = 1 ,1428    ,177,177,177
BEGIN DESCRIPTION:
UNT 085 IN LACR 3.0
END DESCRIPTION:
XS GIS Cut Line= 3
      2268387.69     13202296.89      2268587.72     13202046.85
      2268787.69     13201846.89
#Sta/Elev= 30
  4679.8  253.49    4687  253.54  4693.5  252.43  4715.9  251.89  4722.3  250.94
  4730.3  250.94  4779.9  248.44  4786.3  247.49  4807.9  246.65  4821.5  245.46
  4850.3  244.19  4864.7  244.16  4871.9  243.21  4885.5  242.97  4914.4   241.2
  4922.4  241.26  4928.8  240.77    4936  238.96    4964  234.91  4989.8  234.06
  4992.5  233.56  4995.8  234.06  5003.5  234.25  5014.1   235.5  5028.3  240.32
  5113.1  243.34  5212.1  248.96  5254.6  253.14  5279.3  257.69  5282.8  257.69
#Mann= 3 ,-1 , 0
  4679.8      .1       0  4989.8     .07       0  4995.8      .1       0
Bank Sta=4989.8,4995.8
XS Rating Curve= 0 ,0
Exp/Cntr=0.3,0.1

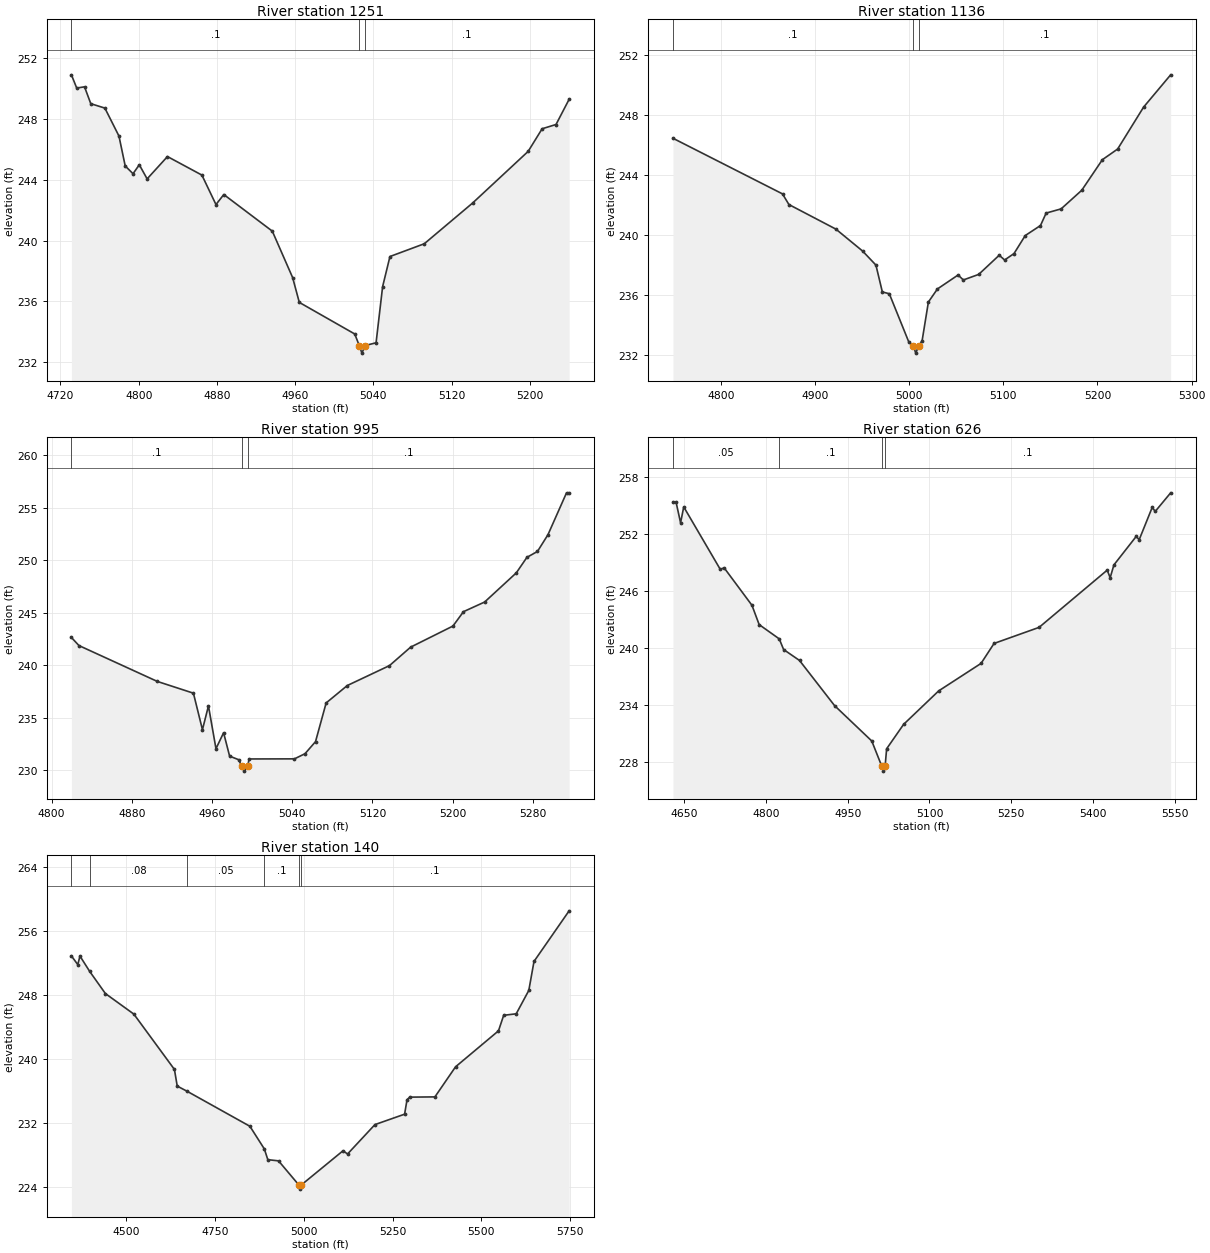
Type RM Length L Ch R = 1 ,1251    ,115,115,115
BEGIN DESCRIPTION:
Mapping XS c864fd54
END DESCRIPTION:
XS GIS Cut Line= 3
      2268486.07     13202323.27      2268673.77     13202172.47
      2268851.63     13201971.83
#Sta/Elev= 30
  4731.2  250.91  4736.6  250.04  4744.6  250.12    4751  249.01  4765.4  248.72
  4779.8  246.88  4786.2  244.91  4794.2   244.4  4800.6  244.99  4808.6  244.06
  4829.4  245.53  4864.6  244.31    4879  242.37    4887  243.03  4936.6  240.62
  4957.4  237.56  4964.2  235.93  5020.9  233.85  5025.5  233.09  5028.2  232.59
  5031.5  233.09  5042.7  233.27  5049.4  236.97  5056.9  238.95    5092  239.79
  5141.4  242.47  5198.2  245.87  5212.5  247.36  5226.7  247.64  5240.1   249.3
#Mann= 3 ,-1 , 0
  4731.2      .1       0  5025.5     .07       0  5031.5      .1       0
Bank Sta=5025.5,5031.5
XS Rating Curve= 0 ,0
Exp/Cntr=0.3,0.1

Type RM Length L Ch R = 1 ,1136    ,141,141,141
BEGIN DESCRIPTION:
Mapping XS 4f01a8e0
END DESCRIPTION:
XS GIS Cut Line= 3
      2268603.21     13202416.64      2268783.36     13202222.38
      2268908.46     13201990.51
#Sta/Elev= 30
  4749.3  246.46  4865.6  242.75  4872.4  242.04  4922.3   240.4  4950.6  238.94
  4964.8     238  4971.6  236.21    4979  236.09  4999.9  232.84  5004.3  232.63
  5007.1  232.13  5010.3  232.63  5013.8  232.95  5020.5  235.54  5030.1  236.41
    5052  237.34  5057.6  237.01  5073.9  237.38  5095.7  238.66  5101.4  238.34
  5111.4  238.77  5123.3  239.97  5139.5  240.64  5145.5  241.47  5161.4  241.75
  5183.3  242.99  5205.2  245.03  5221.4  245.74    5249  248.54  5277.7  250.69
#Mann= 3 ,-1 , 0
  4749.3      .1       0  5004.3     .07       0  5010.3      .1       0
Bank Sta=5004.3,5010.3
XS Rating Curve= 0 ,0
Exp/Cntr=0.3,0.1

Type RM Length L Ch R = 1 ,995     ,369,369,369
BEGIN DESCRIPTION:
UNT 085 IN LACR 2.0
END DESCRIPTION:
XS GIS Cut Line= 3
      2268787.71     13202446.87      2268887.72     13202296.85
      2268987.71     13201996.88
#Sta/Elev= 30
  4819.7  242.64  4827.2  241.87  4905.4  238.45  4941.4  237.33  4950.4  233.85
  4956.4  236.12  4963.9  232.04  4971.5  233.56  4977.5  231.33  4986.5  230.99
  4989.5   230.4  4992.2   229.9  4995.5   230.4    4997  231.06  5042.2  231.07
  5052.7  231.56  5063.2  232.71  5073.8   236.4  5094.9  238.06    5137  239.96
  5158.1  241.72  5200.3  243.73  5210.8   245.1  5231.9  246.02  5263.5   248.8
  5274.1  250.28  5284.6  250.84  5295.1  252.44  5313.6  256.43  5316.2  256.43
#Mann= 3 ,-1 , 0
  4819.7      .1       0  4989.5     .07       0  4995.5      .1       0
Bank Sta=4989.5,4995.5
XS Rating Curve= 0 ,0
Exp/Cntr=0.3,0.1

Type RM Length L Ch R = 1 ,626     ,486,486,486
BEGIN DESCRIPTION:
Mapping XS 682d6f25
END DESCRIPTION:
XS GIS Cut Line= 3
      2268974.35     13202841.76      2269245.16     13202383.47
      2269099.84     13202030.54
#Sta/Elev= 30
  4628.9  255.36  4634.6  255.36  4642.9  253.19  4648.7  254.86  4715.9  248.28
  4722.8  248.46    4774  244.51  4787.2  242.48  4824.1  240.98  4832.1  239.86
  4861.3  238.71  4925.7  233.96    4994  230.24  5012.5  227.57  5015.2  227.07
  5018.5  227.57  5021.3  229.42  5052.5  231.99  5116.9  235.51  5194.7   238.4
  5218.6   240.5  5301.3  242.19  5426.4  248.21  5431.8  247.41  5438.7  248.76
  5479.7  251.76  5485.1  251.41  5509.1  254.82  5514.5  254.38  5542.9  256.34
#Mann= 4 ,-1 , 0
  4628.9     .05       0  4824.1      .1       0  5012.5     .07       0
  5018.5      .1       0
Bank Sta=5012.5,5018.5
XS Rating Curve= 0 ,0
Exp/Cntr=0.3,0.1

Type RM Length L Ch R = 1 ,140     ,0,0,0
BEGIN DESCRIPTION:
UNT 085 IN LACR 1.0
END DESCRIPTION:
XS GIS Cut Line= 4
      2269300.71     13203064.03      2269557.66     13202883.47
      2269627.11     13202307.08      2269224.54     13202001.69
#Sta/Elev= 30
  4346.9  252.86  4364.8  251.77  4370.9  252.84  4398.3  250.92  4442.4  248.16
  4522.5  245.59  4636.6  238.68  4644.5   236.6  4672.8  235.94  4848.9  231.58
  4889.5  228.75  4899.3  227.41  4929.5  227.26  4986.9  224.23  4989.7  223.73
  4992.9  224.23  5110.8  228.52  5123.6  228.12  5200.6  231.79    5284  233.09
  5290.9   234.9  5298.5  235.22  5369.3  235.25  5427.4  239.01  5548.1   243.5
  5562.7  245.44    5598  245.63  5633.4  248.55    5648  252.17  5746.8  258.49
#Mann= 6 ,-1 , 0
  4346.9     .05       0  4398.3     .08       0  4672.8     .05       0
  4889.5      .1       0  4986.9     .07       0  4992.9      .1       0
Bank Sta=4986.9,4992.9
XS Rating Curve= 0 ,0
Exp/Cntr=0.3,0.1