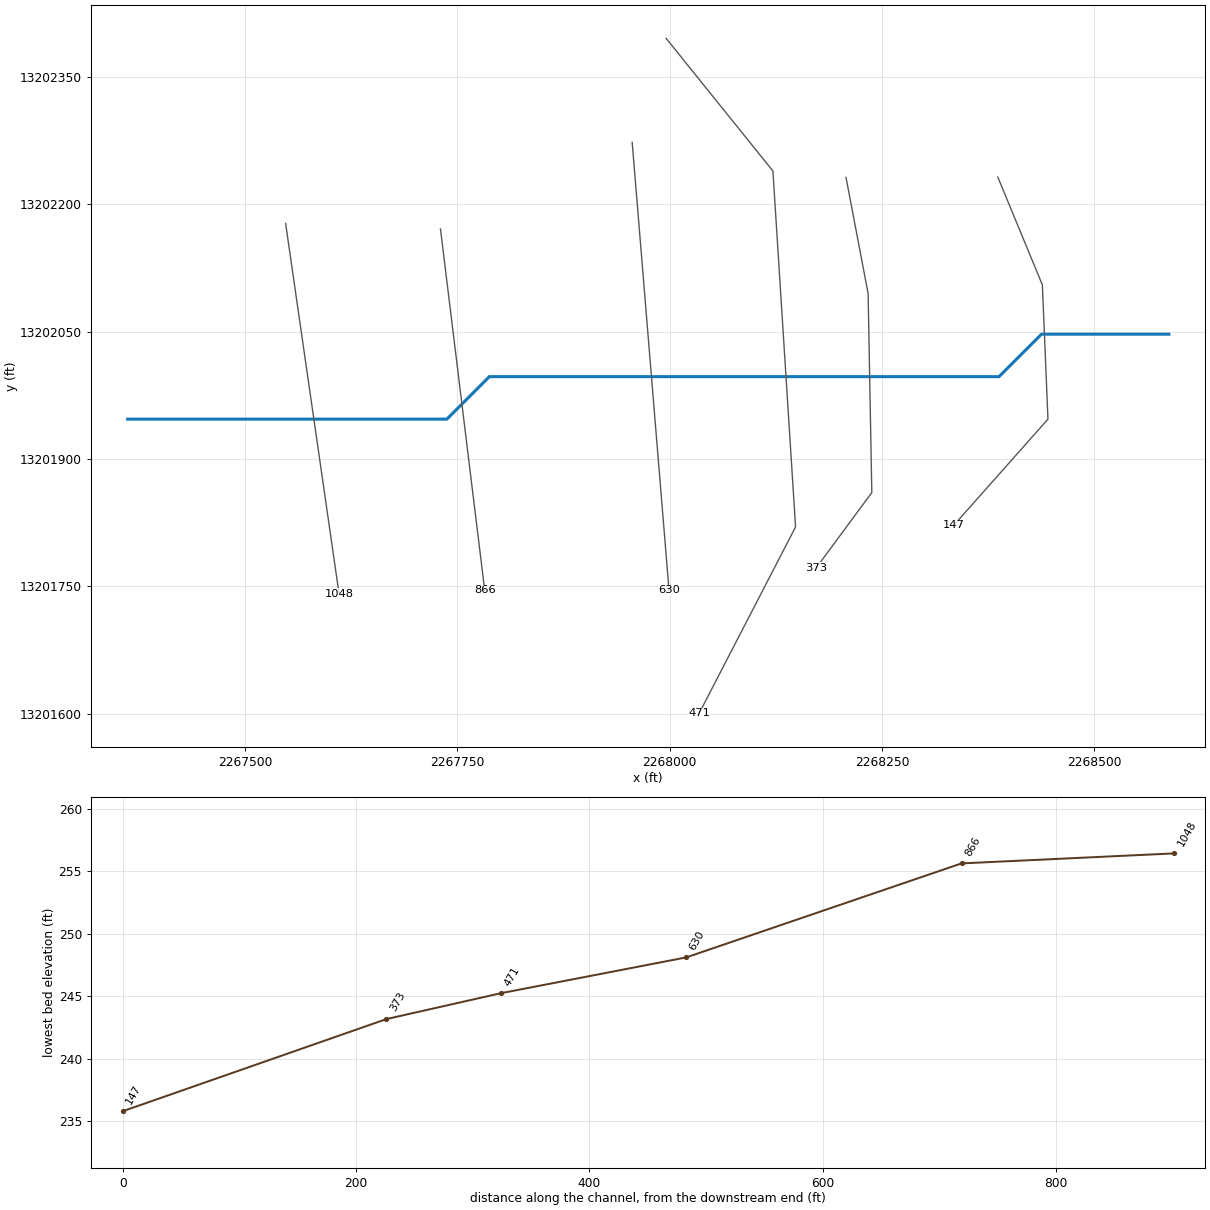
--- UNT 086 IN LACR.prj (project) ---

Proj Title=UNT 086 IN LACR Base Level Engineering
Current Plan=p01
Default Exp/Contr=0.3,0.1
English Units
Geom File=g01
Flow File=f01
Plan File=p01
Y Axis Title=Elevation
X Axis Title(PF)=Main Channel Distance
X Axis Title(XS)=Station
BEGIN DESCRIPTION:
UNT 086 IN LACR
END DESCRIPTION:
DSS Export Rating Curves= 0
DSS Export Rating Curve Sorted= 0
DSS Export Volume Flow Curves= 0
DXF OffsetX= 0
DXF OffsetY= 0
DXF ScaleX= 1
DXF ScaleY= 10

--- UNT 086 IN LACR.p01 (plan) ---

Plan Title=Multiple Run
Short Identifier=Multiple
Geom File=g01
Flow File=f01
Subcritical Flow
K Sum by GR= 0
Std Step Tol= 0.01
Critical Tol= 0.01
Num of Std Step Trials= 20
Max Error Tol= 0.3
Flow Tol Ratio= 0.001
Split Flow NTrial= 30
Split Flow Tol= 0.02
Split Flow Ratio= 0.02
Log Output Level= 0
Friction Slope Method= 1
Unsteady Friction Slope Method= 2
Unsteady Bridges Friction Slope Method= 1
Parabolic Critical Depth
Global Vel Dist=  1 , 1 , 1
Global Log Level= 0
CheckData=True
Encroach Param= -1, 0, 0, 0
BEGIN DESCRIPTION:
Multiple Run
END DESCRIPTION:

--- UNT 086 IN LACR.f01 (steady flow) ---

Flow Title=Multiple
Number of Profiles=7
Profile Names=10-year,25-year,50-year,1pct_min,100-year,1pct_plu,500-year
River Rch & RM= UNT 086 IN LACR,Reach-1,1048
      58      73      85      73      98     133     134
Boundary for River Rch & Prof#=UNT 086 IN LACR,Reach-1,1
Up Type=0
Dn Type=3
Dn Slope=0.005
Boundary for River Rch & Prof#=UNT 086 IN LACR,Reach-1,2
Up Type=0
Dn Type=3
Dn Slope=0.005
Boundary for River Rch & Prof#=UNT 086 IN LACR,Reach-1,3
Up Type=0
Dn Type=3
Dn Slope=0.005
Boundary for River Rch & Prof#=UNT 086 IN LACR,Reach-1,4
Up Type=0
Dn Type=3
Dn Slope=0.005
Boundary for River Rch & Prof#=UNT 086 IN LACR,Reach-1,5
Up Type=0
Dn Type=3
Dn Slope=0.005
Boundary for River Rch & Prof#=UNT 086 IN LACR,Reach-1,6
Up Type=0
Dn Type=3
Dn Slope=0.005
Boundary for River Rch & Prof#=UNT 086 IN LACR,Reach-1,7
Up Type=0
Dn Type=3
Dn Slope=0.005

--- UNT 086 IN LACR.g01 (geometry) ---

Geom Title=Existing Conditions
Program Version=4.10

River Reach=UNT 086 IN LACR ,Reach-1
Reach XY= 26
      2267361.91     13201946.85      2267387.72     13201946.85
      2267437.72     13201946.85      2267487.72     13201946.85
      2267537.72     13201946.85      2267587.72     13201946.85
      2267637.72     13201946.85      2267687.72     13201946.85
      2267737.72     13201946.85      2267787.72     13201996.86
      2267837.72     13201996.86      2267887.72     13201996.86
      2267937.72     13201996.86      2267987.72     13201996.86
      2268037.72     13201996.86      2268087.72     13201996.86
      2268137.72     13201996.86      2268187.72     13201996.86
      2268237.72     13201996.86      2268287.72     13201996.86
      2268337.72     13201996.86      2268387.72     13201996.86
      2268437.72     13202046.85      2268487.72     13202046.85
      2268537.72     13202046.85      2268587.72     13202046.85

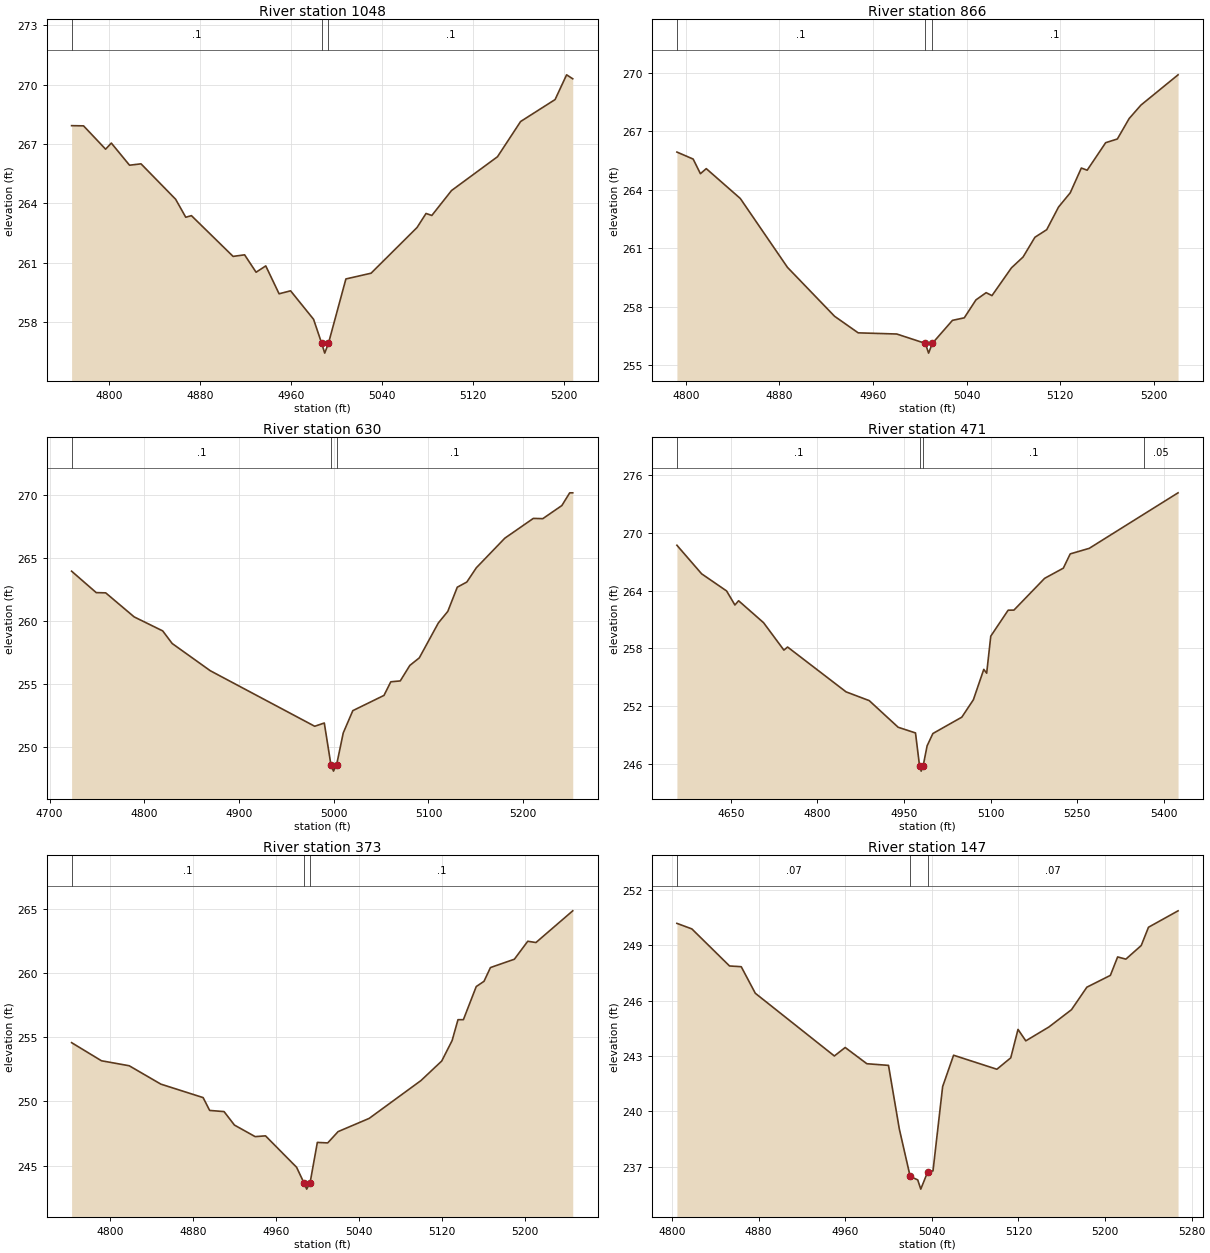
Type RM Length L Ch R = 1 ,1048    ,182,182,182
BEGIN DESCRIPTION:
UNT 086 IN LACR 2.0
END DESCRIPTION:
XS GIS Cut Line= 2
      2267547.85     13202177.27      2267610.72     13201741.48
#Sta/Elev= 30
  4767.2  267.93  4777.7  267.92  4797.1  266.74  4802.1  267.05  4818.1  265.93
  4828.2     266  4858.6  264.21  4867.5   263.3  4872.5  263.38  4909.1  261.32
  4919.2   261.4  4929.3  260.52  4937.8  260.84  4949.5  259.43  4959.6  259.58
  4979.8  258.14  4986.9  256.93  4989.6  256.43  4992.9  256.93  5008.2  260.18
  5030.3  260.47  5070.7  262.78  5078.6  263.49  5083.7  263.39    5101  264.65
  5141.4  266.36  5161.7  268.14    5192  269.25  5202.1   270.5  5207.5   270.3
#Mann= 3 ,-1 , 0
  4767.2      .1       0  4986.9     .07       0  4992.9      .1       0
Bank Sta=4986.9,4992.9
XS Rating Curve= 0 ,0
Exp/Cntr=0.3,0.1

Type RM Length L Ch R = 1 ,866     ,236,236,236
BEGIN DESCRIPTION:
Mapping XS f02ef7b7
END DESCRIPTION:
XS GIS Cut Line= 2
      2267730.15     13202170.69      2267782.23     13201745.36
#Sta/Elev= 30
  4792.3  265.94  4806.2  265.58  4812.4  264.83  4817.4  265.09  4846.5  263.56
  4886.8  260.03  4927.1  257.52  4947.3  256.67  4980.3  256.61  5004.7  256.13
  5007.5  255.63  5010.7  256.13  5027.9  257.31    5038  257.44    5048  258.36
  5056.7  258.73  5061.7  258.58  5078.3     260  5088.3  260.56  5098.4  261.57
  5108.5  261.96  5118.6  263.12  5128.6  263.85  5138.1  265.12  5143.1  265.01
  5158.9  266.42  5168.9  266.61    5179  267.66  5189.1  268.35  5220.8   269.9
#Mann= 3 ,-1 , 0
  4792.3      .1       0  5004.7     .07       0  5010.7      .1       0
Bank Sta=5004.7,5010.7
XS Rating Curve= 0 ,0
Exp/Cntr=0.3,0.1

Type RM Length L Ch R = 1 ,630     ,159,159,159
BEGIN DESCRIPTION:
Mapping XS 57ee8aed
END DESCRIPTION:
XS GIS Cut Line= 2
      2267955.84     13202272.72      2267999.24     13201745.41
#Sta/Elev= 30
  4723.2  263.97  4749.2  262.27  4759.2  262.25  4789.3  260.34  4819.4  259.23
  4829.4  258.23  4869.6  256.07  4979.9  251.66    4990  251.92    4997   248.6
  4999.7   248.1    5003   248.6    5010  251.13  5020.1   252.9    5053  254.11
  5060.2  255.19  5070.2  255.26  5080.3  256.49  5090.3  257.09  5110.4  259.86
  5120.4  260.78  5130.4   262.7  5140.5  263.11  5150.5  264.24  5180.6  266.59
  5210.7  268.16  5220.7  268.14  5240.8  269.18  5249.1  270.19  5252.3  270.19
#Mann= 3 ,-1 , 0
  4723.2      .1       0    4997     .07       0    5003      .1       0
Bank Sta=4997,5003
XS Rating Curve= 0 ,0
Exp/Cntr=0.3,0.1

Type RM Length L Ch R = 1 ,471     ,98,98,98
BEGIN DESCRIPTION:
Mapping XS c7c10451
END DESCRIPTION:
XS GIS Cut Line= 4
      2267995.82     13202395.16      2268121.53     13202238.98
       2268148.2     13201819.93      2268034.67     13201600.44
#Sta/Elev= 30
  4556.9  268.71  4599.7  265.74  4642.9  263.96  4657.3   262.5  4663.7  262.94
  4706.9  260.66  4742.1  257.81  4748.5  258.13  4849.7  253.47  4889.8  252.56
  4939.9  249.79  4969.9   249.2    4977  245.73  4979.7  245.23    4983  245.73
    4990  247.86    5000  249.14  5050.1  250.84  5070.1  252.65  5088.1  255.81
  5093.1  255.41  5100.2  259.26  5130.3  261.96  5140.3  261.97  5193.4  265.27
  5225.8  266.33  5237.7  267.81  5270.7  268.39    5366  271.97  5424.4  274.16
#Mann= 4 ,-1 , 0
  4556.9      .1       0    4977     .07       0    4983      .1       0
    5366     .05       0
Bank Sta=4977,4983
XS Rating Curve= 0 ,0
Exp/Cntr=0.3,0.1

Type RM Length L Ch R = 1 ,373     ,226,226,226
BEGIN DESCRIPTION:
Mapping XS 6e104ebd
END DESCRIPTION:
XS GIS Cut Line= 4
      2268207.58     13202231.48      2268233.62     13202094.78
      2268237.96     13201860.41      2268172.67     13201771.96
#Sta/Elev= 30
  4762.9  254.57  4791.7  253.16  4818.5  252.77    4849  251.34  4889.8  250.29
  4896.1  249.29    4910   249.2    4920  248.15    4940  247.25    4950  247.31
    4980  244.86    4987  243.66  4989.7  243.16    4993  243.66    5000   246.8
    5010  246.76    5020  247.64    5050  248.67    5100  251.62    5120  253.14
    5130  254.73  5135.7  256.36  5140.9  256.36  5153.3  258.94  5160.8  259.35
    5167  260.42  5190.1  261.07    5203  262.47  5210.9  262.37  5246.4  264.84
#Mann= 3 ,-1 , 0
  4762.9      .1       0    4987     .07       0    4993      .1       0
Bank Sta=4987,4993
XS Rating Curve= 0 ,0
Exp/Cntr=0.3,0.1

Type RM Length L Ch R = 1 ,147     ,0,0,0
BEGIN DESCRIPTION:
UNT 086 IN LACR 1.0
END DESCRIPTION:
XS GIS Cut Line= 4
      2268386.31     13202231.79      2268438.77     13202104.87
      2268445.33     13201946.79       2268334.3     13201821.71
#Sta/Elev= 30
  4804.6  250.19  4818.4  249.89  4853.2  247.88    4864  247.84    4877   246.4
    4950     243    4960  243.46    4980  242.58    5000  242.49    5010  239.04
    5020  236.47    5027  236.28  5029.8  235.78  5036.1   236.7  5041.1  236.77
    5050  241.34  5060.1  243.04  5100.1  242.28  5112.9   242.9  5119.6  244.44
  5126.8  243.82  5148.1  244.57    5169  245.51  5183.2  246.73  5204.9  247.37
  5211.6  248.37  5219.2  248.25  5233.4  248.99  5240.1  249.98  5267.4  250.87
#Mann= 3 , 0 , 0
  4804.6     .07       0    5020    .035       0  5036.1     .07       0
Bank Sta=5020,5036.1
XS Rating Curve= 0 ,0
Exp/Cntr=0.3,0.1

Chan Stop Cuts=-1
Use User Specified Reach Order=0
Composite Channel Slope=5