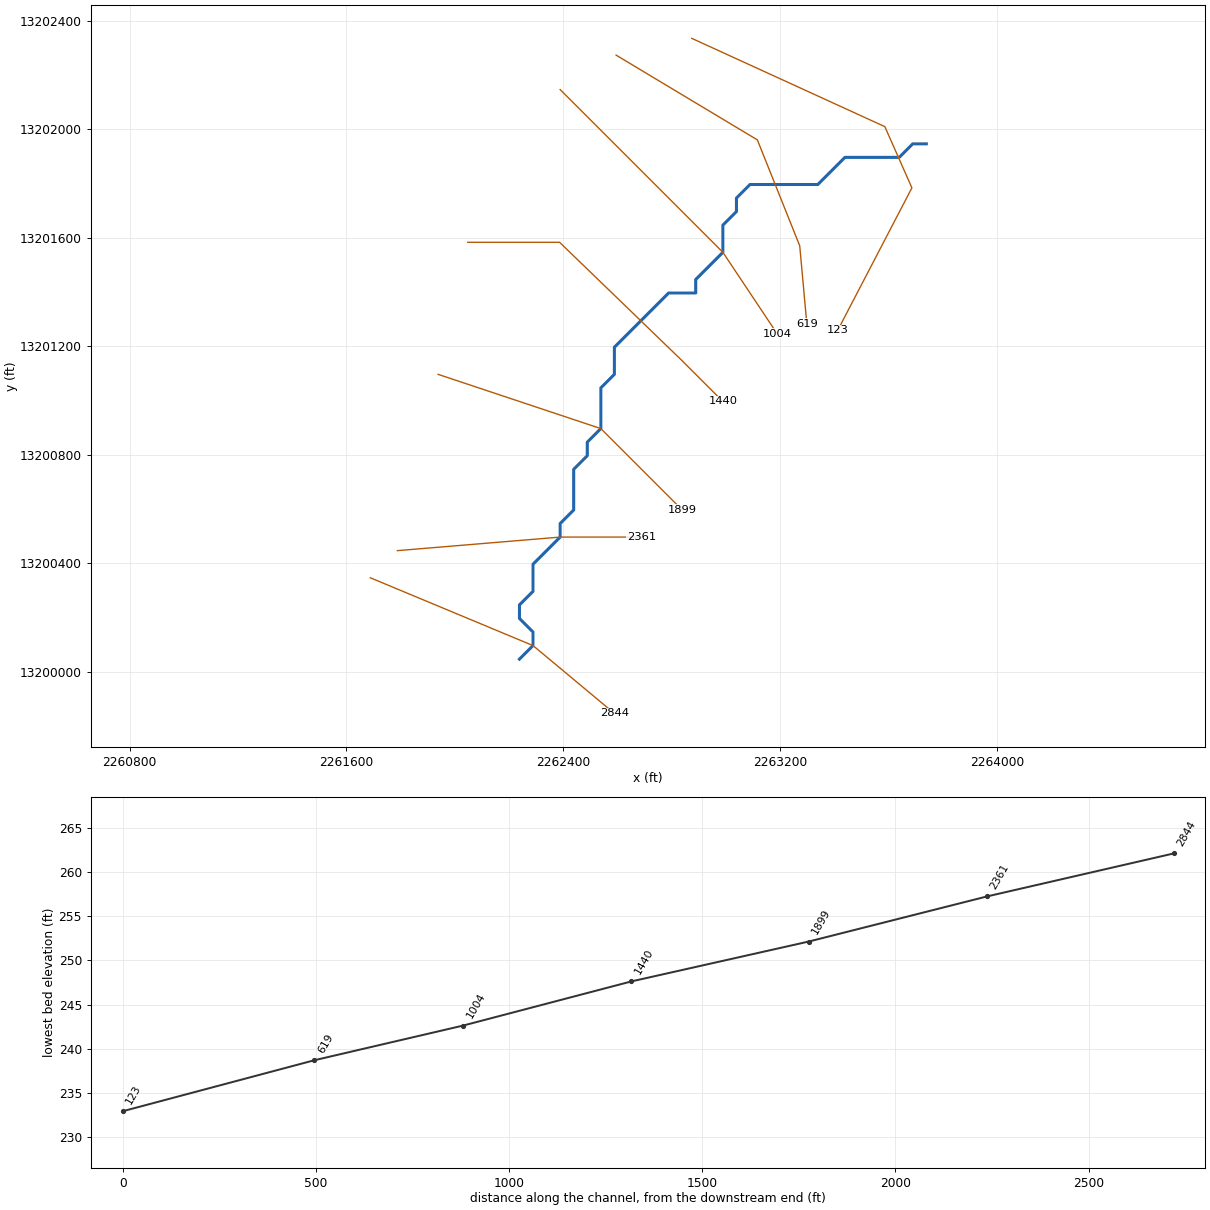
--- UNT 087 IN LACR.prj (project) ---

Proj Title=UNT 087 IN LACR Base Level Engineering
Current Plan=p01
Default Exp/Contr=0.3,0.1
English Units
Geom File=g01
Flow File=f01
Plan File=p01
BEGIN DESCRIPTION:
UNT 087 IN LACR
END DESCRIPTION:

--- UNT 087 IN LACR.p01 (plan) ---

Plan Title=Multiple Run
Short Identifier=Multiple
Geom File=g01
Flow File=f01
Subcritical Flow
K Sum by GR= 0
Std Step Tol= 0.01
Critical Tol= 0.01
Num of Std Step Trials= 20
Max Error Tol= 0.3
Flow Tol Ratio= 0.001
Split Flow NTrial= 30
Split Flow Tol= 0.02
Split Flow Ratio= 0.02
Log Output Level= 0
Friction Slope Method= 1
Unsteady Friction Slope Method= 2
Unsteady Bridges Friction Slope Method= 1
Parabolic Critical Depth
Global Vel Dist=  1 , 1 , 1
Global Log Level= 0
CheckData=True
Encroach Param= -1, 0, 0, 0
BEGIN DESCRIPTION:
Multiple Run
END DESCRIPTION:

--- UNT 087 IN LACR.f01 (steady flow) ---

Flow Title=Multiple
Number of Profiles=7
Profile Names=10-year,25-year,50-year,1pct_min,100-year,1pct_plu,500-year
River Rch & RM= UNT 087 IN LACR,Reach-1,2844
      93     122     144     127     171     231     243
Boundary for River Rch & Prof#=UNT 087 IN LACR,Reach-1,1
Up Type=0
Dn Type=3
Dn Slope=0.005
Boundary for River Rch & Prof#=UNT 087 IN LACR,Reach-1,2
Up Type=0
Dn Type=3
Dn Slope=0.005
Boundary for River Rch & Prof#=UNT 087 IN LACR,Reach-1,3
Up Type=0
Dn Type=3
Dn Slope=0.005
Boundary for River Rch & Prof#=UNT 087 IN LACR,Reach-1,4
Up Type=0
Dn Type=3
Dn Slope=0.005
Boundary for River Rch & Prof#=UNT 087 IN LACR,Reach-1,5
Up Type=0
Dn Type=3
Dn Slope=0.005
Boundary for River Rch & Prof#=UNT 087 IN LACR,Reach-1,6
Up Type=0
Dn Type=3
Dn Slope=0.005
Boundary for River Rch & Prof#=UNT 087 IN LACR,Reach-1,7
Up Type=0
Dn Type=3
Dn Slope=0.005

--- UNT 087 IN LACR.g01 (geometry) ---

Geom Title=Existing Conditions

River Reach=UNT 087 IN LACR,Reach-1
Reach XY= 30
      2262237.72     13200046.85      2262287.72     13200096.85
      2262287.72     13200146.85      2262237.72     13200196.86
      2262237.72     13200246.85      2262287.72     13200296.85
      2262287.72     13200396.85      2262387.72     13200496.85
      2262387.72     13200546.85      2262437.72     13200596.85
      2262437.72     13200746.85      2262487.72     13200796.85
      2262487.72     13200846.86      2262537.72     13200896.85
      2262537.72     13201046.85      2262587.72     13201096.85
      2262587.72     13201196.85      2262787.72     13201396.85
      2262887.72     13201396.85      2262887.72     13201446.85
      2262987.72     13201546.85      2262987.72     13201646.86
      2263037.72     13201696.85      2263037.72     13201746.85
      2263087.72     13201796.85      2263337.72     13201796.85
      2263437.72     13201896.85      2263637.72     13201896.85
      2263687.72     13201946.85      2263737.72     13201946.85

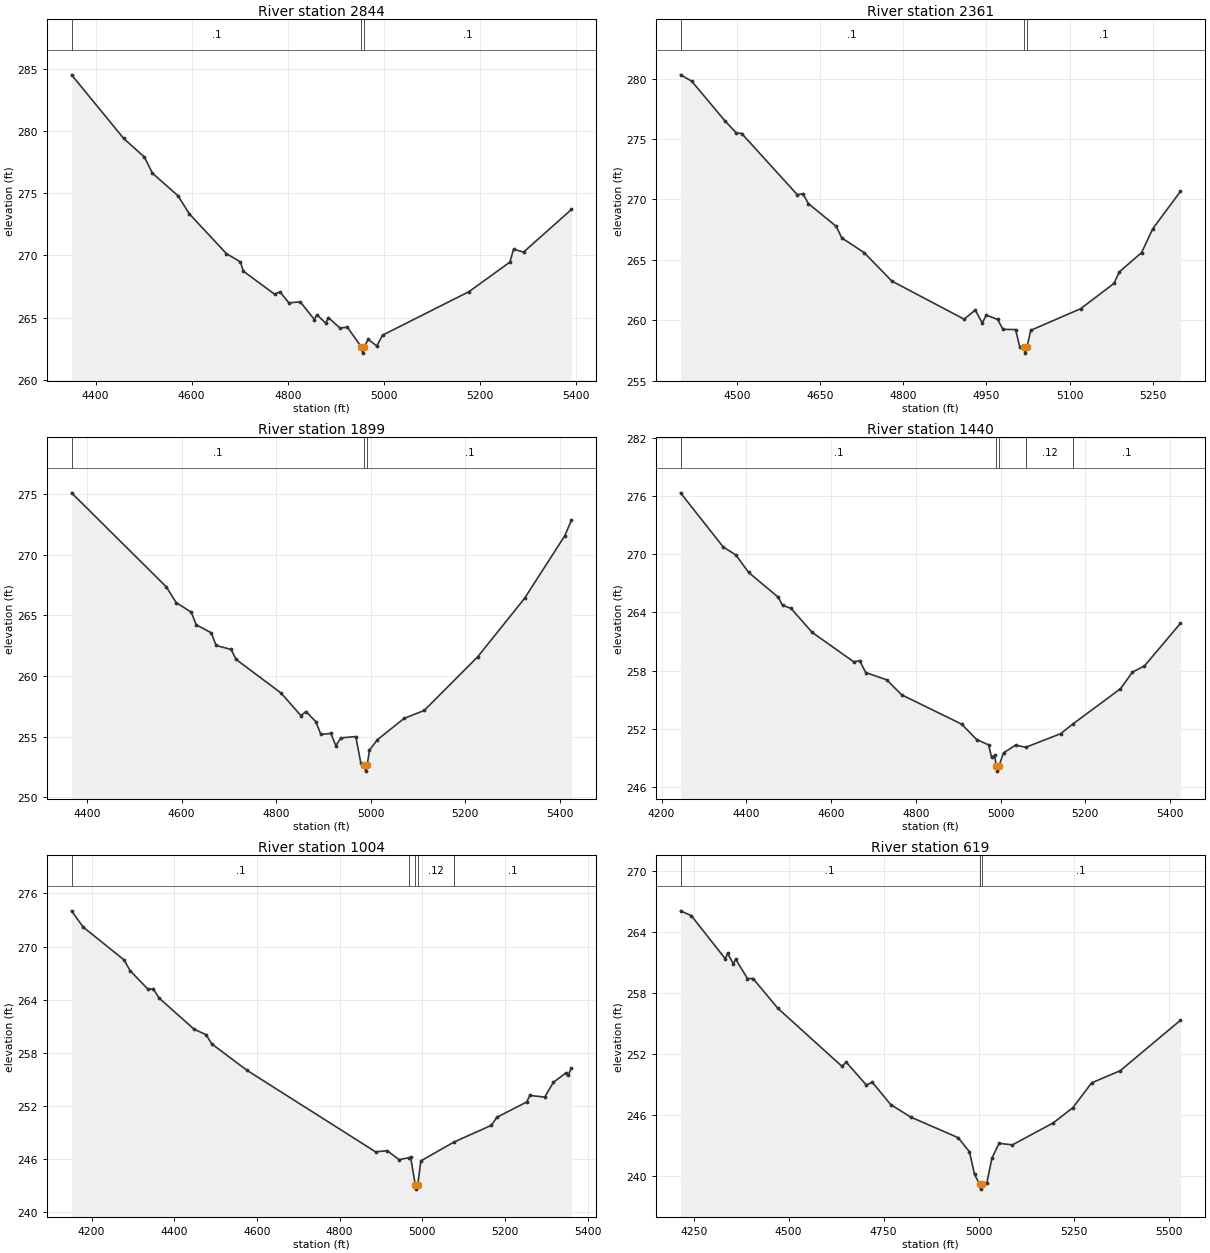
Type RM Length L Ch R = 1,2844,483,483,483
BEGIN DESCRIPTION:
UNT 087 IN LACR 6.0
END DESCRIPTION:
XS GIS Cut Line= 3
      2261687.72     13200346.85      2262287.72     13200096.85
      2262587.71     13199846.86
#Sta/Elev= 30
  4350.0  284.50  4458.3  279.40  4501.7  277.89  4518.5  276.59  4571.5  274.79
  4595.4  273.32  4672.3  270.14  4701.5  269.47  4707.5  268.73  4772.5  266.88
  4783.9  267.06  4802.3  266.18  4826.1  266.26  4855.4  264.84  4860.8  265.23
  4879.2  264.54  4884.6  265.00  4908.5  264.16  4924.2  264.22  4953.1  262.64
  4955.9  262.14  4959.1  262.64  4967.5  263.24  4985.4  262.72  4997.3  263.58
  5177.7  267.09  5262.3  269.45  5270.1  270.49  5290.9  270.26  5390.5  273.68
#Mann=3,-1,0
  4350.0     0.1       0  4953.1    0.07       0  4959.1     0.1       0
Bank Sta=4953.1,4959.1
Exp/Cntr=0.3,0.1

Type RM Length L Ch R = 1,2361,462,462,462
BEGIN DESCRIPTION:
UNT 087 IN LACR 5.0
END DESCRIPTION:
XS GIS Cut Line= 3
      2261787.70     13200446.85      2262387.72     13200496.85
      2262687.72     13200496.85
#Sta/Elev= 30
  4397.9  280.32  4418.0  279.80  4478.2  276.50  4498.3  275.51  4508.3  275.46
  4608.6  270.39  4618.7  270.48  4628.7  269.65  4678.9  267.77  4688.9  266.81
  4729.1  265.60  4779.2  263.24  4909.7  260.08  4929.8  260.84  4942.3  259.77
  4949.8  260.42  4969.9  260.06  4979.9  259.24  5002.5  259.22  5010.0  257.80
  5017.0  257.77  5019.8  257.27  5023.0  257.77  5030.0  259.16  5120.0  260.95
  5180.0  263.04  5190.0  264.01  5230.0  265.60  5250.0  267.57  5300.0  270.66
#Mann=3,-1,0
  4397.9     0.1       0  5017.0    0.07       0  5023.0     0.1       0
Bank Sta=5017,5023
Exp/Cntr=0.3,0.1

Type RM Length L Ch R = 1,1899,459,459,459
BEGIN DESCRIPTION:
UNT 087 IN LACR 4.0
END DESCRIPTION:
XS GIS Cut Line= 3
      2261937.68     13201096.87      2262537.72     13200896.85
      2262837.75     13200596.83
#Sta/Elev= 30
  4367.5  275.09  4567.8  267.34  4588.9  266.03  4620.5  265.26  4631.1  264.21
  4662.7  263.56  4673.2  262.51  4704.9  262.18  4715.4  261.36  4810.3  258.59
  4852.4  256.73  4863.0  257.06  4884.0  256.23  4894.6  255.17  4915.7  255.26
  4926.2  254.25  4936.8  254.89  4968.4  255.00  4978.9  252.85  4986.5  252.65
  4989.2  252.15  4992.5  252.65  4997.4  253.88  5014.1  254.74  5070.7  256.50
  5113.1  257.15  5226.3  261.58  5325.3  266.40  5410.1  271.54  5424.3  272.84
#Mann=3,-1,0
  4367.5     0.1       0  4986.5    0.07       0  4992.5     0.1       0
Bank Sta=4986.5,4992.5
Exp/Cntr=0.3,0.1

Type RM Length L Ch R = 1,1440,436,436,436
BEGIN DESCRIPTION:
UNT 087 IN LACR 3.0
END DESCRIPTION:
XS GIS Cut Line= 4
      2262047.08     13201583.77      2262385.64     13201583.77
      2262837.72     13201146.85      2262987.72     13200996.85
#Sta/Elev= 30
  4244.9  276.34  4345.5  270.76  4375.5  269.93  4405.5  268.13  4475.5  265.57
  4485.5  264.74  4505.5  264.42  4555.5  261.94  4653.5  258.91  4667.7  259.02
  4681.8  257.80  4731.2  257.05  4766.7  255.50  4908.0  252.48  4943.5  250.89
  4971.8  250.34  4978.7  249.07  4985.9  249.26  4989.9  248.13  4992.6  247.63
  4995.9  248.13  5007.0  249.52  5035.3  250.31  5059.6  250.09  5141.5  251.49
  5171.5  252.52  5282.9  256.13  5311.2  257.85  5339.4  258.48  5424.3  262.87
#Mann=5,-1,0
  4244.9     0.1       0  4989.9    0.07       0  4995.9     0.1       0
  5059.6    0.12       0  5171.5     0.1       0
Bank Sta=4989.9,4995.9
Exp/Cntr=0.3,0.1

Type RM Length L Ch R = 1,1004,385,385,385
BEGIN DESCRIPTION:
UNT 087 IN LACR 2.0
END DESCRIPTION:
XS GIS Cut Line= 3
      2262387.74     13202146.83      2262987.72     13201546.85
      2263187.75     13201246.82
#Sta/Elev= 30
  4151.5  274.04  4179.8  272.20  4278.8  268.49  4292.9  267.29  4335.3  265.25
  4349.5  265.19  4363.6  264.18  4448.5  260.65  4476.7  260.07  4490.9  259.01
  4575.7  256.04  4886.9  246.83  4915.1  246.96  4943.4  245.95  4968.1  246.17
  4971.7  246.21  4982.9  243.12  4985.6  242.62  4988.9  243.12  4996.5  245.81
  5076.7  247.94  5166.8  249.82  5180.3  250.73  5252.4  252.46  5259.9  253.20
  5296.0  253.01  5317.0  254.68  5347.0  255.73  5353.0  255.53  5360.6  256.29
#Mann=5,-1,0
  4151.5     0.1       0  4968.1    0.12       0  4982.9    0.07       0
  4988.9    0.12       0  5076.7     0.1       0
Bank Sta=4982.9,4988.9
Exp/Cntr=0.3,0.1

Type RM Length L Ch R = 1,619,496,496,496
BEGIN DESCRIPTION:
Mapping XS 88dc5108
END DESCRIPTION:
XS GIS Cut Line= 4
      2262593.96     13202273.88      2263114.81     13201961.37
      2263271.06     13201570.74      2263297.11     13201284.25
#Sta/Elev= 30
  4215.4  266.10  4243.9  265.62  4333.3  261.37  4339.1  261.91  4354.6  260.88
  4360.5  261.34  4391.6  259.43  4406.4  259.43  4471.3  256.51  4639.6  250.81
  4652.0  251.18  4704.5  248.94  4720.1  249.22  4768.6  247.02  4821.1  245.79
  4946.1  243.76  4975.9  242.37  4989.2  240.15  5002.5  239.19  5005.3  238.69
  5008.5  239.19  5021.5  239.27  5035.1  241.75  5053.9  243.20  5089.0  243.05
  5196.7  245.22  5248.0  246.71  5297.6  249.16  5372.6  250.35  5531.2  255.32
#Mann=3,-1,0
  4215.4     0.1       0  5002.5    0.07       0  5008.5     0.1       0
Bank Sta=5002.5,5008.5
Exp/Cntr=0.3,0.1

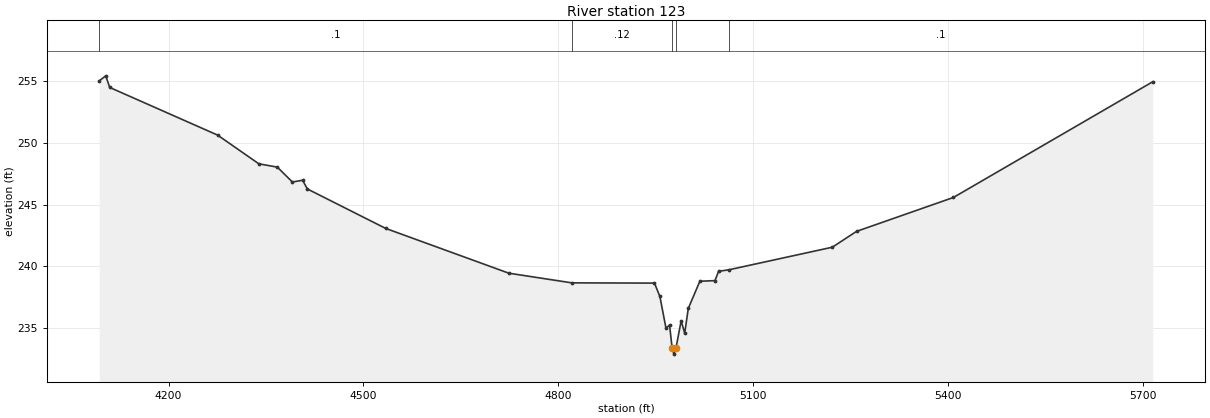
Type RM Length L Ch R = 1,123,0,0,0
BEGIN DESCRIPTION:
UNT 087 IN LACR 1.0
END DESCRIPTION:
XS GIS Cut Line= 4
      2262872.97     13202335.75      2263584.82     13202010.21
      2263684.65     13201784.51      2263411.23     13201259.37
#Sta/Elev= 30
  4093.3  254.99  4103.3  255.40  4109.5  254.46  4275.5  250.61  4339.0  248.29
  4367.5  248.02  4390.6  246.82  4406.4  246.96  4413.6  246.26  4534.2  243.07
  4723.8  239.45  4820.7  238.67  4947.9  238.65  4956.3  237.57  4965.7  235.00
  4971.2  235.26  4975.1  233.41  4977.9  232.91  4981.1  233.41  4989.0  235.60
  4994.5  234.60  5000.0  236.60  5017.8  238.80  5041.1  238.85  5046.6  239.60
  5062.9  239.73  5221.7  241.55  5259.0  242.83  5408.1  245.57  5714.9  254.92
#Mann=5,-1,0
  4093.3     0.1       0  4820.7    0.12       0  4975.1    0.07       0
  4981.1    0.12       0  5062.9     0.1       0
Bank Sta=4975.1,4981.1
Exp/Cntr=0.3,0.1

Chan Stop Cuts=-1