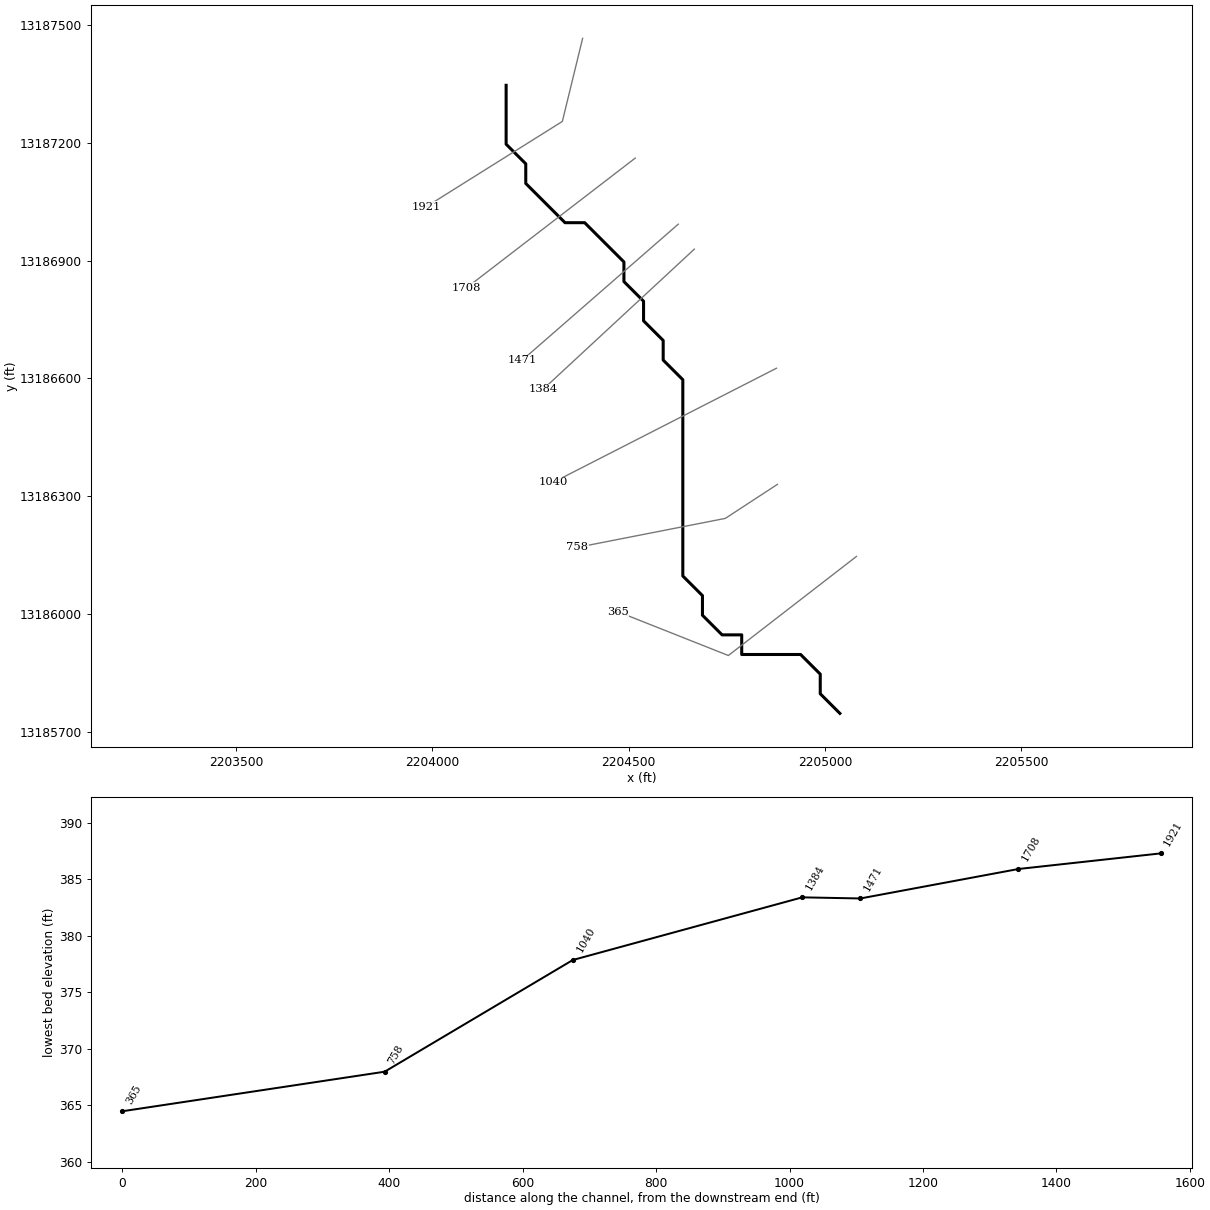
--- UNT 088 IN LACR.prj (project) ---

Proj Title=UNT 088 IN LACR Base Level Engineering
Current Plan=p01
Default Exp/Contr=0.3,0.1
English Units
Geom File=g01
Flow File=f01
Plan File=p01
BEGIN DESCRIPTION:
UNT 088 IN LACR
END DESCRIPTION:

--- UNT 088 IN LACR.p01 (plan) ---

Plan Title=Multiple Run
Short Identifier=Multiple
Geom File=g01
Flow File=f01
Subcritical Flow
K Sum by GR= 0
Std Step Tol= 0.01
Critical Tol= 0.01
Num of Std Step Trials= 20
Max Error Tol= 0.3
Flow Tol Ratio= 0.001
Split Flow NTrial= 30
Split Flow Tol= 0.02
Split Flow Ratio= 0.02
Log Output Level= 0
Friction Slope Method= 1
Unsteady Friction Slope Method= 2
Unsteady Bridges Friction Slope Method= 1
Parabolic Critical Depth
Global Vel Dist=  1 , 1 , 1
Global Log Level= 0
CheckData=True
Encroach Param= -1, 0, 0, 0
BEGIN DESCRIPTION:
Multiple Run
END DESCRIPTION:

--- UNT 088 IN LACR.f01 (steady flow) ---

Flow Title=Multiple
Number of Profiles=7
Profile Names=10-year,25-year,50-year,1pct_min,100-year,1pct_plu,500-year
River Rch & RM= UNT 088 IN LACR,Reach-1,1921
     160     219     268     242     327     442     493
Boundary for River Rch & Prof#=UNT 088 IN LACR,Reach-1,1
Up Type=0
Dn Type=3
Dn Slope=0.005
Boundary for River Rch & Prof#=UNT 088 IN LACR,Reach-1,2
Up Type=0
Dn Type=3
Dn Slope=0.005
Boundary for River Rch & Prof#=UNT 088 IN LACR,Reach-1,3
Up Type=0
Dn Type=3
Dn Slope=0.005
Boundary for River Rch & Prof#=UNT 088 IN LACR,Reach-1,4
Up Type=0
Dn Type=3
Dn Slope=0.005
Boundary for River Rch & Prof#=UNT 088 IN LACR,Reach-1,5
Up Type=0
Dn Type=3
Dn Slope=0.005
Boundary for River Rch & Prof#=UNT 088 IN LACR,Reach-1,6
Up Type=0
Dn Type=3
Dn Slope=0.005
Boundary for River Rch & Prof#=UNT 088 IN LACR,Reach-1,7
Up Type=0
Dn Type=3
Dn Slope=0.005

--- UNT 088 IN LACR.g01 (geometry) ---

Geom Title=Existing Conditions

River Reach=UNT 088 IN LACR,Reach-1
Reach XY= 25
      2204187.72     13187346.85      2204187.72     13187196.85
      2204237.72     13187146.85      2204237.72     13187096.85
      2204287.72     13187046.86      2204337.72     13186996.85
      2204387.72     13186996.85      2204437.72     13186946.85
      2204487.72     13186896.86      2204487.72     13186846.85
      2204537.72     13186796.85      2204537.72     13186746.86
      2204587.72     13186696.85      2204587.72     13186646.85
      2204637.72     13186596.85      2204637.72     13186096.86
      2204687.72     13186046.85      2204687.72     13185996.85
      2204737.72     13185946.85      2204787.72     13185946.85
      2204787.72     13185896.85      2204937.72     13185896.85
      2204987.72     13185846.85      2204987.72     13185796.85
      2205037.72     13185746.86

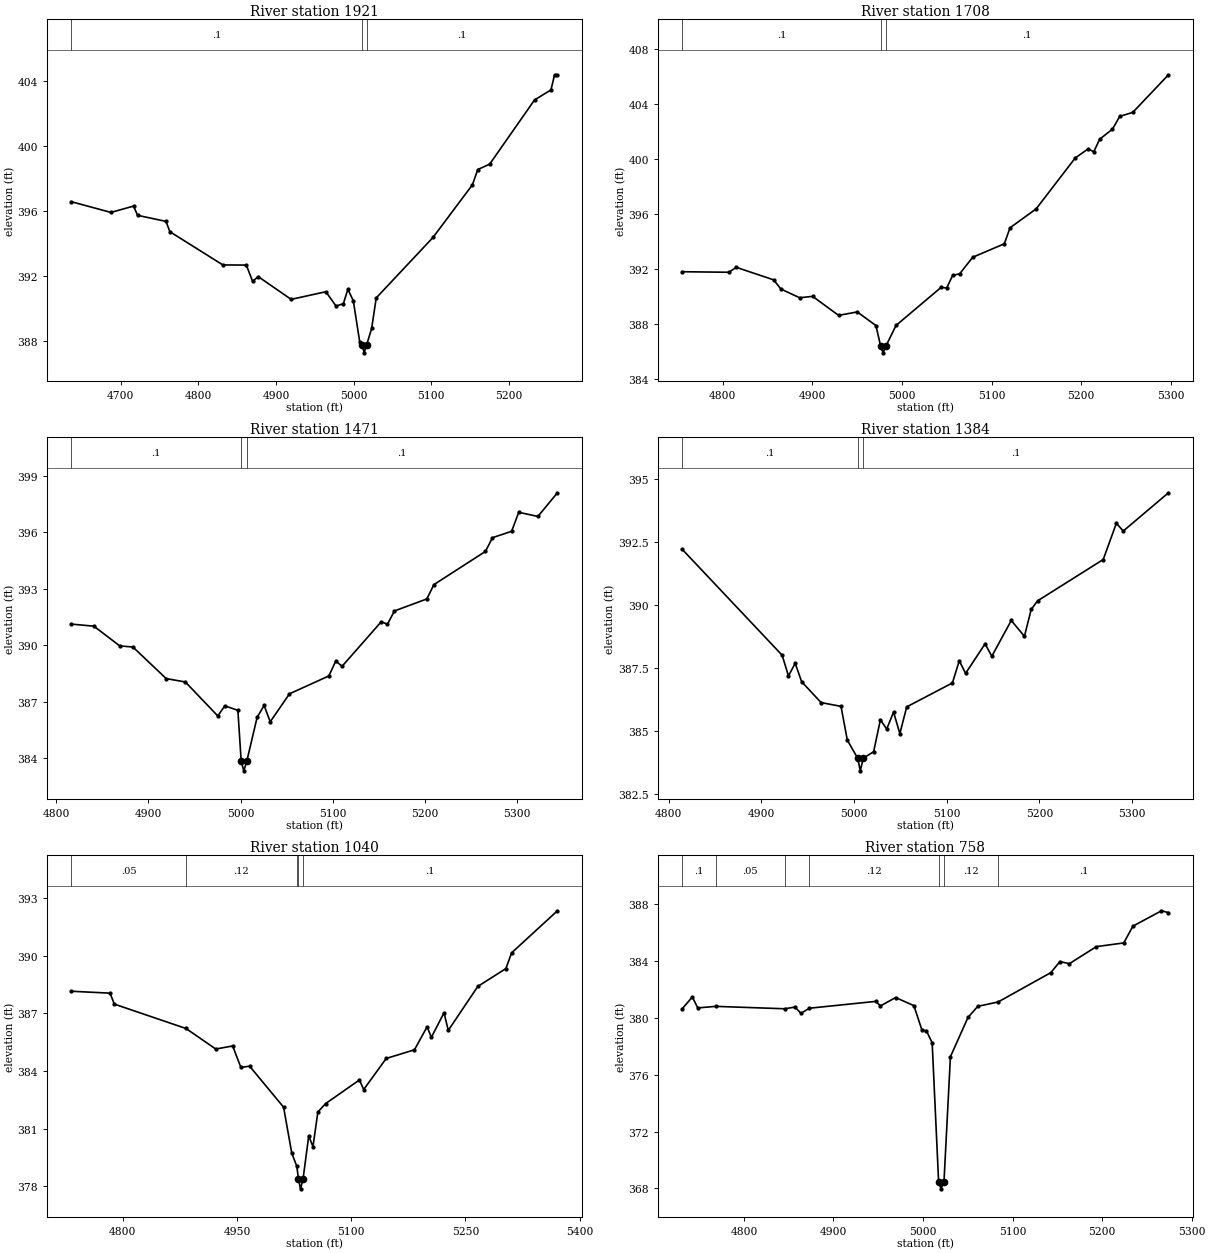
Type RM Length L Ch R = 1,1921,213,213,213
BEGIN DESCRIPTION:
UNT 088 IN LACR 2.0
END DESCRIPTION:
XS GIS Cut Line= 3
      2204382.55     13187466.47      2204330.92     13187254.79
      2203984.96     13187037.92
#Sta/Elev= 30
  4636.2  396.60  4687.3  395.94  4716.4  396.33  4721.6  395.76  4758.1  395.39
  4763.3  394.75  4831.4  392.71  4861.7  392.70  4869.7  391.70  4877.0  391.99
  4919.4  390.59  4964.1  391.06  4977.2  390.18  4986.6  390.32  4992.5  391.21
  4999.5  390.50  5007.8  387.95  5010.7  387.80  5013.5  387.30  5016.7  387.80
  5023.1  388.80  5029.0  390.68  5102.1  394.40  5152.9  397.64  5159.8  398.58
  5175.1  398.91  5232.9  402.86  5254.1  403.48  5258.7  404.41  5262.4  404.41
#Mann=3,-1,0
  4636.2     0.1       0  5010.7    0.07       0  5016.7     0.1       0
Bank Sta=5010.7,5016.7
Exp/Cntr=0.3,0.1

Type RM Length L Ch R = 1,1708,237,237,237
BEGIN DESCRIPTION:
Mapping XS d7d0b83a
END DESCRIPTION:
XS GIS Cut Line= 2
      2204516.58     13187161.42      2204086.90     13186830.90
#Sta/Elev= 30
  4755.1  391.81  4807.0  391.77  4815.2  392.13  4856.9  391.22  4865.1  390.55
  4885.9  389.92  4900.4  390.02  4929.4  388.64  4950.2  388.89  4971.0  387.90
  4976.2  386.42  4979.0  385.92  4982.2  386.42  4993.4  387.91  5043.6  390.67
  5049.9  390.63  5056.5  391.54  5064.4  391.66  5078.9  392.86  5114.2  393.84
  5120.5  395.00  5149.6  396.37  5193.1  400.06  5207.6  400.73  5213.9  400.52
  5220.5  401.43  5234.7  402.16  5242.9  403.09  5257.4  403.38  5297.2  406.11
#Mann=3,-1,0
  4755.1     0.1       0  4976.2    0.07       0  4982.2     0.1       0
Bank Sta=4976.2,4982.2
Exp/Cntr=0.3,0.1

Type RM Length L Ch R = 1,1471,87,87,87
BEGIN DESCRIPTION:
Mapping XS 565fb564
END DESCRIPTION:
XS GIS Cut Line= 2
      2204626.19     13186993.13      2204228.50     13186646.43
#Sta/Elev= 30
  4816.3  391.12  4840.8  391.01  4868.9  389.96  4883.2  389.90  4919.3  388.22
  4940.1  388.04  4975.3  386.23  4982.9  386.77  4997.1  386.53  5000.7  383.81
  5003.5  383.31  5006.7  383.81  5018.0  386.16  5025.6  386.79  5032.2  385.92
  5053.1  387.41  5095.8  388.36  5103.4  389.16  5110.1  388.87  5152.8  391.25
  5159.4  391.11  5167.0  391.82  5202.2  392.46  5209.8  393.22  5265.8  394.99
  5273.4  395.72  5294.2  396.06  5301.9  397.07  5322.7  396.85  5343.9  398.11
#Mann=3,-1,0
  4816.3     0.1       0  5000.7    0.07       0  5006.7     0.1       0
Bank Sta=5000.7,5006.7
Exp/Cntr=0.3,0.1

Type RM Length L Ch R = 1,1384,344,344,344
BEGIN DESCRIPTION:
Mapping XS 8a16a5ca
END DESCRIPTION:
XS GIS Cut Line= 2
      2204667.02     13186929.43      2204282.39     13186572.82
#Sta/Elev= 30
  4814.7  392.20  4922.4  388.00  4929.2  387.18  4936.5  387.68  4943.4  386.95
  4964.4  386.12  4985.9  385.97  4992.7  384.63  5003.9  383.91  5006.7  383.41
  5009.9  383.91  5021.1  384.17  5028.4  385.44  5035.2  385.07  5042.6  385.74
  5049.4  384.89  5056.8  385.95  5106.1  386.90  5113.5  387.78  5120.3  387.28
  5141.3  388.45  5148.6  387.96  5169.6  389.38  5183.8  388.75  5191.1  389.82
  5198.0  390.16  5268.8  391.80  5283.0  393.24  5290.4  392.93  5339.2  394.45
#Mann=3,-1,0
  4814.7     0.1       0  5003.9    0.07       0  5009.9     0.1       0
Bank Sta=5003.9,5009.9
Exp/Cntr=0.3,0.1

Type RM Length L Ch R = 1,1040,282,282,282
BEGIN DESCRIPTION:
Mapping XS a4b33d40
END DESCRIPTION:
XS GIS Cut Line= 2
      2204876.08     13186626.02      2204307.47     13186335.34
#Sta/Elev= 30
  4732.3  388.15  4783.2  388.05  4788.8  387.48  4883.0  386.21  4922.1  385.14
  4944.3  385.30  4955.1  384.18  4966.5  384.25  5011.2  382.11  5021.9  379.72
  5028.6  379.03  5030.7  378.36  5033.4  377.86  5036.7  378.36  5044.2  380.61
  5049.8  380.06  5056.2  381.86  5066.4  382.30  5110.8  383.53  5116.4  383.03
  5146.0  384.65  5183.1  385.10  5199.7  386.30  5205.3  385.75  5221.9  387.03
  5227.5  386.11  5266.3  388.40  5303.2  389.33  5310.7  390.15  5370.9  392.34
#Mann=5,-1,0
  4732.3    0.05       0  4883.0    0.12       0  5028.6     0.1       0
  5030.7    0.07       0  5036.7     0.1       0
Bank Sta=5030.7,5036.7
Exp/Cntr=0.3,0.1

Type RM Length L Ch R = 1,758,393,393,393
BEGIN DESCRIPTION:
Mapping XS ed4d9fda
END DESCRIPTION:
XS GIS Cut Line= 3
      2204878.63     13186330.28      2204746.02     13186243.57
      2204368.74     13186169.64
#Sta/Elev= 30
  4731.2  380.64  4742.4  381.46  4748.4  380.69  4768.4  380.80  4845.6  380.63
  4857.0  380.75  4863.7  380.31  4873.1  380.67  4947.3  381.15  4952.4  380.83
  4969.4  381.42  4989.8  380.85  4998.7  379.15  5003.8  379.08  5010.2  378.24
  5017.4  368.47  5020.1  367.97  5023.4  368.47  5030.6  377.26  5050.2  380.02
  5061.1  380.80  5083.9  381.11  5142.7  383.17  5152.9  383.95  5163.4  383.80
  5193.6  385.00  5224.2  385.26  5234.4  386.44  5266.3  387.52  5274.1  387.39
#Mann=7,-1,0
  4731.2     0.1       0  4768.4    0.05       0  4845.6     0.1       0
  4873.1    0.12       0  5017.4    0.07       0  5023.4    0.12       0
  5083.9     0.1       0
Bank Sta=5017.4,5023.4
Exp/Cntr=0.3,0.1

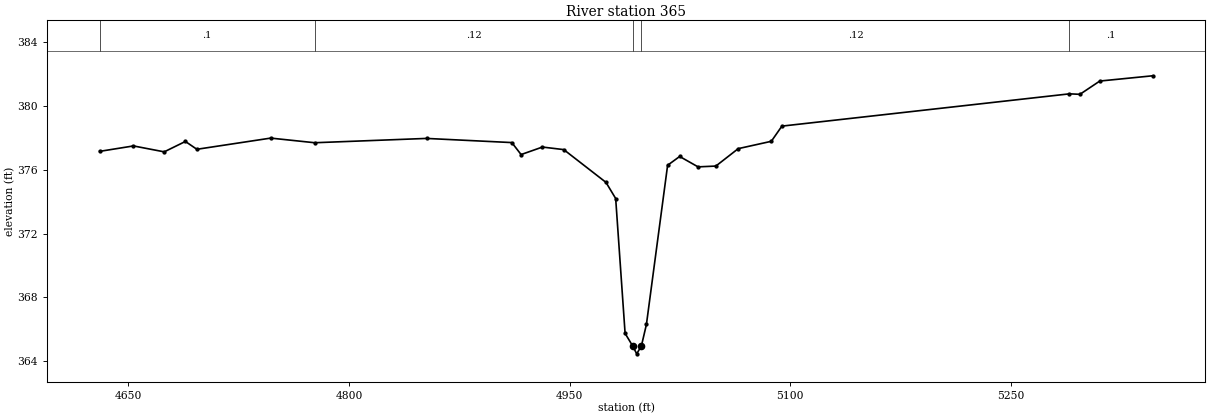
Type RM Length L Ch R = 1,365,0,0,0
BEGIN DESCRIPTION:
UNT 088 IN LACR 1.0
END DESCRIPTION:
XS GIS Cut Line= 3
      2205080.00     13186146.68      2204753.67     13185894.28
      2204471.67     13186006.07
#Sta/Elev= 30
  4630.5  377.14  4653.5  377.48  4674.4  377.11  4688.8  377.76  4696.6  377.27
  4746.8  377.97  4776.7  377.68  4852.7  377.95  4910.7  377.69  4917.0  376.94
  4931.5  377.41  4946.0  377.25  4974.7  375.20  4981.3  374.19  4987.7  365.75
  4992.8  364.97  4995.6  364.47  4998.8  364.97  5002.2  366.31  5016.6  376.27
  5024.8  376.82  5037.3  376.17  5049.4  376.22  5064.6  377.31  5087.1  377.77
  5094.3  378.72  5289.8  380.74  5296.9  380.71  5310.4  381.54  5346.4  381.87
#Mann=5,-1,0
  4630.5     0.1       0  4776.7    0.12       0  4992.8    0.07       0
  4998.8    0.12       0  5289.8     0.1       0
Bank Sta=4992.8,4998.8
Exp/Cntr=0.3,0.1

Chan Stop Cuts=-1