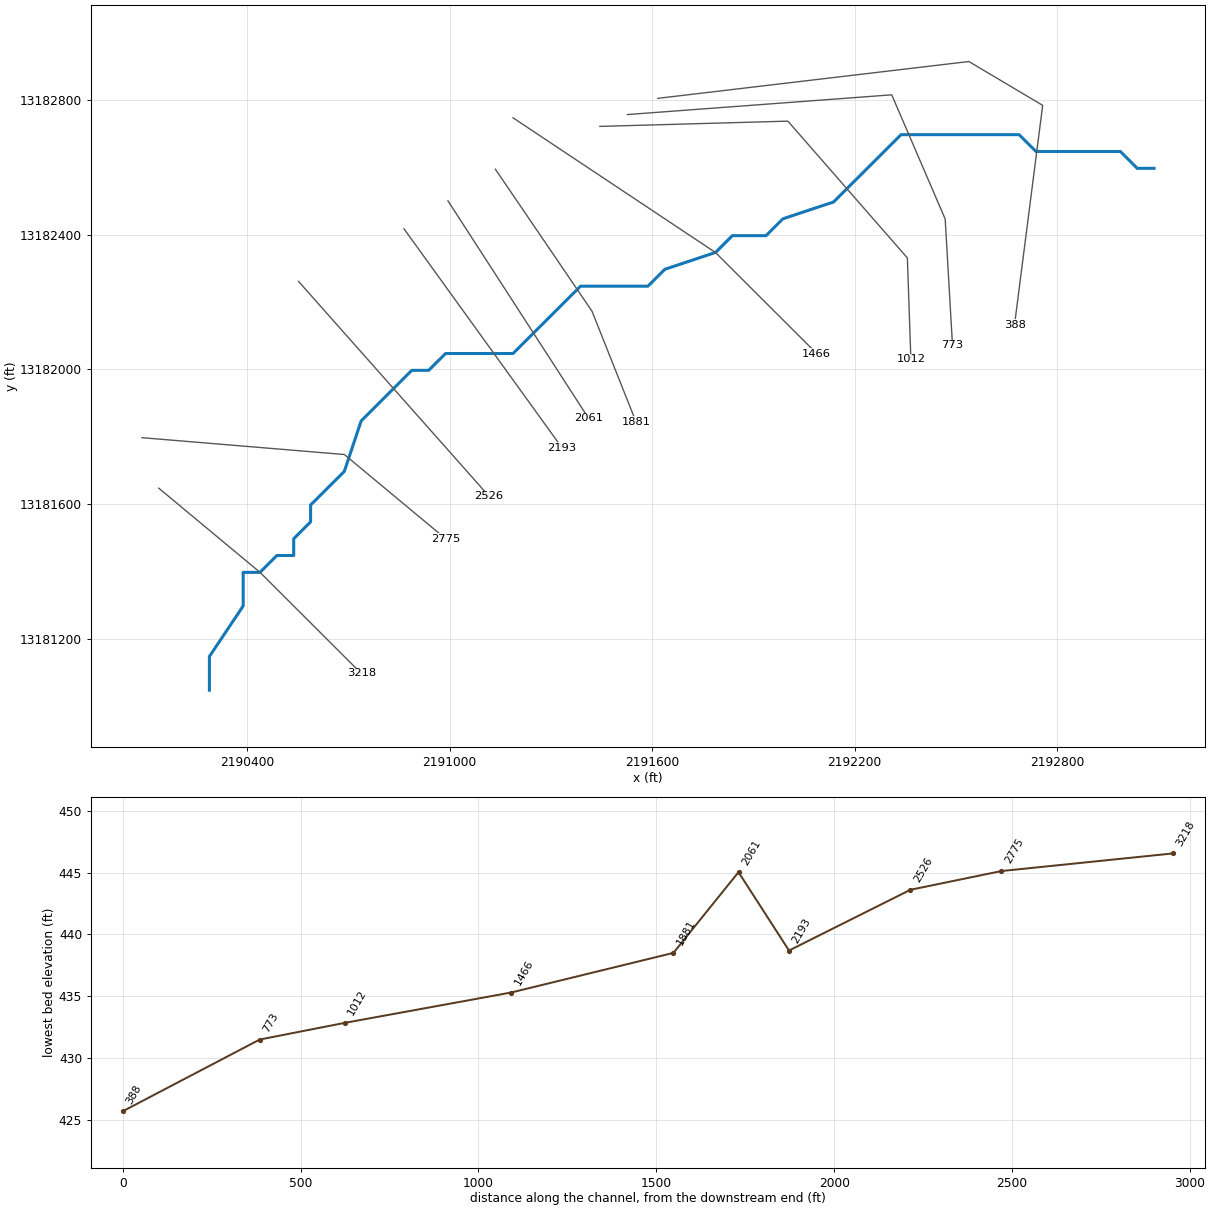
--- UNT 089 IN LACR.prj (project) ---

Proj Title=UNT 089 IN LACR Base Level Engineering
Current Plan=p01
Default Exp/Contr=0.3,0.1
English Units
Geom File=g01
Flow File=f01
Plan File=p01
Y Axis Title=Elevation
X Axis Title(PF)=Main Channel Distance
X Axis Title(XS)=Station
BEGIN DESCRIPTION:
UNT 089 IN LACR
END DESCRIPTION:
DSS Export Rating Curves= 0
DSS Export Rating Curve Sorted= 0
DSS Export Volume Flow Curves= 0
DXF OffsetX= 0
DXF OffsetY= 0
DXF ScaleX= 1
DXF ScaleY= 10

--- UNT 089 IN LACR.p01 (plan) ---

Plan Title=Multiple Run
Short Identifier=Multiple
Geom File=g01
Flow File=f01
Subcritical Flow
K Sum by GR= 0
Std Step Tol= 0.01
Critical Tol= 0.01
Num of Std Step Trials= 20
Max Error Tol= 0.3
Flow Tol Ratio= 0.001
Split Flow NTrial= 30
Split Flow Tol= 0.02
Split Flow Ratio= 0.02
Log Output Level= 0
Friction Slope Method= 1
Unsteady Friction Slope Method= 2
Unsteady Bridges Friction Slope Method= 1
Parabolic Critical Depth
Global Vel Dist=  1 , 1 , 1
Global Log Level= 0
CheckData=True
Encroach Param= -1, 0, 0, 0
BEGIN DESCRIPTION:
Multiple Run
END DESCRIPTION:

--- UNT 089 IN LACR.f01 (steady flow) ---

Flow Title=Multiple
Program Version=4.10
Number of Profiles= 7
Profile Names=10-year,25-year,50-year,1pct_min,100-year,1pct_plu,500-year
River Rch & RM=UNT 089 IN LACR,Reach-1         ,3218
     156     214     261     235     318     430     477
Boundary for River Rch & Prof#=UNT 089 IN LACR,Reach-1         , 1
Up Type= 0
Dn Type= 3
Dn Slope=0.005
Boundary for River Rch & Prof#=UNT 089 IN LACR,Reach-1         , 2
Up Type= 0
Dn Type= 3
Dn Slope=0.005
Boundary for River Rch & Prof#=UNT 089 IN LACR,Reach-1         , 3
Up Type= 0
Dn Type= 3
Dn Slope=0.005
Boundary for River Rch & Prof#=UNT 089 IN LACR,Reach-1         , 4
Up Type= 0
Dn Type= 3
Dn Slope=0.005
Boundary for River Rch & Prof#=UNT 089 IN LACR,Reach-1         , 5
Up Type= 0
Dn Type= 3
Dn Slope=0.005
Boundary for River Rch & Prof#=UNT 089 IN LACR,Reach-1         , 6
Up Type= 0
Dn Type= 3
Dn Slope=0.005
Boundary for River Rch & Prof#=UNT 089 IN LACR,Reach-1         , 7
Up Type= 0
Dn Type= 3
Dn Slope=0.005
DSS Import GetInterval= 0
DSS Import GetPeak= 0
DSS Import FillOption= 0

--- UNT 089 IN LACR.g01 (geometry) ---

Geom Title=Existing Conditions
Program Version=4.10

River Reach=UNT 089 IN LACR ,Reach-1
Reach XY= 30
      2190287.72     13181046.85      2190287.72     13181146.86
      2190387.72     13181296.85      2190387.72     13181396.85
      2190437.72     13181396.85      2190487.72     13181446.85
      2190537.72     13181446.85      2190537.72     13181496.86
      2190587.72     13181546.85      2190587.72     13181596.85
      2190687.72     13181696.85      2190737.72     13181846.85
      2190887.72     13181996.86      2190937.72     13181996.86
      2190987.72     13182046.85      2191187.72     13182046.85
      2191387.72     13182246.85      2191587.72     13182246.85
      2191637.72     13182296.86      2191787.72     13182346.85
      2191837.72     13182396.85      2191937.72     13182396.85
      2191987.72     13182446.85      2192137.72     13182496.85
      2192337.72     13182696.85      2192687.72     13182696.85
      2192737.72     13182646.86      2192987.72     13182646.86
      2193037.72     13182596.85      2193087.72     13182596.85

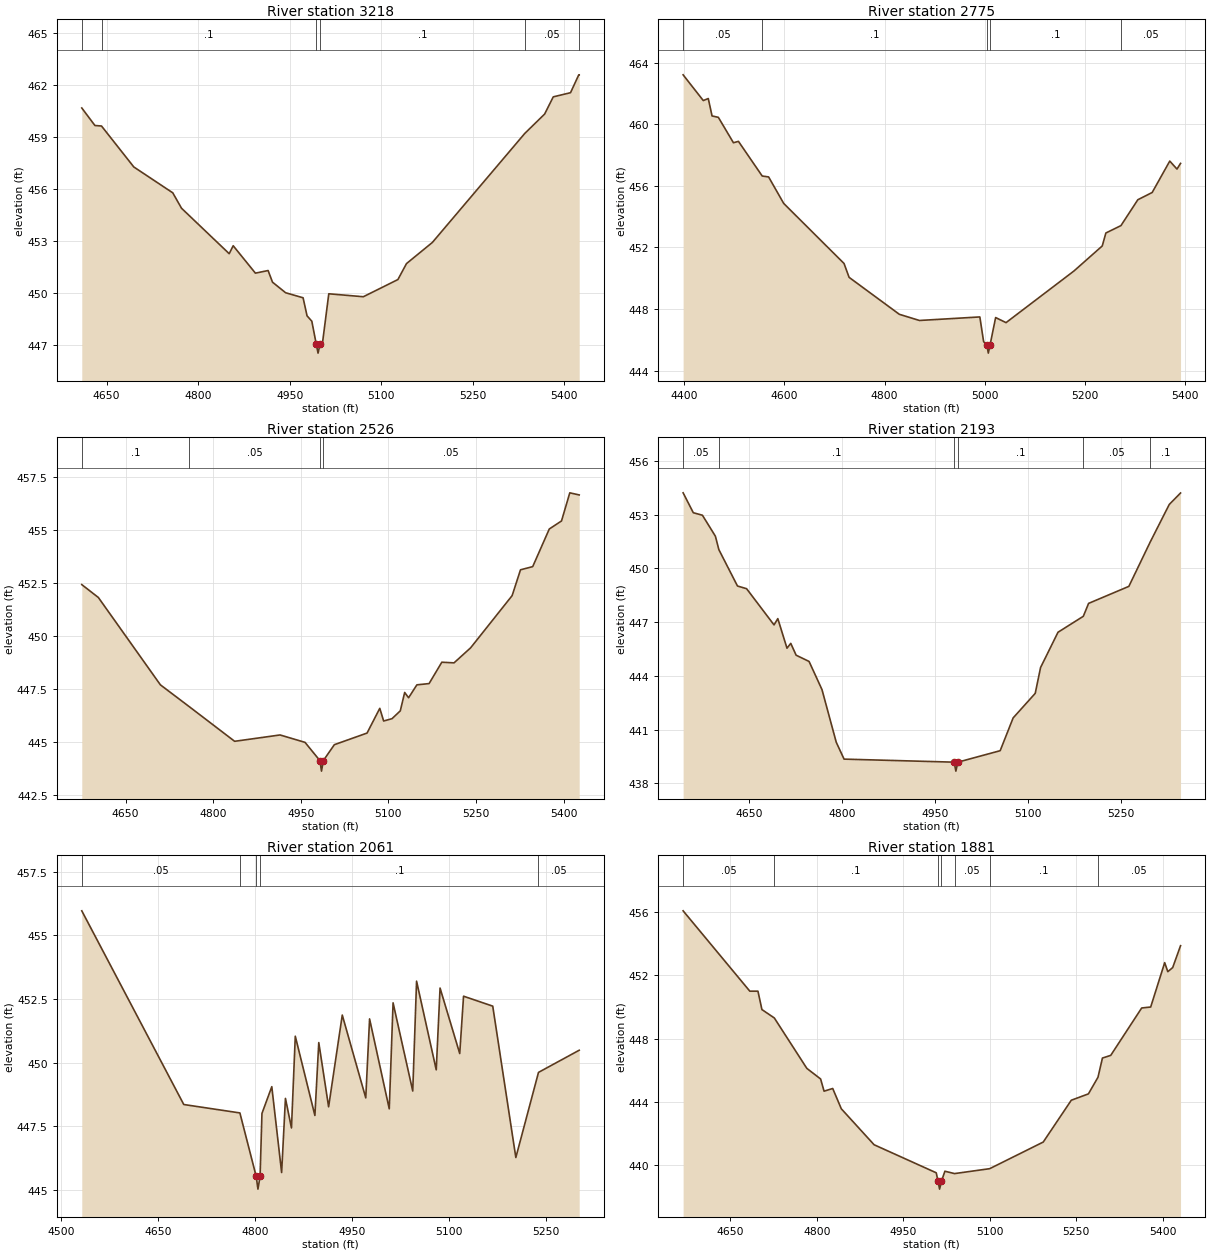
Type RM Length L Ch R = 1 ,3218    ,483,483,483
BEGIN DESCRIPTION:
UNT 089 IN LACR 6.0
END DESCRIPTION:
XS GIS Cut Line= 3
      2190137.73     13181646.85      2190437.72     13181396.85
      2190737.75     13181096.83
#Sta/Elev= 30
  4609.5  460.69    4631  459.68  4641.8  459.65  4694.7  457.29  4758.5   455.8
  4772.9  454.91    4851  452.29  4857.5  452.75  4893.9  451.17  4914.7  451.32
  4921.9  450.65  4943.4  450.04    4972  449.75  4978.5  448.71  4986.3   448.4
  4993.7  447.06  4996.5  446.56  4999.7  447.06  5003.5  447.06  5014.1  449.98
  5070.7  449.81  5127.3   450.8  5141.4  451.72  5183.8  452.94  5335.1  459.22
  5367.7  460.34  5381.8  461.33  5410.1  461.57  5423.6   462.6  5424.3   462.6
#Mann= 6 ,-1 , 0
  4609.5     .05       0  4641.8      .1       0  4993.7     .07       0
  4999.7      .1       0  5335.1     .05       0  5423.6      .1       0
Bank Sta=4993.7,4999.7
XS Rating Curve= 0 ,0
Exp/Cntr=0.3,0.1

Type RM Length L Ch R = 1 ,2775    ,256,256,256
BEGIN DESCRIPTION:
UNT 089 IN LACR 5.0
END DESCRIPTION:
XS GIS Cut Line= 3
       2190087.7     13181796.86      2190687.72     13181746.85
      2190987.71     13181496.86
#Sta/Elev= 30
  4397.9   463.2  4438.1  461.53  4448.1  461.66  4455.6  460.53  4468.2  460.44
  4498.3  458.79  4508.3  458.88  4555.7  456.63  4568.5  456.57  4598.6  454.85
    4719  450.95  4729.1  450.05  4829.4  447.65  4869.5  447.25    4990  447.48
  4997.5  445.88  5004.2  445.63  5006.9  445.13  5010.2  445.63  5021.5  447.44
  5042.3  447.11  5177.7  450.46  5234.3  452.09  5241.5  452.93  5271.6  453.41
  5305.3  455.09  5333.9  455.56    5369   457.6  5383.4  457.08  5390.5  457.45
#Mann= 5 ,-1 , 0
  4397.9     .05       0  4555.7      .1       0  5004.2     .07       0
  5010.2      .1       0  5271.6     .05       0
Bank Sta=5004.2,5010.2
XS Rating Curve= 0 ,0
Exp/Cntr=0.3,0.1

Type RM Length L Ch R = 1 ,2526    ,341,341,341
BEGIN DESCRIPTION:
UNT 089 IN LACR 4.0
END DESCRIPTION:
XS GIS Cut Line= 2
      2190552.02     13182260.94      2191116.35     13181623.16
#Sta/Elev= 30
  4575.1  452.43  4603.5  451.82  4709.7  447.69  4759.5  446.65  4836.8  445.02
  4914.6  445.32  4957.3  444.97  4982.7  444.11  4985.5  443.61  4988.7  444.11
  5007.5  444.86  5063.5  445.41  5085.3  446.58  5091.9  445.98  5106.2  446.09
  5120.4  446.46  5127.9  447.33  5134.6  447.08  5148.8  447.69  5169.7  447.75
  5191.5  448.76  5212.4  448.73  5240.8  449.44  5311.9  451.91  5326.2  453.13
  5347.1  453.28  5375.5  455.06  5396.4  455.44  5410.6  456.77  5426.7  456.67
#Mann= 4 ,-1 , 0
  4575.1      .1       0  4759.5     .05       0  4982.7     .03       0
  4988.7     .05       0
Bank Sta=4982.7,4988.7
XS Rating Curve= 0 ,0
Exp/Cntr=0.3,0.1

Type RM Length L Ch R = 1 ,2193    ,142,142,142
BEGIN DESCRIPTION:
Mapping XS beb232a5
END DESCRIPTION:
XS GIS Cut Line= 2
      2190864.55     13182417.16      2191332.99     13181766.55
#Sta/Elev= 30
  4543.7  454.22  4560.1  453.11  4574.8  452.97  4595.7   451.8  4601.3  451.05
  4631.3  449.02    4646  448.87  4690.2  446.85  4696.3   447.2  4711.1  445.55
  4717.2  445.82  4725.8  445.16  4746.7  444.81  4767.5  443.24  4790.5   440.3
  4803.1  439.36  4980.5  439.19  4983.3  438.69  4986.5  439.19  5054.7  439.83
  5075.6  441.66  5111.2  443.03  5119.8  444.47  5147.9  446.44  5188.7  447.33
  5197.2  448.05  5262.1     449  5296.3  451.46  5327.2  453.57  5345.4  454.21
#Mann= 6 ,-1 , 0
  4543.7     .05       0  4601.3      .1       0  4980.5     .07       0
  4986.5      .1       0  5188.7     .05       0  5296.3      .1       0
Bank Sta=4980.5,4986.5
XS Rating Curve= 0 ,0
Exp/Cntr=0.3,0.1

Type RM Length L Ch R = 1 ,2061    ,183,183,183
BEGIN DESCRIPTION:
Mapping XS 9ae351f1
END DESCRIPTION:
XS GIS Cut Line= 2
      2190994.78     13182500.47      2191411.45     13181854.62
#Sta/Elev= 30
  4532.3  455.96  4689.9  448.36  4776.6  448.03  4801.8  445.54  4804.5  445.04
  4807.8  445.54  4810.7  448.01  4825.9  449.06  4841.1  445.69    4847   448.6
  4856.3  447.44  4862.2  451.04  4892.5  447.93  4898.5  450.79  4913.7  448.27
  4934.8  451.87  4971.1  448.62    4977  451.72  5007.4  448.19  5013.3  452.35
  5043.7  448.89  5049.6   453.2    5080  449.72  5085.9  452.93  5116.3  450.36
  5122.2  452.61  5167.3  452.22    5203  446.28    5238  449.62  5300.9  450.49
#Mann= 5 ,-1 , 0
  4532.3     .05       0  4776.6      .1       0  4801.8     .07       0
  4807.8      .1       0    5238     .05       0
Bank Sta=4801.8,4807.8
XS Rating Curve= 0 ,0
Exp/Cntr=0.3,0.1

Type RM Length L Ch R = 1 ,1881    ,456,456,456
BEGIN DESCRIPTION:
UNT 089 IN LACR 3.0
END DESCRIPTION:
XS GIS Cut Line= 3
      2191135.41      13182594.2      2191421.84     13182172.37
      2191552.05     13181844.25
#Sta/Elev= 30
  4568.3  456.06    4684  450.99  4698.1  450.99    4705  449.83  4726.5   449.3
  4782.9  446.12  4806.8  445.45  4812.8  444.68  4827.8  444.85  4842.7  443.57
  4899.6   441.3  5007.4  439.53  5010.5     439  5013.2   438.5  5016.5     439
  5022.4  439.63  5039.1  439.48  5100.1  439.79    5193  441.47  5241.7  444.11
  5271.4  444.51    5288  445.56  5295.7  446.77  5310.1  446.94  5363.8  449.93
  5379.4  449.99  5403.7  452.79  5409.1  452.22  5417.6  452.48  5431.2  453.86
#Mann= 7 ,-1 , 0
  4568.3     .05       0  4726.5      .1       0  5010.5     .07       0
  5016.5      .1       0  5039.1     .05       0  5100.1      .1       0
    5288     .05       0
Bank Sta=5010.5,5016.5
XS Rating Curve= 0 ,0
Exp/Cntr=0.3,0.1

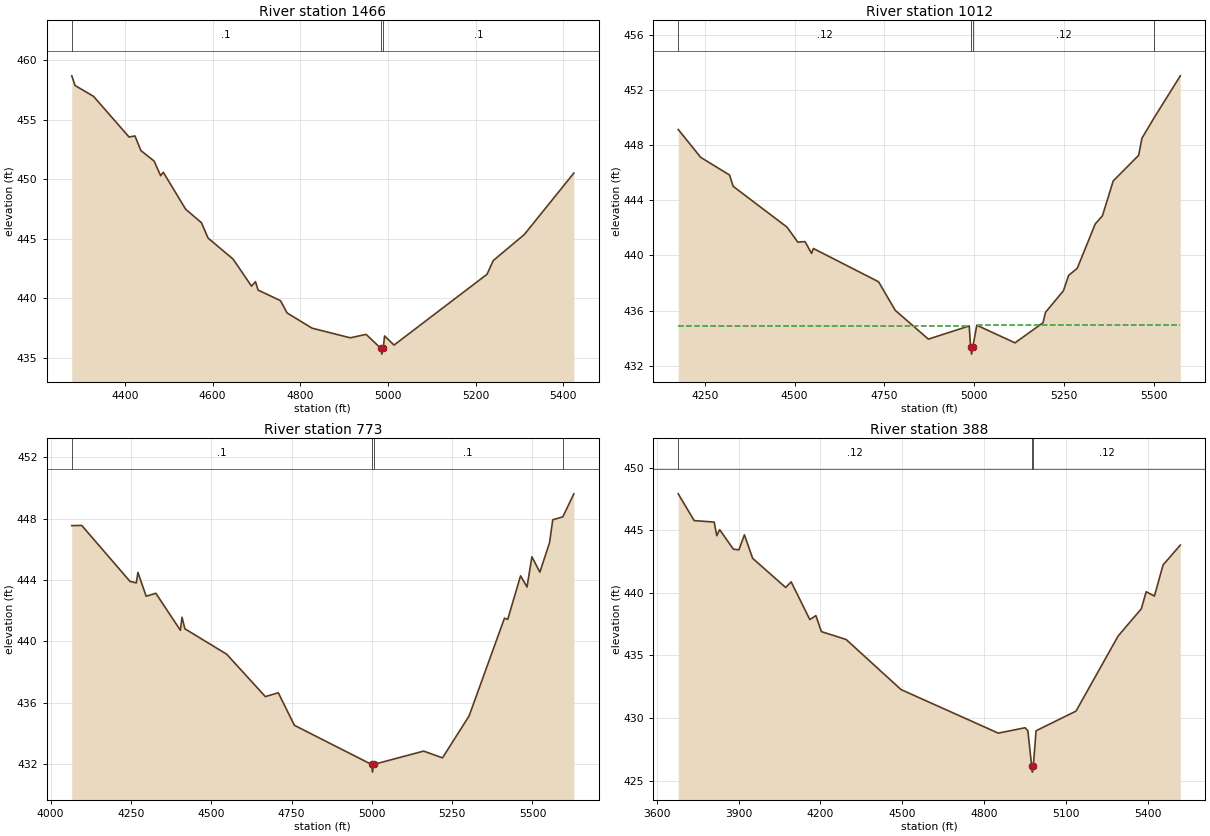
Type RM Length L Ch R = 1 ,1466    ,468,468,468
BEGIN DESCRIPTION:
UNT 089 IN LACR 2.0
END DESCRIPTION:
XS GIS Cut Line= 3
      2191187.73     13182746.85      2191787.72     13182346.85
      2192087.75     13182046.83
#Sta/Elev= 30
  4278.9  458.67  4286.4  457.86  4328.5  456.95  4409.6  453.53  4423.1  453.62
  4436.6  452.39  4466.7  451.51  4481.7  450.28  4487.7  450.57  4538.8  447.46
  4574.8  446.33  4589.9  445.04    4647  443.27    4689     441    4698  441.38
    4704  440.67  4755.1  439.78  4770.1  438.75  4827.2  437.47  4914.4  436.66
  4950.4  436.95  4983.5  435.79  4986.2  435.29  4989.5  435.79  4992.5  436.82
  5014.1  436.05  5226.3     442  5240.4  443.15  5311.1  445.33  5424.3   450.5
#Mann= 3 ,-1 , 0
  4278.9      .1       0  4983.5     .07       0  4989.5      .1       0
Bank Sta=4983.5,4989.5
XS Rating Curve= 0 ,0
Exp/Cntr=0.3,0.1

Type RM Length L Ch R = 1 ,1012    ,239,239,239
BEGIN DESCRIPTION:
Mapping XS 9638e983
END DESCRIPTION:
XS GIS Cut Line= 4
      2191445.01     13182721.36      2192002.34     13182736.99
      2192356.51     13182330.74      2192366.87     13182030.22
#Sta/Elev= 30
  4176.3  449.16    4239  447.13  4319.1  445.85  4329.1  445.03  4479.1  442.06
  4509.1  440.97  4529.1  441.01  4547.4  440.15  4552.4  440.51  4733.8  438.09
  4780.3  436.01  4872.4  433.92  4986.1  434.88  4989.9  433.33  4992.7  432.83
  4995.9  433.33  5007.2  434.93  5113.5  433.65  5191.3  435.11  5198.4  435.87
  5248.3  437.44  5262.6  438.55  5286.7  439.07  5336.7  442.29  5356.7  442.88
  5386.8  445.42  5457.5  447.28  5466.8  448.53  5500.4     450  5573.5  453.06
#Mann= 4 ,-1 , 0
  4176.3     .12       0  4989.9     .07       0  4995.9     .12       0
  5500.4     .05       0
#XS Ineff= 2 , 0
         4986.12  434.88 5007.45          434.94
Permanent Ineff=
       F       F
Bank Sta=4989.9,4995.9
XS Rating Curve= 0 ,0
Exp/Cntr=0.3,0.1

Type RM Length L Ch R = 1 ,773     ,385,385,385
BEGIN DESCRIPTION:
Mapping XS c4fc2351
END DESCRIPTION:
XS GIS Cut Line= 4
      2191526.74     13182756.55      2192310.16     13182815.14
      2192468.58     13182446.22      2192490.25     13182071.35
#Sta/Elev= 30
  4066.1  447.54  4097.2  447.55  4247.6   443.9    4267  443.81    4272  444.49
  4297.7  442.94  4327.8  443.13  4404.2  440.72  4409.2  441.57  4418.1  440.82
  4548.4  439.16  4668.6   436.4  4708.9  436.65    4759  434.53  4999.2  431.98
    5002  431.48  5005.2  431.98  5161.2  432.85  5219.9  432.41  5302.7  435.14
  5412.8  441.51  5422.9  441.43  5462.9  444.27    5483  443.54  5498.1  445.51
    5523  444.51  5553.1  446.43  5563.1  447.92  5594.4  448.11  5628.7  449.61
#Mann= 4 ,-1 , 0
  4066.1      .1       0  4999.2     .07       0  5005.2      .1       0
  5594.4     .05       0
Bank Sta=4999.2,5005.2
XS Rating Curve= 0 ,0
Exp/Cntr=0.3,0.1

Type RM Length L Ch R = 1 ,388     ,0,0,0
BEGIN DESCRIPTION:
UNT 089 IN LACR 1.0
END DESCRIPTION:
XS GIS Cut Line= 4
      2191616.96      13182804.7       2192538.8     13182914.07
      2192757.55     13182783.86      2192674.22     13182132.85
#Sta/Elev= 30
    3679  447.93  3737.4  445.79  3810.7  445.67  3820.1  444.58  3830.8  445.06
  3881.2   443.5  3901.3  443.45  3921.4  444.65  3951.7  442.77  4072.5  440.44
  4092.6  440.89  4161.1  437.87  4183.3  438.19  4203.4  436.91    4294  436.28
  4495.4  432.27  4851.3  428.79  4949.6  429.22  4959.7  428.98  4973.7  426.17
  4976.5  425.67  4979.7  426.17  4989.9  428.98  5136.1  430.55  5290.5  436.56
  5375.3  438.73  5393.2   440.1  5423.4  439.75    5455  442.24  5518.2  443.83
#Mann= 3 ,-1 , 0
    3679     .12       0  4973.7     .07       0  4979.7     .12       0
Bank Sta=4973.7,4979.7
XS Rating Curve= 0 ,0
Exp/Cntr=0.3,0.1
Stream Node=UNT 089 IN LACR ,Reach-1         , 0 , 0 ,Upstream end
Stream Node=UNT 089 IN LACR ,Reach-1         , 0 , 1 ,Downstream end

Chan Stop Cuts=-1
Use User Specified Reach Order=0
Composite Channel Slope=5