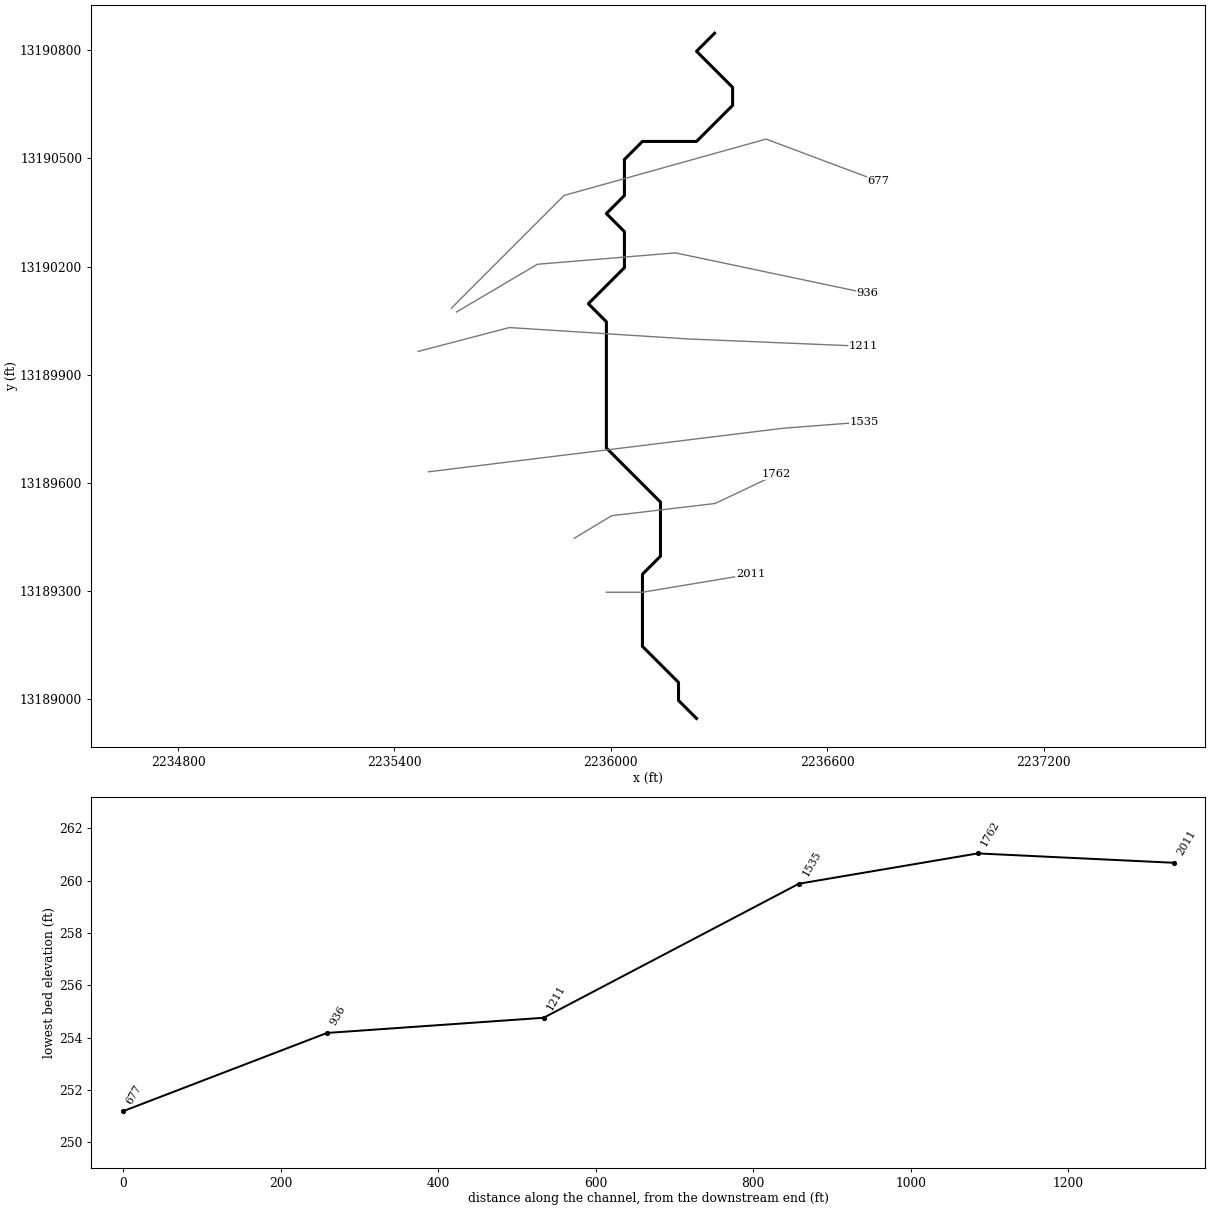
--- UNT 090 IN LACR.prj (project) ---

Proj Title=UNT 090 IN LACR Base Level Engineering
Current Plan=p01
Default Exp/Contr=0.3,0.1
English Units
Geom File=g01
Flow File=f01
Plan File=p01
Y Axis Title=Elevation
X Axis Title(PF)=Main Channel Distance
X Axis Title(XS)=Station
BEGIN DESCRIPTION:
UNT 090 IN LACR
END DESCRIPTION:
DSS Export Rating Curves= 0
DSS Export Rating Curve Sorted= 0
DSS Export Volume Flow Curves= 0
DXF OffsetX= 0
DXF OffsetY= 0
DXF ScaleX= 1
DXF ScaleY= 10

--- UNT 090 IN LACR.p01 (plan) ---

Plan Title=Multiple Run
Short Identifier=Multiple
Geom File=g01
Flow File=f01
Subcritical Flow
K Sum by GR= 0
Std Step Tol= 0.01
Critical Tol= 0.01
Num of Std Step Trials= 20
Max Error Tol= 0.3
Flow Tol Ratio= 0.001
Split Flow NTrial= 30
Split Flow Tol= 0.02
Split Flow Ratio= 0.02
Log Output Level= 0
Friction Slope Method= 1
Unsteady Friction Slope Method= 2
Unsteady Bridges Friction Slope Method= 1
Parabolic Critical Depth
Global Vel Dist=  1 , 1 , 1
Global Log Level= 0
CheckData=True
Encroach Param= -1, 0, 0, 0
BEGIN DESCRIPTION:
Multiple Run
END DESCRIPTION:

--- UNT 090 IN LACR.f01 (steady flow) ---

Flow Title=Multiple
Program Version=4.10
Number of Profiles= 7
Profile Names=10-year,25-year,50-year,1pct_min,100-year,1pct_plu,500-year
River Rch & RM=UNT 090 IN LACR,Reach-1         ,2011
     124     166     200     177     240     324     351
River Rch & RM=UNT 090 IN LACR,Reach-1         ,1535
     172     235     287     258     349     472     524
River Rch & RM=UNT 090 IN LACR,Reach-1         ,936
     172     235     287     258     349     472     524
Boundary for River Rch & Prof#=UNT 090 IN LACR,Reach-1         , 1
Up Type= 0
Dn Type= 3
Dn Slope=0.005
Boundary for River Rch & Prof#=UNT 090 IN LACR,Reach-1         , 2
Up Type= 0
Dn Type= 3
Dn Slope=0.005
Boundary for River Rch & Prof#=UNT 090 IN LACR,Reach-1         , 3
Up Type= 0
Dn Type= 3
Dn Slope=0.005
Boundary for River Rch & Prof#=UNT 090 IN LACR,Reach-1         , 4
Up Type= 0
Dn Type= 3
Dn Slope=0.005
Boundary for River Rch & Prof#=UNT 090 IN LACR,Reach-1         , 5
Up Type= 0
Dn Type= 3
Dn Slope=0.005
Boundary for River Rch & Prof#=UNT 090 IN LACR,Reach-1         , 6
Up Type= 0
Dn Type= 3
Dn Slope=0.005
Boundary for River Rch & Prof#=UNT 090 IN LACR,Reach-1         , 7
Up Type= 0
Dn Type= 3
Dn Slope=0.005
DSS Import GetInterval= 0
DSS Import GetPeak= 0
DSS Import FillOption= 0

--- UNT 090 IN LACR.g01 (geometry) ---

Geom Title=Existing Conditions
Program Version=4.10

River Reach=UNT 090 IN LACR ,Reach-1
Reach XY= 25
      2236237.72     13188946.85      2236187.72     13188996.85
      2236187.72     13189046.86      2236137.72     13189096.85
      2236087.72     13189146.85      2236087.72     13189346.86
      2236137.72     13189396.85      2236137.72     13189546.86
      2236087.72     13189596.85      2236037.72     13189646.85
      2235987.72     13189696.86      2235987.72     13190046.85
      2235937.72     13190096.85      2235987.72     13190146.85
      2236037.72     13190196.86      2236037.72     13190296.85
      2235987.72     13190346.86      2236037.72     13190396.85
      2236037.72     13190496.86      2236087.72     13190546.85
      2236237.72     13190546.85      2236337.72     13190646.85
      2236337.72     13190696.85      2236237.72     13190796.85
      2236287.72     13190846.86

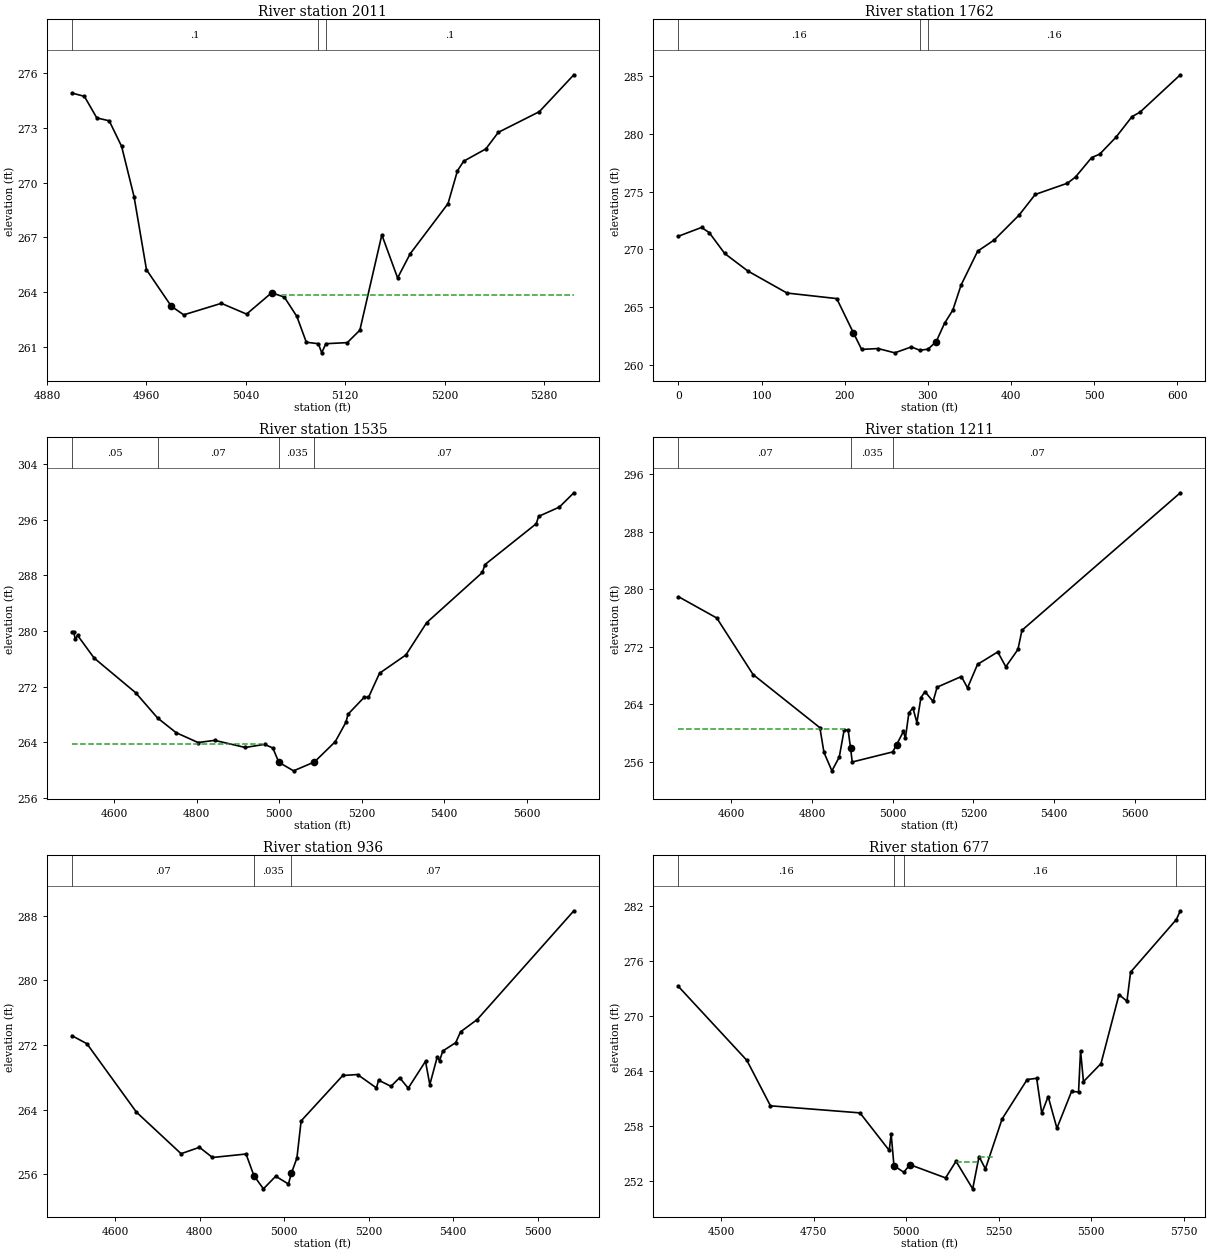
Type RM Length L Ch R = 1 ,2011    ,249,249,249
BEGIN DESCRIPTION:
UNT 090 IN LACR 3.0
END DESCRIPTION:
XS GIS Cut Line= 3
      2235987.72     13189296.85      2236087.72     13189296.85
      2236387.68     13189346.85
#Sta/Elev= 30
    4900   274.9    4910  274.72    4920  273.54    4930  273.38    4940  271.98
    4950  269.23    4960  265.23    4980  263.23    4990  262.76  5020.3  263.39
  5040.6   262.8  5060.8  263.97    5071  263.73  5081.1  262.67  5088.7  261.26
  5098.4  261.18  5101.1  260.68  5104.4  261.18  5121.7  261.24  5131.8  261.92
  5149.5  267.14  5162.2  264.78  5172.3   266.1  5202.8  268.85  5210.4  270.65
  5215.4  271.17  5233.2  271.84  5243.3  272.75  5276.3  273.88  5304.1   275.9
#Mann= 3 ,-1 , 0
    4900      .1       0  5098.4     .07       0  5104.4      .1       0
#XS Ineff= 2 , 0
       0                 5069.08       0  263.85
Permanent Ineff=
       F       T
Bank Sta=4980,5060.8
XS Rating Curve= 0 ,0
Exp/Cntr=0.3,0.1

Type RM Length L Ch R = 1 ,1762    ,227,227,227
BEGIN DESCRIPTION:
Mapping XS b2f0eb87
END DESCRIPTION:
XS GIS Cut Line= 4
     2235898.613    13189446.633      2236002.78    13189509.133
     2236289.238    13189542.987     2236459.811    13189623.717
#Sta/Elev= 30
       0271.1485   27.84271.9102   37.12271.4593   55.68269.6519   83.52268.1339
  130.61266.2225  190.44265.7424  210.38262.7884  220.36261.3367   240.3261.4096
  260.24 261.038  280.19261.5509  290.16261.2669  300.13261.3504   310.1 262.011
  320.07263.5931  330.05  264.74  340.02266.9153  359.96269.8548  379.91270.8261
  409.82272.9857  429.21274.7715  467.99275.7475  477.69276.2871  497.08277.9691
  506.78278.2685  526.17279.7205  545.56281.5162  555.25281.9058  603.73285.1487
#Mann= 3 ,-1 , 0
       0     .16       0  290.16     .07       0  300.13     .16       0
Bank Sta=210.38,310.1
XS Rating Curve= 0 ,0
Exp/Cntr=0.3,0.1

Type RM Length L Ch R = 1 ,1535    ,324,324,324
BEGIN DESCRIPTION:
Mapping XS 33d34c9c
END DESCRIPTION:
XS GIS Cut Line= 3
      2235494.42     13189630.82      2236478.39     13189751.65
      2236702.77     13189768.91
#Sta/Elev= 30
  4498.1  279.81  4502.3  279.81  4506.5  278.78  4511.6  279.37  4551.8   276.1
  4652.5  271.11  4705.8  267.47  4750.5  265.37  4803.7  263.95    4844  264.26
  4918.2  263.24  4964.9  263.69    4985  263.16  4999.5  261.11  5035.2  259.88
  5085.9  261.16  5136.2  264.07  5162.1  266.87  5167.2  268.02  5206.7  270.48
  5216.8  270.44  5243.5  273.91  5307.4  276.54  5357.8  281.19  5492.9  288.41
  5498.8  289.52  5623.3  295.41  5629.2  296.47  5679.3   297.8  5714.5  299.86
#Mann= 4 ,-1 , 0
  4498.1     .05       0  4705.8     .07       0  4999.5    .035       0
  5085.9     .07       0
#XS Ineff= 2 , 0
       0 4963.98   263.7               0
Permanent Ineff=
       T       F
Bank Sta=4999.5,5085.9
XS Rating Curve= 0 ,0
Exp/Cntr=0.3,0.1

Type RM Length L Ch R = 1 ,1211    ,275,275,275
BEGIN DESCRIPTION:
UNT 090 IN LACR 2.0
END DESCRIPTION:
XS GIS Cut Line= 4
      2235465.67     13189964.57      2235718.82     13190030.74
      2236216.57     13189999.09      2236699.94     13189978.95
#Sta/Elev= 30
  4468.9  278.99    4564  276.02  4653.9  268.16  4819.6  260.76  4829.7  257.32
  4849.4  254.76  4867.6  256.67  4879.8  260.47  4889.8  260.38 4895.57  257.93
  4899.8  255.99    5000  257.39    5010  258.41  5026.6  260.24  5031.6  259.31
  5040.1  262.79  5050.1  263.53  5060.1  261.48  5070.1  264.96  5080.2  265.77
  5100.2  264.41  5110.2   266.4  5170.3  267.88  5185.6   266.3  5210.4  269.57
  5260.5   271.3  5280.5  269.24  5310.5  271.64  5320.5  274.31  5713.1  293.44
#Mann= 3 ,-1 , 0
  4468.9     .07       0 4895.57    .035       0    5000     .07       0
#XS Ineff= 2 , 0
       0 4880.45  260.61               0
Permanent Ineff=
       T       F
Bank Sta=4895.57,5010
XS Rating Curve= 0 ,0
Exp/Cntr=0.3,0.1

Type RM Length L Ch R = 1 ,936     ,259,259,259
BEGIN DESCRIPTION:
Mapping XS 6f5b1ede
END DESCRIPTION:
XS GIS Cut Line= 4
      2235572.07     13190073.88      2235796.51     13190206.25
      2236179.17     13190237.89      2236711.44     13190125.69
#Sta/Elev= 30
  4497.4  273.14  4532.9  272.14    4650  263.68  4755.8  258.53  4799.3  259.32
  4830.2  258.06  4909.7  258.49 4928.18  255.82  4950.8  254.18  4979.9  255.74
    5010  254.78 5017.27  256.15  5030.1  257.99  5040.1  262.59  5138.7  268.21
  5173.7  268.33  5218.4  266.67  5223.5  267.63  5252.9  266.87  5273.3  267.94
  5293.7  266.64  5334.6  269.97  5344.8  267.08  5362.6  270.54  5367.8  270.02
  5375.5  271.24  5406.2  272.28  5417.5  273.61  5457.1  275.14  5685.9   288.6
#Mann= 3 , 0 , 0
  4497.4     .07       0 4928.18    .035       0 5017.27     .07       0
Bank Sta=4928.18,5017.27
XS Rating Curve= 0 ,0
Exp/Cntr=0.3,0.1

Type RM Length L Ch R = 1 ,677     ,0,0,0
BEGIN DESCRIPTION:
UNT 090 IN LACR 1.0
END DESCRIPTION:
XS GIS Cut Line= 4
      2235558.14     13190084.64      2235870.63     13190397.13
      2236430.53     13190553.38      2236742.87     13190436.25
#Sta/Elev= 30
  4384.6   273.2  4569.7  265.16  4633.4  260.22  4875.4  259.45  4954.5  255.37
  4959.7  257.15 4967.27  253.71  4993.9  252.99  5010.4  253.82  5106.8  252.38
    5135  254.19  5180.1  251.19  5197.3   254.7  5214.5  253.36  5259.6  258.79
  5327.4  263.08    5353  263.21  5366.8  259.42  5384.1  261.23  5407.8  257.78
  5447.5  261.79  5466.3  261.72  5471.7  266.21  5479.6  262.85  5526.9  264.81
  5575.7  272.31  5597.1   271.6    5607  274.76  5730.7  280.48  5741.4  281.43
#Mann= 4 ,-1 , 0
  4384.6     .16       0 4967.27     .07       0  4993.9     .16       0
  5730.7     .05       0
#XS Ineff= 2 ,-1
 5135.08  5193.1   254.1 5197.09 5234.25  254.69
Permanent Ineff=
       T       T
Bank Sta=4967.27,5010.4
XS Rating Curve= 0 ,0
Exp/Cntr=0.3,0.1

Chan Stop Cuts=-1
Use User Specified Reach Order=0
Composite Channel Slope=5