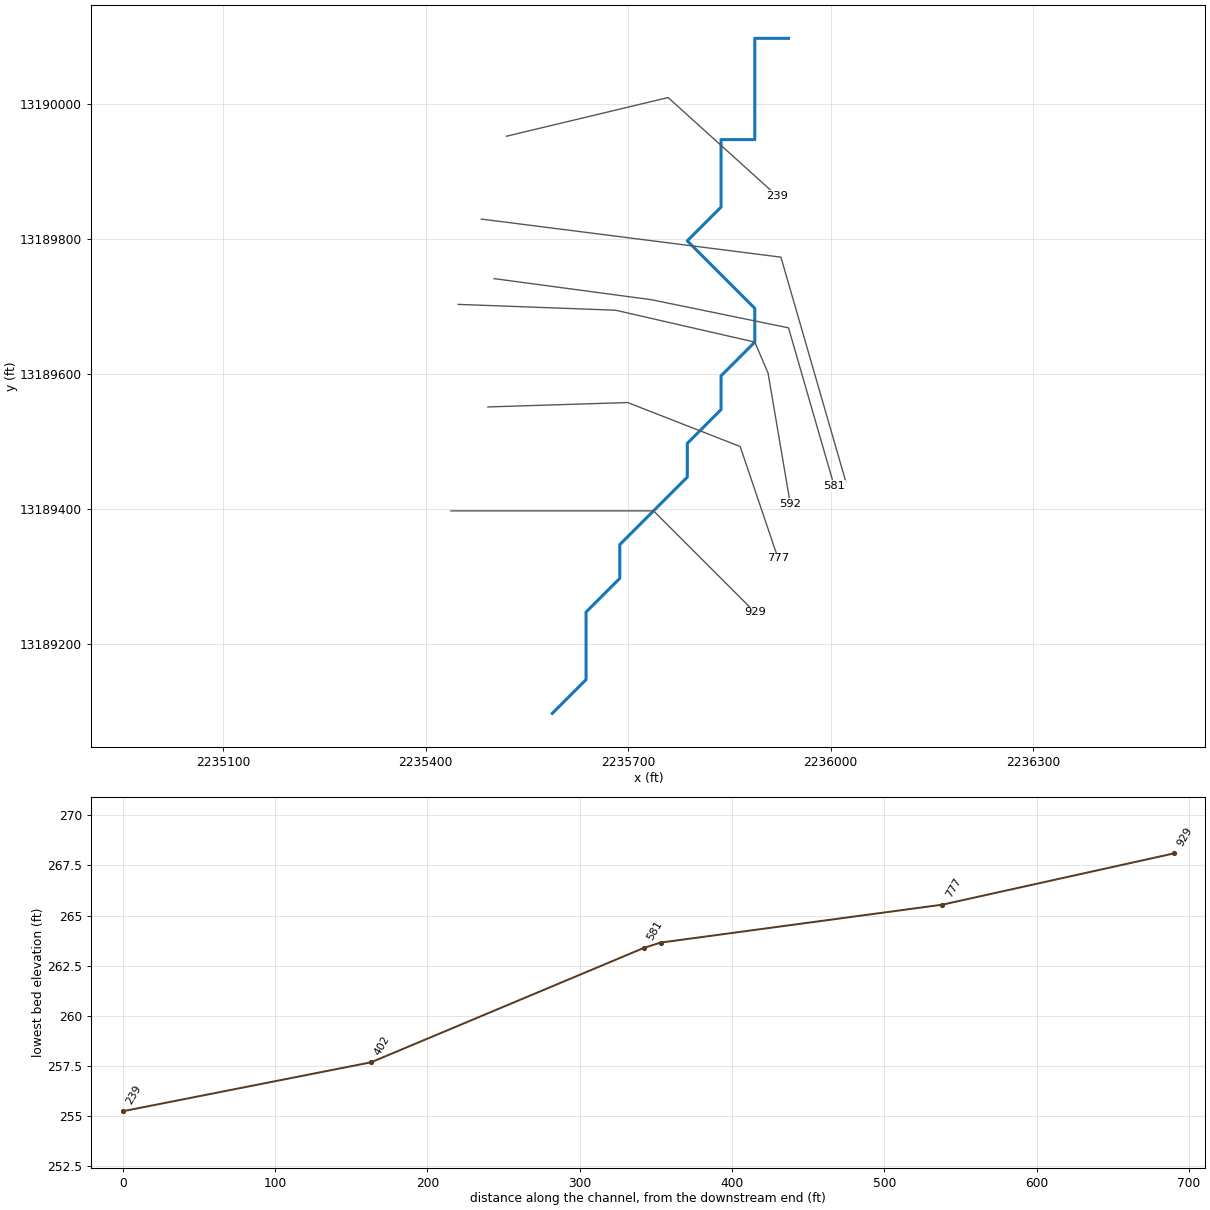
--- UNT 091 IN LACR.prj (project) ---

Proj Title=UNT 091 IN LACR Base Level Engineering
Current Plan=p01
Default Exp/Contr=0.3,0.1
English Units
Geom File=g01
Flow File=f01
Plan File=p01
Y Axis Title=Elevation
X Axis Title(PF)=Main Channel Distance
X Axis Title(XS)=Station
BEGIN DESCRIPTION:
UNT 091 IN LACR
END DESCRIPTION:
DSS Export Rating Curves= 0
DSS Export Rating Curve Sorted= 0
DSS Export Volume Flow Curves= 0
DXF OffsetX= 0
DXF OffsetY= 0
DXF ScaleX= 1
DXF ScaleY= 10

--- UNT 091 IN LACR.p01 (plan) ---

Plan Title=Multiple Run
Short Identifier=Multiple
Geom File=g01
Flow File=f01
Subcritical Flow
K Sum by GR= 0
Std Step Tol= 0.01
Critical Tol= 0.01
Num of Std Step Trials= 20
Max Error Tol= 0.3
Flow Tol Ratio= 0.001
Split Flow NTrial= 30
Split Flow Tol= 0.02
Split Flow Ratio= 0.02
Log Output Level= 0
Friction Slope Method= 1
Unsteady Friction Slope Method= 2
Unsteady Bridges Friction Slope Method= 1
Parabolic Critical Depth
Global Vel Dist=  1 , 1 , 1
Global Log Level= 0
CheckData=True
Encroach Param= -1, 0, 0, 0
BEGIN DESCRIPTION:
Multiple Run
END DESCRIPTION:

--- UNT 091 IN LACR.f01 (steady flow) ---

Flow Title=Multiple
Program Version=4.10
Number of Profiles= 7
Profile Names=10-year,25-year,50-year,1pct_min,100-year,1pct_plu,500-year
River Rch & RM=UNT 091 IN LACR,Reach-1         ,929
      70      90     105      92     124     167     173
Boundary for River Rch & Prof#=UNT 091 IN LACR,Reach-1         , 1
Up Type= 0
Dn Type= 3
Dn Slope=0.02
Boundary for River Rch & Prof#=UNT 091 IN LACR,Reach-1         , 2
Up Type= 0
Dn Type= 3
Dn Slope=0.02
Boundary for River Rch & Prof#=UNT 091 IN LACR,Reach-1         , 3
Up Type= 0
Dn Type= 3
Dn Slope=0.02
Boundary for River Rch & Prof#=UNT 091 IN LACR,Reach-1         , 4
Up Type= 0
Dn Type= 3
Dn Slope=0.02
Boundary for River Rch & Prof#=UNT 091 IN LACR,Reach-1         , 5
Up Type= 0
Dn Type= 3
Dn Slope=0.02
Boundary for River Rch & Prof#=UNT 091 IN LACR,Reach-1         , 6
Up Type= 0
Dn Type= 3
Dn Slope=0.02
Boundary for River Rch & Prof#=UNT 091 IN LACR,Reach-1         , 7
Up Type= 0
Dn Type= 3
Dn Slope=0.02
DSS Import GetInterval= 0
DSS Import GetPeak= 0
DSS Import FillOption= 0

--- UNT 091 IN LACR.g01 (geometry) ---

Geom Title=Existing Conditions
Program Version=4.10

River Reach=UNT 091 IN LACR ,Reach-1
Reach XY= 23
      2235587.72     13189096.85      2235637.72     13189146.85
      2235637.72     13189196.86      2235637.72     13189246.85
      2235687.72     13189296.85      2235687.72     13189346.86
      2235737.72     13189396.85      2235787.72     13189446.85
      2235787.72     13189496.85      2235837.72     13189546.86
      2235837.72     13189596.85      2235887.72     13189646.85
      2235887.72     13189696.86      2235837.72     13189746.85
      2235787.72     13189796.85      2235837.72     13189846.86
      2235837.72     13189896.85      2235837.72     13189946.85
      2235887.72     13189946.85      2235887.72     13189996.85
      2235887.72     13190046.85      2235887.72     13190096.85
      2235937.72     13190096.85

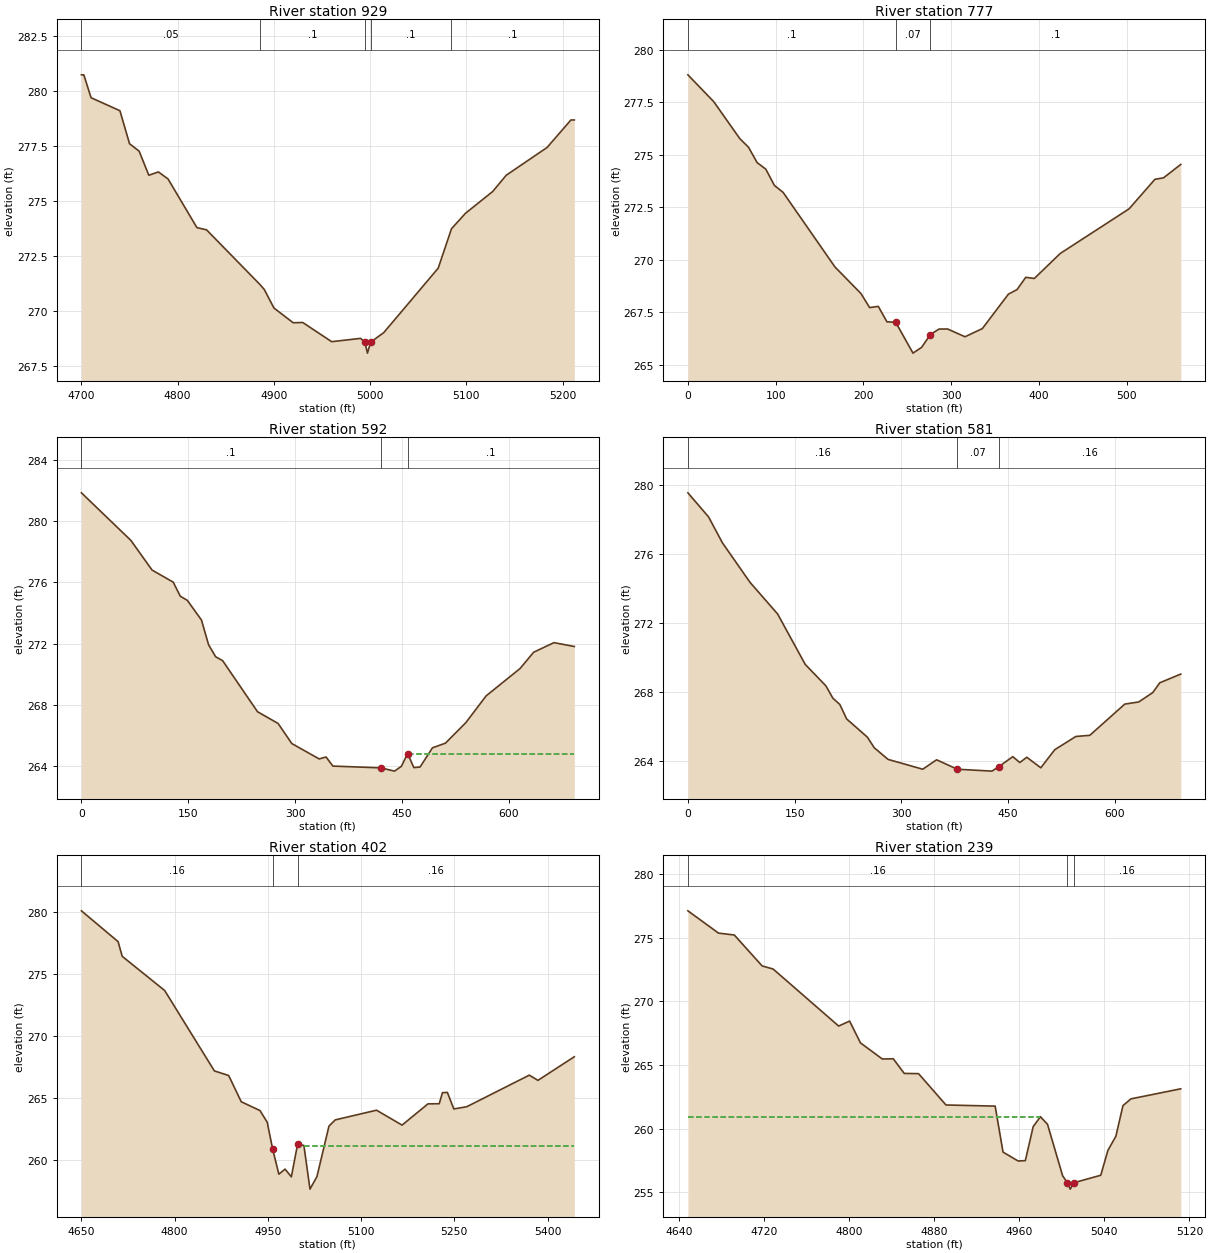
Type RM Length L Ch R = 1 ,929     ,152,152,152
BEGIN DESCRIPTION:
UNT 091 IN LACR 1.0
END DESCRIPTION:
XS GIS Cut Line= 3
      2235437.72     13189396.85      2235737.72     13189396.85
       2235887.7     13189246.88
#Sta/Elev= 30
    4700  280.74  4702.5  280.74    4710   279.7    4740  279.11    4750  277.61
    4760  277.27    4770  276.18    4780  276.33    4790  276.01    4820   273.8
    4830   273.7  4885.4  271.22    4890  270.99    4900  270.15    4920  269.48
    4930  269.49    4960  268.62    4990  268.77  4994.5   268.6  4997.2   268.1
  5000.5   268.6  5014.1  269.03  5070.7  271.96  5084.5  273.75    5099  274.45
  5127.3  275.44  5141.4  276.18  5183.8  277.44  5208.6  278.69  5212.1  278.69
#Mann= 5 ,-1 , 0
    4700     .05       0  4885.4      .1       0  4994.5     .07       0
  5000.5      .1       0  5084.5      .1       0
Bank Sta=4994.5,5000.5
XS Rating Curve= 0 ,0
Exp/Cntr=0.3,0.1

Type RM Length L Ch R = 1 ,777     ,185,185,185
BEGIN DESCRIPTION:
Mapping XS c83826bf
END DESCRIPTION:
XS GIS Cut Line= 4
     2235492.363      13189550.8     2235699.394     13189557.31
     2235866.061    13189492.206     2235922.051    13189326.842
#Sta/Elev= 30
       0278.8167   29.58277.5304   59.16275.7737   69.02275.3662   78.88274.6309
   88.74274.3198    98.6273.5408  108.46273.2123  167.63269.6518  197.21268.3859
  207.07267.7172  216.95 267.775  226.83267.0374  236.72267.0216  256.48265.5453
  266.37265.8229  276.25266.4313  286.13266.6929  296.02266.6949  315.78266.3253
  335.55266.7164   365.2268.3579  375.08268.5758  384.96269.1597  394.78269.1062
  424.22270.2955  502.73272.4267  532.17273.8344  541.98273.9047  561.61274.5444
#Mann= 3 , 0 , 0
       0      .1       0  236.72     .07       0  276.25      .1       0
Bank Sta=236.72,276.25
XS Rating Curve= 0 ,0
Exp/Cntr=0.3,0.1

Type RM Length L Ch R = 1 ,592     ,11,11,11
BEGIN DESCRIPTION:
Mapping XS 91f857bd
END DESCRIPTION:
XS GIS Cut Line= 5
      2235448.41     13189702.74      2235681.42     13189694.11
     2235887.721    13189646.855     2235907.338    13189601.186
      2235940.28    13189407.571
#Sta/Elev= 30
       0281.8566   69.36278.7465   99.09276.8053  128.81276.0127  138.72 275.094
  148.63274.8219  168.45273.5348  178.36271.9258  188.26271.1377  198.17270.8767
  247.12267.5378  275.96266.7709  295.18265.4576  333.63264.4513  343.24264.5781
  352.85263.9839  420.13263.8683  439.35263.6542  448.96263.9712  457.68 264.805
   466.4 263.886  475.11263.9216  492.54265.1792  510.77265.4834  539.32266.8216
  567.87 268.577  615.44270.3642  634.47271.4295  663.02272.0574  691.56271.8066
#Mann= 3 , 0 , 0
       0      .1       0  420.13     .07       0  457.68      .1       0
#XS Ineff= 2 , 0
                          457.77           264.8
Permanent Ineff=
       F       F
Bank Sta=420.13,457.68
XS Rating Curve= 0 ,0
Exp/Cntr=0.3,0.1

Type RM Length L Ch R = 1 ,581     ,179,179,179
BEGIN DESCRIPTION:
Mapping XS 1d2f4dc4
END DESCRIPTION:
XS GIS Cut Line= 4
     2235501.478    13189740.904     2235734.551    13189709.654
     2235937.676    13189667.987     2236005.384    13189433.612
#Sta/Elev= 30
       0279.572229.10944278.168448.51573276.666687.32832274.3666126.1409272.5265
164.9535269.5941194.0629268.3433203.7661267.6322213.4692267.2706223.1724266.4233
252.2818265.3641262.0126264.7454281.4743264.0693330.1285263.4997349.5902264.0473
378.7827263.4989427.4369263.3887437.1678263.6516456.7363264.2306 466.574263.8892
476.4117264.1958 496.087263.5833515.7624264.6363545.2755265.4029564.9509265.4704
614.1393267.2867633.8146267.4123  653.49267.9571663.3277268.5255692.8408 269.033
#Mann= 3 , 0 , 0
       0     .16       0378.7827     .07       0437.1678     .16       0
Bank Sta=378.7827,437.1678
XS Rating Curve= 0 ,0
Exp/Cntr=0.3,0.1

Type RM Length L Ch R = 1 ,402     ,163,163,163
BEGIN DESCRIPTION:
Mapping XS 582b2f42
END DESCRIPTION:
XS GIS Cut Line= 3
      2235482.69     13189829.11      2235926.44     13189772.69
      2236022.37     13189440.69
#Sta/Elev= 30
  4650.1  280.08  4709.1   277.6  4715.7  276.42    4784  273.67    4864   267.2
    4887  266.83  4907.2  264.72  4937.4  264.01    4949  263.07  4957.6  260.94
  4967.7  258.89  4977.7   259.3  4987.8  258.68  4997.9  261.32    5008   261.2
  5017.8  257.69    5029   258.7  5048.3  262.76  5058.4  263.26  5124.8  264.04
  5165.9  262.84  5207.6  264.55  5225.7  264.56  5230.9  265.45  5238.8  265.47
  5249.2  264.14    5270  264.32  5370.6  266.86  5384.5  266.44    5443  268.34
#Mann= 3 , 0 , 0
  4650.1     .16       0  4957.6     .07       0  4997.9     .16       0
#XS Ineff= 2 , 0
       0                 5008.05       0  261.19
Permanent Ineff=
       F       T
Bank Sta=4957.6,4997.9
XS Rating Curve= 0 ,0
Exp/Cntr=0.3,0.1

Type RM Length L Ch R = 1 ,239     ,0,0,0
BEGIN DESCRIPTION:
UNT 091 IN LACR 2.0
END DESCRIPTION:
XS GIS Cut Line= 3
      2235519.73     13189951.82      2235759.31     13190009.11
      2235920.76     13189863.28
#Sta/Elev= 30
    4648  277.11  4676.8  275.36  4691.7  275.21  4717.9  272.78  4728.2  272.54
  4789.9  268.06  4800.2  268.45  4810.4  266.74    4831  265.47  4841.3  265.49
  4851.6  264.34  4865.1  264.32  4890.9  261.86  4937.2  261.77  4944.6  258.16
  4958.8  257.46  4965.6  257.49    4973  260.16  4979.8  260.94  4986.5  260.34
  5000.7   256.3  5005.2  255.75  5007.9  255.25  5011.2  255.75  5036.6  256.34
  5043.3  258.29  5050.8   259.4  5057.5  261.81    5065  262.34  5111.9  263.13
#Mann= 3 , 0 , 0
    4648     .16       0  5005.2     .07       0  5011.2     .16       0
#XS Ineff= 2 , 0
       0 4979.77  260.94               0
Permanent Ineff=
       T       F
Bank Sta=5005.2,5011.2
XS Rating Curve= 0 ,0
Exp/Cntr=0.3,0.1
Stream Node=UNT 091 IN LACR ,Reach-1         , 0 , 0 ,Upstream end
Stream Node=UNT 091 IN LACR ,Reach-1         , 0 , 1 ,Downstream end

Chan Stop Cuts=-1
Use User Specified Reach Order=0
Composite Channel Slope=5