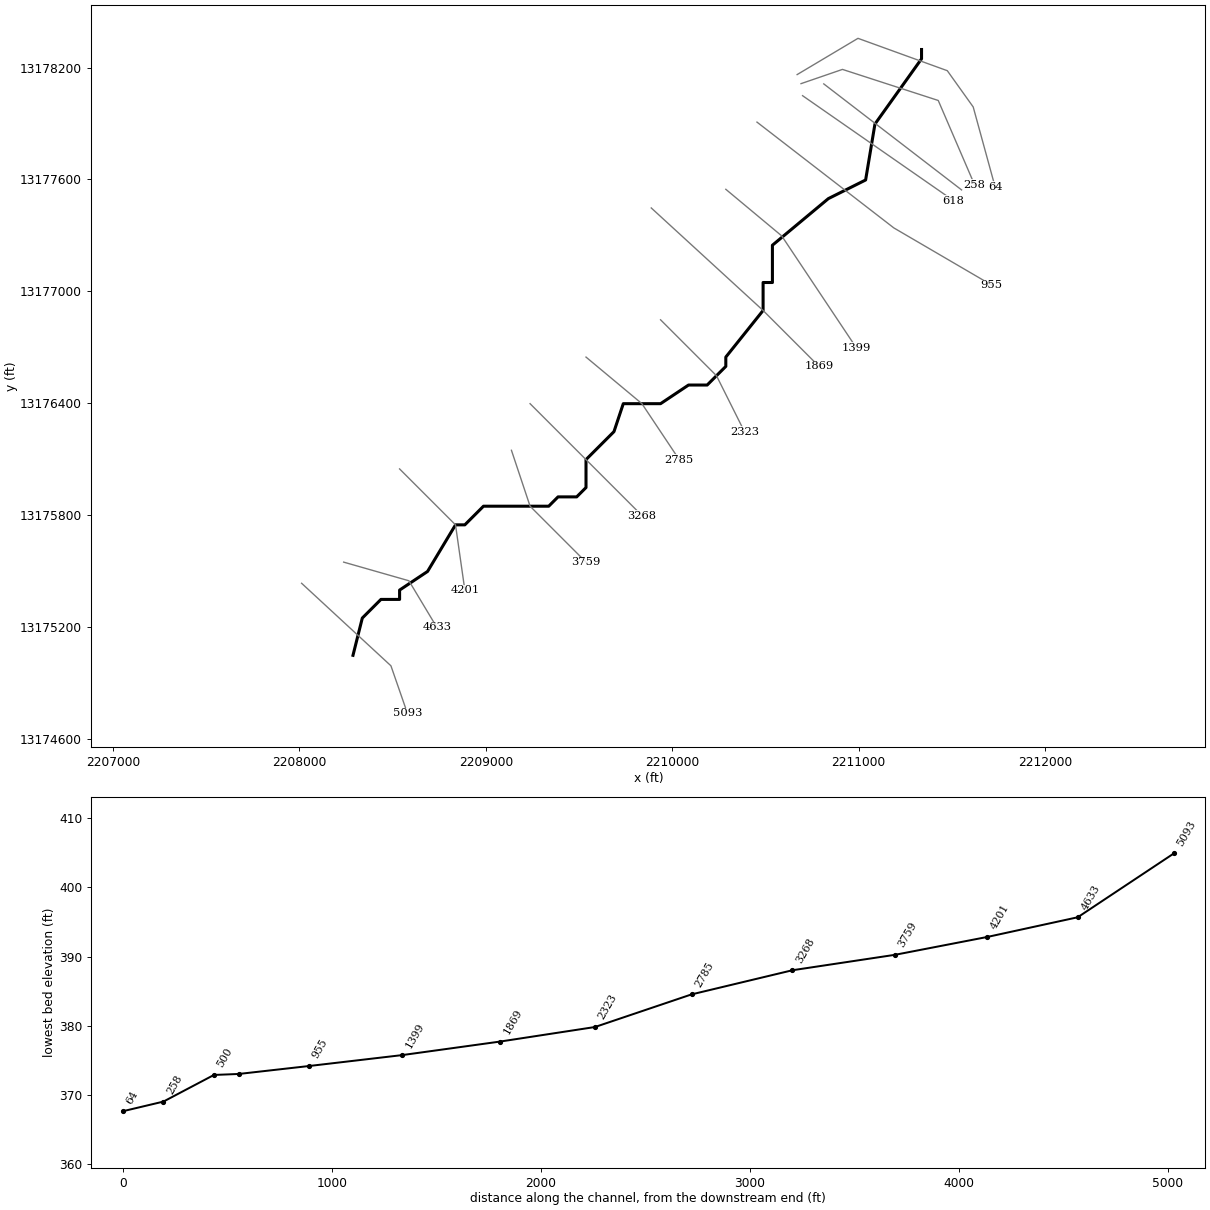
--- UNT 092 IN LACR.prj (project) ---

Proj Title=UNT 092 IN LACR Base Level Engineering
Current Plan=p01
Default Exp/Contr=0.3,0.1
English Units
Geom File=g01
Flow File=f01
Plan File=p01
Y Axis Title=Elevation
X Axis Title(PF)=Main Channel Distance
X Axis Title(XS)=Station
BEGIN DESCRIPTION:
UNT 092 IN LACR
END DESCRIPTION:
DSS Export Rating Curves= 0
DSS Export Rating Curve Sorted= 0
DSS Export Volume Flow Curves= 0
DXF OffsetX= 0
DXF OffsetY= 0
DXF ScaleX= 1
DXF ScaleY= 10

--- UNT 092 IN LACR.p01 (plan) ---

Plan Title=Multiple Run
Short Identifier=Multiple
Geom File=g01
Flow File=f01
Subcritical Flow
K Sum by GR= 0
Std Step Tol= 0.01
Critical Tol= 0.01
Num of Std Step Trials= 20
Max Error Tol= 0.3
Flow Tol Ratio= 0.001
Split Flow NTrial= 30
Split Flow Tol= 0.02
Split Flow Ratio= 0.02
Log Output Level= 0
Friction Slope Method= 1
Unsteady Friction Slope Method= 2
Unsteady Bridges Friction Slope Method= 1
Parabolic Critical Depth
Global Vel Dist=  1 , 1 , 1
Global Log Level= 0
CheckData=True
Encroach Param= -1, 0, 0, 0
BEGIN DESCRIPTION:
Multiple Run
END DESCRIPTION:

--- UNT 092 IN LACR.f01 (steady flow) ---

Flow Title=Multiple
Program Version=4.10
Number of Profiles= 7
Profile Names=10-year,25-year,50-year,1pct_min,100-year,1pct_plu,500-year
River Rch & RM=UNT 092 IN LACR,Reach-1         ,5093
     186     257     316     286     387     523     588
Boundary for River Rch & Prof#=UNT 092 IN LACR,Reach-1         , 1
Up Type= 0
Dn Type= 3
Dn Slope=0.009
Boundary for River Rch & Prof#=UNT 092 IN LACR,Reach-1         , 2
Up Type= 0
Dn Type= 3
Dn Slope=0.009
Boundary for River Rch & Prof#=UNT 092 IN LACR,Reach-1         , 3
Up Type= 0
Dn Type= 3
Dn Slope=0.009
Boundary for River Rch & Prof#=UNT 092 IN LACR,Reach-1         , 4
Up Type= 0
Dn Type= 3
Dn Slope=0.009
Boundary for River Rch & Prof#=UNT 092 IN LACR,Reach-1         , 5
Up Type= 0
Dn Type= 3
Dn Slope=0.009
Boundary for River Rch & Prof#=UNT 092 IN LACR,Reach-1         , 6
Up Type= 0
Dn Type= 3
Dn Slope=0.009
Boundary for River Rch & Prof#=UNT 092 IN LACR,Reach-1         , 7
Up Type= 0
Dn Type= 3
Dn Slope=0.009
DSS Import GetInterval= 0
DSS Import GetPeak= 0
DSS Import FillOption= 0

--- UNT 092 IN LACR.g01 (geometry) ---

Geom Title=Existing Conditions
Program Version=4.10

River Reach=UNT 092 IN LACR ,Reach-1
Reach XY= 30
      2208287.72     13175046.85      2208337.72     13175246.86
      2208437.72     13175346.85      2208537.72     13175346.85
      2208537.72     13175396.85      2208687.72     13175496.85
      2208837.72     13175746.86      2208887.72     13175746.86
      2208987.72     13175846.85      2209337.72     13175846.85
      2209387.72     13175896.86      2209487.72     13175896.86
      2209537.72     13175946.85      2209537.72     13176096.85
      2209687.72     13176246.86      2209737.72     13176396.86
      2209937.72     13176396.86      2210087.72     13176496.85
      2210187.72     13176496.85      2210287.72     13176596.85
      2210287.72     13176646.85      2210487.72     13176896.86
      2210487.72     13177046.86      2210537.72     13177046.86
      2210537.72     13177246.85      2210837.72     13177496.85
      2211037.72     13177596.85      2211087.72     13177896.86
      2211337.72     13178246.85      2211337.72     13178296.85

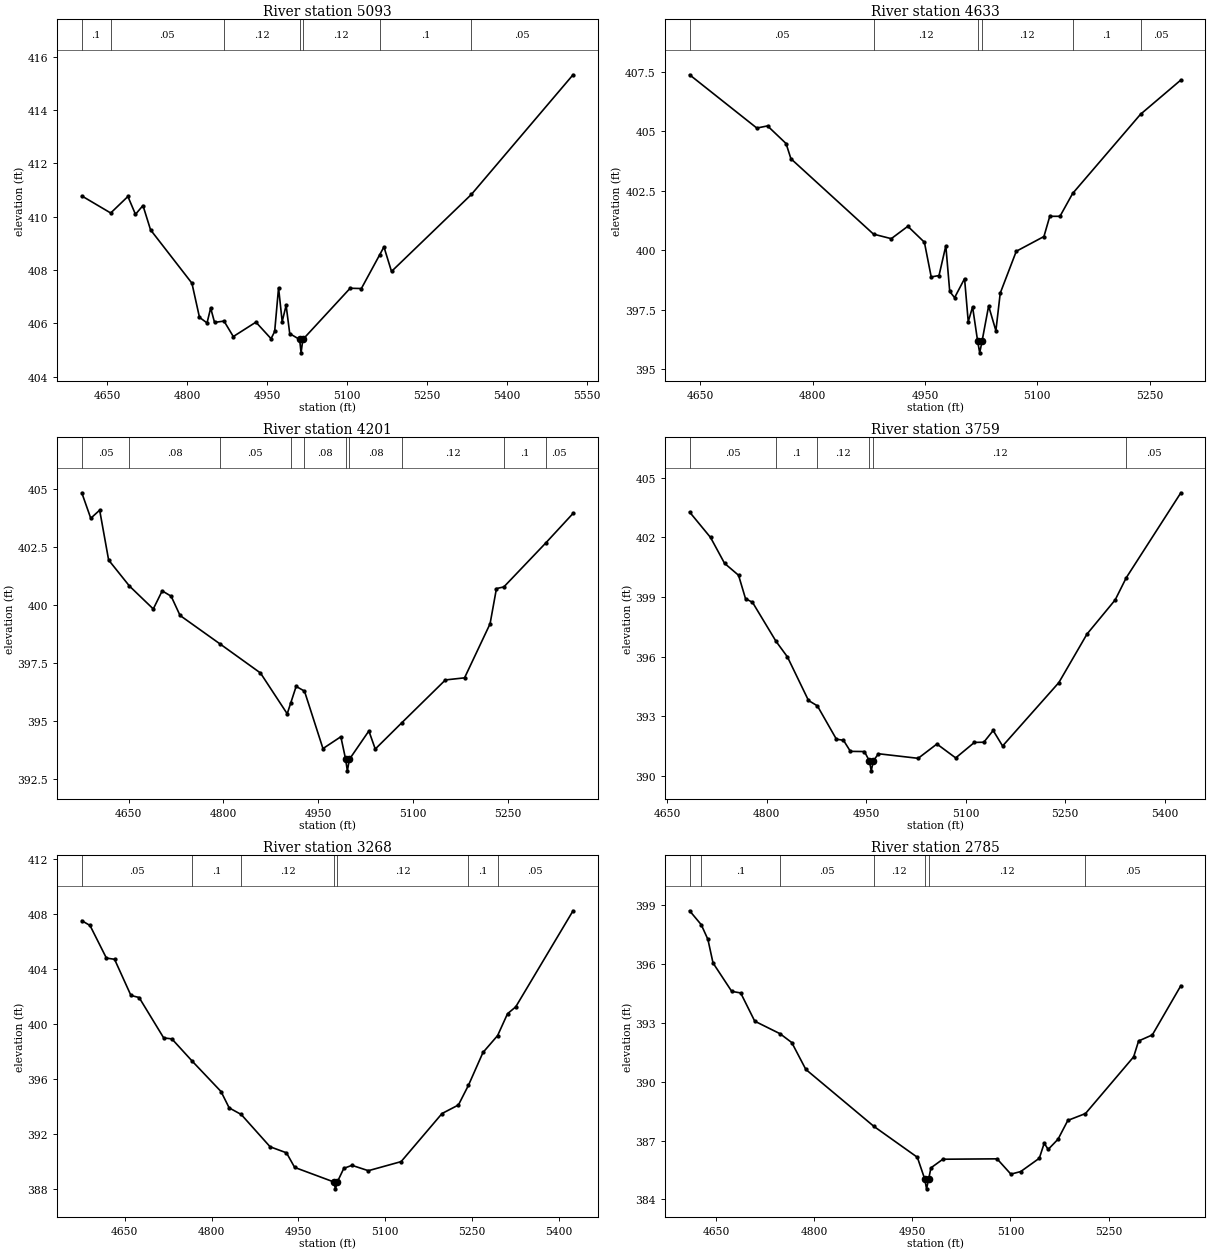
Type RM Length L Ch R = 1 ,5093    ,460,460,460
BEGIN DESCRIPTION:
UNT 092 IN LACR 11.0
END DESCRIPTION:
XS GIS Cut Line= 3
      2208012.12     13175433.39      2208491.29     13174990.68
      2208579.83     13174735.48
#Sta/Elev= 30
  4602.2  410.78  4656.5  410.14  4688.8  410.76    4703  410.09  4717.1  410.42
  4731.3  409.51    4809  407.51  4823.2  406.23  4837.4  406.02  4844.2  406.58
  4851.5  406.04  4869.3  406.09  4886.7  405.51  4929.2  406.05  4957.6  405.43
  4964.4   405.7  4971.7  407.34  4978.5  406.07  4985.9  406.68  4992.7  405.62
  5011.3   405.4    5014   404.9  5017.3   405.4  5106.1  407.32  5127.2  407.31
  5161.5  408.57  5169.6  408.87  5183.8  407.95    5334  410.84  5524.7  415.32
#Mann= 7 ,-1 , 0
  4602.2      .1       0  4656.5     .05       0  4869.3     .12       0
  5011.3     .07       0  5017.3     .12       0  5161.5      .1       0
    5334     .05       0
Bank Sta=5011.3,5017.3
XS Rating Curve= 0 ,0
Exp/Cntr=0.3,0.1

Type RM Length L Ch R = 1 ,4633    ,432,432,432
BEGIN DESCRIPTION:
UNT 092 IN LACR 10.0
END DESCRIPTION:
XS GIS Cut Line= 3
      2208237.73     13175546.85      2208587.72     13175446.85
       2208737.7      13175196.9
#Sta/Elev= 30
    4636  407.37  4725.7  405.13    4740  405.22  4764.7  404.48  4771.2  403.84
  4881.4  400.67  4905.1  400.48  4927.2     401  4949.3  400.33  4958.4  398.87
  4968.8  398.93  4977.9  400.18  4983.1  398.26  4989.6     398  5002.9   398.8
  5007.8  396.99  5013.6  397.61  5020.3  396.18  5023.1  395.68  5026.3  396.18
    5035  397.65  5044.7  396.61  5050.5  398.19  5071.9  399.95  5108.8  400.57
  5116.6  401.42  5130.2  401.42  5147.1  402.38  5237.7  405.71  5291.5  407.15
#Mann= 6 ,-1 , 0
    4636     .05       0  4881.4     .12       0  5020.3     .07       0
  5026.3     .12       0  5147.1      .1       0  5237.7     .05       0
Bank Sta=5020.3,5026.3
XS Rating Curve= 0 ,0
Exp/Cntr=0.3,0.1

Type RM Length L Ch R = 1 ,4201    ,442,442,442
BEGIN DESCRIPTION:
UNT 092 IN LACR 9.0
END DESCRIPTION:
XS GIS Cut Line= 3
       2208537.7     13176046.88      2208837.72     13175746.86
      2208887.73     13175396.81
#Sta/Elev= 30
  4575.7  404.83  4589.9  403.73    4604  404.08  4618.2  401.93  4651.1  400.81
  4688.9  399.82    4703   400.6  4717.2  400.37  4731.3  399.54  4794.2  398.32
  4858.6  397.06    4901   395.3  4906.5  395.76  4915.1  396.48  4928.3  396.28
  4957.6   393.8  4985.9  394.31  4993.5  393.34  4996.2  392.84  4999.5  393.34
  5030.3  394.56  5040.4  393.78  5082.3  394.91  5151.5  396.76  5181.8  396.85
  5222.2  399.18  5232.3   400.7    5244  400.77  5310.2  402.66  5353.6  403.94
#Mann= 10 ,-1 , 0
  4575.7     .05       0  4651.1     .08       0  4794.2     .05       0
  4906.5     .12       0  4928.3     .08       0  4993.5     .07       0
  4999.5     .08       0  5082.3     .12       0    5244      .1       0
  5310.2     .05       0
Bank Sta=4993.5,4999.5
XS Rating Curve= 0 ,0
Exp/Cntr=0.3,0.1

Type RM Length L Ch R = 1 ,3759    ,491,491,491
BEGIN DESCRIPTION:
UNT 092 IN LACR 8.0
END DESCRIPTION:
XS GIS Cut Line= 3
      2209137.73     13176146.83      2209237.72     13175846.85
      2209537.75     13175546.83
#Sta/Elev= 30
  4683.8  403.28  4715.4     402  4736.5   400.7  4757.6   400.1  4768.1  398.92
  4778.6  398.74    4814  396.78  4831.3  395.99    4863   393.8  4876.4  393.53
  4905.1  391.85  4915.7   391.8  4926.2  391.24  4947.3  391.23  4954.8  390.76
  4957.6  390.26  4960.8  390.76  4968.4  391.12  5028.3  390.89  5056.6  391.61
  5084.9  390.91  5113.1  391.69  5127.3   391.7  5141.4  392.29  5155.6  391.51
  5240.4   394.7  5282.8  397.14  5325.3  398.86  5341.9  399.97  5424.3  404.25
#Mann= 6 ,-1 , 0
  4683.8     .05       0    4814      .1       0  4876.4     .12       0
  4954.8     .07       0  4960.8     .12       0  5341.9     .05       0
Bank Sta=4954.8,4960.8
XS Rating Curve= 0 ,0
Exp/Cntr=0.3,0.1

Type RM Length L Ch R = 1 ,3268    ,483,483,483
BEGIN DESCRIPTION:
UNT 092 IN LACR 7.0
END DESCRIPTION:
XS GIS Cut Line= 3
       2209237.7     13176396.88      2209537.72     13176096.85
      2209837.75     13175796.83
#Sta/Elev= 30
  4575.7  407.54  4589.9  407.19  4618.2  404.82  4632.3  404.73  4660.6   402.1
  4674.7  401.95  4717.2  399.01  4731.3  398.94    4766  397.34  4816.2  395.11
  4830.3  393.92  4851.1  393.44    4901  391.09  4929.3  390.65  4943.4  389.59
  5011.1  388.53  5013.9  388.03  5017.1  388.53  5028.3  389.52  5042.4  389.74
  5070.7  389.35  5127.3  390.01    5198  393.51  5226.3  394.13  5243.7  395.57
  5268.7  397.95    5294  399.18  5311.1  400.77  5325.3  401.27  5424.3  408.26
#Mann= 7 ,-1 , 0
  4575.7     .05       0    4766      .1       0  4851.1     .12       0
  5011.1     .07       0  5017.1     .12       0  5243.7      .1       0
    5294     .05       0
Bank Sta=5011.1,5017.1
XS Rating Curve= 0 ,0
Exp/Cntr=0.3,0.1

Type RM Length L Ch R = 1 ,2785    ,462,462,462
BEGIN DESCRIPTION:
UNT 092 IN LACR 6.0
END DESCRIPTION:
XS GIS Cut Line= 3
      2209537.73     13176646.85      2209837.72     13176396.86
      2210037.75     13176096.82
#Sta/Elev= 30
  4609.5  398.72  4627.3  398.01  4637.5  397.26  4645.3  396.06  4673.9  394.61
  4687.6  394.53  4709.1  393.09  4747.8  392.45  4765.7     392  4787.2  390.63
  4891.5  387.72  4957.7  386.15    4969  385.04  4971.8  384.54    4975  385.04
  4978.5  385.61  4996.7  386.05  5079.6  386.07  5100.7  385.29  5115.7  385.42
  5144.2   386.1  5151.7  386.87  5157.7  386.55  5172.8  387.07  5187.8  388.03
  5214.8  388.38  5288.4  391.27    5296  392.08    5317  392.39  5360.6   394.9
#Mann= 7 ,-1 , 0
  4609.5     .05       0  4627.3      .1       0  4747.8     .05       0
  4891.5     .12       0    4969     .07       0    4975     .12       0
  5214.8     .05       0
Bank Sta=4969,4975
XS Rating Curve= 0 ,0
Exp/Cntr=0.3,0.1

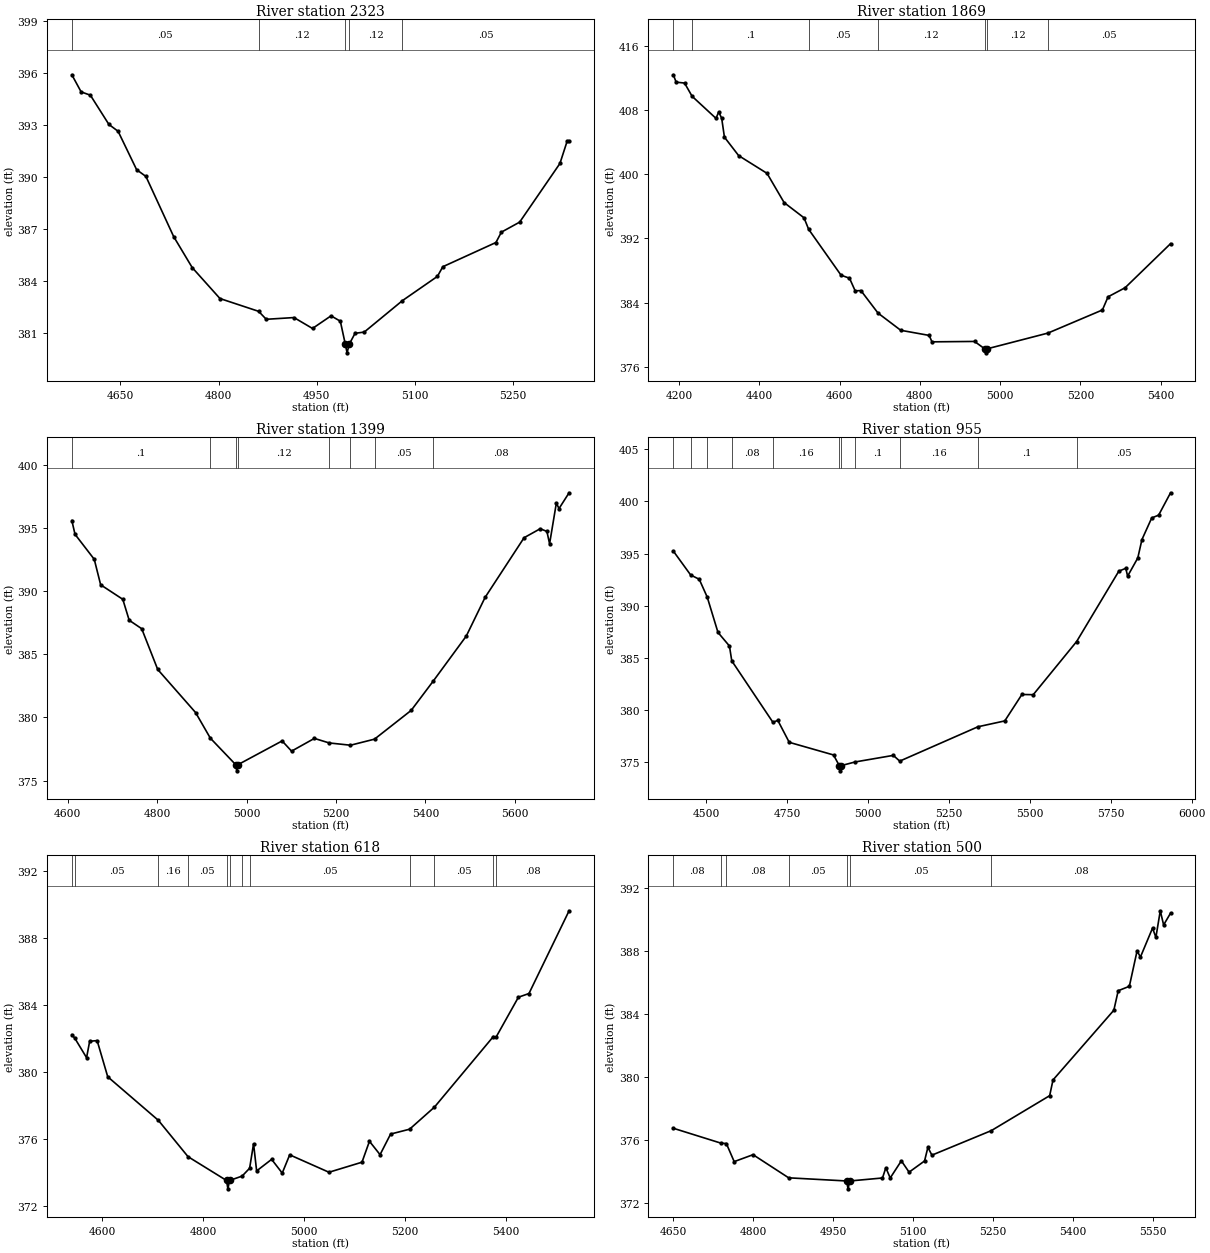
Type RM Length L Ch R = 1 ,2323    ,454,454,454
BEGIN DESCRIPTION:
UNT 092 IN LACR 5.0
END DESCRIPTION:
XS GIS Cut Line= 3
       2209937.7     13176846.88      2210237.72     13176546.85
      2210387.72     13176246.86
#Sta/Elev= 30
  4575.7  395.91  4589.9  394.92    4604  394.73  4632.3  393.04  4646.4  392.64
  4674.7  390.42  4688.9  390.03  4731.3  386.55  4759.6  384.76    4802  382.97
  4861.1  382.23  4872.7  381.77  4915.1  381.87  4943.4  381.24  4971.7  381.97
  4985.9  381.66  4993.5  380.33  4996.2  379.83  4999.5  380.33  5008.4  380.96
  5022.4  381.03  5080.8  382.85  5134.2  384.25  5142.5  384.81  5223.6  386.21
    5232  386.81  5259.9  387.39  5321.4  390.78  5332.6  392.09  5335.4  392.09
#Mann= 5 ,-1 , 0
  4575.7     .05       0  4861.1     .12       0  4993.5     .07       0
  4999.5     .12       0  5080.8     .05       0
Bank Sta=4993.5,4999.5
XS Rating Curve= 0 ,0
Exp/Cntr=0.3,0.1

Type RM Length L Ch R = 1 ,1869    ,470,470,470
BEGIN DESCRIPTION:
UNT 092 IN LACR 4.0
END DESCRIPTION:
XS GIS Cut Line= 3
      2209887.75     13177446.83      2210487.72     13176896.86
      2210787.75     13176596.83
#Sta/Elev= 30
  4186.1  412.37  4193.2  411.45  4214.1  411.34  4232.9  409.69  4292.4  406.94
  4299.2  407.75  4306.6  406.94  4313.4   404.6  4348.8   402.3  4419.5  400.09
    4462  396.45  4511.6  394.55  4523.1  393.12  4603.8   387.4  4624.8  387.03
    4639  385.45  4653.2  385.49  4695.9  382.68  4752.4  380.54  4823.3   379.9
  4830.1   379.1  4936.2  379.15  4961.5  378.23  4964.3  377.73  4967.5  378.23
  5118.9  380.19  5254.6  383.07  5268.7  384.71  5311.1  385.84  5424.3  391.33
#Mann= 7 ,-1 , 0
  4186.1     .08       0  4232.9      .1       0  4523.1     .05       0
  4695.9     .12       0  4961.5     .07       0  4967.5     .12       0
  5118.9     .05       0
Bank Sta=4961.5,4967.5
XS Rating Curve= 0 ,0
Exp/Cntr=0.3,0.1

Type RM Length L Ch R = 1 ,1399    ,444,444,444
BEGIN DESCRIPTION:
UNT 092 IN LACR 3.0
END DESCRIPTION:
XS GIS Cut Line= 3
      2210287.73     13177546.85      2210587.72     13177296.85
      2210987.71     13176696.86
#Sta/Elev= 30
  4609.5   395.6  4616.6  394.51  4659.6  392.53  4673.9  390.51  4723.4  389.36
  4737.7   387.7  4765.7  387.03  4801.5   383.8  4886.1  380.39  4919.1  378.36
  4975.5  376.27  4978.3  375.77  4981.5  376.27  5079.6  378.14  5100.7  377.33
  5151.7  378.34  5184.8  377.98  5232.4   377.8  5286.1  378.28  5368.1  380.56
  5417.6  382.89  5491.3  386.45  5533.3  389.51  5620.5  394.24  5656.5  394.95
  5671.5  394.74  5677.5  393.76  5692.6  396.98  5698.6  396.55  5721.1   397.8
#Mann= 8 ,-1 , 0
  4609.5      .1       0  4919.1     .12       0  4975.5     .07       0
  4981.5     .12       0  5184.8     .05       0  5232.4      .1       0
  5286.1     .05       0  5417.6     .08       0
Bank Sta=4975.5,4981.5
XS Rating Curve= 0 ,0
Exp/Cntr=0.3,0.1

Type RM Length L Ch R = 1 ,955     ,337,337,337
BEGIN DESCRIPTION:
UNT 092 IN LACR 2.0
END DESCRIPTION:
XS GIS Cut Line= 3
      2210454.85     13177907.33      2211189.21     13177339.64
      2211714.03     13177033.06
#Sta/Elev= 30
  4398.8  395.24  4452.4  392.95  4478.9  392.54  4503.6  390.83  4536.8  387.45
  4572.2  386.15  4579.4  384.73  4706.4  378.85  4721.6  379.03  4756.9  376.93
  4893.7  375.72  4911.5   374.7  4914.2   374.2  4917.5   374.7  4960.3  375.05
  5078.4  375.68  5098.2  375.13  5339.9  378.42  5422.7  378.98  5475.6  381.51
  5510.6  381.49  5644.7  386.58  5774.9  393.31  5796.4  393.59  5802.2  392.84
  5833.6  394.58  5846.4  396.34  5876.6  398.41    5898  398.68  5934.8  400.82
#Mann= 11 ,-1 , 0
  4398.8     .05       0  4452.4      .1       0  4503.6     .05       0
  4579.4     .08       0  4706.4     .16       0  4911.5     .07       0
  4917.5     .16       0  4960.3      .1       0  5098.2     .16       0
  5339.9      .1       0  5644.7     .05       0
Bank Sta=4911.5,4917.5
XS Rating Curve= 0 ,0
Exp/Cntr=0.3,0.1

Type RM Length L Ch R = 1 ,618     ,118,118,118
BEGIN DESCRIPTION:
Mapping XS 185fe662
END DESCRIPTION:
XS GIS Cut Line= 2
      2210699.52     13178049.07      2211508.32      13177486.7
#Sta/Elev= 30
  4539.9  382.25  4545.4  382.06  4569.1  380.88  4575.2  381.86    4590   381.9
    4611  379.74  4711.3  377.14  4770.1  374.97  4846.3  373.55  4849.1  373.05
  4852.3  373.55  4877.2  373.81  4892.1  374.28  4899.9  375.74    4906  374.12
  4935.7  374.81  4956.7  373.99  4971.5  375.08  5049.3  374.04  5114.7  374.64
  5129.5  375.89  5150.5  375.09  5171.4  376.32    5209  376.61  5258.3  377.93
  5374.9  382.14  5380.4  382.11  5424.6  384.49  5445.5  384.71    5525  389.65
#Mann= 12 ,-1 , 0
  4539.9     .08       0  4545.4     .05       0  4711.3     .16       0
  4770.1     .05       0  4846.3    .035       0  4852.3     .05       0
  4877.2     .16       0  4892.1     .05       0    5209      .1       0
  5258.3     .05       0  5374.9      .1       0  5380.4     .08       0
Bank Sta=4846.3,4852.3
XS Rating Curve= 0 ,0
Exp/Cntr=0.3,0.1

Type RM Length L Ch R = 1 ,500     ,242,242,242
BEGIN DESCRIPTION:
Mapping XS 533b21ca
END DESCRIPTION:
XS GIS Cut Line= 2
       2210813.2     13178112.31      2211552.56     13177543.57
#Sta/Elev= 30
  4650.6  376.76  4740.3  375.81  4750.1  375.79  4764.8  374.64  4800.2  375.08
    4867  373.61  4975.7  373.41  4978.4  372.91  4981.7  373.41    5043   373.6
  5049.3  374.25  5057.5   373.6  5078.4  374.69  5092.9  373.97  5121.9  374.68
  5128.2  375.55  5135.7  375.05  5247.2  376.61  5356.6  378.83  5362.9  379.83
    5477  384.26  5485.2   385.5  5506.1  385.78  5520.6  388.03  5526.9  387.64
  5549.6  389.48  5555.9  388.89  5564.1  390.58  5570.4  389.68  5583.4  390.43
#Mann= 7 ,-1 , 0
  4650.6     .08       0  4740.3     .05       0  4750.1     .08       0
    4867     .05       0  4975.7     .04       0  4981.7     .05       0
  5247.2     .08       0
Bank Sta=4975.7,4981.7
XS Rating Curve= 0 ,0
Exp/Cntr=0.3,0.1

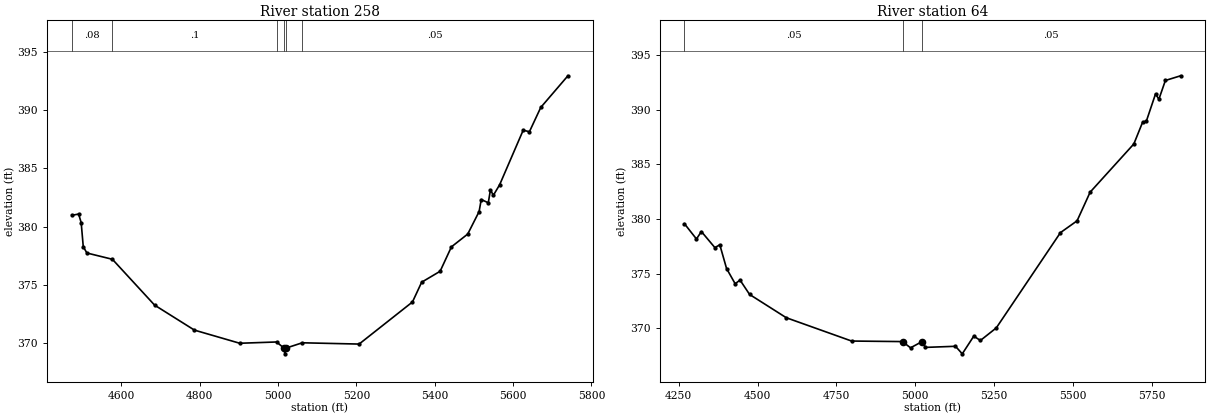
Type RM Length L Ch R = 1 ,258     ,194,194,194
BEGIN DESCRIPTION:
Mapping XS f9e2c5dd
END DESCRIPTION:
XS GIS Cut Line= 4
      2210691.21     13178113.66      2210913.44     13178190.05
      2211427.33     13178023.38      2211621.77     13177572.01
#Sta/Elev= 30
  4473.3  380.97  4490.8  381.08  4497.3  380.34  4502.6  378.27  4511.9  377.73
    4577  377.19  4684.7  373.25  4786.4   371.1  4902.1  369.97  4996.2  370.08
  5014.7  369.56  5017.4  369.06  5020.7  369.56  5061.8  370.01  5206.9   369.9
  5343.1  373.52  5366.6  375.22  5413.7  376.16  5442.6  378.26  5484.2  379.36
  5513.2  381.29  5518.7  382.33  5536.7  382.05  5542.2  383.16  5549.6  382.69
  5565.7   383.6  5625.8  388.29  5641.7  388.16  5670.7  390.25    5740  392.97
#Mann= 6 ,-1 , 0
  4473.3     .08       0    4577      .1       0  4996.2     .12       0
  5014.7     .07       0  5020.7     .12       0  5061.8     .05       0
Bank Sta=5014.7,5020.7
XS Rating Curve= 0 ,0
Exp/Cntr=0.3,0.1

Type RM Length L Ch R = 1 ,64      ,0,0,0
BEGIN DESCRIPTION:
UNT 092 IN LACR 1.0
END DESCRIPTION:
XS GIS Cut Line= 5
      2210670.37     13178162.26      2210996.78     13178356.72
      2211475.94      13178183.1      2211614.83     13177988.66
      2211732.28     13177560.31
#Sta/Elev= 30
  4268.1  379.56  4306.1  378.17  4321.7  378.85  4364.5  377.38  4380.1  377.64
  4401.5  375.47  4428.7  374.08  4444.3  374.41  4474.5   373.1  4590.9  370.97
  4797.9  368.84  4959.3  368.79  4984.7  368.22  5021.3  368.79  5031.9  368.26
  5127.2  368.36  5148.7  367.67  5185.2  369.29  5206.1  368.89  5256.5  370.04
  5459.9  378.75  5512.6  379.83    5554  382.45  5692.6  386.86    5720  388.82
  5732.3  388.95  5761.4  391.44  5771.9  390.94  5792.5  392.66  5840.8  393.09
#Mann= 3 , 0 , 0
  4268.1     .05       0  4959.3    .035       0  5021.3     .05       0
Bank Sta=4959.3,5021.3
XS Rating Curve= 0 ,0
Exp/Cntr=0.3,0.1

Chan Stop Cuts=-1
Use User Specified Reach Order=0
Composite Channel Slope=5