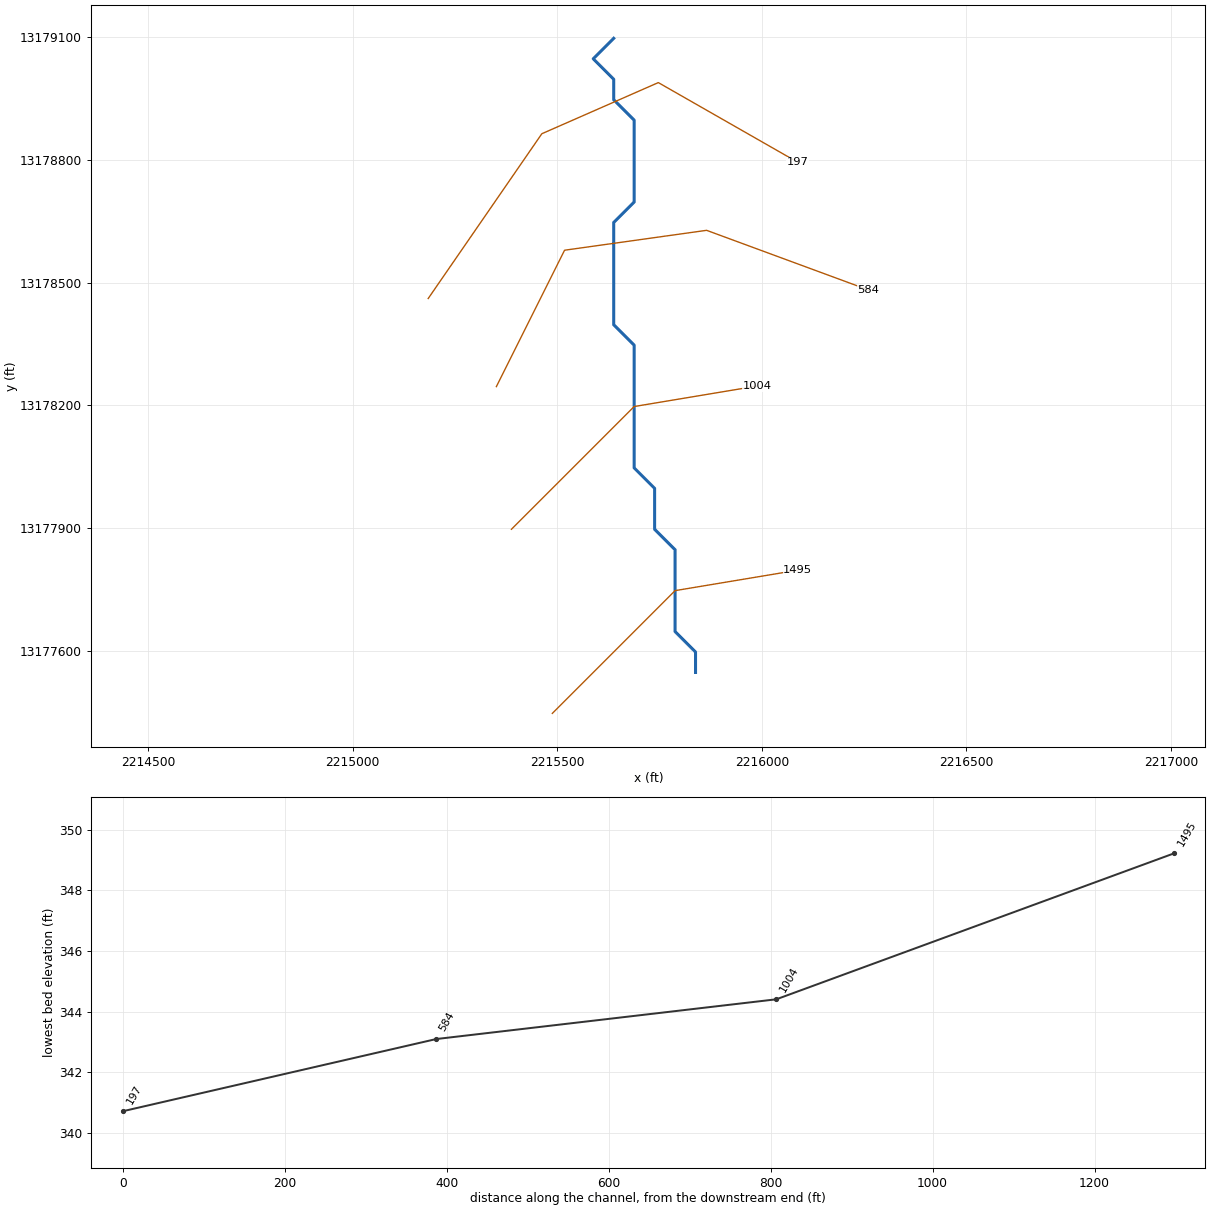
--- UNT 093 IN LACR.prj (project) ---

Proj Title=UNT 093 IN LACR Base Level Engineering
Current Plan=p01
Default Exp/Contr=0.3,0.1
English Units
Geom File=g01
Flow File=f01
Plan File=p01
BEGIN DESCRIPTION:
UNT 093 IN LACR
END DESCRIPTION:

--- UNT 093 IN LACR.p01 (plan) ---

Plan Title=Multiple Run
Short Identifier=Multiple
Geom File=g01
Flow File=f01
Subcritical Flow
K Sum by GR= 0
Std Step Tol= 0.01
Critical Tol= 0.01
Num of Std Step Trials= 20
Max Error Tol= 0.3
Flow Tol Ratio= 0.001
Split Flow NTrial= 30
Split Flow Tol= 0.02
Split Flow Ratio= 0.02
Log Output Level= 0
Friction Slope Method= 1
Unsteady Friction Slope Method= 2
Unsteady Bridges Friction Slope Method= 1
Parabolic Critical Depth
Global Vel Dist=  1 , 1 , 1
Global Log Level= 0
CheckData=True
Encroach Param= -1, 0, 0, 0
BEGIN DESCRIPTION:
Multiple Run
END DESCRIPTION:

--- UNT 093 IN LACR.f01 (steady flow) ---

Flow Title=Multiple
Number of Profiles=7
Profile Names=10-year,25-year,50-year,1pct_min,100-year,1pct_plu,500-year
River Rch & RM= UNT 093 IN LACR,Reach-1,1495
     179     245     300     271     366     496     553
Boundary for River Rch & Prof#=UNT 093 IN LACR,Reach-1,1
Up Type=0
Dn Type=3
Dn Slope=0.005
Boundary for River Rch & Prof#=UNT 093 IN LACR,Reach-1,2
Up Type=0
Dn Type=3
Dn Slope=0.005
Boundary for River Rch & Prof#=UNT 093 IN LACR,Reach-1,3
Up Type=0
Dn Type=3
Dn Slope=0.005
Boundary for River Rch & Prof#=UNT 093 IN LACR,Reach-1,4
Up Type=0
Dn Type=3
Dn Slope=0.005
Boundary for River Rch & Prof#=UNT 093 IN LACR,Reach-1,5
Up Type=0
Dn Type=3
Dn Slope=0.005
Boundary for River Rch & Prof#=UNT 093 IN LACR,Reach-1,6
Up Type=0
Dn Type=3
Dn Slope=0.005
Boundary for River Rch & Prof#=UNT 093 IN LACR,Reach-1,7
Up Type=0
Dn Type=3
Dn Slope=0.005

--- UNT 093 IN LACR.g01 (geometry) ---

Geom Title=Existing Conditions

River Reach=UNT 093 IN LACR,Reach-1
Reach XY= 16
      2215837.72     13177546.86      2215837.72     13177596.85
      2215787.72     13177646.85      2215787.72     13177846.85
      2215737.72     13177896.86      2215737.72     13177996.85
      2215687.72     13178046.86      2215687.72     13178346.85
      2215637.72     13178396.85      2215637.72     13178646.85
      2215687.72     13178696.86      2215687.72     13178896.85
      2215637.72     13178946.85      2215637.72     13178996.85
      2215587.72     13179046.86      2215637.72     13179096.85

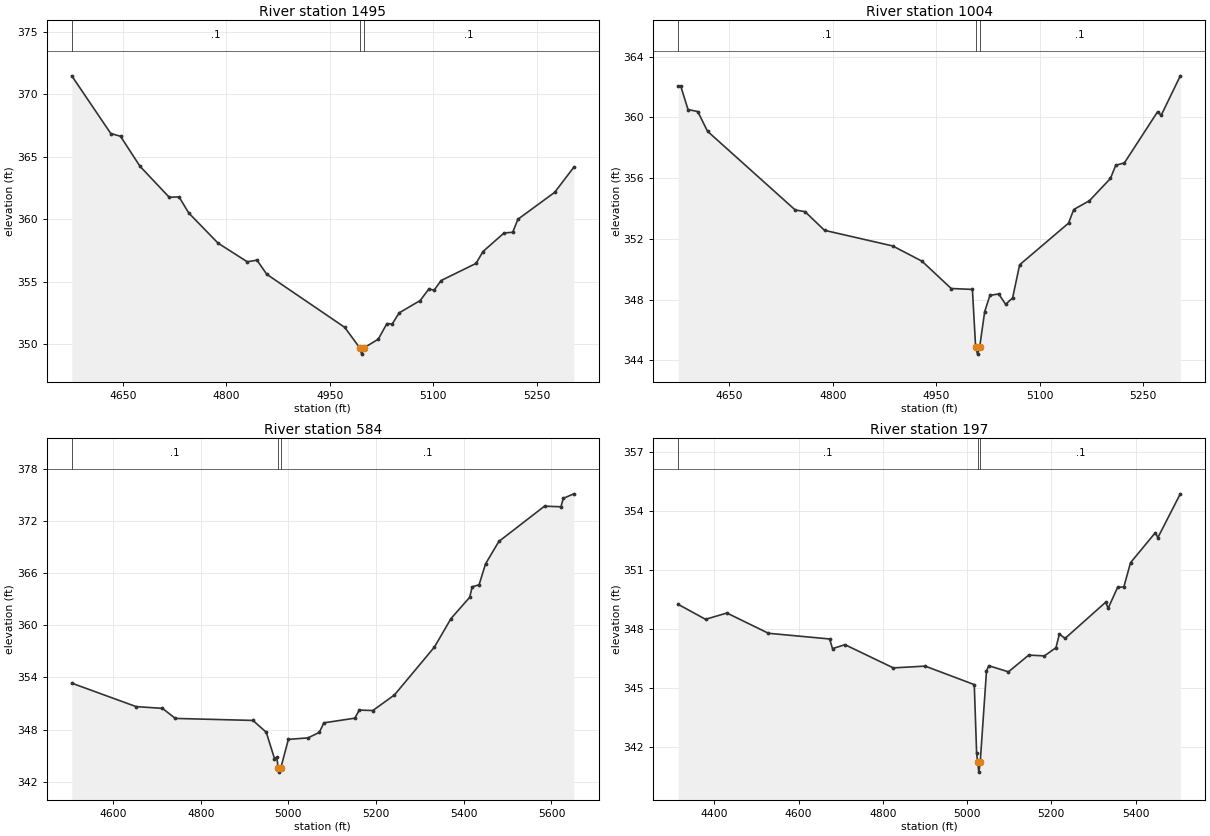
Type RM Length L Ch R = 1,1495,491,491,491
BEGIN DESCRIPTION:
UNT 093 IN LACR 3.0
END DESCRIPTION:
XS GIS Cut Line= 3
      2215487.70     13177446.83      2215787.72     13177746.85
      2216087.68     13177796.85
#Sta/Elev= 30
  4575.7  371.46  4632.3  366.85  4646.4  366.63  4674.7  364.23  4717.2  361.75
  4731.3  361.79  4745.4  360.50  4787.9  358.09  4830.3  356.60  4844.4  356.73
  4858.6  355.60  4971.7  351.36  4993.5  349.72  4996.2  349.22  4999.5  349.72
  5020.3  350.41  5032.9  351.66  5040.6  351.63  5050.7  352.52  5081.1  353.50
  5093.8  354.43  5101.4  354.33  5111.5  355.10  5162.2  356.47  5172.3  357.42
  5202.8  358.90  5215.4  358.96  5223.0  360.00  5276.3  362.15  5304.1  364.16
#Mann=3,-1,0
  4575.7     0.1       0  4993.5    0.07       0  4999.5     0.1       0
Bank Sta=4993.5,4999.5
Exp/Cntr=0.3,0.1

Type RM Length L Ch R = 1,1004,420,420,420
BEGIN DESCRIPTION:
UNT 093 IN LACR 2.0
END DESCRIPTION:
XS GIS Cut Line= 3
      2215387.70     13177896.83      2215687.72     13178196.86
      2215987.68     13178246.85
#Sta/Elev= 30
  4575.7  362.06  4579.3  362.06  4589.9  360.51  4604.0  360.38  4618.2  359.08
  4745.4  353.90  4759.6  353.79  4787.9  352.56  4886.9  351.53  4929.3  350.53
  4971.7  348.73  5002.5  348.67  5007.1  344.91  5009.9  344.41  5013.1  344.91
  5020.3  347.21  5027.9  348.28  5040.6  348.37  5050.7  347.69  5060.8  348.11
  5071.0  350.29  5141.9  353.03  5149.5  353.93  5172.3  354.51  5202.8  355.98
  5210.4  356.84  5223.0  357.00  5271.2  360.37  5276.3  360.13  5304.1  362.73
#Mann=3,-1,0
  4575.7     0.1       0  5007.1    0.07       0  5013.1     0.1       0
Bank Sta=5007.1,5013.1
Exp/Cntr=0.3,0.1

Type RM Length L Ch R = 1,584,387,387,387
BEGIN DESCRIPTION:
Mapping XS 101ff3d6
END DESCRIPTION:
XS GIS Cut Line= 4
      2215350.92     13178245.57      2215517.61     13178578.94
      2215864.83     13178627.55      2216260.51     13178481.77
#Sta/Elev= 30
  4506.0  353.34  4652.8  350.64  4712.8  350.44  4742.2  349.28  4919.2  349.05
  4949.5  347.69  4968.3  344.66  4973.3  344.81  4976.8  343.60  4979.6  343.10
  4982.8  343.60  5000.0  346.87  5044.7  347.04  5070.7  347.68  5080.8  348.77
  5151.5  349.31  5161.6  350.24  5192.6  350.19  5241.8  351.98  5333.1  357.50
  5370.9  360.78  5413.6  363.23  5419.1  364.43  5434.9  364.66  5449.6  367.07
  5480.0  369.65  5584.1  373.71  5621.6  373.64  5626.9  374.61  5651.0  375.13
#Mann=3,-1,0
  4506.0     0.1       0  4976.8    0.07       0  4982.8     0.1       0
Bank Sta=4976.8,4982.8
Exp/Cntr=0.3,0.1

Type RM Length L Ch R = 1,197,0,0,0
BEGIN DESCRIPTION:
UNT 093 IN LACR 1.0
END DESCRIPTION:
XS GIS Cut Line= 4
      2215184.30     13178460.91      2215462.05     13178863.66
      2215746.78     13178988.66      2216087.05     13178794.22
#Sta/Elev= 30
  4314.3  349.25  4379.1  348.49  4429.8  348.81  4528.5  347.78  4673.8  347.49
  4680.6  347.00  4710.2  347.20  4825.0  346.02  4900.6  346.11  5017.2  345.17
  5022.8  341.67  5025.3  341.22  5028.0  340.72  5031.3  341.22  5046.2  345.86
  5051.6  346.13  5098.4  345.82  5146.4  346.67  5183.8  346.63  5211.2  347.05
  5219.2  347.74  5232.8  347.52  5329.2  349.36  5335.0  349.05  5357.4  350.11
  5372.4  350.14  5388.2  351.37  5447.3  352.90  5453.0  352.64  5506.4  354.87
#Mann=3,-1,0
  4314.3     0.1       0  5025.3    0.07       0  5031.3     0.1       0
Bank Sta=5025.3,5031.3
Exp/Cntr=0.3,0.1

Chan Stop Cuts=-1