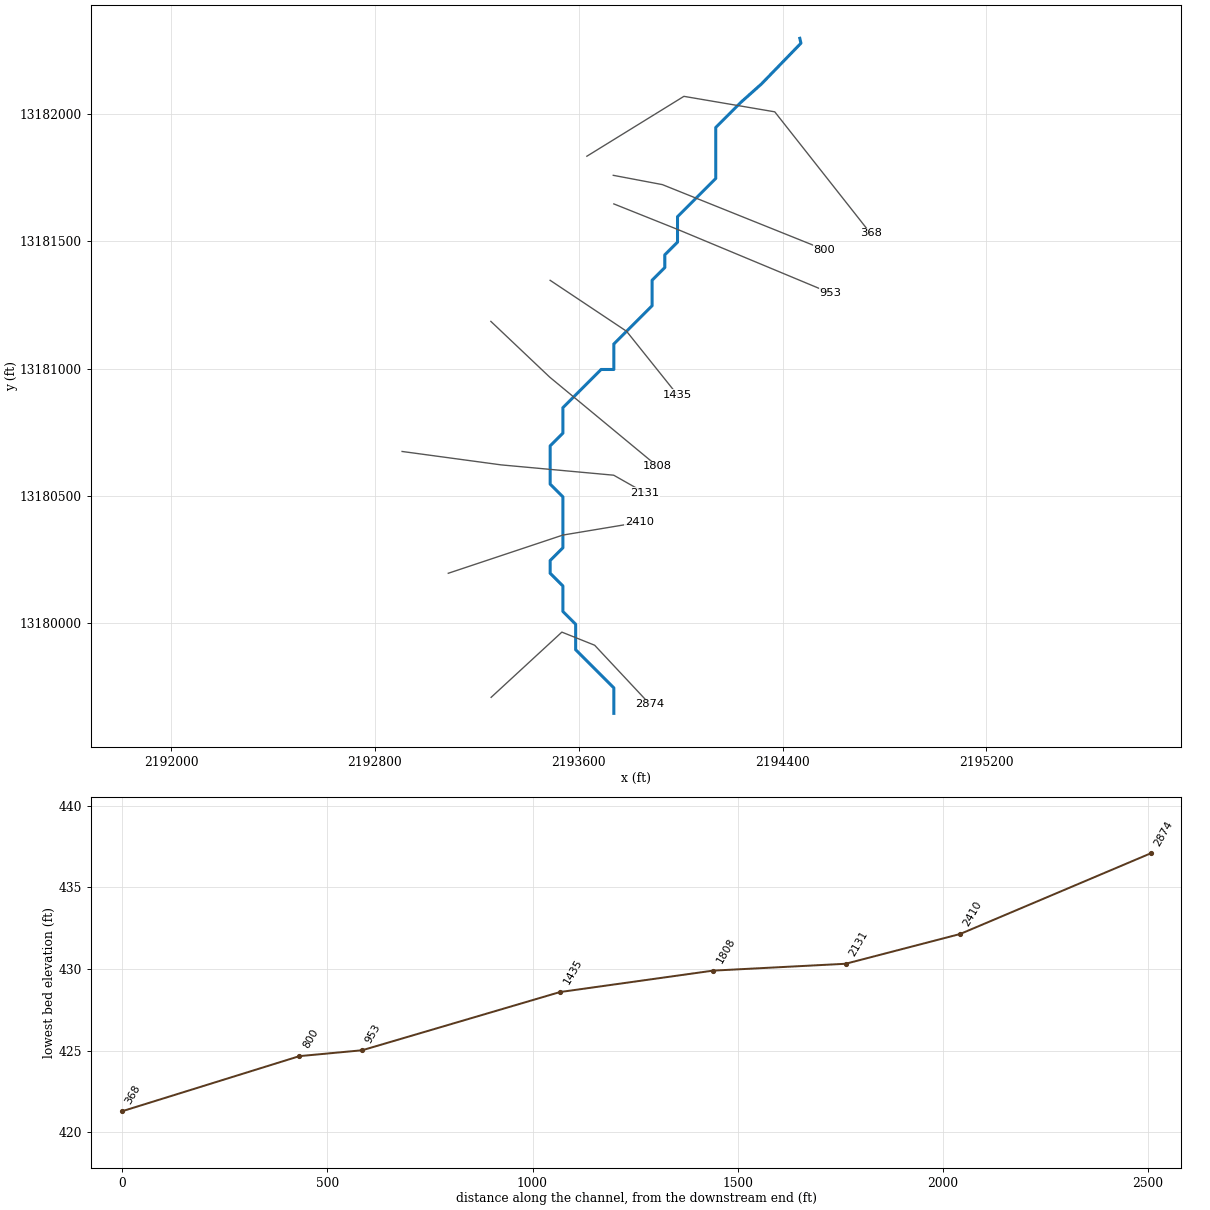
--- UNT 094 IN LACR.prj (project) ---

Proj Title=UNT 094 IN LACR Base Level Engineering
Current Plan=p01
Default Exp/Contr=0.3,0.1
English Units
Geom File=g01
Flow File=f01
Plan File=p01
Y Axis Title=Elevation
X Axis Title(PF)=Main Channel Distance
X Axis Title(XS)=Station
BEGIN DESCRIPTION:
UNT 094 IN LACR
END DESCRIPTION:
DSS Export Rating Curves= 0
DSS Export Rating Curve Sorted= 0
DSS Export Volume Flow Curves= 0
DXF OffsetX= 0
DXF OffsetY= 0
DXF ScaleX= 1
DXF ScaleY= 10

--- UNT 094 IN LACR.p01 (plan) ---

Plan Title=Multiple Run
Short Identifier=Multiple
Geom File=g01
Flow File=f01
Subcritical Flow
K Sum by GR= 0
Std Step Tol= 0.01
Critical Tol= 0.01
Num of Std Step Trials= 20
Max Error Tol= 0.3
Flow Tol Ratio= 0.001
Split Flow NTrial= 30
Split Flow Tol= 0.02
Split Flow Ratio= 0.02
Log Output Level= 0
Friction Slope Method= 1
Unsteady Friction Slope Method= 2
Unsteady Bridges Friction Slope Method= 1
Parabolic Critical Depth
Global Vel Dist=  1 , 1 , 1
Global Log Level= 0
CheckData=True
Encroach Param= -1, 0, 0, 0
BEGIN DESCRIPTION:
Multiple Run
END DESCRIPTION:

--- UNT 094 IN LACR.f01 (steady flow) ---

Flow Title=Multiple
Program Version=4.10
Number of Profiles= 7
Profile Names=10-year,25-year,50-year,1pct_min,100-year,1pct_plu,500-year
River Rch & RM=UNT 094 IN LACR,Reach-1         ,2874
     111     148     178     157     213     288     308
River Rch & RM=UNT 094 IN LACR,Reach-1         ,368
     369     527     663     612     827    1119    1309
Boundary for River Rch & Prof#=UNT 094 IN LACR,Reach-1         , 1
Up Type= 0
Dn Type= 3
Dn Slope=0.008
Boundary for River Rch & Prof#=UNT 094 IN LACR,Reach-1         , 2
Up Type= 0
Dn Type= 3
Dn Slope=0.008
Boundary for River Rch & Prof#=UNT 094 IN LACR,Reach-1         , 3
Up Type= 0
Dn Type= 3
Dn Slope=0.008
Boundary for River Rch & Prof#=UNT 094 IN LACR,Reach-1         , 4
Up Type= 0
Dn Type= 3
Dn Slope=0.008
Boundary for River Rch & Prof#=UNT 094 IN LACR,Reach-1         , 5
Up Type= 0
Dn Type= 3
Dn Slope=0.008
Boundary for River Rch & Prof#=UNT 094 IN LACR,Reach-1         , 6
Up Type= 0
Dn Type= 3
Dn Slope=0.008
Boundary for River Rch & Prof#=UNT 094 IN LACR,Reach-1         , 7
Up Type= 0
Dn Type= 3
Dn Slope=0.008
DSS Import GetInterval= 0
DSS Import GetPeak= 0
DSS Import FillOption= 0

--- UNT 094 IN LACR.g01 (geometry) ---

Geom Title=Existing Conditions
Program Version=4.10

River Reach=UNT 094 IN LACR ,Reach-1
Reach XY= 30
      2193737.72     13179646.85      2193737.72     13179746.85
      2193587.72     13179896.85      2193587.72     13179996.86
      2193537.72     13180046.85      2193537.72     13180146.85
      2193487.72     13180196.86      2193487.72     13180246.85
      2193537.72     13180296.85      2193537.72     13180496.86
      2193487.72     13180546.85      2193487.72     13180696.85
      2193537.72     13180746.85      2193537.72     13180846.86
      2193687.72     13180996.86      2193737.72     13180996.86
      2193737.72     13181096.85      2193887.72     13181246.85
      2193887.72     13181346.85      2193937.72     13181396.85
      2193937.72     13181446.85      2193987.72     13181496.86
      2193987.72     13181596.85      2194037.72     13181646.86
      2194137.72     13181746.85      2194137.72     13181946.85
      2194237.72     13182046.85       2194317.2     13182117.74
      2194472.23     13182277.63      2194467.72     13182296.86

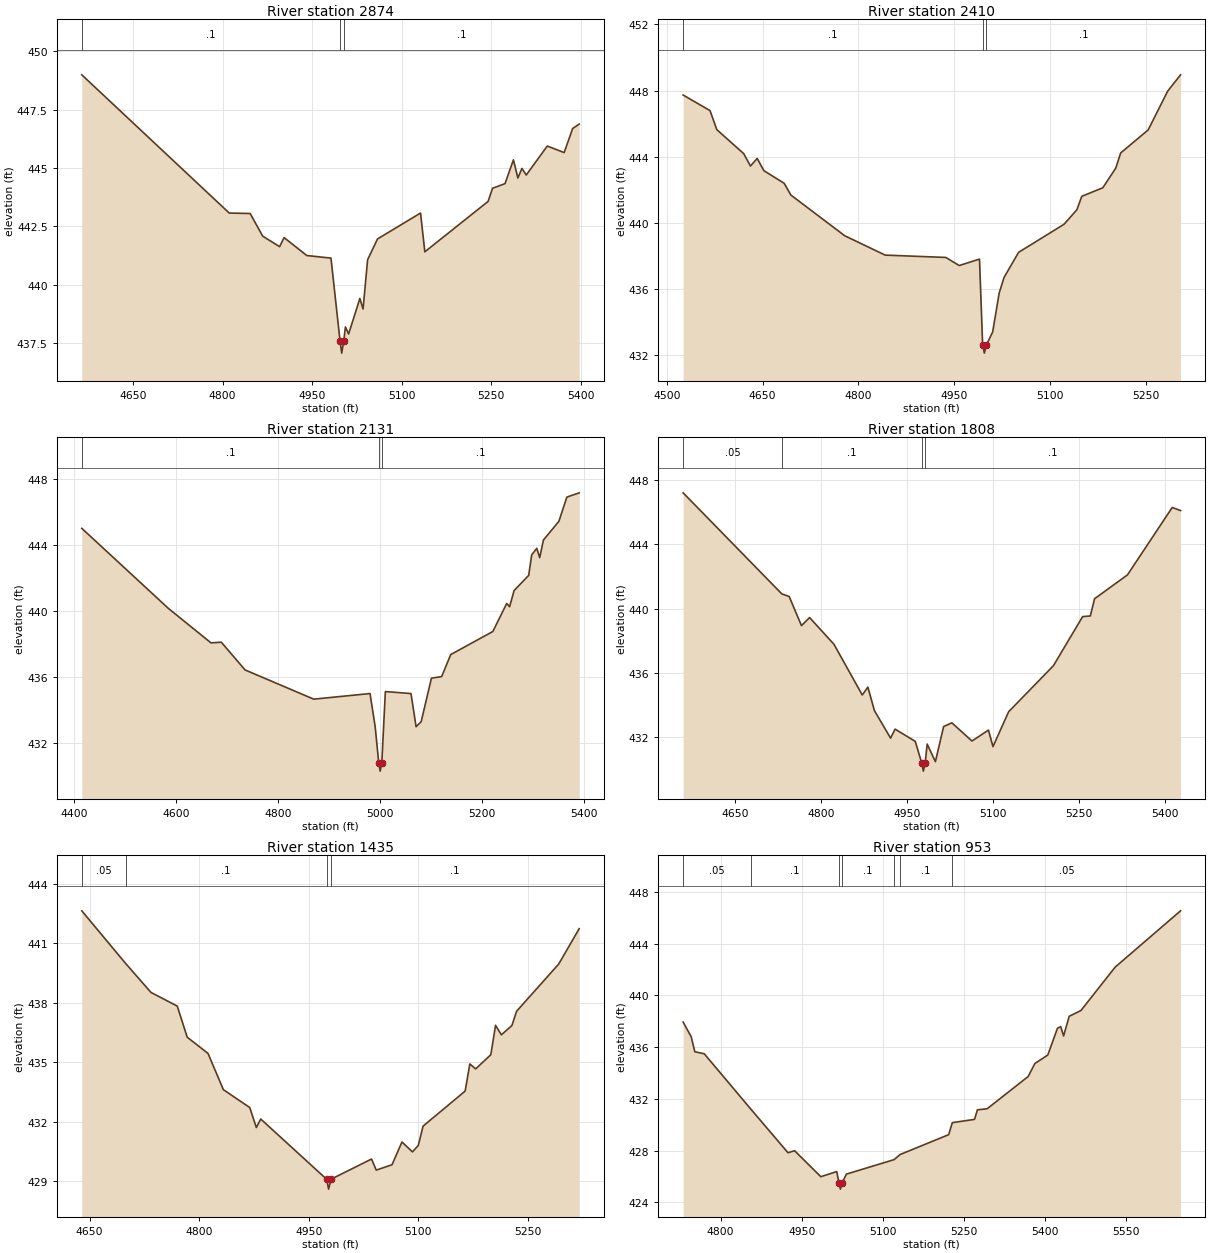
Type RM Length L Ch R = 1 ,2874    ,464,464,464
BEGIN DESCRIPTION:
UNT 094 IN LACR 6.0
END DESCRIPTION:
XS GIS Cut Line= 4
        2193256.     13179709.81       2193533.7     13179965.84
       2193662.4     13179914.36      2193879.17     13179682.69
#Sta/Elev= 30
  4564.1  448.99  4811.2  443.07  4846.3  443.05  4867.3  442.08  4895.7  441.63
  4903.1  442.02  4941.2  441.25  4981.7  441.14    4997  437.57  4999.7  437.07
    5003  437.57  5005.9  438.19  5011.3  437.89  5030.1  439.41  5035.5  438.96
  5043.1  441.07  5059.7  441.96  5131.8  443.07    5139  441.41  5245.1  443.57
  5252.4  444.13  5273.4  444.33  5287.5  445.35  5294.9  444.57  5301.7  444.98
    5309   444.7  5344.2  445.94  5372.5  445.66  5386.7  446.69  5397.7  446.88
#Mann= 3 ,-1 , 0
  4564.1      .1       0    4997     .07       0    5003      .1       0
Bank Sta=4997,5003
XS Rating Curve= 0 ,0
Exp/Cntr=0.3,0.1

Type RM Length L Ch R = 1 ,2410    ,279,279,279
BEGIN DESCRIPTION:
UNT 094 IN LACR 5.0
END DESCRIPTION:
XS GIS Cut Line= 3
      2193087.76     13180196.87      2193537.72     13180346.86
      2193837.68     13180396.85
#Sta/Elev= 30
  4525.7  447.73  4567.8  446.79  4578.4  445.64  4620.5  444.19  4631.1  443.44
  4641.6   443.9  4652.1  443.16  4683.8   442.4  4694.3  441.69  4778.6  439.23
  4841.9  438.06  4936.8  437.92  4957.8  437.43  4989.5  437.82  4994.4  432.64
  4997.1  432.14  5000.4  432.64  5010.1  433.42  5020.3  435.77  5027.9  436.71
  5050.7  438.23  5121.7  439.92  5141.9   440.8  5149.5  441.61  5182.5  442.13
  5202.8  443.32  5210.4  444.23  5253.4  445.62  5283.9  447.96  5304.1  448.95
#Mann= 3 ,-1 , 0
  4525.7      .1       0  4994.4     .07       0  5000.4      .1       0
Bank Sta=4994.4,5000.4
XS Rating Curve= 0 ,0
Exp/Cntr=0.3,0.1

Type RM Length L Ch R = 1 ,2131    ,323,323,323
BEGIN DESCRIPTION:
Mapping XS 374082eb
END DESCRIPTION:
XS GIS Cut Line= 4
      2192906.48     13180675.03       2193295.5     13180622.35
      2193737.23     13180581.82      2193858.81     13180512.93
#Sta/Elev= 30
  4414.4  445.03  4584.6  440.17  4667.9  438.09  4688.1  438.13  4734.8  436.45
  4869.5  434.68  4979.9  435.02    4990  433.02    4997  430.82  4999.8  430.32
    5003  430.82    5010  435.14  5060.3  435.02  5070.3  433.01  5080.3  433.32
  5100.4  435.95  5120.5  436.05  5138.2  437.38  5220.9  438.78  5248.1  440.48
  5253.7  440.28  5262.6  441.26  5291.2  442.18  5297.1  443.42  5307.1  443.82
  5312.8  443.25  5320.1  444.32  5350.4  445.45  5366.1  446.92  5390.3  447.18
#Mann= 3 ,-1 , 0
  4414.4      .1       0    4997     .07       0    5003      .1       0
Bank Sta=4997,5003
XS Rating Curve= 0 ,0
Exp/Cntr=0.3,0.1

Type RM Length L Ch R = 1 ,1808    ,373,373,373
BEGIN DESCRIPTION:
UNT 094 IN LACR 4.0
END DESCRIPTION:
XS GIS Cut Line= 3
      2193254.94     13181185.69      2193485.97     13180966.82
      2193908.91     13180616.85
#Sta/Elev= 30
  4559.8  447.19  4731.9  440.91  4744.7  440.75  4766.1  438.94  4780.3  439.44
  4822.8  437.78  4872.1  434.63  4881.9  435.12  4893.3  433.66  4921.5  431.95
  4929.3  432.51  4964.5  431.75  4975.8   430.4  4978.6   429.9  4981.8   430.4
  4985.3  431.58  4999.6  430.49    5014  432.67  5028.3   432.9  5063.4  431.77
  5092.1  432.45    5100  431.42  5127.3  433.59  5205.4  436.45  5256.3   439.5
  5269.7  439.54  5277.1  440.61  5334.4  442.09  5412.5  446.28    5427  446.09
#Mann= 4 ,-1 , 0
  4559.8     .05       0  4731.9      .1       0  4975.8     .07       0
  4981.8      .1       0
Bank Sta=4975.8,4981.8
XS Rating Curve= 0 ,0
Exp/Cntr=0.3,0.1

Type RM Length L Ch R = 1 ,1435    ,482,482,482
BEGIN DESCRIPTION:
UNT 094 IN LACR 3.0
END DESCRIPTION:
XS GIS Cut Line= 3
      2193487.68     13181346.88      2193787.72     13181146.86
      2193987.75     13180896.82
#Sta/Elev= 30
  4639.4  442.64  4699.7  439.97  4734.1  438.52  4770.1  437.83  4783.7  436.26
  4812.2  435.44  4833.2  433.61  4869.3  432.71  4878.3   431.7  4884.3  432.13
  4974.5  429.09  4977.2  428.59  4980.5  429.09    5036  430.11  5042.4  429.55
    5064  429.82  5077.6  430.97    5092  430.47    5100   430.8  5106.5  431.77
  5164.1  433.54  5170.5  434.91  5178.5  434.66  5199.3  435.38  5205.7  436.86
  5213.7  436.38  5228.1  436.85  5234.5  437.57  5292.1  439.95  5320.2  441.74
#Mann= 4 ,-1 , 0
  4639.4     .05       0  4699.7      .1       0  4974.5     .07       0
  4980.5      .1       0
Bank Sta=4974.5,4980.5
XS Rating Curve= 0 ,0
Exp/Cntr=0.3,0.1

Type RM Length L Ch R = 1 ,953     ,153,153,153
BEGIN DESCRIPTION:
UNT 094 IN LACR 2.0
END DESCRIPTION:
XS GIS Cut Line= 3
      2193737.68     13181646.87      2193987.72     13181546.85
      2194587.72     13181296.85
#Sta/Elev= 30
  4730.7  437.94  4745.6  436.81  4752.3  435.65  4769.8  435.49  4855.5  431.23
  4924.6  427.84  4936.7     428  4985.2  425.99  5014.6  426.39  5018.7  425.53
  5021.4  425.03  5024.7  425.53  5032.5  426.19  5120.6  427.31  5131.5   427.7
  5221.5  429.24  5228.2  430.17  5269.2  430.42  5274.6  431.16  5292.5  431.24
  5368.3  433.73  5380.8  434.74  5404.6  435.39  5422.5  437.46  5428.5  437.59
  5433.9  436.87  5444.2  438.39  5465.8  438.83  5529.2  442.19    5650  446.54
#Mann= 7 ,-1 , 0
  4730.7     .05       0  4855.5      .1       0  5018.7     .07       0
  5024.7      .1       0  5120.6     .05       0  5131.5      .1       0
  5228.2     .05       0
Bank Sta=5018.7,5024.7
XS Rating Curve= 0 ,0
Exp/Cntr=0.3,0.1

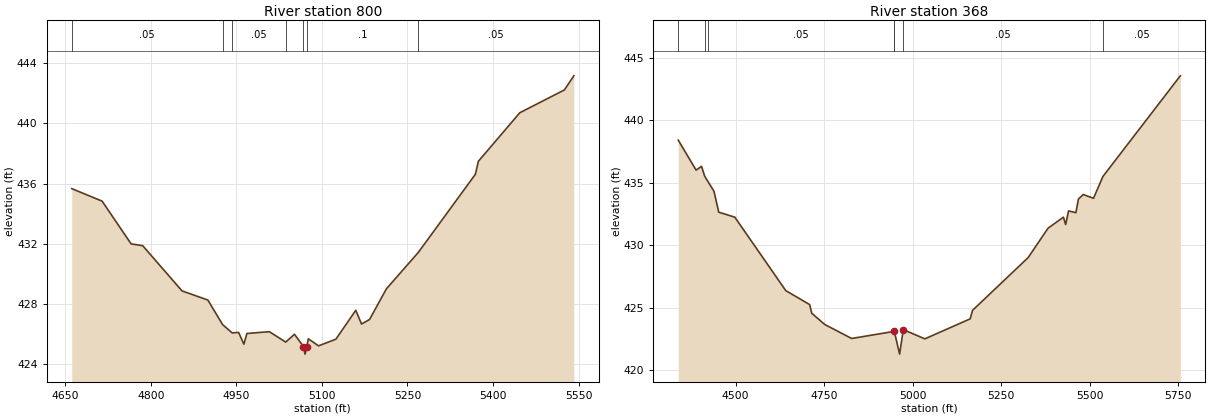
Type RM Length L Ch R = 1 ,800     ,432,432,432
BEGIN DESCRIPTION:
Mapping XS 7ec7e634
END DESCRIPTION:
XS GIS Cut Line= 3
      2193735.48     13181759.09      2193928.15     13181722.64
      2194563.15      13181467.6
#Sta/Elev= 30
  4661.4  435.66  4714.6  434.83  4765.5  431.99  4785.8  431.87  4854.7  428.87
  4900.1  428.26  4925.9  426.63  4942.7  426.08    4954  426.11  4963.2  425.33
  4968.5  426.04  5007.9  426.16  5036.6  425.47  5051.9  425.99  5067.7  425.17
  5070.5  424.67  5073.7  425.17  5076.1  425.69  5094.1  425.22  5124.5  425.66
  5159.4  427.58  5169.5  426.67  5183.6  426.97  5213.2  429.01  5269.2  431.43
  5369.1  436.61  5374.5  437.48  5447.1   440.7  5525.1  442.21  5541.8  443.15
#Mann= 7 ,-1 , 0
  4661.4     .05       0  4925.9      .1       0  4942.7     .05       0
  5036.6      .1       0  5067.7     .04       0  5073.7      .1       0
  5269.2     .05       0
Bank Sta=5067.7,5073.7
XS Rating Curve= 0 ,0
Exp/Cntr=0.3,0.1

Type RM Length L Ch R = 1 ,368     ,0,0,0
BEGIN DESCRIPTION:
UNT 094 IN LACR 1.0
END DESCRIPTION:
XS GIS Cut Line= 4
      2193631.83     13181834.05       2194012.8     13182069.13
      2194369.43     13182008.34      2194745.64       13181531.
#Sta/Elev= 30
  4338.1  438.41  4388.6  436.01  4403.8  436.32  4412.7  435.53  4421.3  435.13
    4439  434.32  4452.4  432.65  4497.8  432.25  4641.6  426.38  4709.1  425.26
    4715  424.57  4751.6  423.67  4827.6  422.55    4948  423.12    4963   421.3
  4973.3  423.26  5034.2  422.52  5162.2  424.12  5168.8   424.8  5325.9  429.02
    5382  431.37  5425.3  432.25  5431.7  431.66  5439.8  432.75  5460.6  432.61
  5467.7   433.7  5481.4  434.06  5510.3  433.76    5537  435.51  5755.3  443.55
#Mann= 7 ,-1 , 0
  4338.1      .1       0  4412.7     .05       0  4421.3     .05       0
    4948     .12       0    4948    .035       0  4973.3     .05       0
    5537     .05       0
Bank Sta=4948,4973.3
XS Rating Curve= 0 ,0
Exp/Cntr=0.3,0.1

Chan Stop Cuts=-1
Use User Specified Reach Order=0
Composite Channel Slope=5