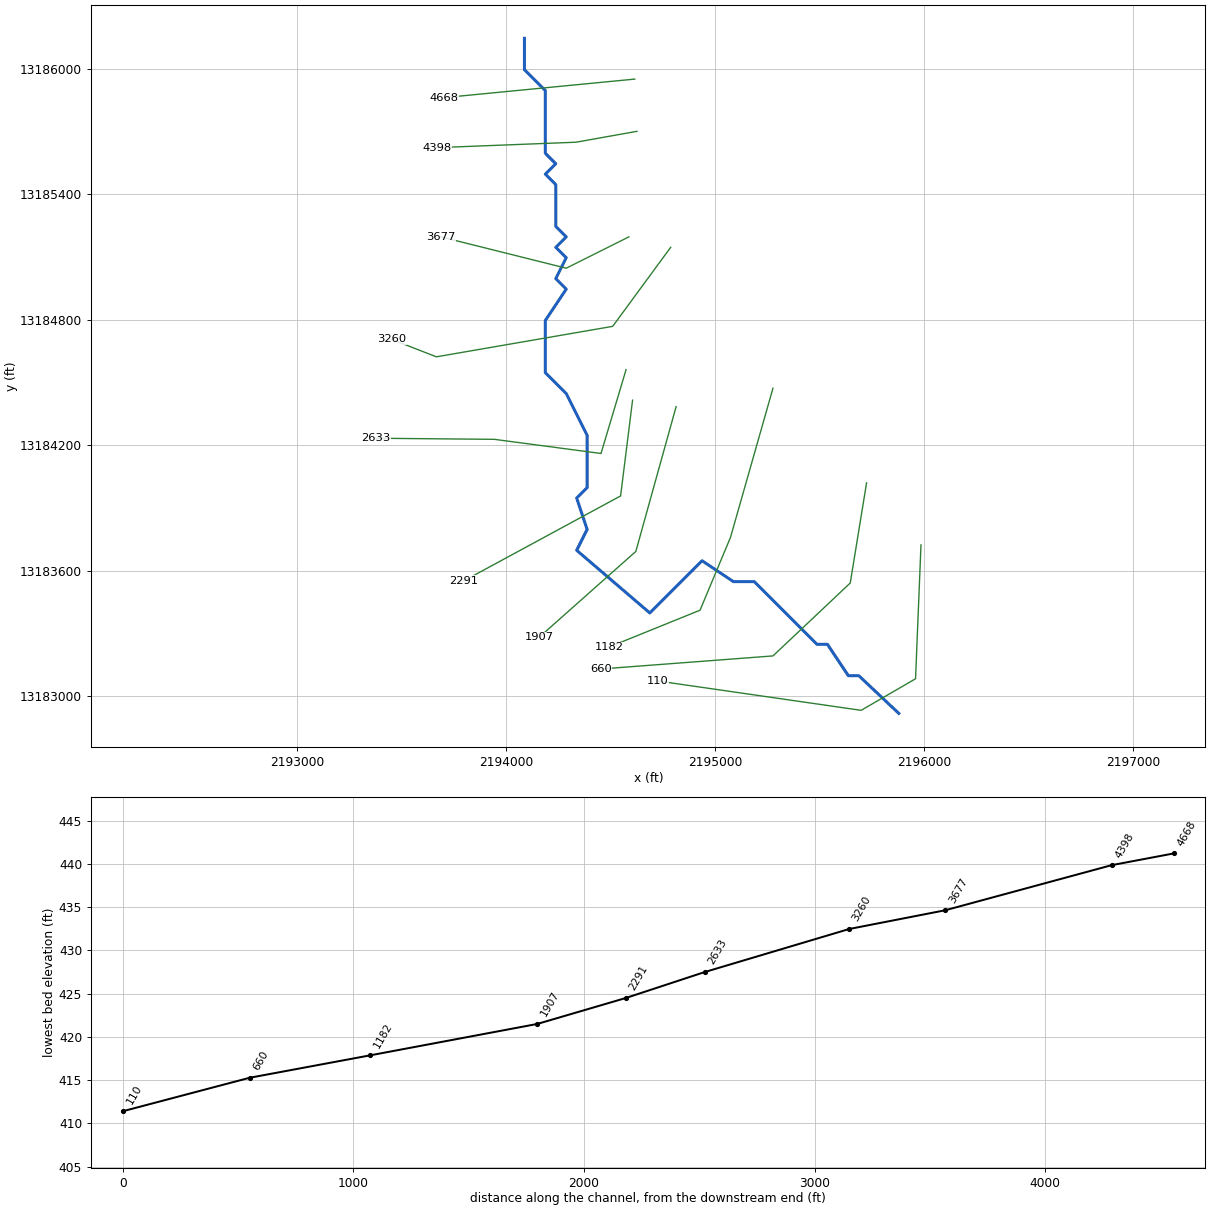
--- UNT 099 IN LACR.prj (project) ---

Proj Title=UNT 099 IN LACR Base Level Engineering
Current Plan=p01
Default Exp/Contr=0.3,0.1
English Units
Geom File=g01
Flow File=f01
Plan File=p01
BEGIN DESCRIPTION:
UNT 099 IN LACR
END DESCRIPTION:

--- UNT 099 IN LACR.p01 (plan) ---

Plan Title=Multiple Run
Short Identifier=Multiple
Geom File=g01
Flow File=f01
Subcritical Flow
K Sum by GR= 0
Std Step Tol= 0.01
Critical Tol= 0.01
Num of Std Step Trials= 20
Max Error Tol= 0.3
Flow Tol Ratio= 0.001
Split Flow NTrial= 30
Split Flow Tol= 0.02
Split Flow Ratio= 0.02
Log Output Level= 0
Friction Slope Method= 1
Unsteady Friction Slope Method= 2
Unsteady Bridges Friction Slope Method= 1
Parabolic Critical Depth
Global Vel Dist=  1 , 1 , 1
Global Log Level= 0
CheckData=True
Encroach Param= -1, 0, 0, 0
BEGIN DESCRIPTION:
Multiple Run
END DESCRIPTION:

--- UNT 099 IN LACR.f01 (steady flow) ---

Flow Title=Multiple
Number of Profiles=7
Profile Names=10-year,25-year,50-year,1pct_min,100-year,1pct_plu,500-year
River Rch & RM= UNT 099 IN LACR,Reach-1,4668
     148     202     247     222     300     405     450
Boundary for River Rch & Prof#=UNT 099 IN LACR,Reach-1,1
Up Type=0
Dn Type=3
Dn Slope=0.005
Boundary for River Rch & Prof#=UNT 099 IN LACR,Reach-1,2
Up Type=0
Dn Type=3
Dn Slope=0.005
Boundary for River Rch & Prof#=UNT 099 IN LACR,Reach-1,3
Up Type=0
Dn Type=3
Dn Slope=0.005
Boundary for River Rch & Prof#=UNT 099 IN LACR,Reach-1,4
Up Type=0
Dn Type=3
Dn Slope=0.005
Boundary for River Rch & Prof#=UNT 099 IN LACR,Reach-1,5
Up Type=0
Dn Type=3
Dn Slope=0.005
Boundary for River Rch & Prof#=UNT 099 IN LACR,Reach-1,6
Up Type=0
Dn Type=3
Dn Slope=0.005
Boundary for River Rch & Prof#=UNT 099 IN LACR,Reach-1,7
Up Type=0
Dn Type=3
Dn Slope=0.005

--- UNT 099 IN LACR.g01 (geometry) ---

Geom Title=Existing Conditions

River Reach=UNT 099 IN LACR,Reach-1
Reach XY= 30
      2194087.72     13186146.85      2194087.72     13185996.85
      2194187.72     13185896.85      2194187.72     13185596.86
      2194237.72     13185546.85      2194187.72     13185496.85
      2194237.72     13185446.86      2194237.72     13185246.86
      2194287.72     13185196.85      2194237.72     13185146.85
      2194287.72     13185096.86      2194237.72     13184996.85
      2194287.72     13184946.86      2194187.72     13184796.85
      2194187.72     13184546.85      2194287.72     13184446.86
      2194387.72     13184246.85      2194387.72     13183996.85
      2194337.72     13183946.86      2194387.72     13183796.86
      2194337.72     13183696.85      2194687.72     13183396.85
      2194937.72     13183646.85      2195087.72     13183546.85
      2195187.72     13183546.85      2195487.72     13183246.85
      2195537.72     13183246.85      2195637.72     13183096.85
      2195687.72     13183096.85      2195879.14     13182916.42

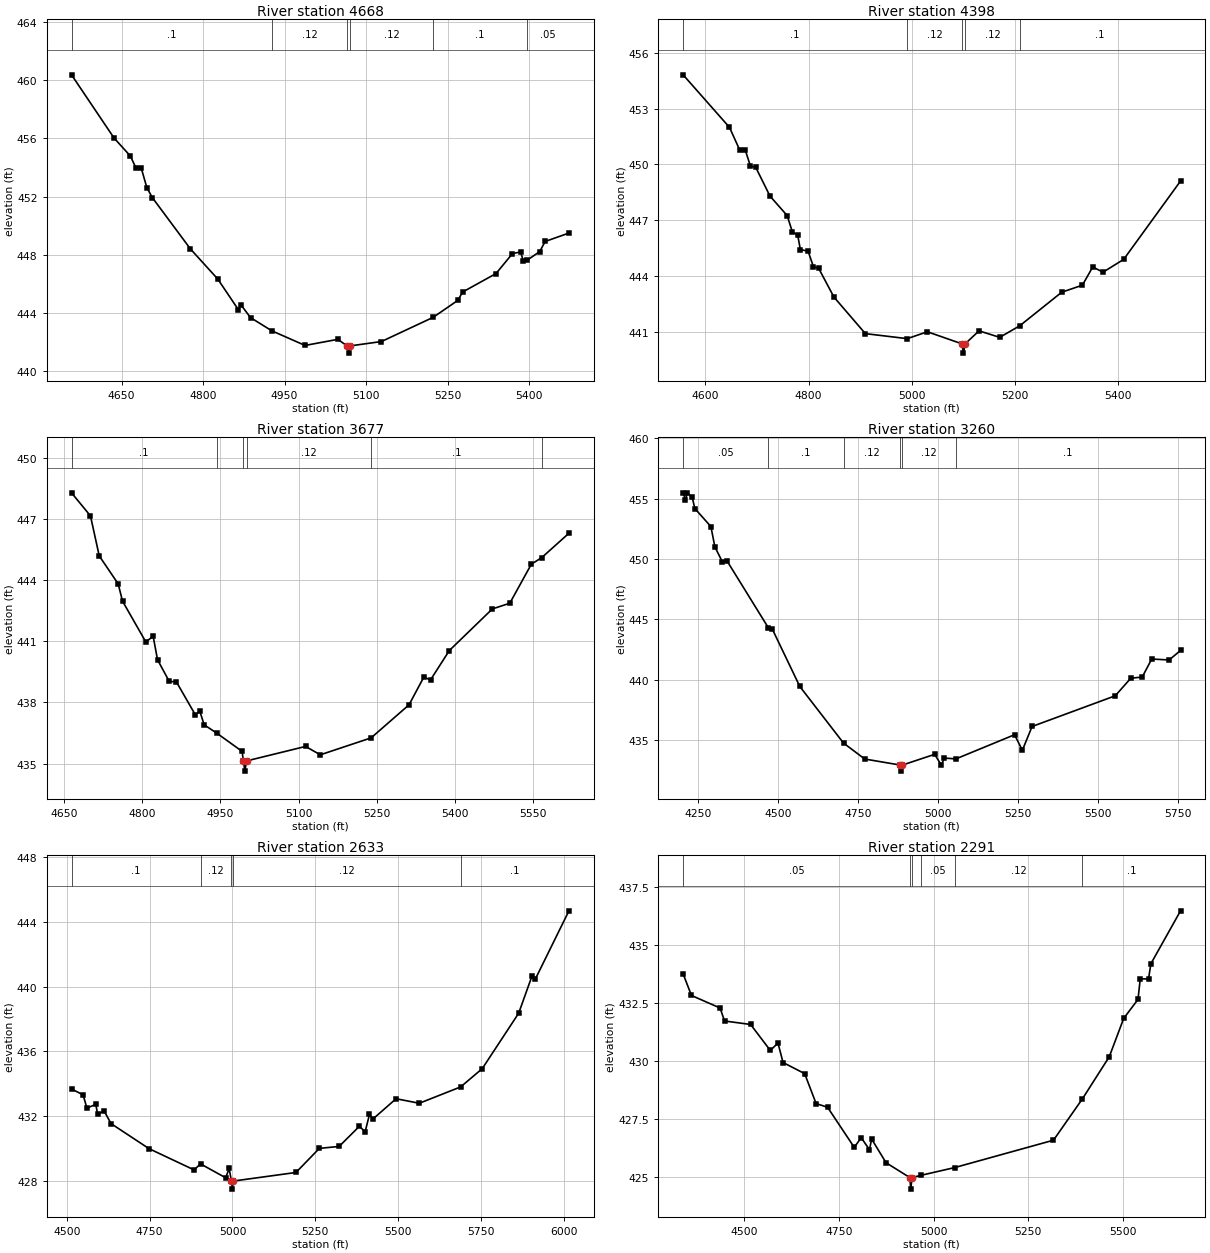
Type RM Length L Ch R = 1,4668,270,270,270
BEGIN DESCRIPTION:
UNT 099 IN LACR 6.0
END DESCRIPTION:
XS GIS Cut Line= 2
      2194615.65     13185951.81      2193704.14     13185863.26
#Sta/Elev= 30
  4557.8  460.39  4636.1  456.03  4666.2  454.79  4676.3  453.97  4686.3  453.94
  4696.4  452.62  4706.4  451.93  4776.8  448.38  4827.0  446.31  4864.9  444.20
  4869.9  444.52  4887.3  443.65  4926.5  442.74  4987.7  441.73  5048.0  442.15
  5065.1  441.70  5067.9  441.20  5071.1  441.70  5128.4  442.00  5223.7  443.67
  5269.1  444.84  5277.7  445.41  5339.4  446.69  5369.5  448.06  5384.7  448.18
  5389.7  447.53  5396.6  447.61  5419.8  448.20  5429.8  448.90  5473.6  449.48
#Mann=6,-1,0
  4557.8     0.1       0  4926.5    0.12       0  5065.1    0.07       0
  5071.1    0.12       0  5223.7     0.1       0  5396.6    0.05       0
Bank Sta=5065.1,5071.1
Exp/Cntr=0.3,0.1

Type RM Length L Ch R = 1,4398,721,721,721
BEGIN DESCRIPTION:
UNT 099 IN LACR 5.0
END DESCRIPTION:
XS GIS Cut Line= 3
      2194626.09     13185701.81      2194334.40     13185649.72
      2193667.72     13185623.68
#Sta/Elev= 30
  4556.9  454.83  4646.7  452.00  4666.2  450.80  4677.1  450.79  4687.3  449.91
  4697.5  449.85  4725.1  448.30  4758.4  447.25  4768.6  446.36  4778.7  446.21
  4784.0  445.42  4799.0  445.33  4809.2  444.50  4819.4  444.41  4849.0  442.86
  4909.9  440.89  4991.0  440.62  5030.0  440.99  5097.1  440.34  5099.8  439.84
  5103.1  440.34  5130.1  441.04  5170.1  440.69  5208.8  441.31  5290.2  443.12
  5330.3  443.50  5350.3  444.48  5370.3  444.20  5410.3  444.89  5520.4  449.11
#Mann=5,-1,0
  4556.9     0.1       0  4991.0    0.12       0  5097.1    0.07       0
  5103.1    0.12       0  5208.8     0.1       0
Bank Sta=5097.1,5103.1
Exp/Cntr=0.3,0.1

Type RM Length L Ch R = 1,3677,417,417,417
BEGIN DESCRIPTION:
UNT 099 IN LACR 4.0
END DESCRIPTION:
XS GIS Cut Line= 3
      2194587.71     13185196.85      2194287.72     13185046.85
      2193687.69     13185196.86
#Sta/Elev= 30
  4664.6  448.27  4700.9  447.14  4717.7  445.18  4754.0  443.81  4762.4  442.96
  4807.1  440.96  4821.1  441.24  4829.5  440.09  4851.9  439.03  4865.8  439.00
  4902.2  437.38  4910.6  437.57  4918.9  436.90  4943.2  436.49  4991.6  435.60
  4994.2  435.13  4997.0  434.63  5000.2  435.13  5113.4  435.84  5141.7  435.43
  5239.1  436.26  5311.8  437.88  5340.2  439.24  5353.0  439.10  5389.1  440.54
  5471.6  442.58  5505.1  442.86  5546.3  444.77  5566.5  445.10  5618.5  446.29
#Mann=6,-1,0
  4664.6     0.1       0  4943.2    0.12       0  4994.2    0.07       0
  5000.2    0.12       0  5239.1     0.1       0  5566.5    0.05       0
Bank Sta=4994.2,5000.2
Exp/Cntr=0.3,0.1

Type RM Length L Ch R = 1,3260,627,627,627
BEGIN DESCRIPTION:
UNT 099 IN LACR 3.0
END DESCRIPTION:
XS GIS Cut Line= 4
      2194787.73     13185146.87      2194510.04     13184768.55
      2193666.29     13184622.71      2193452.74     13184706.05
#Sta/Elev= 30
  4203.6  455.47  4210.9  454.89  4217.1  455.46  4231.8  455.11  4240.3  454.17
  4290.4  452.68  4302.9  451.00  4325.9  449.78  4340.1  449.87  4470.3  444.30
  4482.6  444.19  4568.3  439.46  4704.9  434.78  4771.3  433.46  4882.8  432.96
  4885.6  432.46  4888.8  432.96  4989.9  433.85  5010.5  432.96  5020.3  433.54
  5056.1  433.47  5239.6  435.47  5263.9  434.18  5294.3  436.15  5554.4  438.69
  5602.8  440.14  5638.6  440.24  5668.4  441.73  5722.8  441.65  5758.4  442.44
#Mann=6,-1,0
  4203.6    0.05       0  4470.3     0.1       0  4704.9    0.12       0
  4882.8    0.07       0  4888.8    0.12       0  5056.1     0.1       0
Bank Sta=4882.8,4888.8
Exp/Cntr=0.3,0.1

Type RM Length L Ch R = 1,2633,342,342,342
BEGIN DESCRIPTION:
Mapping XS cedbe563
END DESCRIPTION:
XS GIS Cut Line= 4
      2194573.98     13184561.18      2194454.19     13184160.14
      2193943.77     13184227.85      2193376.03     13184233.06
#Sta/Elev= 30
  4514.4  433.67  4549.4  433.31  4560.7  432.49  4587.7  432.72  4592.9  432.13
  4612.8  432.31  4633.7  431.53  4748.5  429.98  4884.2  428.67  4903.7  429.04
  4979.8  428.18  4989.9  428.76  4997.0  427.98  4999.7  427.48  5003.0  427.98
  5191.7  428.51  5262.3  430.00  5322.0  430.12  5383.3  431.37  5400.4  431.02
  5413.6  432.10  5423.7  431.81  5493.9  433.07  5563.9  432.79  5688.7  433.80
  5753.9  434.93  5863.9  438.36  5903.9  440.65  5913.9  440.46  6015.6  444.69
#Mann=5,-1,0
  4514.4     0.1       0  4903.7    0.12       0  4997.0    0.07       0
  5003.0    0.12       0  5688.7     0.1       0
Bank Sta=4997,5003
Exp/Cntr=0.3,0.1

Type RM Length L Ch R = 1,2291,384,384,384
BEGIN DESCRIPTION:
UNT 099 IN LACR 2.0
END DESCRIPTION:
XS GIS Cut Line= 3
      2194605.23     13184415.39      2194547.94     13183957.02
      2193798.91     13183551.29
#Sta/Elev= 30
  4338.6  433.76  4360.6  432.83  4436.2  432.29  4448.0  431.73  4516.8  431.58
  4568.9  430.46  4589.1  430.78  4602.5  429.94  4659.6  429.46  4689.8  428.17
  4720.1  428.01  4790.6  426.28  4808.9  426.70  4830.8  426.18  4836.5  426.64
  4874.5  425.62  4937.2  424.98  4939.9  424.48  4943.2  424.98  4968.1  425.08
  5056.0  425.41  5316.8  426.59  5393.1  428.37  5464.2  430.19  5502.2  431.84
  5540.0  432.66  5546.0  433.55  5567.8  433.54  5574.1  434.20  5652.4  436.48
#Mann=6,-1,0
  4338.6    0.05       0  4937.2    0.04       0  4943.2    0.05       0
  4968.1    0.05       0  5056.0    0.12       0  5393.1     0.1       0
Bank Sta=4937.2,4943.2
Exp/Cntr=0.3,0.1

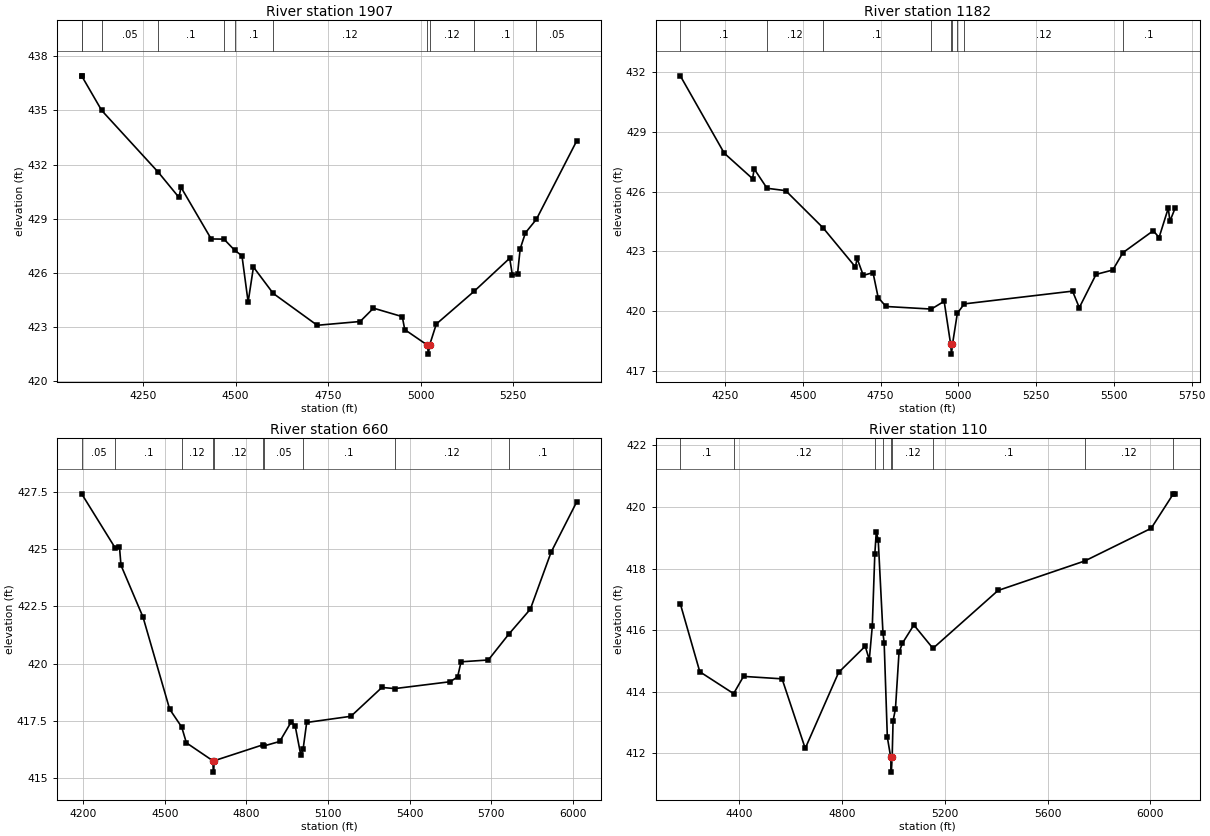
Type RM Length L Ch R = 1,1907,725,725,725
BEGIN DESCRIPTION:
Mapping XS 1247142e
END DESCRIPTION:
XS GIS Cut Line= 3
      2194813.56     13184384.10      2194620.85     13183691.39
      2194158.38     13183280.88
#Sta/Elev= 30
  4084.3  436.92  4084.5  436.91  4138.4  435.00  4291.4  431.57  4347.4  430.17
  4352.6  430.74  4434.3  427.87  4468.8  427.86  4498.3  427.23  4517.4  426.94
  4534.1  424.37  4548.5  426.31  4601.8  424.85  4720.8  423.08  4836.8  423.29
  4872.8  424.03  4950.6  423.56  4957.3  422.84  5018.4  421.98  5021.2  421.48
  5024.4  421.98  5042.6  423.15  5145.0  424.97  5240.8  426.80  5248.3  425.85
  5262.1  425.94  5269.2  427.32  5283.4  428.21  5313.0  428.96  5421.7  433.30
#Mann=11,-1,0
  4084.3    0.05       0  4084.5     0.1       0  4138.4    0.05       0
  4291.4     0.1       0  4468.8    0.05       0  4498.3     0.1       0
  4601.8    0.12       0  5018.4    0.07       0  5024.4    0.12       0
  5145.0     0.1       0  5313.0    0.05       0
Bank Sta=5018.4,5024.4
Exp/Cntr=0.3,0.1

Type RM Length L Ch R = 1,1182,522,522,522
BEGIN DESCRIPTION:
Mapping XS ffd22674
END DESCRIPTION:
XS GIS Cut Line= 4
      2195277.10     13184472.62      2195073.98     13183759.10
      2194928.15     13183410.14      2194491.72     13183233.49
#Sta/Elev= 30
  4106.4  431.81  4247.6  427.93  4338.7  426.65  4343.9  427.14  4385.2  426.17
  4445.1  426.05  4565.0  424.19  4669.4  422.22  4674.6  422.65  4694.6  421.80
  4725.8  421.94  4742.4  420.69  4767.4  420.24  4913.2  420.11  4954.5  420.50
  4975.3  418.35  4978.0  417.85  4981.3  418.35  4996.9  419.90  5019.1  420.37
  5367.2  421.01  5388.8  420.18  5442.7  421.85  5496.6  422.07  5529.1  422.94
  5626.6  424.04  5645.3  423.70  5674.8  425.17  5680.2  424.52  5697.3  425.19
#Mann=9,-1,0
  4106.4     0.1       0  4385.2    0.12       0  4565.0     0.1       0
  4913.2    0.05       0  4975.3    0.07       0  4981.3    0.05       0
  4996.9     0.1       0  5019.1    0.12       0  5529.1     0.1       0
Bank Sta=4975.3,4981.3
Exp/Cntr=0.3,0.1

Type RM Length L Ch R = 1,660,550,550,550
BEGIN DESCRIPTION:
Mapping XS cf12e30a
END DESCRIPTION:
XS GIS Cut Line= 4
      2195725.02     13184019.50      2195646.90     13183540.35
      2195277.10     13183191.39      2194454.20     13183128.89
#Sta/Elev= 30
  4194.3  427.42  4318.3  425.04  4333.3  425.10  4338.8  424.30  4419.9  422.03
  4517.7  418.01  4562.0  417.23  4579.2  416.54  4676.0  415.76  4678.8  415.26
  4682.0  415.76  4859.6  416.45  4863.1  416.40  4922.3  416.60  4964.8  417.46
  4978.9  417.29  4999.9  415.99  5008.4  416.28  5021.4  417.43  5184.0  417.70
  5297.9  418.96  5345.2  418.91  5548.6  419.21  5576.0  419.42  5588.8  420.08
  5689.0  420.16  5763.6  421.28  5843.4  422.38  5919.7  424.87  6013.5  427.06
#Mann=10,-1,0
  4194.3    0.05       0  4318.3     0.1       0  4562.0    0.12       0
  4676.0    0.04       0  4682.0    0.12       0  4859.6     0.1       0
  4863.1    0.05       0  5008.4     0.1       0  5345.2    0.12       0
  5763.6     0.1       0
Bank Sta=4676,4682
Exp/Cntr=0.3,0.1

Type RM Length L Ch R = 1,110,0,0,0
BEGIN DESCRIPTION:
UNT 099 IN LACR 1.0
END DESCRIPTION:
XS GIS Cut Line= 4
      2195985.44     13183722.67      2195959.40     13183082.02
      2195698.98     13182930.97      2194725.01     13183071.60
#Sta/Elev= 30
  4170.9  416.86  4246.8  414.65  4378.4  413.94  4416.9  414.50  4567.0  414.42
  4657.1  412.16  4787.2  414.63  4890.6  415.48  4906.4  415.04  4918.1  416.13
  4927.9  418.47  4933.7  419.20  4941.2  418.93  4959.7  415.90  4964.3  415.59
  4976.7  412.52  4989.5  411.89  4992.2  411.39  4995.5  411.89  4999.0  413.06
  5008.2  413.44  5022.1  415.28  5035.5  415.58  5079.9  416.17  5154.2  415.41
  5407.4  417.29  5745.4  418.25  6003.5  419.31  6089.8  420.43  6097.2  420.41
#Mann=9,-1,0
  4170.9     0.1       0  4378.4    0.12       0  4927.9    0.05       0
  4959.7    0.12       0  4989.5    0.07       0  4995.5    0.12       0
  5154.2     0.1       0  5745.4    0.12       0  6089.8     0.1       0
Bank Sta=4989.5,4995.5
Exp/Cntr=0.3,0.1

Chan Stop Cuts=-1