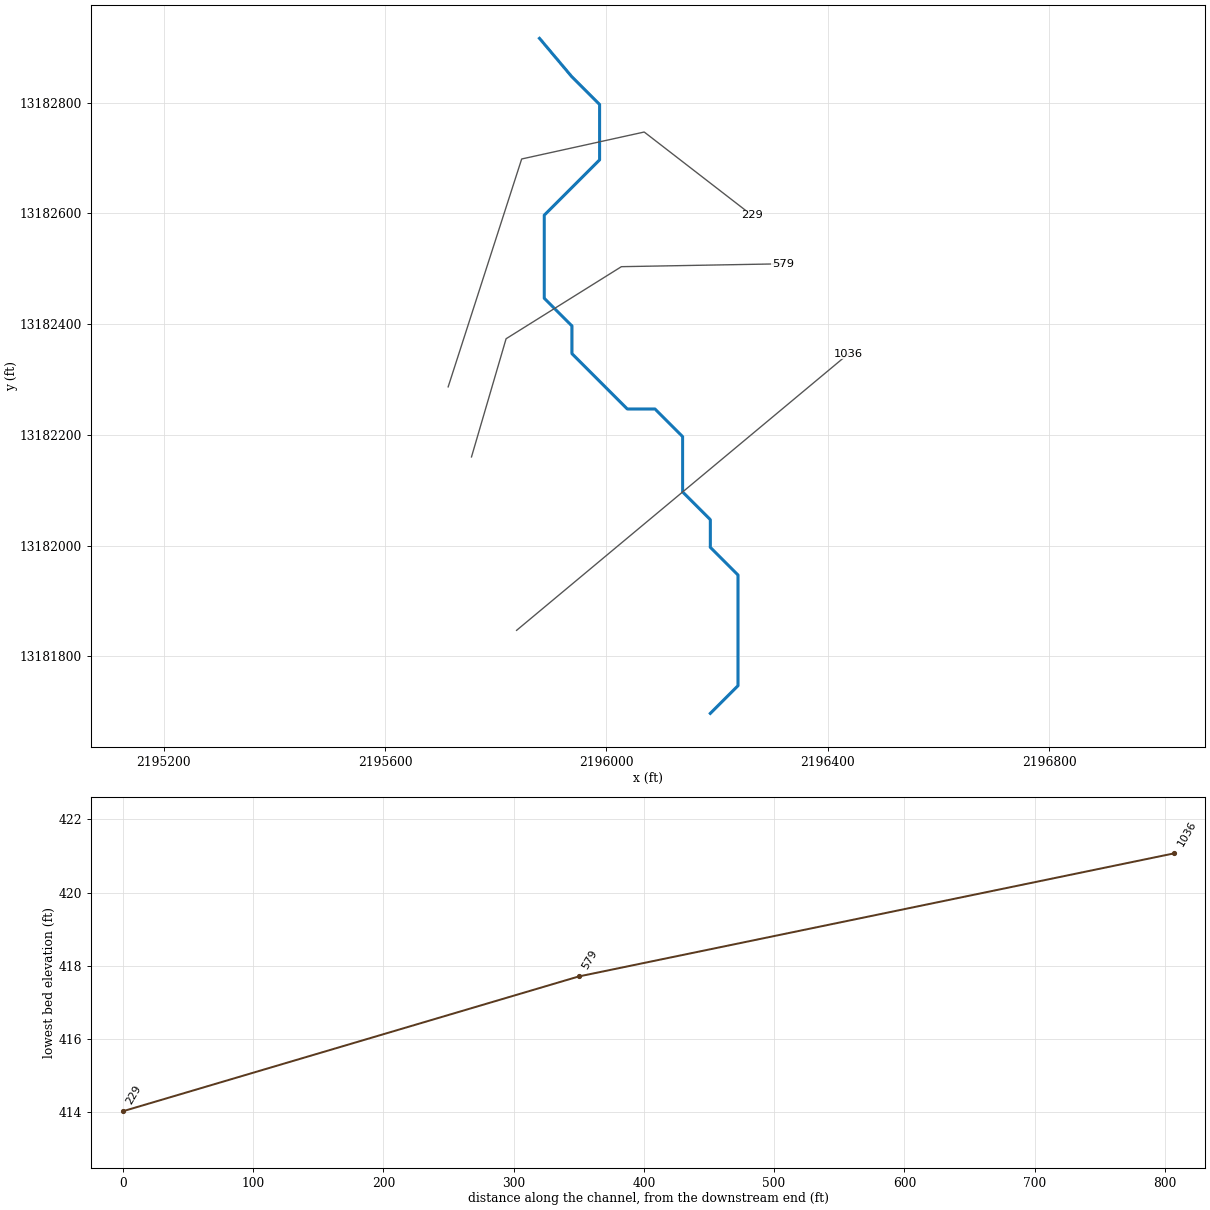
--- UNT 100 IN LACR.prj (project) ---

Proj Title=UNT 100 IN LACR Base Level Engineering
Current Plan=p01
Default Exp/Contr=0.3,0.1
English Units
Geom File=g01
Flow File=f01
Plan File=p01
Y Axis Title=Elevation
X Axis Title(PF)=Main Channel Distance
X Axis Title(XS)=Station
BEGIN DESCRIPTION:
UNT 100 IN LACR
END DESCRIPTION:
DSS Export Rating Curves= 0
DSS Export Rating Curve Sorted= 0
DSS Export Volume Flow Curves= 0
DXF OffsetX= 0
DXF OffsetY= 0
DXF ScaleX= 1
DXF ScaleY= 10

--- UNT 100 IN LACR.p01 (plan) ---

Plan Title=Multiple Run
Short Identifier=Multiple
Geom File=g01
Flow File=f01
Subcritical Flow
K Sum by GR= 0
Std Step Tol= 0.01
Critical Tol= 0.01
Num of Std Step Trials= 20
Max Error Tol= 0.3
Flow Tol Ratio= 0.001
Split Flow NTrial= 30
Split Flow Tol= 0.02
Split Flow Ratio= 0.02
Log Output Level= 0
Friction Slope Method= 1
Unsteady Friction Slope Method= 2
Unsteady Bridges Friction Slope Method= 1
Parabolic Critical Depth
Global Vel Dist=  1 , 1 , 1
Global Log Level= 0
CheckData=True
Encroach Param= -1, 0, 0, 0
BEGIN DESCRIPTION:
Multiple Run
END DESCRIPTION:

--- UNT 100 IN LACR.f01 (steady flow) ---

Flow Title=Multiple
Number of Profiles=7
Profile Names=10-year,25-year,50-year,1pct_min,100-year,1pct_plu,500-year
River Rch & RM= UNT 100 IN LACR,Reach-1,1036
      64      82      96      83     112     152     156
Boundary for River Rch & Prof#=UNT 100 IN LACR,Reach-1,1
Up Type=0
Dn Type=3
Dn Slope=0.005
Boundary for River Rch & Prof#=UNT 100 IN LACR,Reach-1,2
Up Type=0
Dn Type=3
Dn Slope=0.005
Boundary for River Rch & Prof#=UNT 100 IN LACR,Reach-1,3
Up Type=0
Dn Type=3
Dn Slope=0.005
Boundary for River Rch & Prof#=UNT 100 IN LACR,Reach-1,4
Up Type=0
Dn Type=3
Dn Slope=0.005
Boundary for River Rch & Prof#=UNT 100 IN LACR,Reach-1,5
Up Type=0
Dn Type=3
Dn Slope=0.005
Boundary for River Rch & Prof#=UNT 100 IN LACR,Reach-1,6
Up Type=0
Dn Type=3
Dn Slope=0.005
Boundary for River Rch & Prof#=UNT 100 IN LACR,Reach-1,7
Up Type=0
Dn Type=3
Dn Slope=0.005

--- UNT 100 IN LACR.g01 (geometry) ---

Geom Title=Existing Conditions
Program Version=4.10

River Reach=UNT 100 IN LACR ,Reach-1
Reach XY= 26
      2196187.72     13181696.85      2196237.72     13181746.85
      2196237.72     13181796.86      2196237.72     13181846.85
      2196237.72     13181896.85      2196237.72     13181946.85
      2196187.72     13181996.86      2196187.72     13182046.85
      2196137.72     13182096.85      2196137.72     13182146.86
      2196137.72     13182196.85      2196087.72     13182246.85
      2196037.72     13182246.85      2195987.72     13182296.86
      2195937.72     13182346.85      2195937.72     13182396.85
      2195887.72     13182446.85      2195887.72     13182496.85
      2195887.72     13182546.85      2195887.72     13182596.85
      2195937.72     13182646.86      2195987.72     13182696.85
      2195987.72     13182746.85      2195987.72     13182796.86
      2195937.72     13182846.85      2195879.14     13182916.42

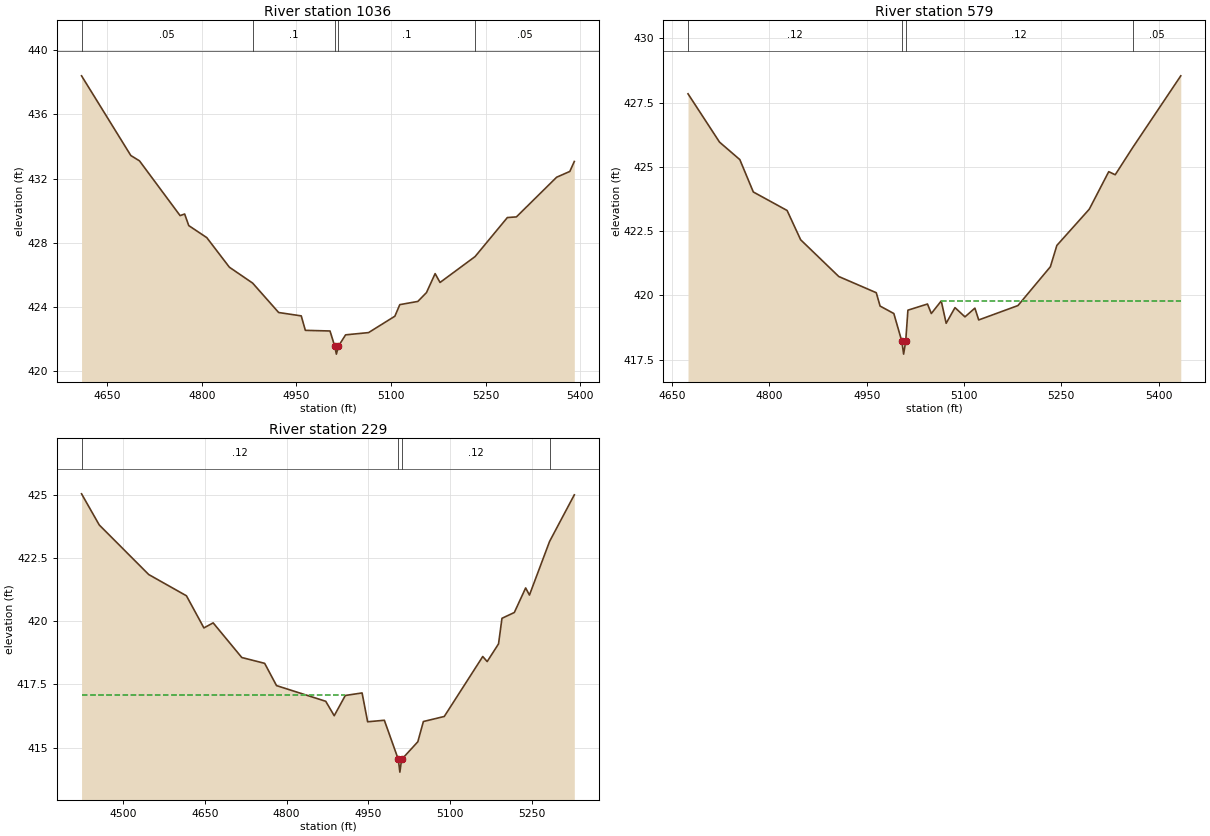
Type RM Length L Ch R = 1 ,1036    ,457,457,457
BEGIN DESCRIPTION:
UNT 100 IN LACR 2.0
END DESCRIPTION:
XS GIS Cut Line= 3
      2195837.73     13181846.86      2196137.72     13182096.85
      2196437.71     13182346.85
#Sta/Elev= 30
  4609.5  438.39  4687.6  433.43  4701.3   433.1  4765.7  429.69  4772.9  429.79
  4779.4  429.07    4808  428.32  4843.8  426.48  4880.7  425.49  4921.9  423.66
  4957.7  423.45  4964.2  422.55  5003.3  422.51  5010.7  421.57  5013.4  421.07
  5016.7  421.57    5028  422.27  5064.4  422.41  5106.1  423.43  5113.9  424.15
  5142.5  424.35  5156.2   424.9  5169.9  426.08  5177.7  425.53  5233.2  427.14
  5284.4  429.57  5298.7  429.61  5362.5  432.08  5383.4  432.44  5390.5  433.06
#Mann= 5 ,-1 , 0
  4609.5     .05       0  4880.7      .1       0  5010.7     .07       0
  5016.7      .1       0  5233.2     .05       0
Bank Sta=5010.7,5016.7
XS Rating Curve= 0 ,0
Exp/Cntr=0.3,0.1

Type RM Length L Ch R = 1 ,579     ,350,350,350
BEGIN DESCRIPTION:
Mapping XS 67cda01f
END DESCRIPTION:
XS GIS Cut Line= 4
      2195756.28     13182160.18      2195818.77     13182373.68
       2196027.1     13182503.89      2196318.82      13182509.1
#Sta/Elev= 30
  4674.4  427.84    4723  425.96  4754.3  425.28  4775.1  424.02  4827.2   423.3
  4848.1  422.16  4906.9  420.73  4964.7   420.1  4970.6  419.58  4991.8  419.29
  5004.1  418.21  5006.9  417.71  5010.1  418.21  5013.5  419.42  5043.7  419.66
  5049.6  419.29  5064.9  419.78  5072.5  418.91  5086.1  419.52  5101.5  419.16
  5116.8   419.5  5122.7  419.04  5183.2   419.6  5233.2  421.11  5243.2  421.94
  5293.2  423.35  5323.2  424.81  5333.2  424.69  5360.2  425.75  5434.3  428.54
#Mann= 4 ,-1 , 0
  4674.4     .12       0  5004.1     .07       0  5010.1     .12       0
  5360.2     .05       0
#XS Ineff= 2 , 0
       0                 5064.77       0  419.78
Permanent Ineff=
       F       F
Bank Sta=5004.1,5010.1
XS Rating Curve= 0 ,0
Exp/Cntr=0.3,0.1

Type RM Length L Ch R = 1 ,229     ,0,0,0
BEGIN DESCRIPTION:
UNT 100 IN LACR 1.0
END DESCRIPTION:
XS GIS Cut Line= 4
      2195714.11     13182286.71      2195846.93     13182698.45
      2196068.32     13182747.16      2196262.95     13182596.76
#Sta/Elev= 30
  4423.2  425.03  4455.7   423.8  4546.6  421.84  4615.9     421    4648  419.73
    4665  419.93  4717.6  418.56  4759.6  418.33  4781.4  417.45  4871.8  416.83
  4887.4  416.26  4907.8  417.06  4938.6  417.16  4948.8  416.02  4979.5  416.08
  5005.2  414.53    5008  414.03  5011.2  414.53    5041  415.23  5051.2  416.03
  5089.6  416.23  5160.3   418.6  5168.4   418.4  5189.3   419.1  5195.6  420.11
  5218.3  420.34  5239.1  421.31  5246.1  421.03  5283.1  423.15  5328.5  424.99
#Mann= 4 ,-1 , 0
  4423.2     .12       0  5005.2     .07       0  5011.2     .12       0
  5283.1     .05       0
#XS Ineff= 2 , 0
         4907.95  417.08
Permanent Ineff=
       F       F
Bank Sta=5005.2,5011.2
XS Rating Curve= 0 ,0
Exp/Cntr=0.3,0.1

Chan Stop Cuts=-1
Use User Specified Reach Order=0
Composite Channel Slope=5