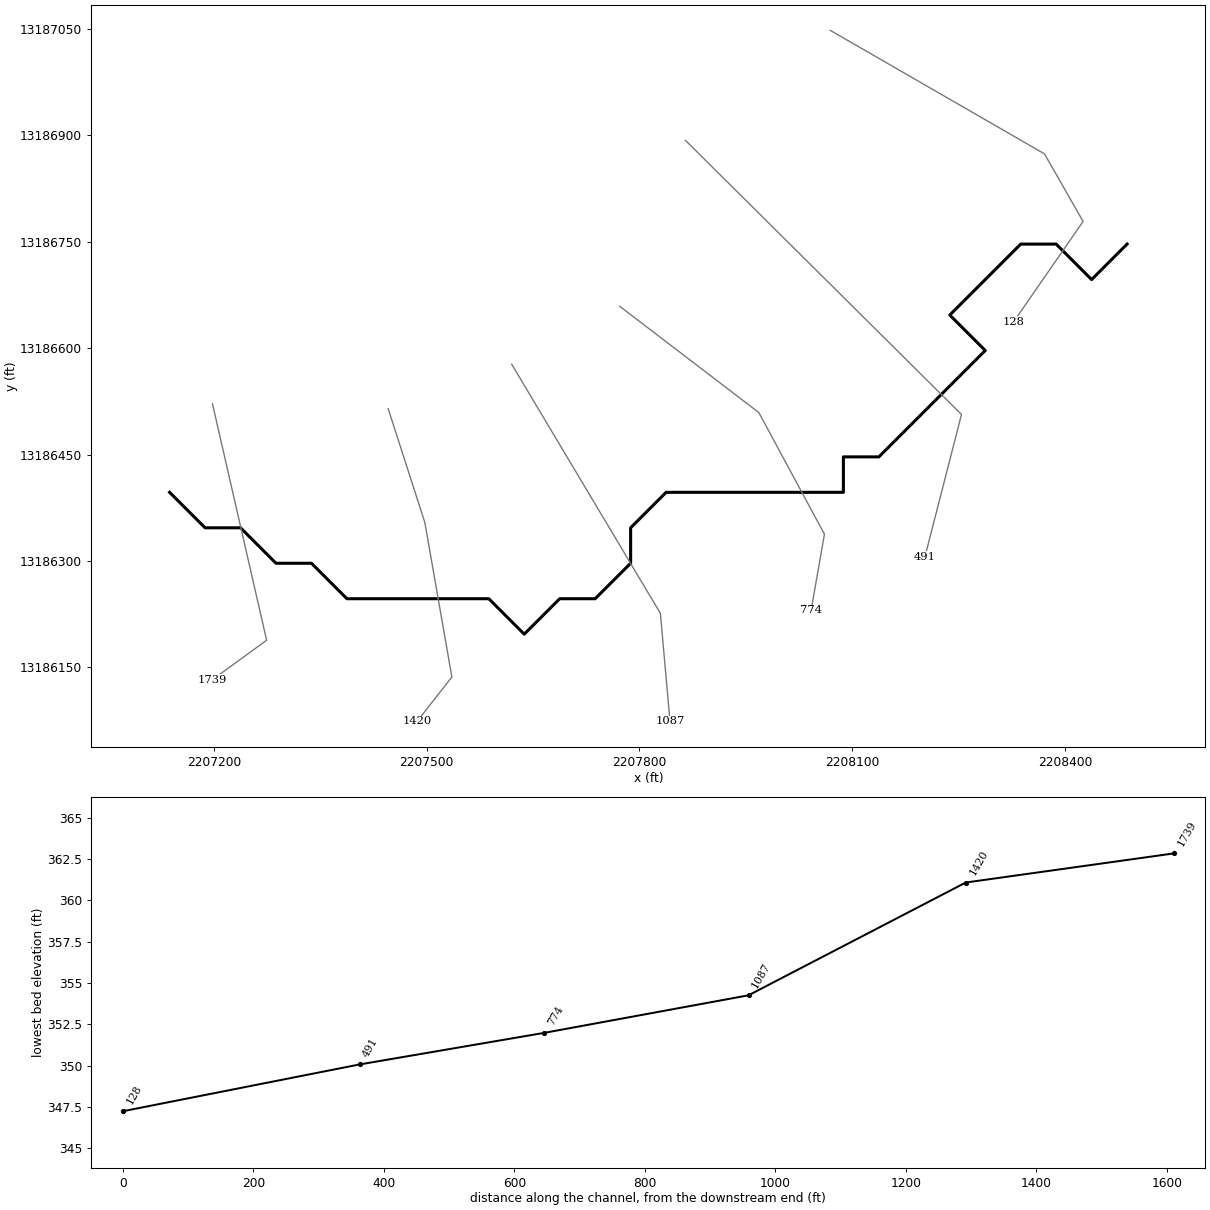
--- UNT 103 IN LACR.prj (project) ---

Proj Title=UNT 103 IN LACR Base Level Engineering
Current Plan=p01
Default Exp/Contr=0.3,0.1
English Units
Geom File=g01
Flow File=f01
Plan File=p01
Y Axis Title=Elevation
X Axis Title(PF)=Main Channel Distance
X Axis Title(XS)=Station
BEGIN DESCRIPTION:
UNT 103 IN LACR
END DESCRIPTION:
DSS Export Rating Curves= 0
DSS Export Rating Curve Sorted= 0
DSS Export Volume Flow Curves= 0
DXF OffsetX= 0
DXF OffsetY= 0
DXF ScaleX= 1
DXF ScaleY= 10

--- UNT 103 IN LACR.p01 (plan) ---

Plan Title=Multiple Run
Short Identifier=Multiple
Geom File=g01
Flow File=f01
Subcritical Flow
K Sum by GR= 0
Std Step Tol= 0.01
Critical Tol= 0.01
Num of Std Step Trials= 20
Max Error Tol= 0.3
Flow Tol Ratio= 0.001
Split Flow NTrial= 30
Split Flow Tol= 0.02
Split Flow Ratio= 0.02
Log Output Level= 0
Friction Slope Method= 1
Unsteady Friction Slope Method= 2
Unsteady Bridges Friction Slope Method= 1
Parabolic Critical Depth
Global Vel Dist=  1 , 1 , 1
Global Log Level= 0
CheckData=True
Encroach Param= -1, 0, 0, 0
BEGIN DESCRIPTION:
Multiple Run
END DESCRIPTION:

--- UNT 103 IN LACR.f01 (steady flow) ---

Flow Title=Multiple
Number of Profiles=7
Profile Names=10-year,25-year,50-year,1pct_min,100-year,1pct_plu,500-year
River Rch & RM= UNT 103 IN LACR,Reach-1,1739
      79     103     122     107     144     195     205
River Rch & RM= UNT 103 IN LACR,Reach-1,128
     889    1304    1667    1560    2109    2853    3433
Boundary for River Rch & Prof#=UNT 103 IN LACR,Reach-1,1
Up Type=0
Dn Type=3
Dn Slope=0.005
Boundary for River Rch & Prof#=UNT 103 IN LACR,Reach-1,2
Up Type=0
Dn Type=3
Dn Slope=0.005
Boundary for River Rch & Prof#=UNT 103 IN LACR,Reach-1,3
Up Type=0
Dn Type=3
Dn Slope=0.005
Boundary for River Rch & Prof#=UNT 103 IN LACR,Reach-1,4
Up Type=0
Dn Type=3
Dn Slope=0.005
Boundary for River Rch & Prof#=UNT 103 IN LACR,Reach-1,5
Up Type=0
Dn Type=3
Dn Slope=0.005
Boundary for River Rch & Prof#=UNT 103 IN LACR,Reach-1,6
Up Type=0
Dn Type=3
Dn Slope=0.005
Boundary for River Rch & Prof#=UNT 103 IN LACR,Reach-1,7
Up Type=0
Dn Type=3
Dn Slope=0.005

--- UNT 103 IN LACR.g01 (geometry) ---

Geom Title=Existing Conditions
Program Version=4.10

River Reach=UNT 103 IN LACR ,Reach-1
Reach XY= 23
      2207137.72     13186396.86      2207187.72     13186346.85
      2207237.72     13186346.85      2207287.72     13186296.85
      2207337.72     13186296.85      2207387.72     13186246.86
      2207587.72     13186246.86      2207637.72     13186196.85
      2207687.72     13186246.86      2207737.72     13186246.86
      2207787.72     13186296.85      2207787.72     13186346.85
      2207837.72     13186396.86      2208087.72     13186396.86
      2208087.72     13186446.85      2208137.72     13186446.85
      2208287.72     13186596.85      2208237.72     13186646.85
      2208287.72     13186696.85      2208337.72     13186746.86
      2208387.72     13186746.86      2208437.72     13186696.85
      2208487.72     13186746.86

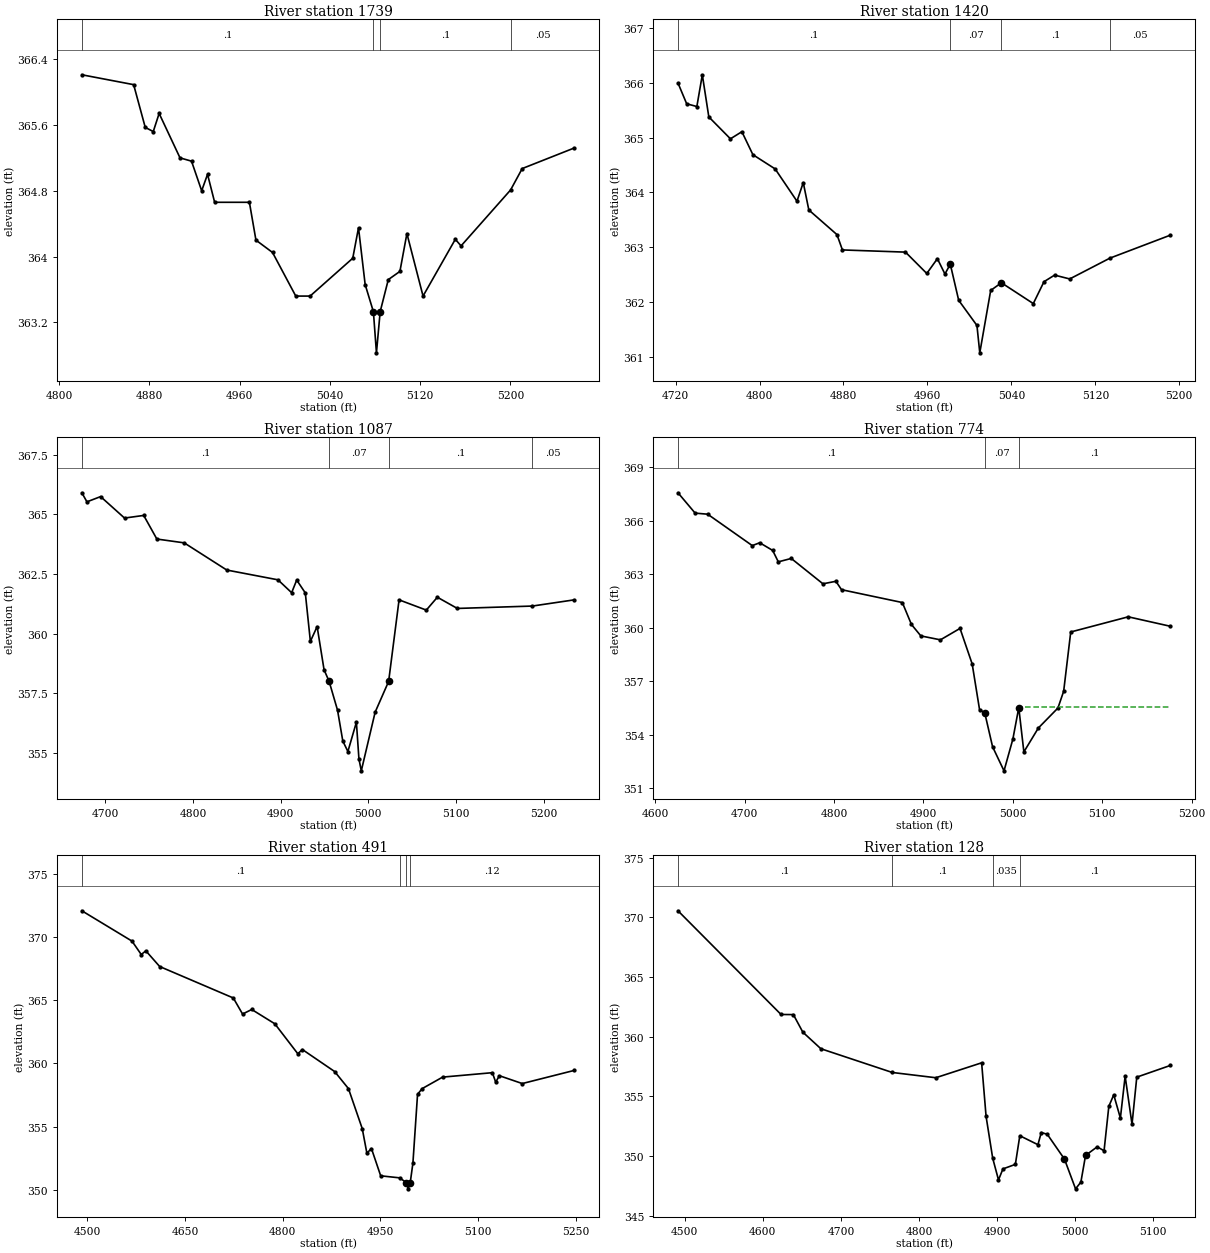
Type RM Length L Ch R = 1 ,1739    ,319,319,319
BEGIN DESCRIPTION:
UNT 103 IN LACR 2.0
END DESCRIPTION:
XS GIS Cut Line= 3
      2207198.13     13186521.62      2207274.51      13186188.3
      2207198.13     13186132.75
#Sta/Elev= 30
  4820.1  366.21    4866  366.09  4876.3  365.57  4883.4  365.52  4888.6  365.74
  4907.1   365.2  4917.3  365.16  4926.3   364.8  4931.5     365  4937.8  364.66
  4968.6  364.66  4974.4   364.2  4989.1  364.05  5009.7  363.52  5022.4  363.52
  5060.2  363.98  5065.3  364.35  5071.2  363.66  5078.5  363.33  5081.2  362.83
  5084.5  363.33  5091.7  363.72    5102  363.82  5108.2  364.28  5122.5  363.52
  5151.1  364.21  5156.2  364.13  5200.1  364.81  5210.4  365.07  5256.5  365.32
#Mann= 4 ,-1 , 0
  4820.1      .1       0  5078.5     .07       0  5084.5      .1       0
  5200.1     .05       0
Bank Sta=5078.5,5084.5
XS Rating Curve= 0 ,0
Exp/Cntr=0.3,0.1

Type RM Length L Ch R = 1 ,1420    ,333,333,333
BEGIN DESCRIPTION:
Mapping XS a12c6108
END DESCRIPTION:
XS GIS Cut Line= 4
      2207445.88      13186514.8      2207497.59     13186354.23
       2207535.7     13186136.49      2207486.73     13186073.92
#Sta/Elev= 30
  4722.3     366  4730.6  365.62  4740.3  365.57  4745.5  366.15  4751.7  365.38
  4772.3  364.98  4783.2  365.11  4793.7  364.69  4814.9  364.43  4835.7  363.84
  4841.7  364.18    4847  363.68  4873.8  363.23    4879  362.95  4939.1  362.91
  4959.4  362.52  4969.5  362.79  4976.7  362.51  4981.8  362.69  4989.8  362.03
  5007.2  361.57  5009.9  361.07  5020.3  362.21  5030.5  362.35  5060.9  361.97
  5071.1  362.37  5081.2  362.49  5095.6  362.42  5133.9   362.8  5191.5  363.22
#Mann= 4 ,-1 , 0
  4722.3      .1       0  4981.8     .07       0  5030.5      .1       0
  5133.9     .05       0
Bank Sta=4981.8,5030.5
XS Rating Curve= 0 ,0
Exp/Cntr=0.3,0.1

Type RM Length L Ch R = 1 ,1087    ,313,313,313
BEGIN DESCRIPTION:
Mapping XS 0e19bd8e
END DESCRIPTION:
XS GIS Cut Line= 3
      2207620.06     13186577.44      2207829.65     13186226.31
      2207843.25     13186073.94
#Sta/Elev= 30
  4673.1  365.91  4678.9  365.53  4694.5  365.75  4721.8  364.85  4743.7  364.96
  4758.7  363.97  4789.9  363.81  4838.5  362.67  4896.9  362.26  4912.5  361.72
  4918.3  362.25  4928.1  361.71  4933.9  359.68  4941.6   360.3  4949.5  358.49
  4955.3     358  4964.9  356.79  4970.9   355.5  4976.7  355.06  4986.4  356.29
  4989.3  354.75    4992  354.25  5007.8  356.71  5023.2     358  5035.1  361.42
  5066.2  360.99  5078.8  361.53  5101.6  361.06  5187.2  361.16    5235  361.42
#Mann= 4 ,-1 , 0
  4673.1      .1       0  4955.3     .07       0  5023.2      .1       0
  5187.2     .05       0
Bank Sta=4955.3,5023.2
XS Rating Curve= 0 ,0
Exp/Cntr=0.3,0.1

Type RM Length L Ch R = 1 ,774     ,283,283,283
BEGIN DESCRIPTION:
Mapping XS 82befad7
END DESCRIPTION:
XS GIS Cut Line= 4
      2207772.45     13186659.09      2207968.46     13186509.37
      2208060.99      13186337.9      2208042.19     13186230.43
#Sta/Elev= 30
  4625.5  367.56  4644.7  366.42  4658.7  366.36  4708.6   364.6  4716.9  364.76
  4731.4  364.33  4737.7  363.69  4752.2  363.88  4787.6  362.46  4802.1   362.6
  4808.4  362.13  4876.4  361.41  4886.6  360.18  4897.1  359.54    4919  359.32
  4940.9  359.96  4954.5  357.97  4962.8  355.39  4968.5  355.24  4977.3  353.33
  4990.1  351.98    5000  353.76  5006.6  355.52  5012.3  353.04  5028.5  354.38
  5050.4   355.5  5056.8  356.44  5064.7  359.76    5129  360.61  5176.1  360.08
#Mann= 3 , 0 , 0
  4625.5      .1       0  4968.5     .07       0  5006.6      .1       0
#XS Ineff= 2 , 0
       0                 5006.36       0  355.54
Permanent Ineff=
       F       T
Bank Sta=4968.5,5006.6
XS Rating Curve= 0 ,0
Exp/Cntr=0.3,0.1

Type RM Length L Ch R = 1 ,491     ,363,363,363
BEGIN DESCRIPTION:
Mapping XS a9ce6bb3
END DESCRIPTION:
XS GIS Cut Line= 3
      2207865.02     13186893.14      2208254.24     13186506.65
      2208202.61     13186305.58
#Sta/Elev= 30
  4491.6  372.07  4568.6  369.67  4582.8  368.61  4589.9   368.9  4611.1  367.66
  4724.2  365.17  4738.4   363.9  4752.5  364.26  4787.9  363.13  4823.2  360.76
  4830.3  361.09  4879.8  359.35    4901     358  4922.2  354.83  4929.3  352.89
  4936.3  353.26  4950.5   351.1  4979.5  350.94  4989.9  350.57  4992.7  350.07
  4995.9  350.57    5000  352.12  5007.1  357.55  5014.2     358  5045.6  358.91
    5122  359.26  5127.1  358.51  5132.8  359.02  5167.9   358.4  5247.7  359.44
#Mann= 4 ,-1 , 0
  4491.6      .1       0  4979.5     .12       0  4989.9     .07       0
  4995.9     .12       0
Bank Sta=4989.9,4995.9
XS Rating Curve= 0 ,0
Exp/Cntr=0.3,0.1

Type RM Length L Ch R = 1 ,128     ,0,0,0
BEGIN DESCRIPTION:
UNT 103 IN LACR 1.0
END DESCRIPTION:
XS GIS Cut Line= 4
      2208069.18     13187048.26      2208371.27     13186874.08
      2208425.71     13186778.82       2208327.7     13186637.26
#Sta/Elev= 30
  4491.3  370.54  4623.3  361.85  4639.1  361.84  4651.2  360.37  4674.3  358.98
  4765.8  356.99  4821.5  356.55  4880.2   357.8  4885.9  353.31  4894.4   349.8
  4901.8  347.99  4907.5  348.91  4923.4  349.29  4929.1  351.69  4952.3  350.94
  4956.6  351.96  4964.3  351.81  4986.3  349.73  5000.5  347.24  5007.3   347.8
  5013.3  350.04  5028.2  350.76    5037  350.43  5043.1  354.15  5049.4  355.12
  5057.9  353.17    5064  356.68  5072.8  352.65  5078.9   356.6  5121.9  357.58
#Mann= 4 ,-1 , 0
  4491.3      .1       0  4765.8      .1       0  4894.4    .035       0
  4929.1      .1       0
Bank Sta=4986.3,5013.3
XS Rating Curve= 0 ,0
Exp/Cntr=0.3,0.1

Chan Stop Cuts=-1
Use User Specified Reach Order=0
Composite Channel Slope=5