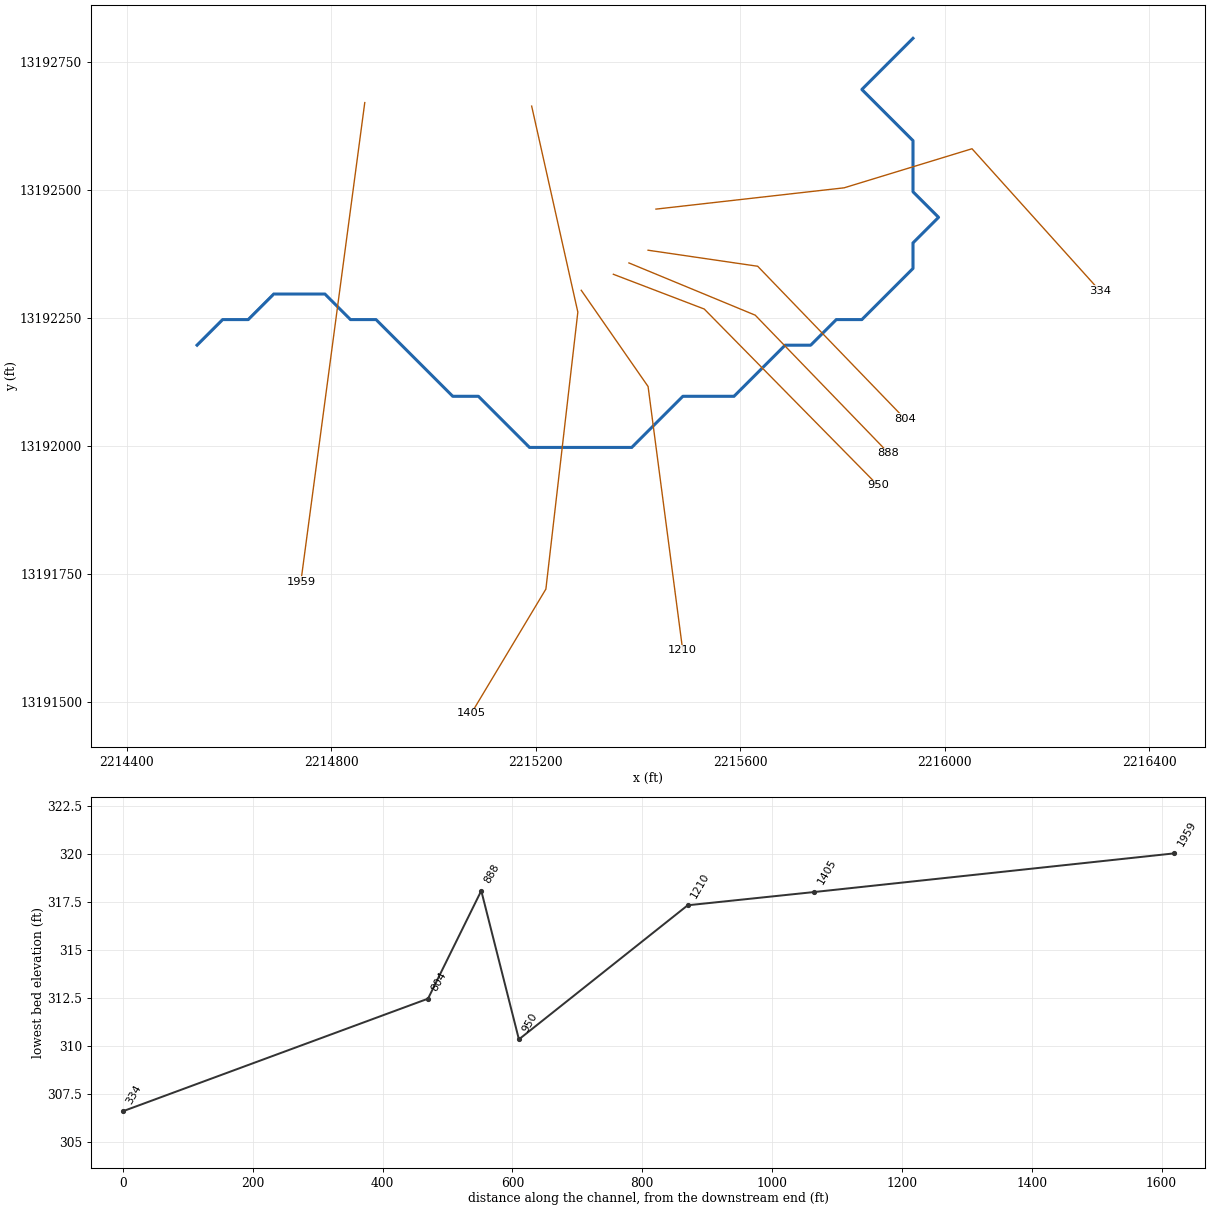
--- UNT 105 IN LACR.prj (project) ---

Proj Title=UNT 105 IN LACR Base Level Engineering
Current Plan=p01
Default Exp/Contr=0.3,0.1
English Units
Geom File=g01
Flow File=f01
Plan File=p01
Y Axis Title=Elevation
X Axis Title(PF)=Main Channel Distance
X Axis Title(XS)=Station
BEGIN DESCRIPTION:
UNT 105 IN LACR
END DESCRIPTION:
DSS Export Rating Curves= 0
DSS Export Rating Curve Sorted= 0
DSS Export Volume Flow Curves= 0
DXF OffsetX= 0
DXF OffsetY= 0
DXF ScaleX= 1
DXF ScaleY= 10

--- UNT 105 IN LACR.p01 (plan) ---

Plan Title=Multiple Run
Short Identifier=Multiple
Geom File=g01
Flow File=f01
Subcritical Flow
K Sum by GR= 0
Std Step Tol= 0.01
Critical Tol= 0.01
Num of Std Step Trials= 20
Max Error Tol= 0.3
Flow Tol Ratio= 0.001
Split Flow NTrial= 30
Split Flow Tol= 0.02
Split Flow Ratio= 0.02
Log Output Level= 0
Friction Slope Method= 1
Unsteady Friction Slope Method= 2
Unsteady Bridges Friction Slope Method= 1
Parabolic Critical Depth
Global Vel Dist=  1 , 1 , 1
Global Log Level= 0
CheckData=True
Encroach Param= -1, 0, 0, 0
BEGIN DESCRIPTION:
Multiple Run
END DESCRIPTION:

--- UNT 105 IN LACR.f01 (steady flow) ---

Flow Title=Multiple
Number of Profiles=7
Profile Names=10-year,25-year,50-year,1pct_min,100-year,1pct_plu,500-year
River Rch & RM= UNT 105 IN LACR,Reach-1,1959
      77     101     120     105     142     192     202
Boundary for River Rch & Prof#=UNT 105 IN LACR,Reach-1,1
Up Type=0
Dn Type=3
Dn Slope=0.005
Boundary for River Rch & Prof#=UNT 105 IN LACR,Reach-1,2
Up Type=0
Dn Type=3
Dn Slope=0.005
Boundary for River Rch & Prof#=UNT 105 IN LACR,Reach-1,3
Up Type=0
Dn Type=3
Dn Slope=0.005
Boundary for River Rch & Prof#=UNT 105 IN LACR,Reach-1,4
Up Type=0
Dn Type=3
Dn Slope=0.005
Boundary for River Rch & Prof#=UNT 105 IN LACR,Reach-1,5
Up Type=0
Dn Type=3
Dn Slope=0.005
Boundary for River Rch & Prof#=UNT 105 IN LACR,Reach-1,6
Up Type=0
Dn Type=3
Dn Slope=0.005
Boundary for River Rch & Prof#=UNT 105 IN LACR,Reach-1,7
Up Type=0
Dn Type=3
Dn Slope=0.005

--- UNT 105 IN LACR.g01 (geometry) ---

Geom Title=Existing Conditions
Program Version=4.10

River Reach=UNT 105 IN LACR ,Reach-1
Reach XY= 30
      2214537.72     13192196.85      2214587.72     13192246.85
      2214637.72     13192246.85      2214687.72     13192296.86
      2214787.72     13192296.86      2214837.72     13192246.85
      2214887.72     13192246.85      2214987.72     13192146.86
      2215037.72     13192096.85      2215087.72     13192096.85
      2215137.72     13192046.85      2215187.72     13191996.86
      2215387.72     13191996.86      2215437.72     13192046.85
      2215487.72     13192096.85      2215587.72     13192096.85
      2215637.72     13192146.86      2215687.72     13192196.85
      2215737.72     13192196.85      2215787.72     13192246.85
      2215837.72     13192246.85      2215887.72     13192296.86
      2215937.72     13192346.85      2215937.72     13192396.85
      2215987.72     13192446.85      2215937.72     13192496.86
      2215937.72     13192596.85      2215887.72     13192646.86
      2215837.72     13192696.85      2215937.72     13192796.86

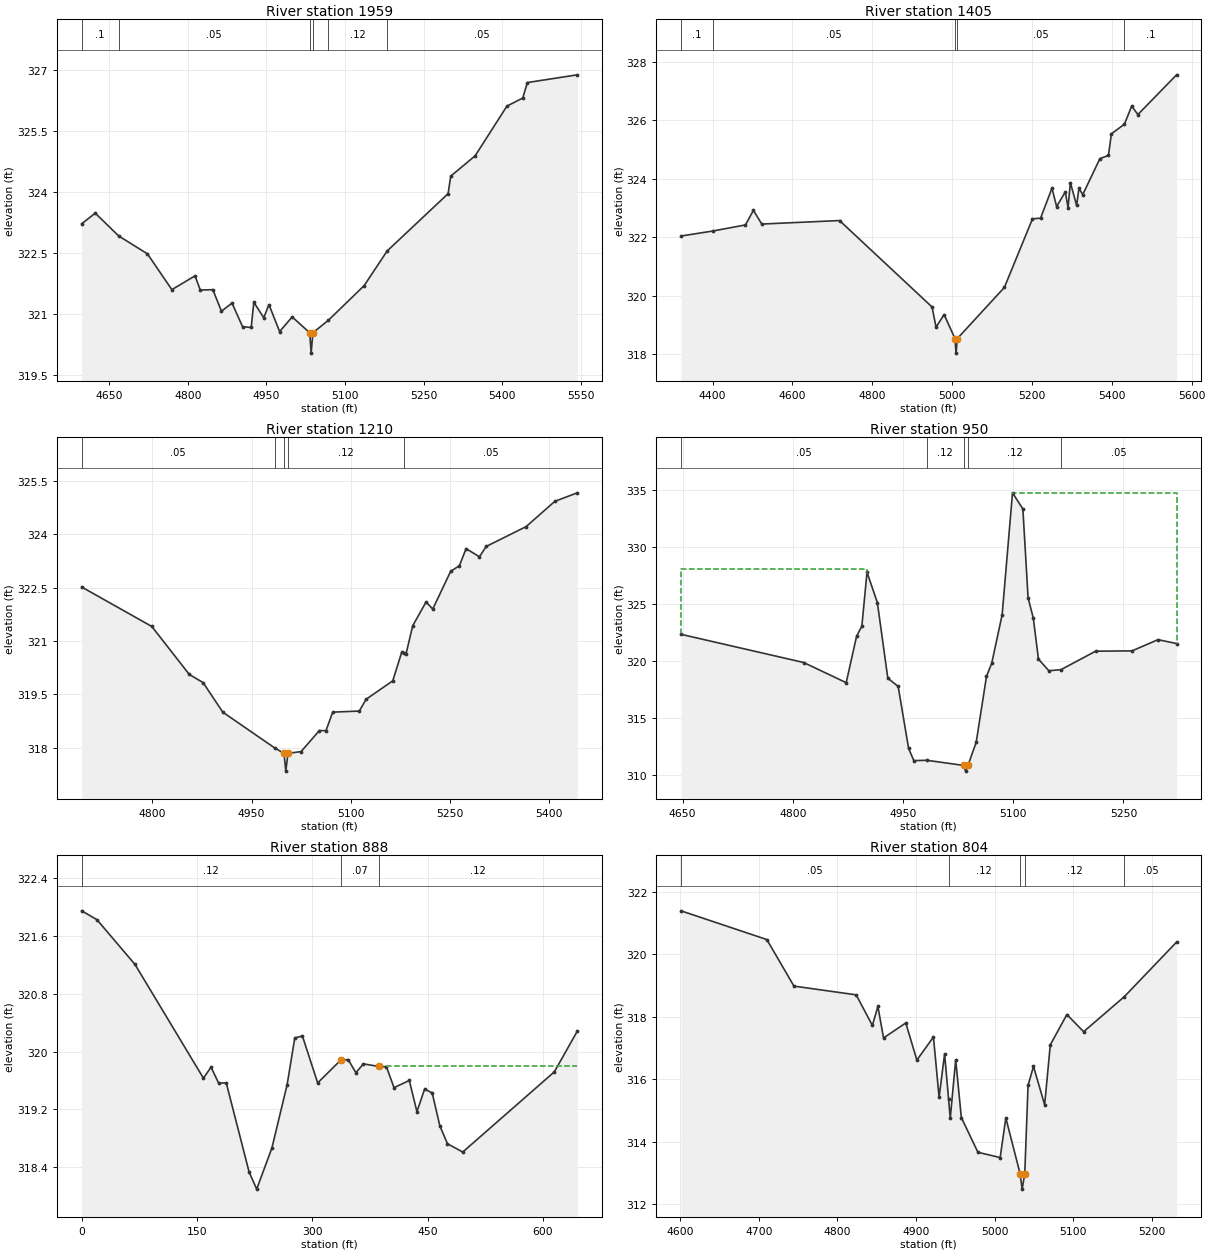
Type RM Length L Ch R = 1 ,1959    ,554,554,554
BEGIN DESCRIPTION:
UNT 105 IN LACR 2.0
END DESCRIPTION:
XS GIS Cut Line= 2
      2214865.64     13192671.21      2214740.64     13191733.71
#Sta/Elev= 30
  4597.4  323.22  4623.3  323.48    4668  322.92  4722.9  322.48  4769.5   321.6
  4813.7  321.94  4823.7  321.59  4847.7   321.6  4864.1  321.07  4884.3  321.27
  4904.4  320.69  4920.9  320.67  4925.9  321.29  4944.8  320.91  4954.9  321.23
  4975.1  320.57  4999.1  320.93  5032.6  320.54  5035.3  320.04  5038.6  320.54
  5068.4  320.85  5136.5   321.7  5180.3  322.55  5296.7  323.96  5301.7  324.39
  5348.3  324.89  5408.9  326.11  5439.1  326.31    5448  326.69  5543.2  326.88
#Mann= 6 ,-1 , 0
  4597.4      .1       0    4668     .05       0  5032.6     .03       0
  5038.6     .05       0  5068.4     .12       0  5180.3     .05       0
Bank Sta=5032.6,5038.6
XS Rating Curve= 0 ,0
Exp/Cntr=0.3,0.1

Type RM Length L Ch R = 1 ,1405    ,195,195,195
BEGIN DESCRIPTION:
Mapping XS 66d7a38e
END DESCRIPTION:
XS GIS Cut Line= 4
      2215192.02     13192664.31      2215282.31     13192261.49
      2215219.81     13191719.83      2215073.98     13191476.78
#Sta/Elev= 30
  4320.8  322.04  4399.8  322.21  4482.2  322.42  4502.2  322.92  4523.1  322.45
  4717.9  322.57  4949.7  319.61  4959.7  318.92  4979.9  319.35  5007.1  318.53
  5009.8  318.03  5013.1  318.53  5130.9  320.28  5201.3  322.63  5221.5  322.65
  5250.1  323.68  5261.7  323.05  5283.5  323.55  5290.4  323.01  5296.2  323.87
  5311.8  323.09  5317.6  323.67  5327.3  323.46  5370.1  324.69  5391.5   324.8
    5399  325.54  5431.6  325.87  5449.8  326.49  5465.3   326.2  5562.3  327.56
#Mann= 5 ,-1 , 0
  4320.8      .1       0  4399.8     .05       0  5007.1    .035       0
  5013.1     .05       0  5431.6      .1       0
Bank Sta=5007.1,5013.1
XS Rating Curve= 0 ,0
Exp/Cntr=0.3,0.1

Type RM Length L Ch R = 1 ,1210    ,260,260,260
BEGIN DESCRIPTION:
Mapping XS 4a06f006
END DESCRIPTION:
XS GIS Cut Line= 3
        2215289.     13192304.15      2215419.69     13192115.95
      2215487.41      13191600.2
#Sta/Elev= 30
  4693.2  322.52  4799.2  321.41  4855.9  320.06  4876.8  319.83  4906.5     319
  4985.2  317.99  4999.1  317.84  5001.8  317.34  5005.1  317.84  5024.9  317.89
  5052.5  318.48  5062.6  318.48  5072.7     319    5113  319.03  5123.1  319.36
  5163.5  319.88  5177.3   320.7    5180  320.67  5183.6  320.64  5193.7  321.43
  5213.9   322.1    5224   321.9    5251  322.96  5264.3  323.12  5274.4   323.6
  5294.6  323.37  5304.7  323.66  5365.2  324.22  5408.5  324.93  5442.5  325.17
#Mann= 5 ,-1 , 0
  4693.2     .05       0  4985.2     .12       0  4999.1     .07       0
  5005.1     .12       0    5180     .05       0
Bank Sta=4999.1,5005.1
XS Rating Curve= 0 ,0
Exp/Cntr=0.3,0.1

Type RM Length L Ch R = 1 ,950     ,58,58,58
BEGIN DESCRIPTION:
Mapping XS f81a4f6c
END DESCRIPTION:
XS GIS Cut Line= 3
      2215351.79     13192335.46      2215529.45     13192267.53
       2215869.2     13191922.55
#Sta/Elev= 30
  4647.9  322.35  4814.8  319.88  4872.7  318.11  4886.8  322.18    4894  323.07
    4901  327.79  4915.1  325.13  4929.3  318.51  4943.4  317.78  4957.6  312.35
  4964.7  311.28  4982.6  311.31  5032.4  310.86  5035.2  310.36  5038.4  310.86
  5049.6  312.89  5063.6  318.66  5070.7  319.81  5084.9  324.06    5099  334.75
  5113.1  333.34  5120.2  325.55  5127.3  323.77  5134.3  320.18  5148.4  319.16
  5164.9  319.25  5212.1  320.87  5261.6   320.9    5297  321.88  5322.3  321.54
#Mann= 5 ,-1 , 0
  4647.9     .05       0  4982.6     .12       0  5032.4     .07       0
  5038.4     .12       0  5164.9     .05       0
#XS Ineff= 2 , 0
       0 4900.82  328.06 5098.86       0  334.74
Permanent Ineff=
       T       T
Bank Sta=5032.4,5038.4
XS Rating Curve= 0 ,0
Exp/Cntr=0.3,0.1

Type RM Length L Ch R = 1 ,888     ,82,82,82
XS GIS Cut Line= 3
     2215382.275    13192357.623     2215629.202     13192255.48
     2215890.013    13191985.745
#Sta/Elev= 30
       0321.947719.79962321.825769.29867321.2068 158.397319.6323168.2968319.7847
178.1966319.5641188.0964319.5678217.7958318.3354227.6956318.0974247.4953318.6666
267.2949319.5414277.2299320.1881 287.165320.2164307.0351 319.567336.8403319.8804
346.7754319.8895356.7104319.7085366.6455319.8303386.5156319.7946396.4507319.7913
406.3857319.5011426.2559319.6008436.1909319.1692 446.126319.4802 456.061319.4289
465.9961318.9728475.9312318.7256495.8013318.6104 615.022319.7203644.8272320.2824
#Mann= 3 , 0 , 0
       0     .12       0336.8403     .07       0386.5156     .12       0
#XS Ineff= 2 , 0
       0  285.71   320.2  396.62       0   319.8
Permanent Ineff=
       T       T
Bank Sta=336.8403,386.5156
XS Rating Curve= 0 ,0
Exp/Cntr=0.3,0.1

Type RM Length L Ch R = 1 ,804     ,470,470,470
BEGIN DESCRIPTION:
Mapping XS c5c3e21f
END DESCRIPTION:
XS GIS Cut Line= 3
      2215419.66     13192382.52      2215633.99     13192351.16
      2215921.45     13192053.24
#Sta/Elev= 30
  4600.9  321.39  4710.1  320.47  4744.6  318.98  4823.8   318.7  4844.4  317.72
  4851.4  318.33  4858.6  317.32  4886.9   317.8    4901  316.61  4922.1  317.35
  4929.3  315.42  4936.3  316.81  4941.3  315.38  4943.5  314.75  4950.4  316.62
  4957.6  314.77  4978.7  313.66    5007  313.49  5014.2  314.76  5032.3  312.98
    5035  312.48  5038.3  312.98  5042.5   315.8  5049.4  316.41  5063.6  315.18
  5070.8   317.1  5091.9  318.07  5113.2  317.52  5164.9  318.64  5231.5  320.39
#Mann= 5 ,-1 , 0
  4600.9     .05       0  4941.3     .12       0  5032.3     .07       0
  5038.3     .12       0  5164.9     .05       0
Bank Sta=5032.3,5038.3
XS Rating Curve= 0 ,0
Exp/Cntr=0.3,0.1

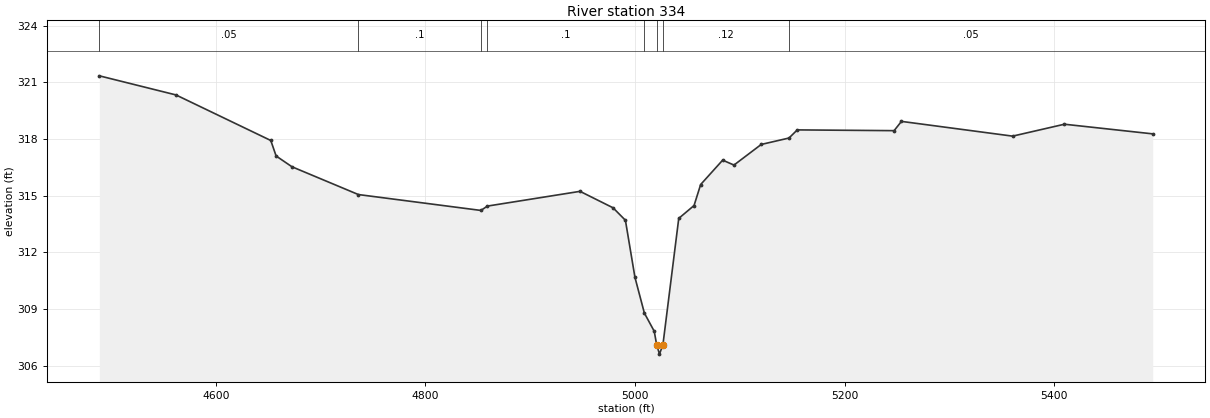
Type RM Length L Ch R = 1 ,334     ,0,0,0
BEGIN DESCRIPTION:
UNT 105 IN LACR 1.0
END DESCRIPTION:
XS GIS Cut Line= 4
      2215435.11     13192462.89      2215803.14     13192504.55
      2216053.14     13192580.94      2216302.94     13192303.38
#Sta/Elev= 30
  4488.9  321.34    4562  320.33  4652.5  317.92  4657.6   317.1  4672.7  316.53
  4736.1  315.06    4853  314.22  4859.2  314.45  4947.6  315.23  4979.1  314.36
  4990.9   313.7    5000  310.68    5009  308.79  5018.4  307.83  5020.7  307.12
  5023.4  306.62  5026.7  307.12  5041.8   313.8  5056.4  314.48  5062.7  315.59
  5083.7  316.88  5094.5  316.62  5120.5  317.71    5147  318.05  5154.9  318.48
  5247.3  318.44  5254.3  318.93  5360.4  318.15  5409.8  318.78  5494.1  318.27
#Mann= 8 ,-1 , 0
  4488.9     .05       0  4736.1      .1       0    4853     .05       0
  4859.2      .1       0    5009     .12       0  5020.7     .07       0
  5026.7     .12       0    5147     .05       0
Bank Sta=5020.7,5026.7
XS Rating Curve= 0 ,0
Exp/Cntr=0.3,0.1

Chan Stop Cuts=-1
Use User Specified Reach Order=0
Composite Channel Slope=5