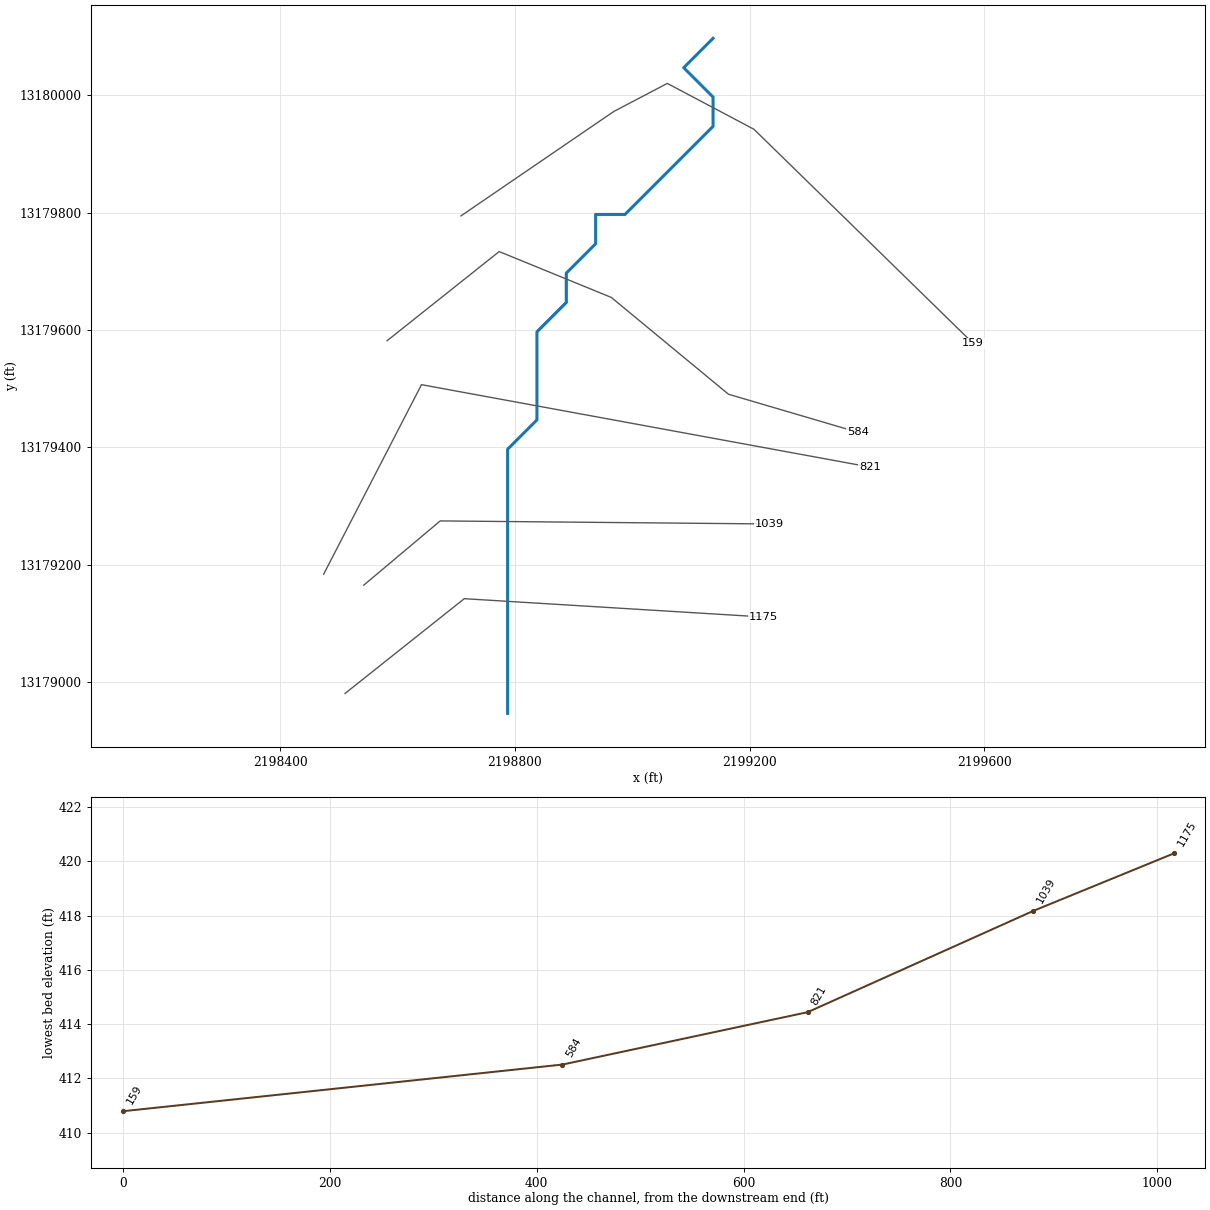
--- UNT 106 IN LACR.prj (project) ---

Proj Title=UNT 106 IN LACR Base Level Engineering
Current Plan=p01
Default Exp/Contr=0.3,0.1
English Units
Geom File=g01
Flow File=f01
Plan File=p01
BEGIN DESCRIPTION:
UNT 106 IN LACR
END DESCRIPTION:

--- UNT 106 IN LACR.p01 (plan) ---

Plan Title=Multiple Run
Short Identifier=Multiple
Geom File=g01
Flow File=f01
Subcritical Flow
K Sum by GR= 0
Std Step Tol= 0.01
Critical Tol= 0.01
Num of Std Step Trials= 20
Max Error Tol= 0.3
Flow Tol Ratio= 0.001
Split Flow NTrial= 30
Split Flow Tol= 0.02
Split Flow Ratio= 0.02
Log Output Level= 0
Friction Slope Method= 1
Unsteady Friction Slope Method= 2
Unsteady Bridges Friction Slope Method= 1
Parabolic Critical Depth
Global Vel Dist=  1 , 1 , 1
Global Log Level= 0
CheckData=True
Encroach Param= -1, 0, 0, 0
BEGIN DESCRIPTION:
Multiple Run
END DESCRIPTION:

--- UNT 106 IN LACR.f01 (steady flow) ---

Flow Title=Multiple
Number of Profiles=7
Profile Names=10-year,25-year,50-year,1pct_min,100-year,1pct_plu,500-year
River Rch & RM= UNT 106 IN LACR,Reach-1,1175
      54      68      78      67      91     123     124
Boundary for River Rch & Prof#=UNT 106 IN LACR,Reach-1,1
Up Type=0
Dn Type=3
Dn Slope=0.005
Boundary for River Rch & Prof#=UNT 106 IN LACR,Reach-1,2
Up Type=0
Dn Type=3
Dn Slope=0.005
Boundary for River Rch & Prof#=UNT 106 IN LACR,Reach-1,3
Up Type=0
Dn Type=3
Dn Slope=0.005
Boundary for River Rch & Prof#=UNT 106 IN LACR,Reach-1,4
Up Type=0
Dn Type=3
Dn Slope=0.005
Boundary for River Rch & Prof#=UNT 106 IN LACR,Reach-1,5
Up Type=0
Dn Type=3
Dn Slope=0.005
Boundary for River Rch & Prof#=UNT 106 IN LACR,Reach-1,6
Up Type=0
Dn Type=3
Dn Slope=0.005
Boundary for River Rch & Prof#=UNT 106 IN LACR,Reach-1,7
Up Type=0
Dn Type=3
Dn Slope=0.005

--- UNT 106 IN LACR.g01 (geometry) ---

Geom Title=Existing Conditions

River Reach=UNT 106 IN LACR,Reach-1
Reach XY= 25
      2198787.72     13178946.85      2198787.72     13178996.85
      2198787.72     13179046.86      2198787.72     13179096.85
      2198787.72     13179146.85      2198787.72     13179196.86
      2198787.72     13179246.85      2198787.72     13179296.85
      2198787.72     13179346.86      2198787.72     13179396.85
      2198837.72     13179446.85      2198837.72     13179496.85
      2198837.72     13179546.85      2198837.72     13179596.85
      2198887.72     13179646.85      2198887.72     13179696.86
      2198937.72     13179746.85      2198937.72     13179796.85
      2198987.72     13179796.85      2199037.72     13179846.86
      2199087.72     13179896.85      2199137.72     13179946.85
      2199137.72     13179996.86      2199087.72     13180046.85
      2199137.72     13180096.85

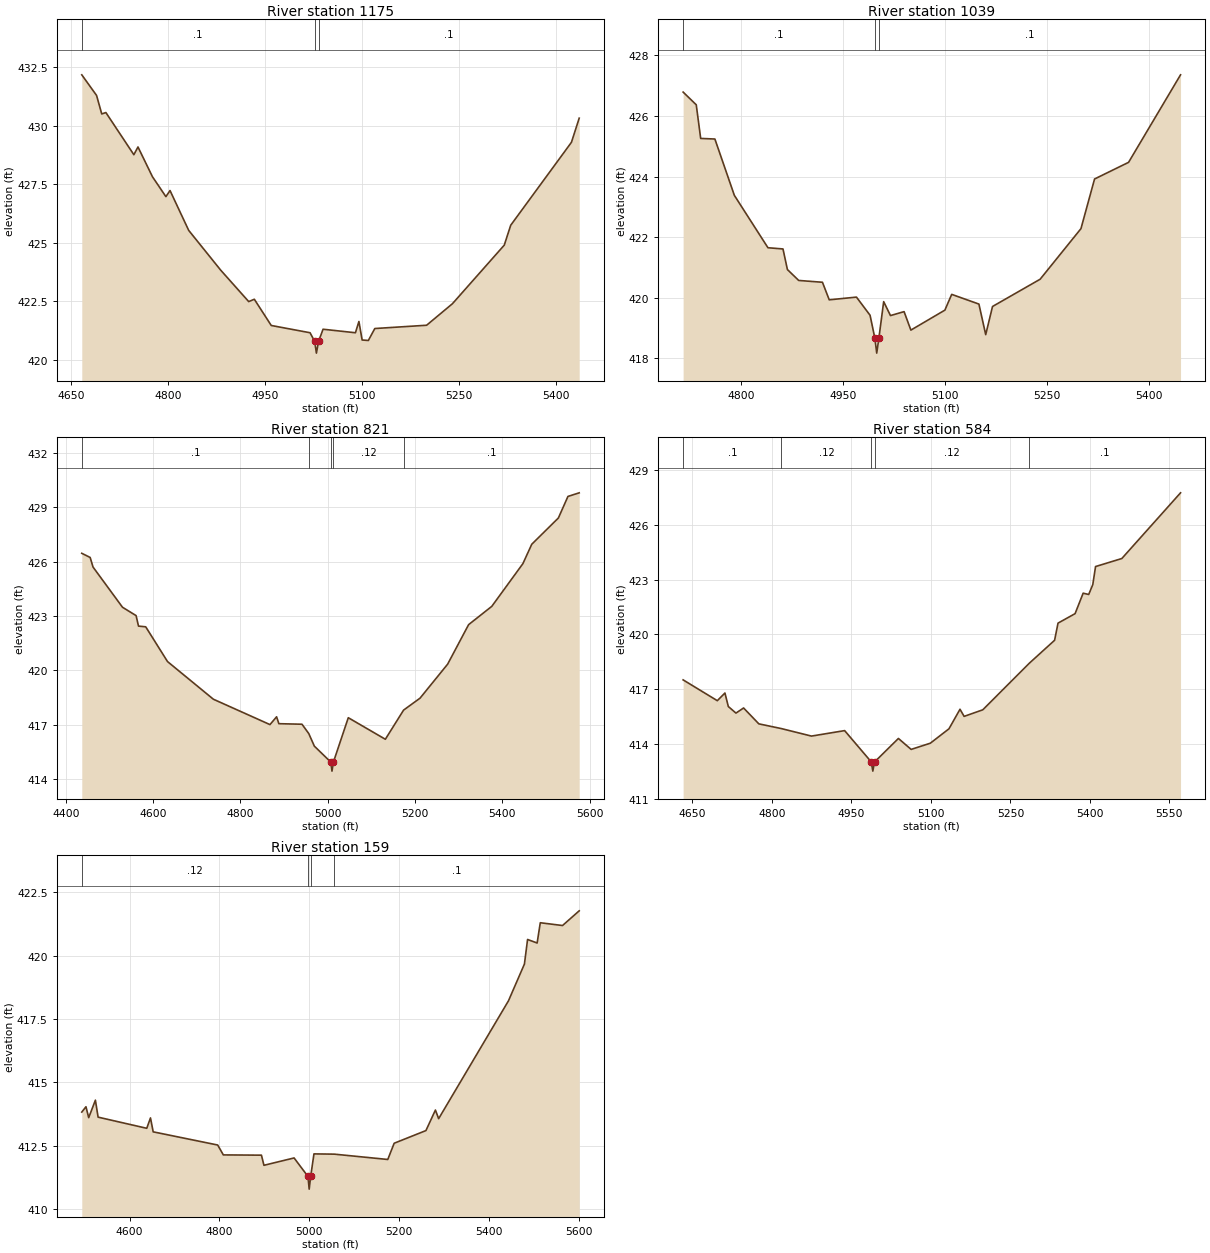
Type RM Length L Ch R = 1,1175,136,136,136
BEGIN DESCRIPTION:
UNT 106 IN LACR 2.0
END DESCRIPTION:
XS GIS Cut Line= 3
      2198510.81     13178980.79      2198713.92     13179142.24
      2199223.50     13179111.05
#Sta/Elev= 30
  4666.6  432.17  4689.5  431.29  4697.5  430.50  4703.9  430.56  4747.2  428.76
  4753.6  429.09  4776.0  427.82  4796.8  426.97  4803.2  427.23  4832.1  425.53
  4881.7  423.83  4925.0  422.49  4933.7  422.59  4959.9  421.47  5020.0  421.16
  5027.1  420.79  5029.8  420.29  5033.1  420.79  5040.1  421.31  5090.2  421.16
  5095.6  421.64  5100.6  420.85  5110.2  420.83  5120.2  421.34  5200.4  421.48
  5240.4  422.40  5320.6  424.90  5330.6  425.75  5424.6  429.29  5436.6  430.32
#Mann=3,-1,0
  4666.6     0.1       0  5027.1    0.07       0  5033.1     0.1       0
Bank Sta=5027.1,5033.1
Exp/Cntr=0.3,0.1

Type RM Length L Ch R = 1,1039,218,218,218
BEGIN DESCRIPTION:
Mapping XS 33eade1a
END DESCRIPTION:
XS GIS Cut Line= 3
      2198542.76     13179165.37      2198672.94     13179274.72
      2199234.10     13179269.53
#Sta/Elev= 30
  4715.2  426.79  4734.5  426.37  4741.0  425.26  4761.9  425.24  4790.5  423.38
  4839.9  421.65  4862.0  421.61  4868.5  420.93  4885.1  420.57  4920.0  420.51
  4930.0  419.93  4970.0  420.02  4990.0  419.42  4997.0  418.67  4999.8  418.17
  5003.0  418.67  5010.0  419.87  5020.0  419.41  5040.0  419.54  5050.0  418.93
  5100.0  419.59  5110.0  420.11  5150.0  419.79  5160.0  418.78  5170.0  419.71
  5240.0  420.61  5300.0  422.28  5320.0  423.92  5370.0  424.47  5446.4  427.36
#Mann=3,-1,0
  4715.2     0.1       0  4997.0    0.07       0  5003.0     0.1       0
Bank Sta=4997,5003
Exp/Cntr=0.3,0.1

Type RM Length L Ch R = 1,821,237,237,237
BEGIN DESCRIPTION:
Mapping XS 87f066cb
END DESCRIPTION:
XS GIS Cut Line= 3
      2198474.34     13179183.91      2198641.01     13179506.83
      2199404.64     13179366.57
#Sta/Elev= 30
  4436.6  426.47  4455.8  426.24  4462.4  425.71  4529.9  423.49  4561.0  423.03
  4566.6  422.45  4583.1  422.41  4633.1  420.49  4738.2  418.41  4867.8  417.01
  4883.0  417.44  4888.2  417.06  4941.2  417.03  4956.8  416.51  4969.5  415.82
  5007.2  414.94  5009.9  414.44  5013.2  414.94  5047.3  417.39  5132.2  416.20
  5174.0  417.81  5211.7  418.47  5275.0  420.35  5323.0  422.53  5376.1  423.54
  5447.4  425.90  5467.7  426.97  5528.7  428.42  5550.6  429.61  5576.4  429.81
#Mann=5,-1,0
  4436.6     0.1       0  4956.8    0.12       0  5007.2    0.07       0
  5013.2    0.12       0  5174.0     0.1       0
Bank Sta=5007.2,5013.2
Exp/Cntr=0.3,0.1

Type RM Length L Ch R = 1,584,425,425,425
BEGIN DESCRIPTION:
Mapping XS c0625f46
END DESCRIPTION:
XS GIS Cut Line= 5
      2198582.38     13179581.65      2198773.39     13179733.59
      2198964.36     13179655.47      2199164.01     13179490.54
      2199384.02     13179425.83
#Sta/Elev= 30
  4632.4  417.51  4696.9  416.37  4711.3  416.79  4717.7  416.05  4732.1  415.69
  4746.5  415.97  4775.3  415.10  4818.0  414.84  4874.6  414.43  4937.2  414.73
  4987.6  413.01  4990.4  412.51  4993.6  413.01  5038.7  414.30  5062.7  413.70
  5098.9  414.04  5134.1  414.83  5154.9  415.90  5162.7  415.51  5197.9  415.87
  5285.6  418.42  5333.4  419.68  5339.9  420.62  5372.1  421.14  5387.3  422.26
  5397.8  422.19  5405.5  422.73  5410.7  423.72  5460.3  424.16  5571.1  427.76
#Mann=5,-1,0
  4632.4     0.1       0  4818.0    0.12       0  4987.6    0.07       0
  4993.6    0.12       0  5285.6     0.1       0
Bank Sta=4987.6,4993.6
Exp/Cntr=0.3,0.1

Type RM Length L Ch R = 1,159,0,0,0
BEGIN DESCRIPTION:
UNT 106 IN LACR 1.0
END DESCRIPTION:
XS GIS Cut Line= 5
      2198708.30     13179794.37      2198968.70     13179972.31
      2199059.84     13180020.05      2199207.41     13179941.92
      2199580.66     13179577.36
#Sta/Elev= 30
  4493.6  413.83  4502.9  414.04  4509.0  413.61  4523.9  414.30  4529.9  413.63
  4638.2  413.19  4646.5  413.60  4652.5  413.05  4796.1  412.53  4808.6  412.14
  4893.4  412.13  4899.0  411.73  4966.1  412.02  4997.0  411.29  4999.7  410.79
  5003.0  411.29  5010.3  412.18  5055.4  412.17  5174.6  411.96  5188.8  412.60
  5259.5  413.10  5280.6  413.91  5287.8  413.57  5443.2  418.22  5478.7  419.67
  5485.7  420.64  5507.0  420.50  5514.0  421.30  5563.5  421.19  5600.6  421.77
#Mann=4,-1,0
  4493.6    0.12       0  4997.0    0.07       0  5003.0    0.12       0
  5055.4     0.1       0
Bank Sta=4997,5003
Exp/Cntr=0.3,0.1

Chan Stop Cuts=-1