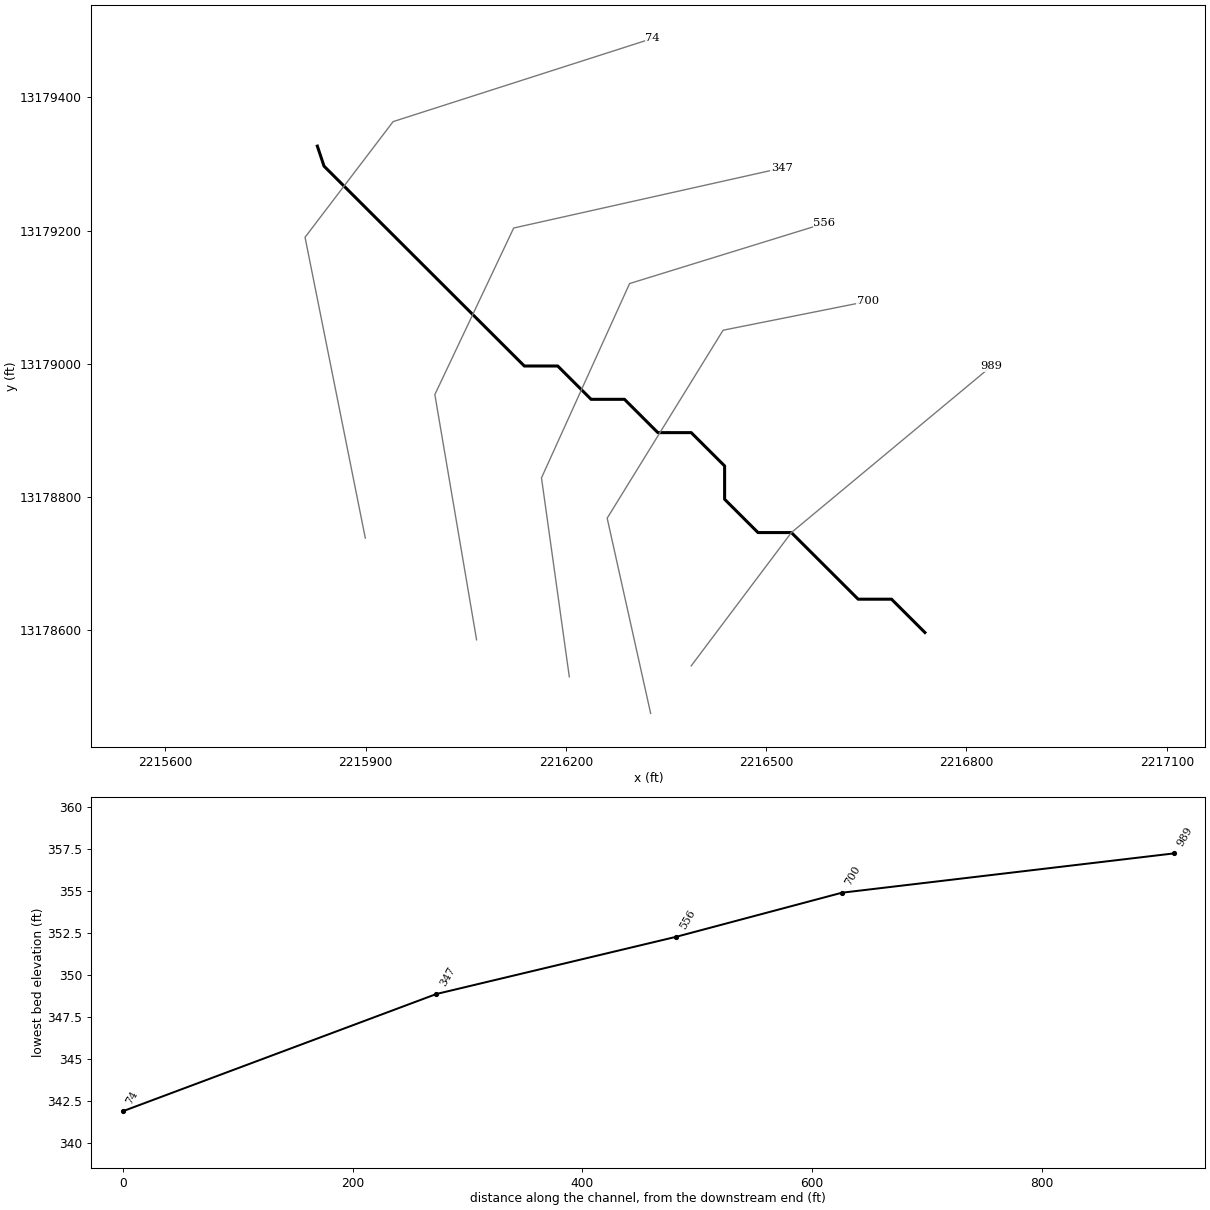
--- UNT 107 IN LACR.prj (project) ---

Proj Title=UNT 107 IN LACR Base Level Engineering
Current Plan=p01
Default Exp/Contr=0.3,0.1
English Units
Geom File=g01
Flow File=f01
Plan File=p01
Y Axis Title=Elevation
X Axis Title(PF)=Main Channel Distance
X Axis Title(XS)=Station
BEGIN DESCRIPTION:
UNT 107 IN LACR
END DESCRIPTION:
DSS Export Rating Curves= 0
DSS Export Rating Curve Sorted= 0
DSS Export Volume Flow Curves= 0
DXF OffsetX= 0
DXF OffsetY= 0
DXF ScaleX= 1
DXF ScaleY= 10

--- UNT 107 IN LACR.p01 (plan) ---

Plan Title=Multiple Run
Short Identifier=Multiple
Geom File=g01
Flow File=f01
Subcritical Flow
K Sum by GR= 0
Std Step Tol= 0.01
Critical Tol= 0.01
Num of Std Step Trials= 20
Max Error Tol= 0.3
Flow Tol Ratio= 0.001
Split Flow NTrial= 30
Split Flow Tol= 0.02
Split Flow Ratio= 0.02
Log Output Level= 0
Friction Slope Method= 1
Unsteady Friction Slope Method= 2
Unsteady Bridges Friction Slope Method= 1
Parabolic Critical Depth
Global Vel Dist=  1 , 1 , 1
Global Log Level= 0
CheckData=True
Encroach Param= -1, 0, 0, 0
BEGIN DESCRIPTION:
Multiple Run
END DESCRIPTION:

--- UNT 107 IN LACR.f01 (steady flow) ---

Flow Title=Multiple
Number of Profiles=7
Profile Names=10-year,25-year,50-year,1pct_min,100-year,1pct_plu,500-year
River Rch & RM= UNT 107 IN LACR,Reach-1,989
      64      82      97      84     114     154     160
Boundary for River Rch & Prof#=UNT 107 IN LACR,Reach-1,1
Up Type=0
Dn Type=3
Dn Slope=0.005
Boundary for River Rch & Prof#=UNT 107 IN LACR,Reach-1,2
Up Type=0
Dn Type=3
Dn Slope=0.005
Boundary for River Rch & Prof#=UNT 107 IN LACR,Reach-1,3
Up Type=0
Dn Type=3
Dn Slope=0.005
Boundary for River Rch & Prof#=UNT 107 IN LACR,Reach-1,4
Up Type=0
Dn Type=3
Dn Slope=0.005
Boundary for River Rch & Prof#=UNT 107 IN LACR,Reach-1,5
Up Type=0
Dn Type=3
Dn Slope=0.005
Boundary for River Rch & Prof#=UNT 107 IN LACR,Reach-1,6
Up Type=0
Dn Type=3
Dn Slope=0.005
Boundary for River Rch & Prof#=UNT 107 IN LACR,Reach-1,7
Up Type=0
Dn Type=3
Dn Slope=0.005

--- UNT 107 IN LACR.g01 (geometry) ---

Geom Title=Existing Conditions
Program Version=4.10

River Reach=UNT 107 IN LACR ,Reach-1
Reach XY= 21
      2216737.72     13178596.85      2216687.72     13178646.85
      2216637.72     13178646.85      2216587.72     13178696.86
      2216537.72     13178746.85      2216487.72     13178746.85
      2216437.72     13178796.85      2216437.72     13178846.86
      2216387.72     13178896.85      2216337.72     13178896.85
      2216287.72     13178946.85      2216237.72     13178946.85
      2216187.72     13178996.85      2216137.72     13178996.85
      2216087.72     13179046.86      2216037.72     13179096.85
      2215987.72     13179146.85      2215937.72     13179196.86
      2215887.72     13179246.85      2215837.72     13179296.85
      2215827.72     13179326.86

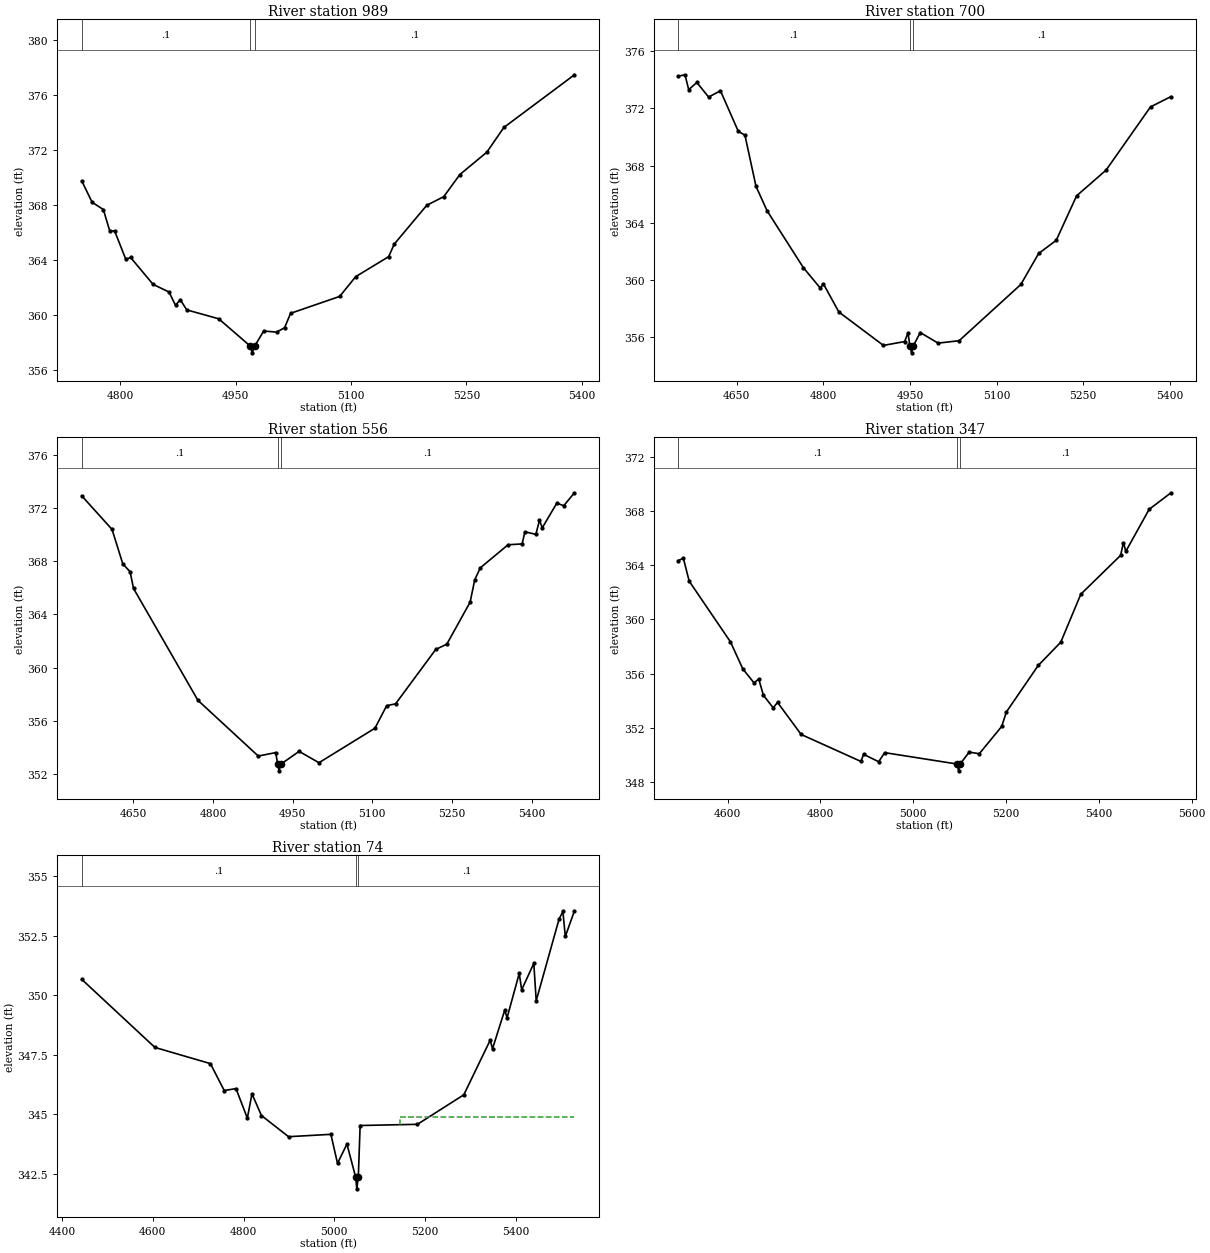
Type RM Length L Ch R = 1 ,989     ,289,289,289
BEGIN DESCRIPTION:
UNT 107 IN LACR 2.0
END DESCRIPTION:
XS GIS Cut Line= 3
      2216387.72     13178546.86      2216537.72     13178746.85
      2216837.71     13178996.85
#Sta/Elev= 30
    4750  369.75  4763.5  368.19  4778.1  367.66  4786.5  366.08  4792.7  366.11
  4807.3  364.03  4813.5  364.17  4842.7  362.21  4863.5  361.65  4871.9  360.68
  4878.1  361.09  4886.5  360.35  4928.1   359.7  4968.9  357.72  4971.6  357.22
  4974.9  357.72  4986.5  358.81  5003.3  358.73  5013.7  359.05  5021.5   360.1
  5085.3  361.33  5106.1  362.77    5149  364.23  5156.2  365.14  5198.5  367.97
  5220.6   368.6  5241.5  370.21  5276.6  371.84  5298.7  373.64  5390.5  377.48
#Mann= 3 ,-1 , 0
    4750      .1       0  4968.9     .07       0  4974.9      .1       0
Bank Sta=4968.9,4974.9
XS Rating Curve= 0 ,0
Exp/Cntr=0.3,0.1

Type RM Length L Ch R = 1 ,700     ,144,144,144
BEGIN DESCRIPTION:
Mapping XS a490cba5
END DESCRIPTION:
XS GIS Cut Line= 4
      2216326.93     13178475.47      2216261.82     13178768.44
      2216435.43     13179050.56      2216652.46     13179093.96
#Sta/Elev= 30
  4549.1  374.26  4560.8  374.36  4567.2  373.32  4581.3  373.82  4601.7   372.8
  4622.2  373.24    4653   370.4  4664.5  370.13  4683.7  366.54  4702.9  364.83
  4765.6  360.85  4795.1  359.41  4800.2  359.72  4827.1  357.74  4904.2   355.4
  4940.9  355.67  4946.7  356.28    4950  355.38  4952.8  354.88    4956  355.38
    4968   356.3  4998.8  355.56  5035.2  355.73    5142  359.67  5172.8  361.84
  5203.2  362.76  5238.5  365.88  5289.5  367.68  5366.4  372.11  5401.8  372.83
#Mann= 3 ,-1 , 0
  4549.1      .1       0    4950     .07       0    4956      .1       0
Bank Sta=4950,4956
XS Rating Curve= 0 ,0
Exp/Cntr=0.3,0.1

Type RM Length L Ch R = 1 ,556     ,209,209,209
BEGIN DESCRIPTION:
Mapping XS 06fac44d
END DESCRIPTION:
XS GIS Cut Line= 4
       2216205.1     13178530.37      2216163.44     13178828.94
      2216295.39      13179120.6      2216587.05     13179210.88
#Sta/Elev= 30
  4553.3   372.9  4610.3  370.38  4630.5   367.8  4644.3   367.2  4650.7  365.95
  4771.9  357.55  4885.4  353.37  4918.3  353.63  4921.8  352.76  4924.6  352.26
  4927.8  352.76  4962.2  353.72  4999.6  352.87  5104.9  355.46  5126.9  357.15
  5143.7  357.29  5219.2  361.37  5240.1  361.77  5283.9  364.92  5292.5  366.58
  5302.9  367.49  5355.3  369.23  5381.7  369.29    5387   370.2  5407.6  370.01
  5414.4  371.07  5419.6   370.5    5447  372.35    5460  372.16  5480.2  373.13
#Mann= 3 ,-1 , 0
  4553.3      .1       0  4921.8     .07       0  4927.8      .1       0
Bank Sta=4921.8,4927.8
XS Rating Curve= 0 ,0
Exp/Cntr=0.3,0.1

Type RM Length L Ch R = 1 ,347     ,273,273,273
BEGIN DESCRIPTION:
Mapping XS a24145cd
END DESCRIPTION:
XS GIS Cut Line= 4
      2216066.22      13178585.9      2216003.72     13178953.94
      2216121.78     13179203.94      2216523.63     13179294.01
#Sta/Elev= 30
  4493.8  364.34  4504.9   364.5  4517.4  362.82  4606.3  358.35  4632.9  356.36
  4657.1  355.33  4667.2  355.61  4677.3  354.42  4698.3  353.49  4707.8  353.89
  4758.6  351.53  4887.6  349.54  4893.1  350.07  4925.6  349.52  4938.6  350.19
    5095  349.35  5097.7  348.85    5101  349.35  5120.8  350.23  5142.4  350.11
  5190.7  352.12  5200.9  353.19  5269.4  356.61  5317.9  358.32  5361.2  361.86
  5446.9  364.72    5453  365.66  5458.2  365.02  5508.4  368.11  5555.4  369.33
#Mann= 3 ,-1 , 0
  4493.8      .1       0    5095     .07       0    5101      .1       0
#XS Ineff= 2 , 0
         4938.42  350.18
Permanent Ineff=
       F       F
Bank Sta=5095,5101
XS Rating Curve= 0 ,0
Exp/Cntr=0.3,0.1

Type RM Length L Ch R = 1 ,74      ,0,0,0
BEGIN DESCRIPTION:
UNT 107 IN LACR 1.0
END DESCRIPTION:
XS GIS Cut Line= 4
      2215899.56     13178738.61      2215809.28     13179190.05
      2215941.22     13179363.66      2216330.09     13179488.65
#Sta/Elev= 30
  4443.1  350.67  4604.5  347.81  4726.9  347.13  4757.4     346  4783.4  346.08
  4808.4  344.84  4818.6  345.86  4839.5  344.95  4899.3  344.06  4992.7  344.16
  5007.3  342.94  5028.1  343.75  5047.2  342.37  5049.9  341.87  5053.2  342.37
  5057.2  344.53  5183.6  344.58  5285.9  345.82    5344  348.11  5349.3  347.76
  5376.1  349.37  5381.4  349.06  5408.2  350.92  5413.5  350.23  5440.3  351.34
  5445.6  349.77    5496   353.2  5504.5  353.52  5509.8  352.47    5530  353.55
#Mann= 3 ,-1 , 0
  4443.1      .1       0  5047.2     .07       0  5053.2      .1       0
#XS Ineff= 2 , 0
                         5145.94           344.9
Permanent Ineff=
       F       F
Bank Sta=5047.2,5053.2
XS Rating Curve= 0 ,0
Exp/Cntr=0.3,0.1

Chan Stop Cuts=-1
Use User Specified Reach Order=0
Composite Channel Slope=5