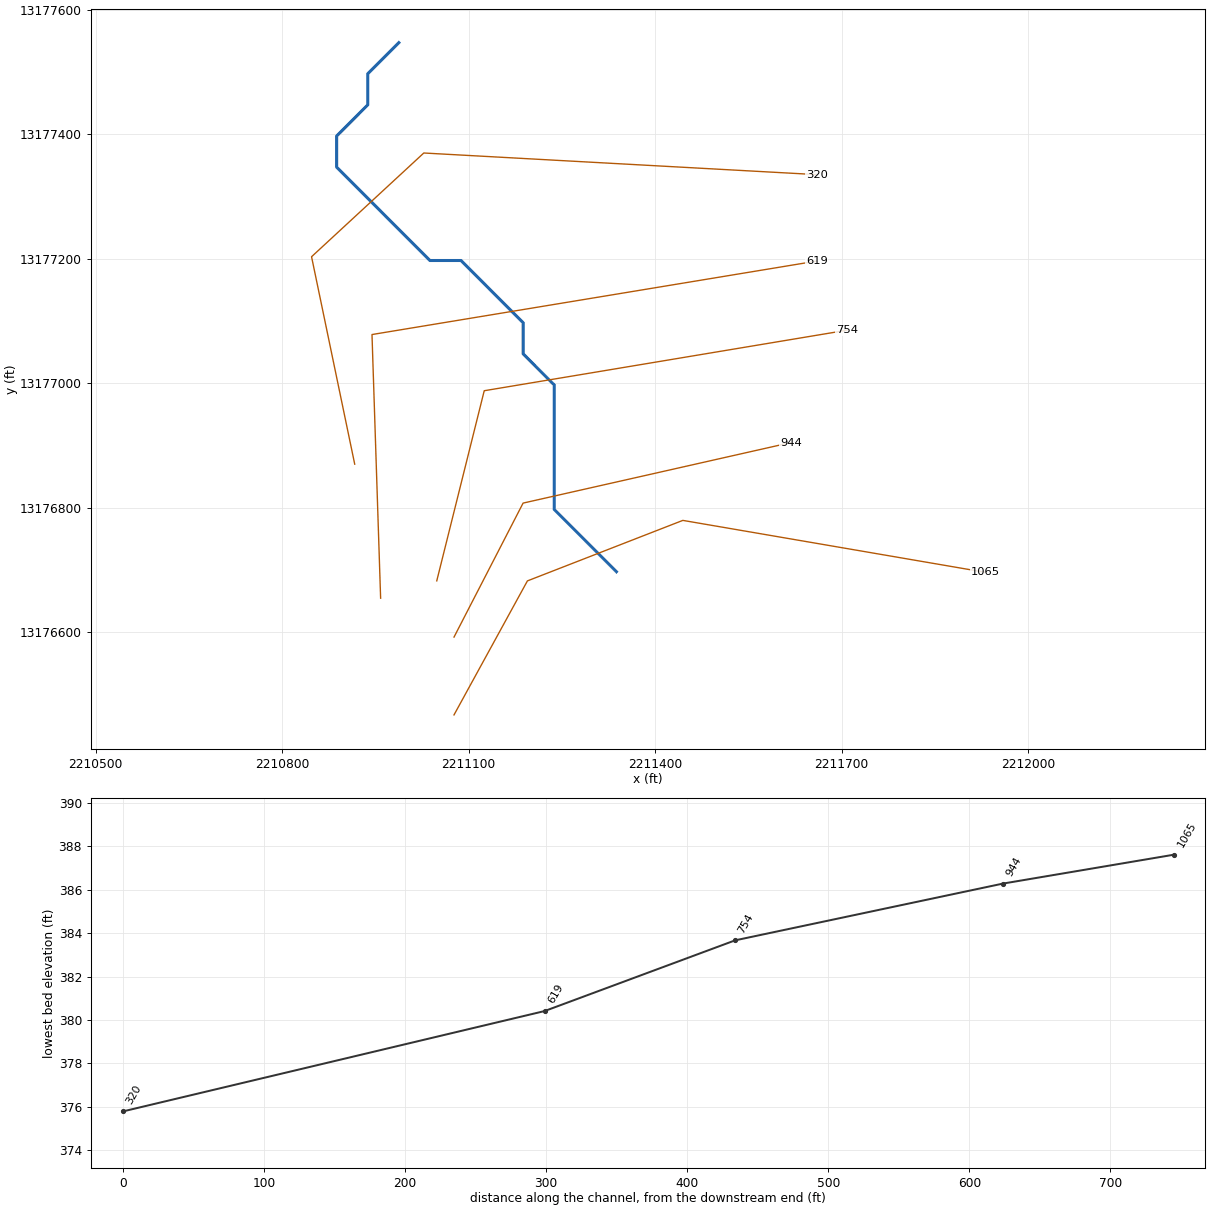
--- UNT 108 IN LACR.prj (project) ---

Proj Title=UNT 108 IN LACR Base Level Engineering
Current Plan=p01
Default Exp/Contr=0.3,0.1
English Units
Geom File=g01
Flow File=f01
Plan File=p01
BEGIN DESCRIPTION:
UNT 108 IN LACR
END DESCRIPTION:

--- UNT 108 IN LACR.p01 (plan) ---

Plan Title=Multiple Run
Short Identifier=Multiple
Geom File=g01
Flow File=f01
Subcritical Flow
K Sum by GR= 0
Std Step Tol= 0.01
Critical Tol= 0.01
Num of Std Step Trials= 20
Max Error Tol= 0.3
Flow Tol Ratio= 0.001
Split Flow NTrial= 30
Split Flow Tol= 0.02
Split Flow Ratio= 0.02
Log Output Level= 0
Friction Slope Method= 1
Unsteady Friction Slope Method= 2
Unsteady Bridges Friction Slope Method= 1
Parabolic Critical Depth
Global Vel Dist=  1 , 1 , 1
Global Log Level= 0
CheckData=True
Encroach Param= -1, 0, 0, 0
BEGIN DESCRIPTION:
Multiple Run
END DESCRIPTION:

--- UNT 108 IN LACR.f01 (steady flow) ---

Flow Title=Multiple
Number of Profiles=7
Profile Names=10-year,25-year,50-year,1pct_min,100-year,1pct_plu,500-year
River Rch & RM= UNT 108 IN LACR,Reach-1,1065
      50      64      74      63      86     116     117
Boundary for River Rch & Prof#=UNT 108 IN LACR,Reach-1,1
Up Type=0
Dn Type=3
Dn Slope=0.005
Boundary for River Rch & Prof#=UNT 108 IN LACR,Reach-1,2
Up Type=0
Dn Type=3
Dn Slope=0.005
Boundary for River Rch & Prof#=UNT 108 IN LACR,Reach-1,3
Up Type=0
Dn Type=3
Dn Slope=0.005
Boundary for River Rch & Prof#=UNT 108 IN LACR,Reach-1,4
Up Type=0
Dn Type=3
Dn Slope=0.005
Boundary for River Rch & Prof#=UNT 108 IN LACR,Reach-1,5
Up Type=0
Dn Type=3
Dn Slope=0.005
Boundary for River Rch & Prof#=UNT 108 IN LACR,Reach-1,6
Up Type=0
Dn Type=3
Dn Slope=0.005
Boundary for River Rch & Prof#=UNT 108 IN LACR,Reach-1,7
Up Type=0
Dn Type=3
Dn Slope=0.005

--- UNT 108 IN LACR.g01 (geometry) ---

Geom Title=Existing Conditions

River Reach=UNT 108 IN LACR,Reach-1
Reach XY= 19
      2211337.72     13176696.85      2211287.72     13176746.86
      2211237.72     13176796.85      2211237.72     13176846.85
      2211237.72     13176896.86      2211237.72     13176946.85
      2211237.72     13176996.85      2211187.72     13177046.86
      2211187.72     13177096.85      2211137.72     13177146.85
      2211087.72     13177196.85      2211037.72     13177196.85
      2210987.72     13177246.85      2210937.72     13177296.85
      2210887.72     13177346.85      2210887.72     13177396.86
      2210937.72     13177446.85      2210937.72     13177496.85
      2210987.72     13177546.86

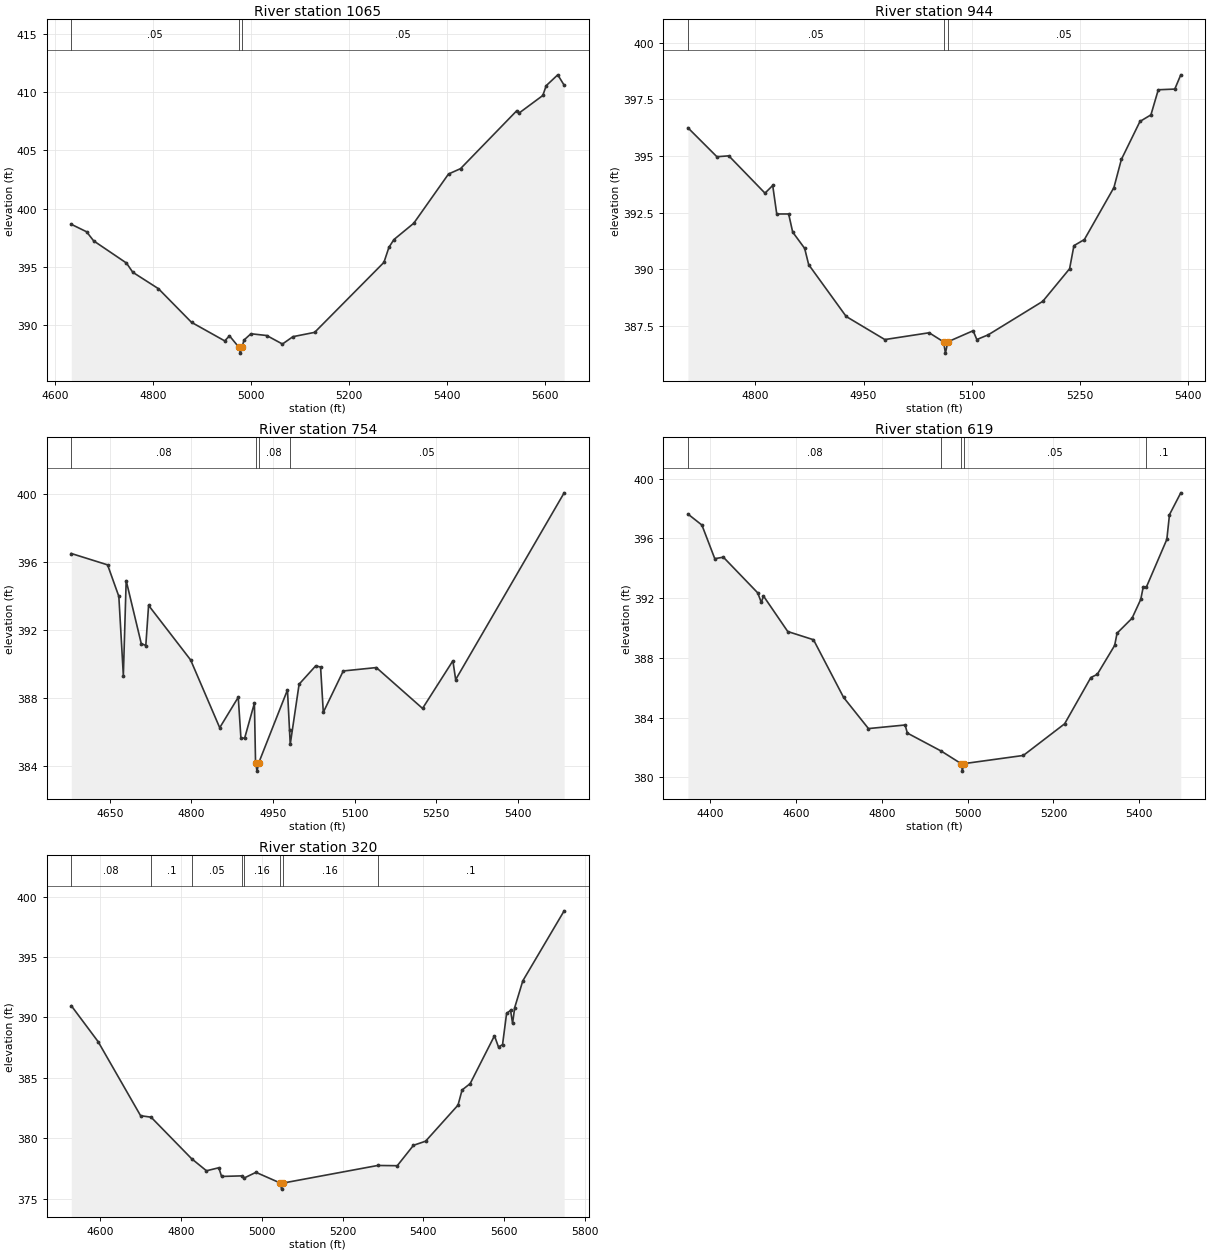
Type RM Length L Ch R = 1,1065,121,121,121
BEGIN DESCRIPTION:
UNT 108 IN LACR 2.0
END DESCRIPTION:
XS GIS Cut Line= 4
      2211076.47     13176466.75      2211194.55     13176682.07
      2211444.55     13176779.29      2211930.65     13176695.96
#Sta/Elev= 30
  4632.4  398.66  4663.6  398.02  4678.1  397.24  4745.1  395.34  4758.0  394.55
  4810.5  393.14  4878.0  390.26  4945.8  388.67  4955.6  389.10  4974.9  388.12
  4977.7  387.62  4980.9  388.12  4985.5  388.75  4999.4  389.28  5031.6  389.13
  5063.8  388.40  5085.2  389.03  5129.6  389.40  5271.2  395.40  5281.3  396.68
  5291.5  397.35  5332.1  398.75  5403.1  402.97  5427.7  403.43  5542.7  408.40
  5547.8  408.21  5595.8  409.70  5602.7  410.54  5626.3  411.47  5639.4  410.58
#Mann=3,-1,0
  4632.4    0.05       0  4974.9    0.03       0  4980.9    0.05       0
Bank Sta=4974.9,4980.9
Exp/Cntr=0.3,0.1

Type RM Length L Ch R = 1,944,190,190,190
BEGIN DESCRIPTION:
Mapping XS 835dacb5
END DESCRIPTION:
XS GIS Cut Line= 3
      2211076.51     13176591.82      2211187.60     13176807.07
      2211618.14     13176904.28
#Sta/Elev= 30
  4706.4  396.25  4746.6  394.97  4763.1  395.01  4813.3  393.36  4824.0  393.70
  4829.6  392.44  4846.1  392.44  4851.7  391.64  4868.3  390.92  4873.9  390.20
  4925.9  387.91  4979.5  386.89  5041.0  387.19  5060.9  386.79  5063.6  386.29
  5066.9  386.79  5102.0  387.28  5107.1  386.89  5123.0  387.10  5198.6  388.58
  5235.8  390.02  5241.8  391.04  5256.3  391.31  5297.3  393.61  5307.6  394.85
  5333.4  396.53  5348.6  396.82  5358.8  397.93  5381.7  397.96  5390.0  398.59
#Mann=3,-1,0
  4706.4    0.05       0  5060.9    0.03       0  5066.9    0.05       0
Bank Sta=5060.9,5066.9
Exp/Cntr=0.3,0.1

Type RM Length L Ch R = 1,754,135,135,135
BEGIN DESCRIPTION:
Mapping XS ba308452
END DESCRIPTION:
XS GIS Cut Line= 3
      2211048.73     13176682.11      2211125.10     13176987.62
      2211708.44     13177084.84
#Sta/Elev= 30
  4579.2  396.51  4645.9  395.84  4666.6  393.98  4674.9  389.31  4680.1  394.91
  4707.8  391.20  4716.2  391.08  4721.3  393.45  4798.6  390.23  4852.1  386.23
  4886.2  388.03  4891.1  385.62  4898.0  385.62  4915.9  387.68  4918.0  384.17
  4920.7  383.67  4924.0  384.17  4976.7  388.46  4980.5  386.07  4981.8  385.25
  4998.1  388.80  5028.6  389.88  5037.6  389.81  5042.6  387.14  5079.3  389.58
  5140.1  389.78  5225.1  387.37  5280.9  390.18  5286.0  389.07  5485.5  400.09
#Mann=4,-1,0
  4579.2    0.08       0  4918.0    0.04       0  4924.0    0.08       0
  4980.5    0.05       0
Bank Sta=4918,4924
Exp/Cntr=0.3,0.1

Type RM Length L Ch R = 1,619,299,299,299
BEGIN DESCRIPTION:
Mapping XS a89a80a9
END DESCRIPTION:
XS GIS Cut Line= 3
      2210958.44     13176654.26      2210944.55     13177077.90
      2211659.81     13177195.95
#Sta/Elev= 30
  4348.1  397.63  4380.7  396.89  4410.7  394.64  4430.7  394.74  4510.8  392.35
  4519.2  391.71  4524.2  392.14  4580.8  389.76  4640.8  389.21  4710.9  385.35
  4768.9  383.26  4854.4  383.50  4859.5  382.96  4938.7  381.75  4985.0  380.91
  4987.8  380.41  4991.0  380.91  5129.9  381.46  5226.2  383.58  5287.3  386.68
  5302.2  386.89  5342.8  388.83  5348.4  389.65  5383.3  390.65  5403.6  391.91
  5409.5  392.76  5416.9  392.75  5464.4  395.93  5470.6  397.59  5496.9  399.05
#Mann=5,-1,0
  4348.1    0.08       0  4938.7    0.05       0  4985.0    0.03       0
  4991.0    0.05       0  5416.9     0.1       0
Bank Sta=4985,4991
Exp/Cntr=0.3,0.1

Type RM Length L Ch R = 1,320,0,0,0
BEGIN DESCRIPTION:
UNT 108 IN LACR 1.0
END DESCRIPTION:
XS GIS Cut Line= 4
      2210916.76     13176869.61      2210847.33     13177202.90
      2211027.88     13177369.57      2211659.87     13177334.84
#Sta/Elev= 30
  4529.1  390.97  4595.3  388.00  4700.5  381.86  4726.4  381.74  4826.7  378.30
  4863.4  377.30  4894.0  377.55  4900.8  376.83  4952.4  376.88  4955.9  376.69
  4985.9  377.17  5046.4  376.28  5049.1  375.78  5052.4  376.28  5287.2  377.74
  5335.4  377.72  5375.5  379.41  5405.5  379.75  5485.7  382.74  5495.7  383.99
  5515.7  384.52  5575.8  388.48  5585.8  387.55  5595.8  387.75  5605.8  390.33
  5615.6  390.59  5620.6  389.51  5625.9  390.82  5645.9  393.03  5748.2  398.83
#Mann=8,-1,0
  4529.1    0.08       0  4726.4     0.1       0  4826.7    0.05       0
  4952.4     0.1       0  4955.9    0.16       0  5046.4    0.07       0
  5052.4    0.16       0  5287.2     0.1       0
Bank Sta=5046.4,5052.4
Exp/Cntr=0.3,0.1

Chan Stop Cuts=-1