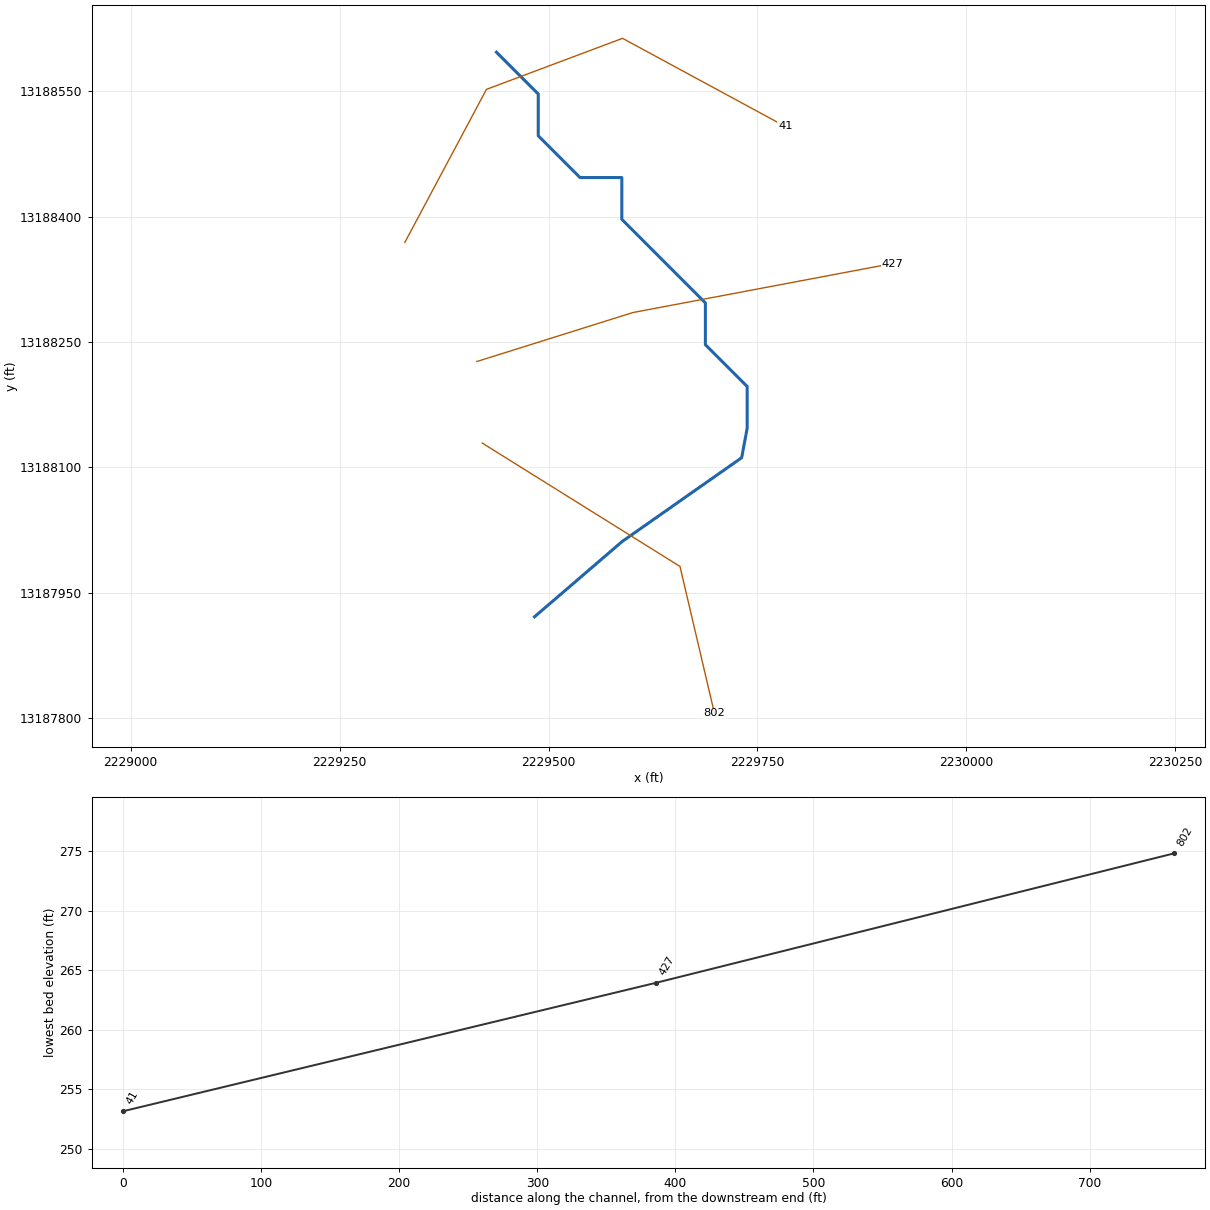
--- UNT 110 IN LACR.prj (project) ---

Proj Title=UNT 110 IN LACR Base Level Engineering
Current Plan=p01
Default Exp/Contr=0.3,0.1
English Units
Geom File=g01
Flow File=f01
Plan File=p01
BEGIN DESCRIPTION:
UNT 110 IN LACR
END DESCRIPTION:

--- UNT 110 IN LACR.p01 (plan) ---

Plan Title=Multiple Run
Short Identifier=Multiple
Geom File=g01
Flow File=f01
Subcritical Flow
K Sum by GR= 0
Std Step Tol= 0.01
Critical Tol= 0.01
Num of Std Step Trials= 20
Max Error Tol= 0.3
Flow Tol Ratio= 0.001
Split Flow NTrial= 30
Split Flow Tol= 0.02
Split Flow Ratio= 0.02
Log Output Level= 0
Friction Slope Method= 1
Unsteady Friction Slope Method= 2
Unsteady Bridges Friction Slope Method= 1
Parabolic Critical Depth
Global Vel Dist=  1 , 1 , 1
Global Log Level= 0
CheckData=True
Encroach Param= -1, 0, 0, 0
BEGIN DESCRIPTION:
Multiple Run
END DESCRIPTION:

--- UNT 110 IN LACR.f01 (steady flow) ---

Flow Title=Multiple
Number of Profiles=7
Profile Names=10-year,25-year,50-year,1pct_min,100-year,1pct_plu,500-year
River Rch & RM= UNT 110 IN LACR,Reach-1,802
      87     115     137     121     164     222     236
Boundary for River Rch & Prof#=UNT 110 IN LACR,Reach-1,1
Up Type=0
Dn Type=3
Dn Slope=0.005
Boundary for River Rch & Prof#=UNT 110 IN LACR,Reach-1,2
Up Type=0
Dn Type=3
Dn Slope=0.005
Boundary for River Rch & Prof#=UNT 110 IN LACR,Reach-1,3
Up Type=0
Dn Type=3
Dn Slope=0.005
Boundary for River Rch & Prof#=UNT 110 IN LACR,Reach-1,4
Up Type=0
Dn Type=3
Dn Slope=0.005
Boundary for River Rch & Prof#=UNT 110 IN LACR,Reach-1,5
Up Type=0
Dn Type=3
Dn Slope=0.005
Boundary for River Rch & Prof#=UNT 110 IN LACR,Reach-1,6
Up Type=0
Dn Type=3
Dn Slope=0.005
Boundary for River Rch & Prof#=UNT 110 IN LACR,Reach-1,7
Up Type=0
Dn Type=3
Dn Slope=0.005

--- UNT 110 IN LACR.g01 (geometry) ---

Geom Title=Existing Conditions

River Reach=UNT 110 IN LACR,Reach-1
Reach XY= 14
      2229483.17     13187921.15      2229588.23     13188011.39
      2229731.14     13188111.58      2229737.72     13188146.85
      2229737.72     13188196.86      2229687.72     13188246.85
      2229687.72     13188296.85      2229637.72     13188346.85
      2229587.72     13188396.86      2229587.72     13188446.85
      2229537.72     13188446.85      2229487.72     13188496.85
      2229487.72     13188546.86      2229437.72     13188596.85

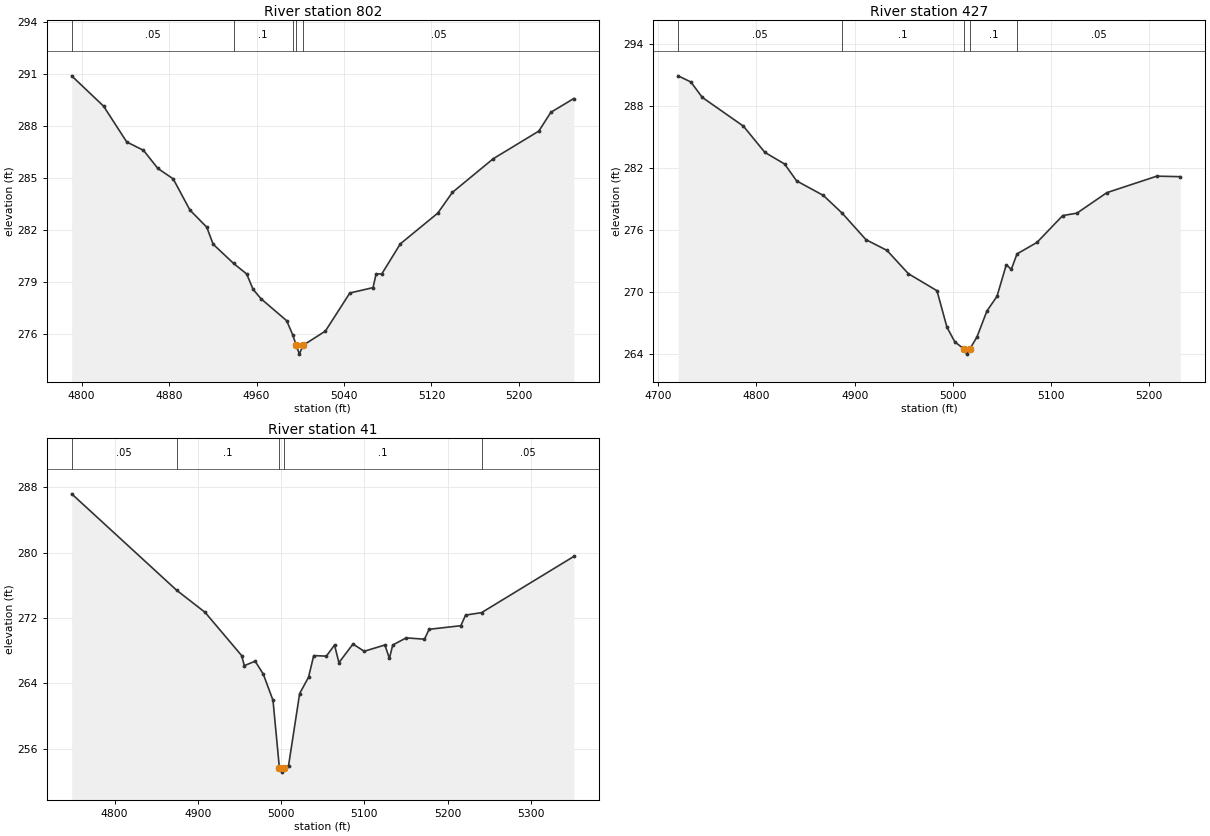
Type RM Length L Ch R = 1,802,375,375,375
BEGIN DESCRIPTION:
UNT 110 IN LACR 1.0
END DESCRIPTION:
XS GIS Cut Line= 3
      2229420.79     13188129.06      2229657.33     13187981.49
      2229698.58     13187805.66
#Sta/Elev= 30
  4790.9  290.89  4820.1  289.14  4841.3  287.07  4856.6  286.59  4869.8  285.54
  4883.8  284.94  4899.1  283.14  4914.5  282.15  4920.3  281.17  4939.0  280.06
  4951.0  279.45  4956.9  278.56  4964.1  278.02  4987.6  276.75  4993.1  275.94
  4996.4  275.32  4999.2  274.82  5002.4  275.32  5023.0  276.15  5045.4  278.35
  5066.6  278.66  5069.4  279.45  5074.6  279.45  5091.6  281.19  5125.8  282.96
  5139.2  284.16  5176.5  286.10  5218.3  287.70  5229.2  288.78  5250.3  289.58
#Mann=5,-1,0
  4790.9    0.05       0  4939.0     0.1       0  4993.1    0.05       0
  4996.4    0.03       0  5002.4    0.05       0
Bank Sta=4996.4,5002.4
Exp/Cntr=0.3,0.1

Type RM Length L Ch R = 1,427,386,386,386
BEGIN DESCRIPTION:
Mapping XS 51184556
END DESCRIPTION:
XS GIS Cut Line= 3
      2229414.29     13188226.72      2229600.91     13188285.31
      2229911.23     13188343.90
#Sta/Elev= 30
  4720.2  290.93  4733.2  290.33  4744.8  288.84  4786.7  286.05  4808.5  283.51
  4828.6  282.38  4840.9  280.74  4868.1  279.33  4887.4  277.60  4911.5  275.04
  4932.9  274.00  4954.7  271.74  4983.8  270.09  4994.0  266.54  5002.0  265.13
  5011.3  264.44  5014.1  263.94  5017.3  264.44  5024.5  265.60  5034.7  268.13
  5044.9  269.54  5054.4  272.61  5059.5  272.16  5065.3  273.66  5085.6  274.77
  5111.9  277.38  5126.3  277.61  5156.8  279.60  5207.7  281.20  5231.6  281.15
#Mann=5,-1,0
  4720.2    0.05       0  4887.4     0.1       0  5011.3    0.07       0
  5017.3     0.1       0  5065.3    0.05       0
Bank Sta=5011.3,5017.3
Exp/Cntr=0.3,0.1

Type RM Length L Ch R = 1,41,0,0,0
BEGIN DESCRIPTION:
UNT 110 IN LACR 2.0
END DESCRIPTION:
XS GIS Cut Line= 4
      2229328.03     13188369.15      2229425.75     13188552.37
      2229588.62     13188613.45      2229783.38     13188507.95
#Sta/Elev= 30
  4748.5  287.20  4874.6  275.40  4908.7  272.70  4952.6  267.41  4955.9  266.17
  4968.9  266.72  4978.7  265.12  4990.3  261.93  4998.0  253.64  5000.7  253.14
  5004.0  253.64  5009.0  253.94  5022.3  262.75  5033.0  264.76  5039.2  267.40
  5054.4  267.34  5064.2  268.69  5069.5  266.54  5086.4  268.82  5099.8  267.93
  5124.7  268.70  5130.1  267.05  5134.1  268.70  5150.3  269.57  5172.2  269.41
  5177.8  270.62  5215.9  271.06  5221.6  272.36  5240.8  272.66  5351.6  279.54
#Mann=5,-1,0
  4748.5    0.05       0  4874.6     0.1       0  4998.0    0.07       0
  5004.0     0.1       0  5240.8    0.05       0
Bank Sta=4998,5004
Exp/Cntr=0.3,0.1

Chan Stop Cuts=-1