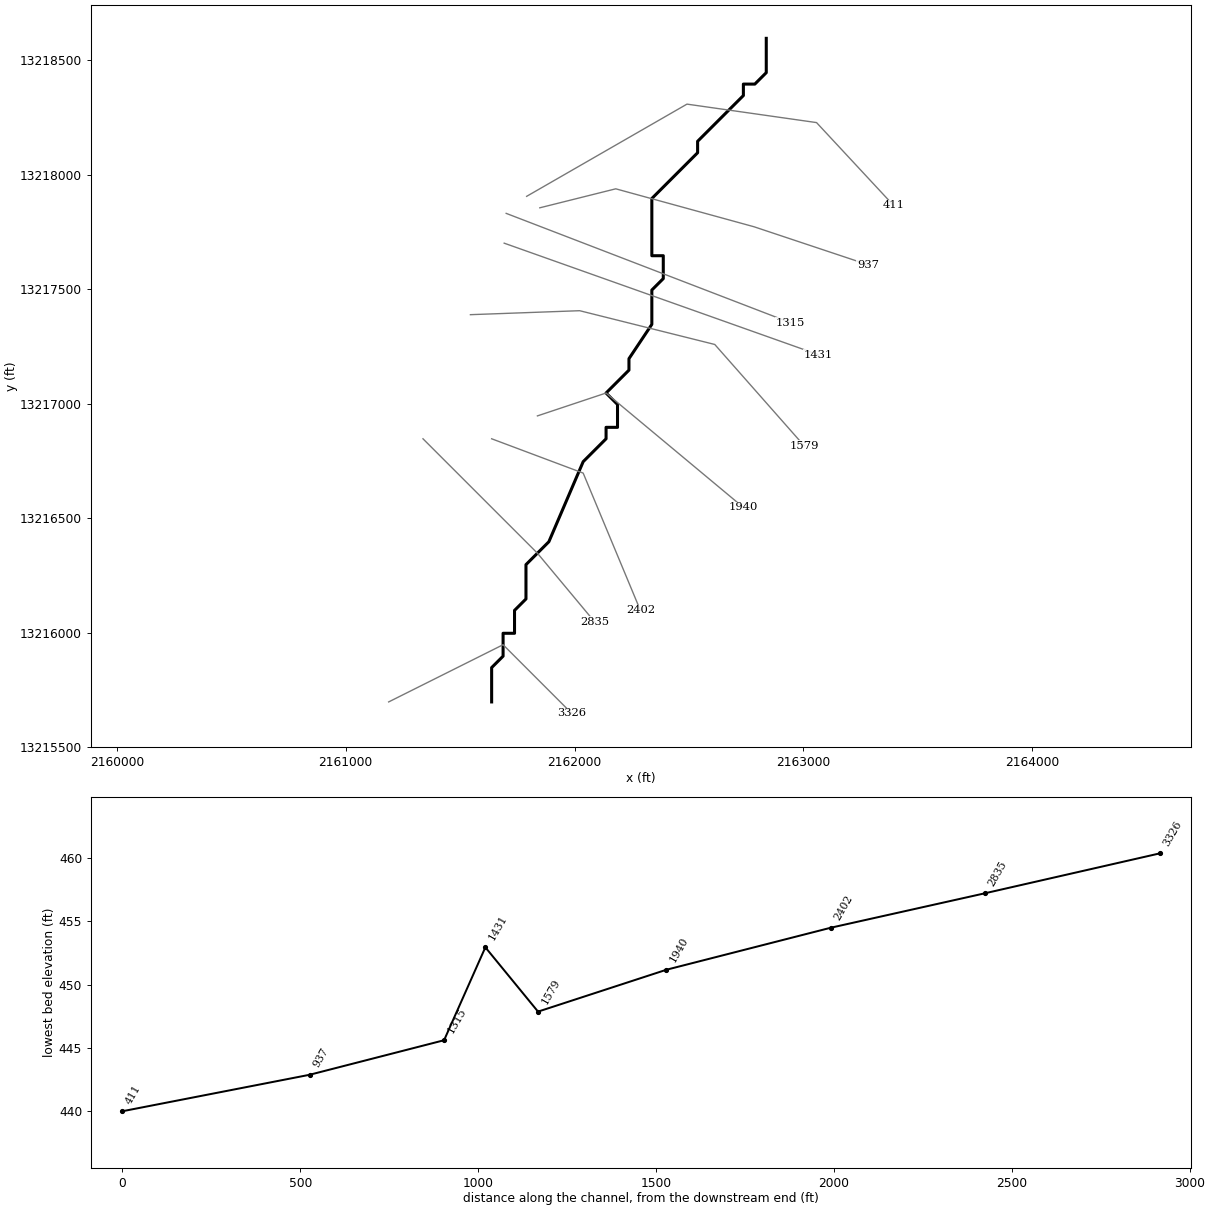
--- UNT 113 IN LACR.prj (project) ---

Proj Title=UNT 113 IN LACR Base Level Engineering
Current Plan=p01
Default Exp/Contr=0.3,0.1
English Units
Geom File=g01
Flow File=f01
Plan File=p01
Y Axis Title=Elevation
X Axis Title(PF)=Main Channel Distance
X Axis Title(XS)=Station
BEGIN DESCRIPTION:
UNT 113 IN LACR
END DESCRIPTION:
DSS Export Rating Curves= 0
DSS Export Rating Curve Sorted= 0
DSS Export Volume Flow Curves= 0
DXF OffsetX= 0
DXF OffsetY= 0
DXF ScaleX= 1
DXF ScaleY= 10

--- UNT 113 IN LACR.p01 (plan) ---

Plan Title=Multiple Run
Short Identifier=Multiple
Geom File=g01
Flow File=f01
Subcritical Flow
K Sum by GR= 0
Std Step Tol= 0.01
Critical Tol= 0.01
Num of Std Step Trials= 20
Max Error Tol= 0.3
Flow Tol Ratio= 0.001
Split Flow NTrial= 30
Split Flow Tol= 0.02
Split Flow Ratio= 0.02
Log Output Level= 0
Friction Slope Method= 1
Unsteady Friction Slope Method= 2
Unsteady Bridges Friction Slope Method= 1
Parabolic Critical Depth
Global Vel Dist=  1 , 1 , 1
Global Log Level= 0
CheckData=True
Encroach Param= -1, 0, 0, 0
BEGIN DESCRIPTION:
Multiple Run
END DESCRIPTION:

--- UNT 113 IN LACR.f01 (steady flow) ---

Flow Title=Multiple
Number of Profiles=7
Profile Names=10-year,25-year,50-year,1pct_min,100-year,1pct_plu,500-year
River Rch & RM= UNT 113 IN LACR,Reach-1,3326
     131     178     216     194     262     354     391
Boundary for River Rch & Prof#=UNT 113 IN LACR,Reach-1,1
Up Type=0
Dn Type=3
Dn Slope=0.005
Boundary for River Rch & Prof#=UNT 113 IN LACR,Reach-1,2
Up Type=0
Dn Type=3
Dn Slope=0.005
Boundary for River Rch & Prof#=UNT 113 IN LACR,Reach-1,3
Up Type=0
Dn Type=3
Dn Slope=0.005
Boundary for River Rch & Prof#=UNT 113 IN LACR,Reach-1,4
Up Type=0
Dn Type=3
Dn Slope=0.005
Boundary for River Rch & Prof#=UNT 113 IN LACR,Reach-1,5
Up Type=0
Dn Type=3
Dn Slope=0.005
Boundary for River Rch & Prof#=UNT 113 IN LACR,Reach-1,6
Up Type=0
Dn Type=3
Dn Slope=0.005
Boundary for River Rch & Prof#=UNT 113 IN LACR,Reach-1,7
Up Type=0
Dn Type=3
Dn Slope=0.005

--- UNT 113 IN LACR.g01 (geometry) ---

Geom Title=Existing Conditions
Program Version=4.10

River Reach=UNT 113 IN LACR ,Reach-1
Reach XY= 30
      2161637.72     13215696.85      2161637.72     13215846.85
      2161687.72     13215896.85      2161687.72     13215996.85
      2161737.72     13215996.85      2161737.72     13216096.86
      2161787.72     13216146.85      2161787.72     13216296.85
      2161887.72     13216396.85      2162037.72     13216746.86
      2162137.72     13216846.85      2162137.72     13216896.85
      2162187.72     13216896.85      2162187.72     13216996.85
      2162137.72     13217046.85      2162237.72     13217146.85
      2162237.72     13217196.85      2162337.72     13217346.85
      2162337.72     13217496.85      2162387.72     13217546.85
      2162387.72     13217646.85      2162337.72     13217646.85
      2162337.72     13217896.86      2162537.72     13218096.85
      2162537.72     13218146.85      2162737.72     13218346.85
      2162737.72     13218396.86      2162787.72     13218396.86
      2162837.72     13218446.85      2162837.72     13218596.85

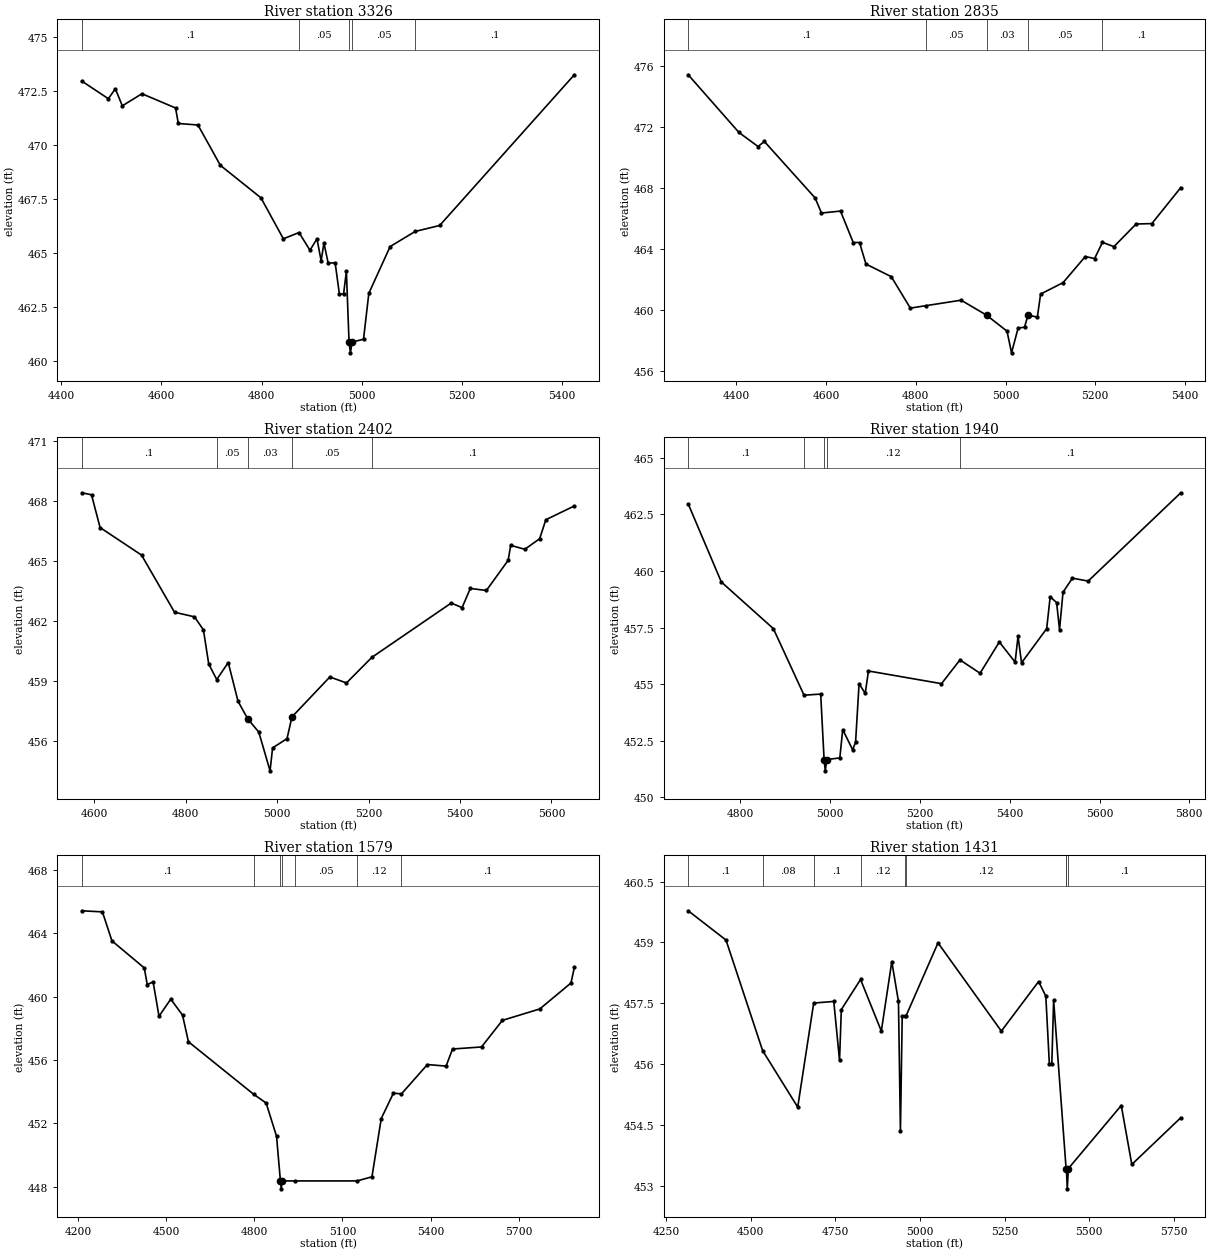
Type RM Length L Ch R = 1 ,3326    ,491,491,491
BEGIN DESCRIPTION:
UNT 113 IN LACR 6.0
END DESCRIPTION:
XS GIS Cut Line= 3
      2161187.74     13215696.86      2161687.72     13215946.86
      2161987.75     13215646.83
#Sta/Elev= 30
    4441  472.97  4494.1  472.15  4508.1  472.61    4522  471.82  4561.2  472.38
  4628.3  471.72  4633.8     471    4673  470.93  4717.7  469.06  4798.8  467.55
  4843.5  465.65  4874.7  465.94  4896.6  465.12  4910.6  465.65  4918.9  464.63
  4924.5  465.45  4932.9  464.53  4946.9  464.53  4955.3  463.09  4963.7  463.09
  4969.3  464.14  4974.6  460.86  4977.4  460.36  4980.6  460.86  5003.5  460.99
  5014.1  463.12  5056.6  465.29  5106.5  465.99  5155.6  466.27  5424.3  473.26
#Mann= 5 ,-1 , 0
    4441      .1       0  4874.7     .05       0  4974.6     .03       0
  4980.6     .05       0  5106.5      .1       0
Bank Sta=4974.6,4980.6
XS Rating Curve= 0 ,0
Exp/Cntr=0.3,0.1

Type RM Length L Ch R = 1 ,2835    ,433,433,433
BEGIN DESCRIPTION:
UNT 113 IN LACR 5.0
END DESCRIPTION:
XS GIS Cut Line= 3
      2161337.73     13216846.85      2161837.72     13216346.85
      2162087.71     13216046.86
#Sta/Elev= 30
  4292.9  475.43    4406  471.65  4448.5  470.73  4462.6  471.06  4575.7  467.36
  4589.9  466.37  4632.3   466.5  4660.6  464.44  4674.7  464.44  4688.9  463.03
  4745.4   462.2  4787.9  460.14  4822.4   460.3    4901  460.66  4957.6  459.68
  5003.3  458.63  5013.4  457.21    5028  458.83  5042.3  458.89  5050.1  459.68
  5070.9  459.55  5078.1  461.06  5128.2  461.81  5177.7  463.52  5198.5  463.39
  5215.9  464.45  5241.5  464.17  5290.9  465.65  5326.1  465.68  5390.5  468.04
#Mann= 5 ,-1 , 0
  4292.9      .1       0  4822.4     .05       0  4957.6     .03       0
  5050.1     .05       0  5215.9      .1       0
Bank Sta=4957.6,5050.1
XS Rating Curve= 0 ,0
Exp/Cntr=0.3,0.1

Type RM Length L Ch R = 1 ,2402    ,462,462,462
BEGIN DESCRIPTION:
UNT 113 IN LACR 4.0
END DESCRIPTION:
XS GIS Cut Line= 3
      2161637.72     13216846.85      2162037.72     13216696.85
      2162287.72     13216096.85
#Sta/Elev= 30
  4572.8  468.41  4594.2  468.31  4612.9  466.67  4703.6  465.29  4775.7  462.43
  4819.3   462.2  4838.9  461.55  4850.5  459.84    4868  459.06  4893.2  459.91
  4914.6  457.97  4935.9  457.09    4960  456.43  4984.6  454.49  4990.2  455.64
  5021.7   456.1  5032.5  457.19  5115.4  459.19  5151.7  458.89  5207.2  460.17
  5380.8  462.89  5404.6  462.66  5422.5  463.62  5457.7  463.52  5505.4  465.03
  5510.8  465.78  5541.7  465.58  5574.2  466.11  5587.7  467.06    5650  467.75
#Mann= 5 ,-1 , 0
  4572.8      .1       0    4868     .05       0  4935.9     .03       0
  5032.5     .05       0  5207.2      .1       0
Bank Sta=4935.9,5032.5
XS Rating Curve= 0 ,0
Exp/Cntr=0.3,0.1

Type RM Length L Ch R = 1 ,1940    ,361,361,361
BEGIN DESCRIPTION:
UNT 113 IN LACR 3.0
END DESCRIPTION:
XS GIS Cut Line= 3
      2161837.75     13216946.86      2162137.72     13217046.85
       2162737.7     13216546.87
#Sta/Elev= 30
  4683.8  462.96  4757.6  459.51  4873.5  457.45  4941.8  454.51  4978.9  454.56
  4986.5  451.67  4989.2  451.17  4992.5  451.67  5021.5  451.74    5028  452.99
  5050.1   452.1  5056.6  452.43  5064.4  455.02  5078.1  454.59  5085.3  455.58
    5248  455.02  5289.2  456.07  5333.9  455.48  5376.8  456.86    5412  455.97
  5418.5  457.12  5426.3  455.94  5482.3  457.45  5490.1  458.86  5504.4   458.6
  5510.9  457.41  5518.7  459.06  5539.6  459.68  5574.7  459.55    5781  463.45
#Mann= 5 ,-1 , 0
  4683.8      .1       0  4941.8     .12       0  4986.5     .07       0
  4992.5     .12       0  5289.2      .1       0
Bank Sta=4986.5,4992.5
XS Rating Curve= 0 ,0
Exp/Cntr=0.3,0.1

Type RM Length L Ch R = 1 ,1579    ,148,148,148
BEGIN DESCRIPTION:
UNT 113 IN LACR 2.0
END DESCRIPTION:
XS GIS Cut Line= 4
      2161544.98      13217389.2      2162022.43     13217406.56
      2162612.71     13217258.99      2163003.06      13216816.6
#Sta/Elev= 30
    4213  465.42  4283.4  465.35  4315.8  463.52  4425.9  461.81  4435.9  460.76
  4455.9  460.93  4475.9  458.76  4515.9  459.84    4556  458.83    4576  457.15
  4797.5  453.84  4840.5  453.28  4875.9  451.18  4889.1  448.36  4891.8  447.86
  4895.1  448.36  4937.9  448.36  5150.1  448.36  5200.6  448.62  5232.2   452.3
  5273.5   453.9  5301.1  453.86  5389.3  455.71  5452.9  455.61  5474.7  456.69
  5573.4  456.82  5644.5   458.5  5771.6  459.22  5877.9  460.86  5889.2  461.84
#Mann= 7 ,-1 , 0
    4213      .1       0  4797.5     .12       0  4889.1    .033       0
  4895.1     .12       0  4937.9     .05       0  5150.1     .12       0
  5301.1      .1       0
Bank Sta=4889.1,4895.1
XS Rating Curve= 0 ,0
Exp/Cntr=0.3,0.1

Type RM Length L Ch R = 1 ,1431    ,116,116,116
BEGIN DESCRIPTION:
Mapping XS e7faf034
END DESCRIPTION:
XS GIS Cut Line= 2
      2161692.57      13217701.7      2163063.35     13217215.05
#Sta/Elev= 30
  4315.4  459.78    4427  459.06  4535.2  456.34  4638.8  454.95    4686  457.51
  4745.3  457.55  4762.3   456.1  4767.6  457.35  4824.4  458.09  4885.7  456.82
  4916.6  458.53  4936.3  457.55  4942.1  454.36  4947.4  457.19  4956.3  457.19
  4957.9  457.18  5053.1  458.99  5240.1  456.82  5350.2  458.04  5371.4  457.68
    5382     456  5389.1     456  5394.5  457.58  5431.3  453.44  5432.1  453.44
  5434.8  452.94  5438.1  453.44  5594.2  454.99  5625.4  453.54    5770  454.69
#Mann= 9 ,-1 , 0
  4315.4      .1       0  4535.2     .08       0    4686      .1       0
  4824.4     .12       0  4956.3     .08       0  4957.9     .12       0
  5431.3      .1       0  5432.1     .07       0  5438.1      .1       0
Bank Sta=5432.1,5438.1
XS Rating Curve= 0 ,0
Exp/Cntr=0.3,0.1

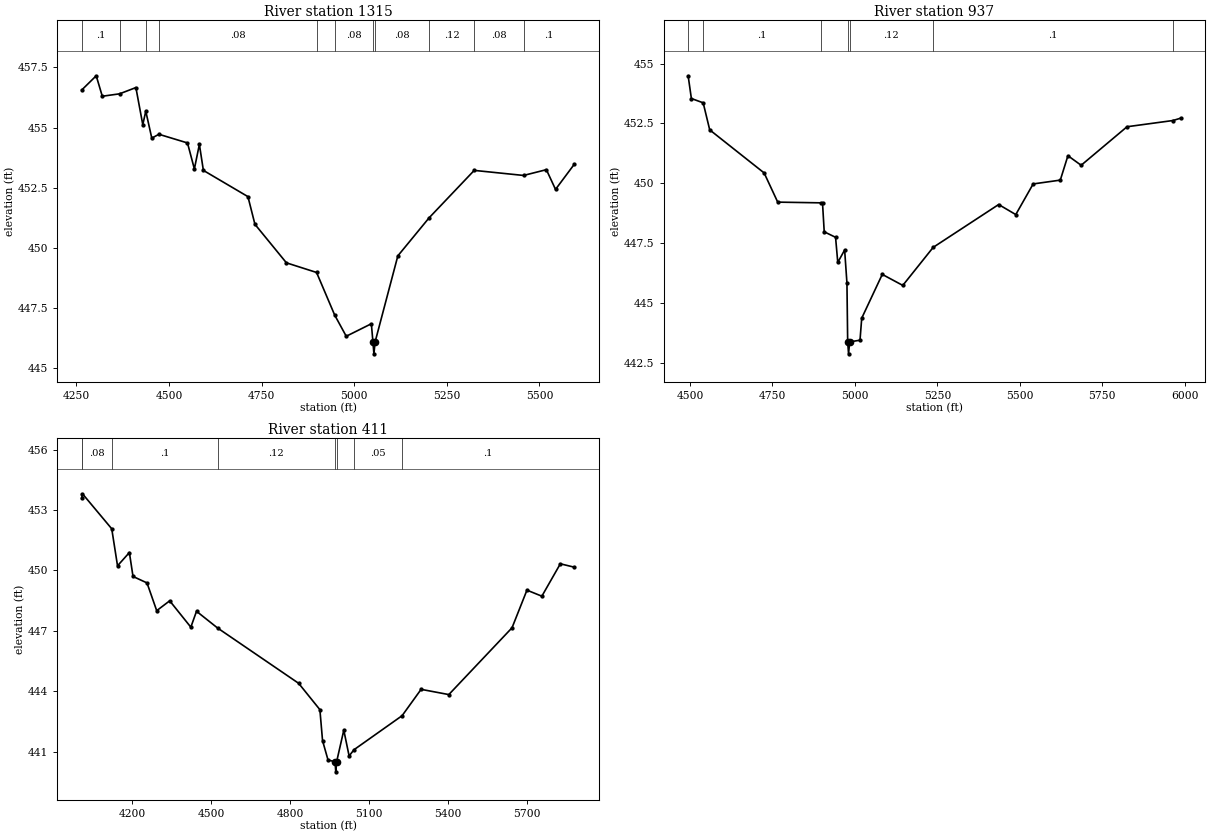
Type RM Length L Ch R = 1 ,1315    ,378,378,378
BEGIN DESCRIPTION:
Mapping XS e65c86f2
END DESCRIPTION:
XS GIS Cut Line= 2
      2161701.24     13217831.91      2162942.59     13217354.47
#Sta/Elev= 30
  4264.5  456.56  4303.6  457.15    4320   456.3  4366.5   456.4  4410.7  456.66
  4429.3  455.12  4437.4  455.68  4453.6  454.56  4472.9  454.72    4550  454.36
  4568.6  453.28  4582.1   454.3  4592.9  453.22  4713.2  452.13  4732.1  450.98
  4817.1  449.38  4898.5  448.98  4947.4  447.21  4978.6  446.33  5046.4  446.85
  5050.6   446.1  5053.3   445.6  5056.6   446.1  5117.9  449.67  5202.3  451.25
  5324.1  453.22  5457.3  453.01  5518.9  453.25  5543.6  452.43  5594.5  453.48
#Mann= 11 ,-1 , 0
  4264.5      .1       0  4366.5     .08       0  4437.4      .1       0
  4472.9     .08       0  4898.5     .12       0  4947.4     .08       0
  5050.6     .07       0  5056.6     .08       0  5202.3     .12       0
  5324.1     .08       0  5457.3      .1       0
Bank Sta=5050.6,5056.6
XS Rating Curve= 0 ,0
Exp/Cntr=0.3,0.1

Type RM Length L Ch R = 1 ,937     ,526,526,526
BEGIN DESCRIPTION:
Mapping XS 7b534979
END DESCRIPTION:
XS GIS Cut Line= 4
      2161848.17     13217856.26      2162180.07     13217939.23
      2162784.53      13217773.3      2163282.36     13217607.36
#Sta/Elev= 30
  4494.4  454.49  4504.2  453.54    4540  453.36  4559.8  452.23  4724.8  450.43
    4766  449.21    4897  449.18  4901.8  449.18    4907  447.97  4941.4  447.74
  4948.1  446.69  4968.9  447.21  4975.9  445.83  4978.1  443.37  4980.8  442.87
  4984.1  443.37  5015.5  443.44  5020.7  444.36    5083  446.19  5145.2  445.73
  5237.4  447.32  5435.9  449.11  5487.8  448.69  5540.5  449.97  5622.8  450.13
  5645.9  451.15    5686  450.75  5825.1  452.36  5964.2  452.62  5988.1  452.72
#Mann= 7 ,-1 , 0
  4494.4     .08       0    4540      .1       0    4897     .12       0
  4978.1     .07       0  4984.1     .12       0  5237.4      .1       0
  5964.2     .08       0
Bank Sta=4978.1,4984.1
XS Rating Curve= 0 ,0
Exp/Cntr=0.3,0.1

Type RM Length L Ch R = 1 ,411     ,0,0,0
BEGIN DESCRIPTION:
UNT 113 IN LACR 1.0
END DESCRIPTION:
XS GIS Cut Line= 4
      2161790.64     13217906.33      2162491.18     13218309.34
      2163057.42     13218228.66      2163393.32     13217867.32
#Sta/Elev= 30
    4007  453.58  4009.8  453.81  4121.1  452.07  4143.1  450.23  4188.2  450.89
    4202   449.7  4255.2  449.38  4292.1     448  4341.5  448.49  4421.9  447.18
  4443.5  447.97  4523.5  447.14  4831.9  444.39  4912.7  443.08  4922.8  441.54
  4943.6  440.58  4970.3  440.49  4973.1  439.99  4976.3  440.49  5003.6  442.06
  5023.8  440.78  5042.5  441.09  5225.3  442.78  5297.6  444.09    5403  443.83
  5643.4  447.15  5700.1  449.02  5756.8  448.72  5827.1  450.33  5880.5  450.16
#Mann= 8 ,-1 , 0
    4007      .1       0  4009.8     .08       0  4121.1      .1       0
  4523.5     .12       0  4970.3     .07       0  4976.3     .12       0
  5042.5     .05       0  5225.3      .1       0
Bank Sta=4970.3,4976.3
XS Rating Curve= 0 ,0
Exp/Cntr=0.3,0.1

Chan Stop Cuts=-1
Use User Specified Reach Order=0
Composite Channel Slope=5