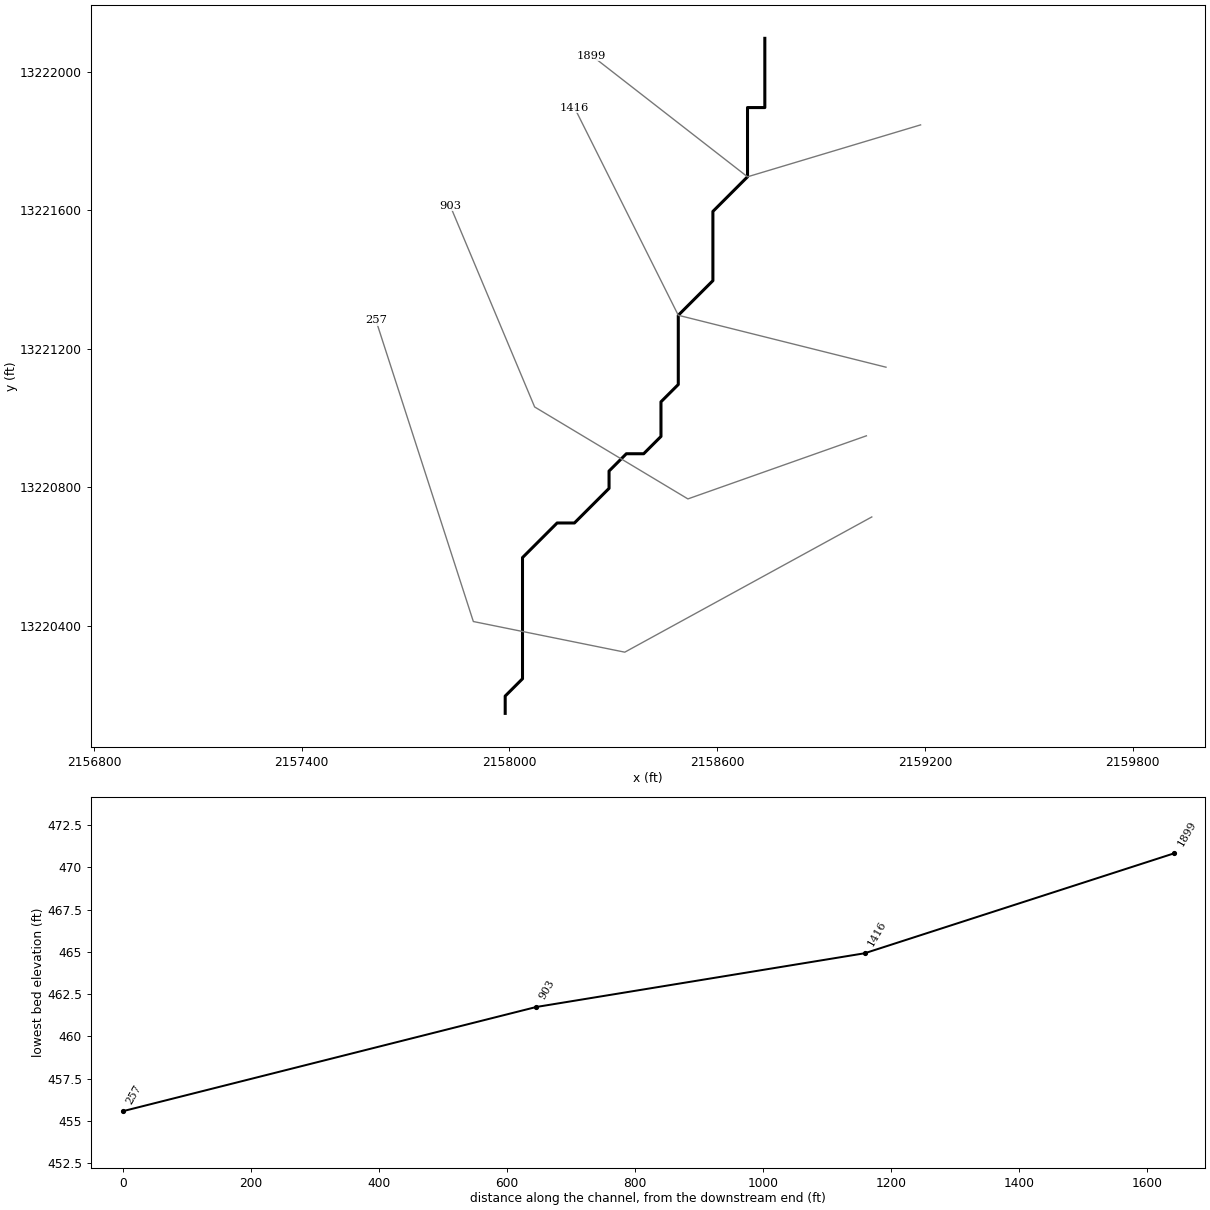
--- UNT 115 IN LACR.prj (project) ---

Proj Title=UNT 115 IN LACR Base Level Engineering
Current Plan=p01
Default Exp/Contr=0.3,0.1
English Units
Geom File=g01
Flow File=f01
Plan File=p01
BEGIN DESCRIPTION:
UNT 115 IN LACR
END DESCRIPTION:

--- UNT 115 IN LACR.p01 (plan) ---

Plan Title=Multiple Run
Short Identifier=Multiple
Geom File=g01
Flow File=f01
Subcritical Flow
K Sum by GR= 0
Std Step Tol= 0.01
Critical Tol= 0.01
Num of Std Step Trials= 20
Max Error Tol= 0.3
Flow Tol Ratio= 0.001
Split Flow NTrial= 30
Split Flow Tol= 0.02
Split Flow Ratio= 0.02
Log Output Level= 0
Friction Slope Method= 1
Unsteady Friction Slope Method= 2
Unsteady Bridges Friction Slope Method= 1
Parabolic Critical Depth
Global Vel Dist=  1 , 1 , 1
Global Log Level= 0
CheckData=True
Encroach Param= -1, 0, 0, 0
BEGIN DESCRIPTION:
Multiple Run
END DESCRIPTION:

--- UNT 115 IN LACR.f01 (steady flow) ---

Flow Title=Multiple
Number of Profiles=7
Profile Names=10-year,25-year,50-year,1pct_min,100-year,1pct_plu,500-year
River Rch & RM= UNT 115 IN LACR,Reach-1,1899
      70      92     110      96     130     176     185
Boundary for River Rch & Prof#=UNT 115 IN LACR,Reach-1,1
Up Type=0
Dn Type=3
Dn Slope=0.005
Boundary for River Rch & Prof#=UNT 115 IN LACR,Reach-1,2
Up Type=0
Dn Type=3
Dn Slope=0.005
Boundary for River Rch & Prof#=UNT 115 IN LACR,Reach-1,3
Up Type=0
Dn Type=3
Dn Slope=0.005
Boundary for River Rch & Prof#=UNT 115 IN LACR,Reach-1,4
Up Type=0
Dn Type=3
Dn Slope=0.005
Boundary for River Rch & Prof#=UNT 115 IN LACR,Reach-1,5
Up Type=0
Dn Type=3
Dn Slope=0.005
Boundary for River Rch & Prof#=UNT 115 IN LACR,Reach-1,6
Up Type=0
Dn Type=3
Dn Slope=0.005
Boundary for River Rch & Prof#=UNT 115 IN LACR,Reach-1,7
Up Type=0
Dn Type=3
Dn Slope=0.005

--- UNT 115 IN LACR.g01 (geometry) ---

Geom Title=Existing Conditions

River Reach=UNT 115 IN LACR,Reach-1
Reach XY= 24
      2158737.72     13222096.85      2158737.72     13221896.85
      2158687.72     13221896.85      2158687.72     13221696.86
      2158637.72     13221646.85      2158587.72     13221596.85
      2158587.72     13221396.85      2158537.72     13221346.86
      2158487.72     13221296.85      2158487.72     13221096.85
      2158437.72     13221046.85      2158437.72     13220946.85
      2158387.72     13220896.85      2158337.72     13220896.85
      2158287.72     13220846.86      2158287.72     13220796.85
      2158237.72     13220746.85      2158187.72     13220696.86
      2158137.72     13220696.86      2158087.72     13220646.85
      2158037.72     13220596.85      2158037.72     13220246.85
      2157987.72     13220196.86      2157987.72     13220146.85

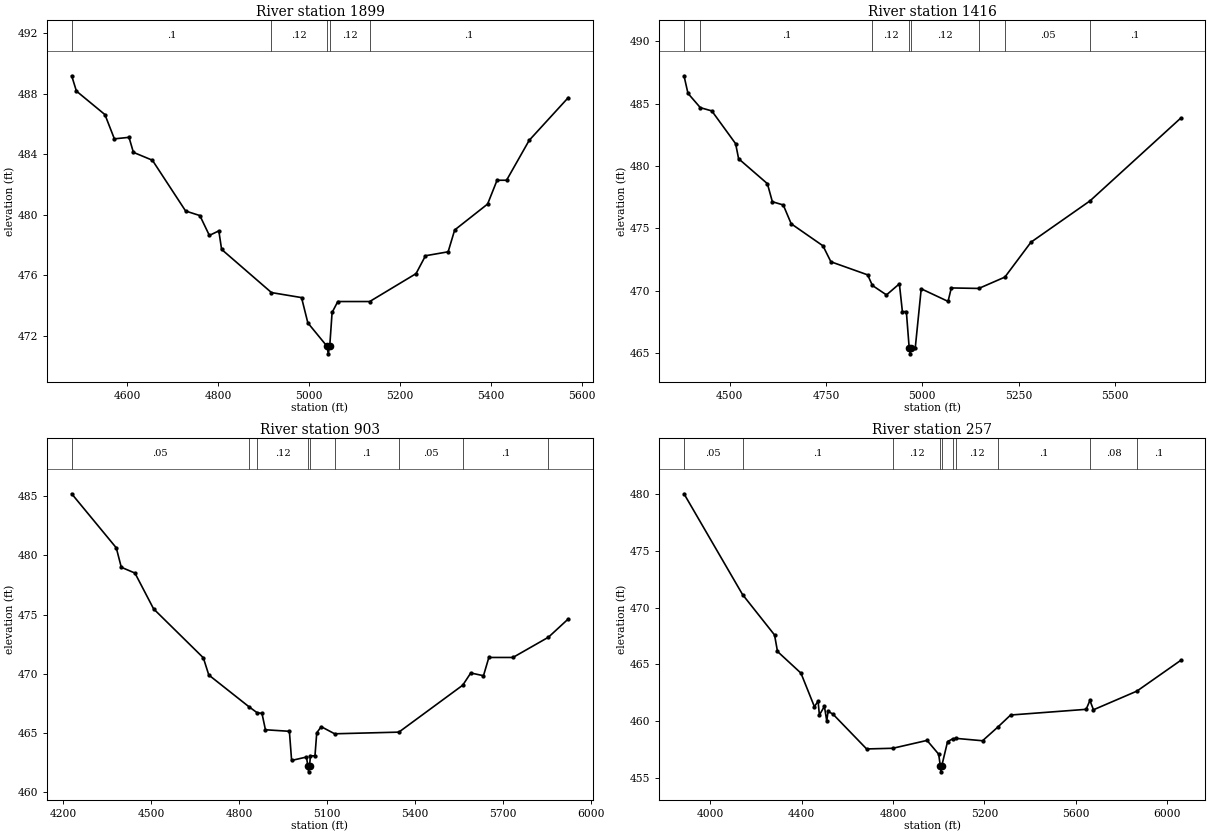
Type RM Length L Ch R = 1,1899,483,483,483
BEGIN DESCRIPTION:
UNT 115 IN LACR 3.0
END DESCRIPTION:
XS GIS Cut Line= 3
      2159187.71     13221846.85      2158687.72     13221696.86
      2158237.71     13222046.86
#Sta/Elev= 30
  4478.0  489.17  4488.4  488.16  4551.1  486.61  4571.9  485.01  4604.1  485.11
  4613.7  484.12  4655.5  483.60  4728.6  480.25  4759.9  479.95  4780.8  478.64
  4801.6  478.94  4807.7  477.72  4917.4  474.87  4983.5  474.54  4997.4  472.87
  5039.5  471.33  5042.3  470.83  5045.5  471.33  5050.7  473.56  5063.3  474.28
  5133.4  474.28  5235.3  476.12  5256.1  477.30  5305.9  477.56  5320.3  479.00
  5392.7  480.71  5413.5  482.28  5434.4  482.28  5484.1  484.91  5570.1  487.73
#Mann=5,-1,0
  4478.0     0.1       0  4917.4    0.12       0  5039.5    0.07       0
  5045.5    0.12       0  5133.4     0.1       0
Bank Sta=5039.5,5045.5
Exp/Cntr=0.3,0.1

Type RM Length L Ch R = 1,1416,513,513,513
BEGIN DESCRIPTION:
UNT 115 IN LACR 2.0
END DESCRIPTION:
XS GIS Cut Line= 3
      2159087.75     13221146.85      2158487.72     13221296.85
      2158187.73     13221896.84
#Sta/Elev= 30
  4381.5  487.24  4391.8  485.83  4423.9  484.68  4453.7  484.42  4515.5  481.79
  4523.3  480.58  4598.0  478.58  4610.9  477.13  4639.2  476.87  4659.8  475.36
  4742.3  473.59  4762.9  472.31  4858.3  471.26  4870.6  470.41  4907.2  469.65
  4940.7  470.54  4948.5  468.31  4958.8  468.31  4966.1  465.42  4968.8  464.92
  4972.1  465.42  4982.0  465.42  4997.4  470.14  5067.1  469.13  5075.5  470.21
  5146.9  470.17  5214.6  471.08  5282.3  473.88  5435.7  477.20  5670.8  483.83
#Mann=8,-1,0
  4381.5    0.05       0  4423.9     0.1       0  4870.6    0.12       0
  4966.1    0.07       0  4972.1    0.12       0  5146.9     0.1       0
  5214.6    0.05       0  5435.7     0.1       0
Bank Sta=4966.1,4972.1
Exp/Cntr=0.3,0.1

Type RM Length L Ch R = 1,903,646,646,646
BEGIN DESCRIPTION:
Mapping XS a52eb5c1
END DESCRIPTION:
XS GIS Cut Line= 4
      2159031.14     13220948.67      2158515.49     13220766.37
      2158072.78     13221032.00      2157828.73     13221613.56
#Sta/Elev= 30
  4228.4  485.20  4380.5  480.64  4397.6  479.00  4444.2  478.51  4507.8  475.49
  4677.5  471.36  4696.1  469.91  4832.2  467.25  4860.8  466.73  4877.5  466.67
  4889.3  465.29  4971.0  465.16  4978.6  462.70  5029.3  462.99  5033.9  462.24
  5036.6  461.74  5039.9  462.24  5042.7  463.09  5058.3  463.09  5064.3  465.03
  5079.6  465.55  5125.4  464.95  5344.5  465.09  5562.3  469.05  5589.7  470.08
  5633.1  469.85  5651.4  471.39  5733.6  471.39  5854.7  473.10  5922.3  474.64
#Mann=9,-1,0
  4228.4    0.05       0  4832.2     0.1       0  4860.8    0.12       0
  5033.9    0.07       0  5039.9    0.12       0  5125.4     0.1       0
  5344.5    0.05       0  5562.3     0.1       0  5854.7    0.08       0
Bank Sta=5033.9,5039.9
Exp/Cntr=0.3,0.1

Type RM Length L Ch R = 1,257,0,0,0
BEGIN DESCRIPTION:
UNT 115 IN LACR 1.0
END DESCRIPTION:
XS GIS Cut Line= 4
      2159046.71     13220714.27      2158333.20     13220323.66
      2157895.70     13220412.20      2157614.46     13221281.96
#Sta/Elev= 30
  3885.1  479.99  4141.4  471.14  4281.5  467.59  4294.4  466.14  4397.0  464.24
  4456.0  461.29  4472.1  461.78  4477.8  460.56  4499.7  461.32  4510.1  460.04
  4515.8  460.89  4537.6  460.63  4684.6  457.58  4799.3  457.64  4949.0  458.33
  5000.0  457.12  5007.2  456.07  5010.0  455.57  5013.2  456.07  5039.0  458.23
  5060.6  458.46  5075.4  458.51  5192.1  458.30  5258.3  459.49  5314.9  460.56
  5645.6  461.06  5662.1  461.84  5677.6  461.02  5867.8  462.66  6059.0  465.35
#Mann=10,-1,0
  3885.1    0.05       0  4141.4     0.1       0  4799.3    0.12       0
  5007.2    0.07       0  5013.2    0.12       0  5060.6     0.1       0
  5075.4    0.12       0  5258.3     0.1       0  5662.1    0.08       0
  5867.8     0.1       0
Bank Sta=5007.2,5013.2
Exp/Cntr=0.3,0.1

Chan Stop Cuts=-1