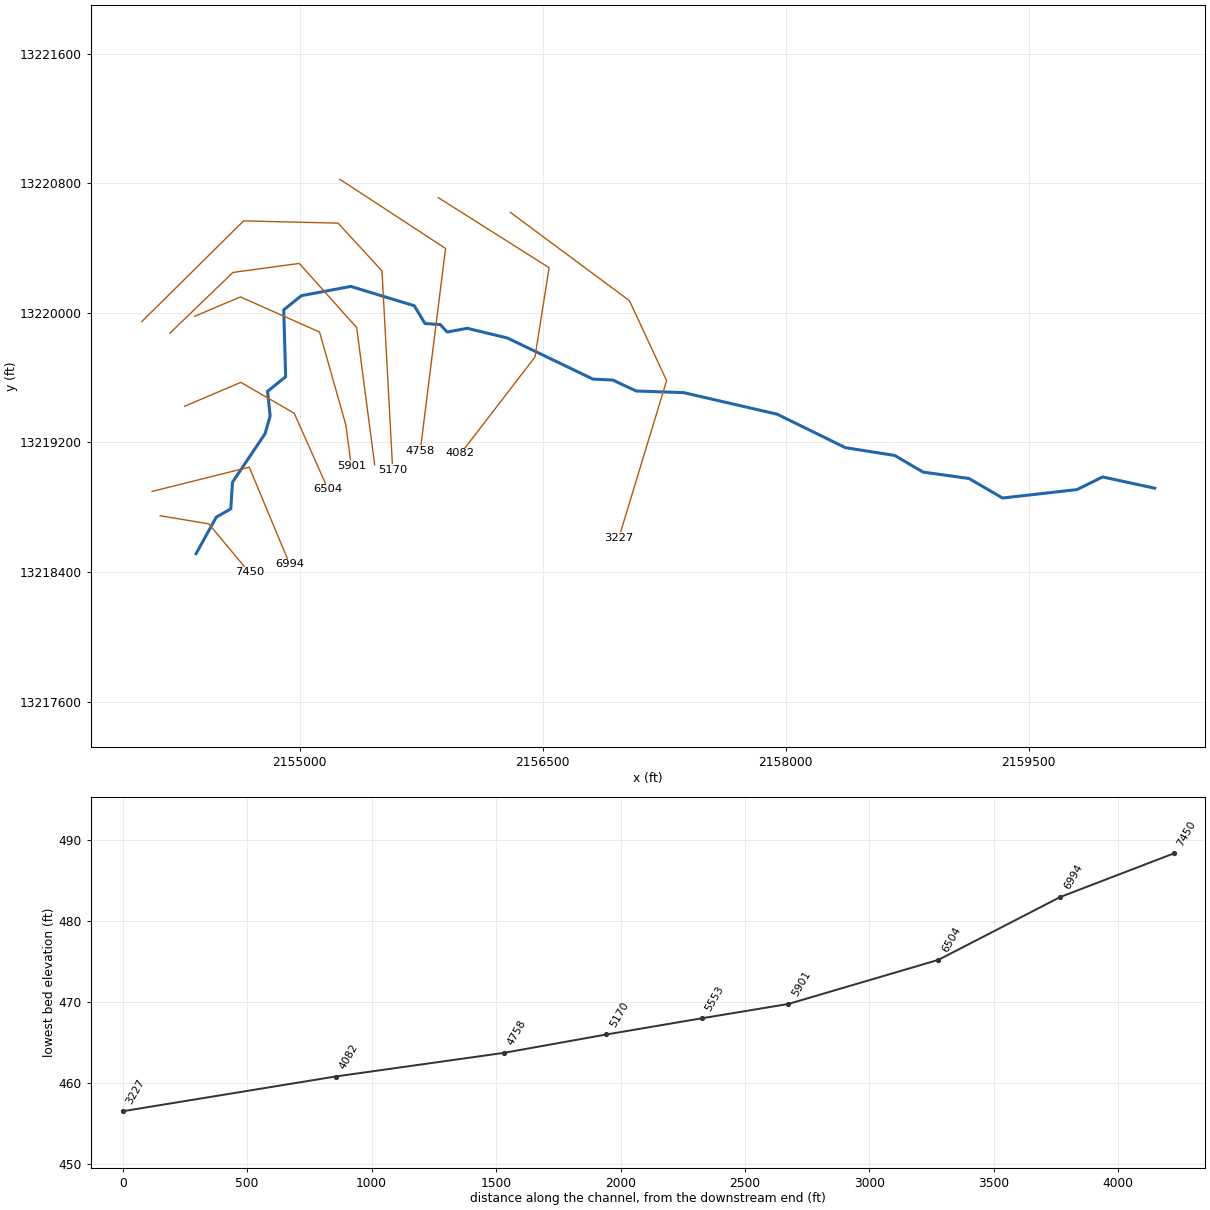
--- UNT 119 IN LACR.prj (project) ---

Proj Title=UNT 119 IN LACR Base Level Engineering
Current Plan=p01
Default Exp/Contr=0.3,0.1
English Units
Geom File=g01
Geom File=g02
Flow File=f01
Plan File=p01
Y Axis Title=Elevation
X Axis Title(PF)=Main Channel Distance
X Axis Title(XS)=Station
BEGIN DESCRIPTION:
UNT 119 IN LACR
END DESCRIPTION:
DSS Export Rating Curves= 0
DSS Export Rating Curve Sorted= 0
DSS Export Volume Flow Curves= 0
DXF OffsetX= 0
DXF OffsetY= 0
DXF ScaleX= 1
DXF ScaleY= 10

--- UNT 119 IN LACR.p01 (plan) ---

Plan Title=Multiple Run
Short Identifier=Multiple
Geom File=g01
Flow File=f01
Subcritical Flow
K Sum by GR= 0
Std Step Tol= 0.01
Critical Tol= 0.01
Num of Std Step Trials= 20
Max Error Tol= 0.3
Flow Tol Ratio= 0.001
Split Flow NTrial= 30
Split Flow Tol= 0.02
Split Flow Ratio= 0.02
Log Output Level= 0
Friction Slope Method= 1
Unsteady Friction Slope Method= 2
Unsteady Bridges Friction Slope Method= 1
Parabolic Critical Depth
Global Vel Dist=  1 , 1 , 1
Global Log Level= 0
CheckData=True
Encroach Param= -1, 0, 0, 0
BEGIN DESCRIPTION:
Multiple Run
END DESCRIPTION:

--- UNT 119 IN LACR.f01 (steady flow) ---

Flow Title=Multiple
Number of Profiles=7
Profile Names=10-year,25-year,50-year,1pct_min,100-year,1pct_plu,500-year
River Rch & RM= UNT 119 IN LACR,Reach-1,7450
     135     184     224     201     272     368     407
Boundary for River Rch & Prof#=UNT 119 IN LACR,Reach-1,1
Up Type=0
Dn Type=3
Dn Slope=0.005
Boundary for River Rch & Prof#=UNT 119 IN LACR,Reach-1,2
Up Type=0
Dn Type=3
Dn Slope=0.005
Boundary for River Rch & Prof#=UNT 119 IN LACR,Reach-1,3
Up Type=0
Dn Type=3
Dn Slope=0.005
Boundary for River Rch & Prof#=UNT 119 IN LACR,Reach-1,4
Up Type=0
Dn Type=3
Dn Slope=0.005
Boundary for River Rch & Prof#=UNT 119 IN LACR,Reach-1,5
Up Type=0
Dn Type=3
Dn Slope=0.005
Boundary for River Rch & Prof#=UNT 119 IN LACR,Reach-1,6
Up Type=0
Dn Type=3
Dn Slope=0.005
Boundary for River Rch & Prof#=UNT 119 IN LACR,Reach-1,7
Up Type=0
Dn Type=3
Dn Slope=0.005

--- UNT 119 IN LACR.g01 (geometry) ---

Geom Title=Existing Conditions
Program Version=4.10

River Reach=UNT 119 IN LACR ,Reach-1
Reach XY= 30
      2154359.43     13218512.68       2154484.1     13218738.05
      2154573.66     13218789.23      2154584.46     13218954.05
       2154785.2     13219253.12      2154816.59     13219362.21
      2154800.99     13219514.97      2154912.41     13219605.24
      2154900.63     13220017.85      2155009.49     13220105.45
      2155314.35     13220162.48      2155706.37     13220043.25
      2155772.52     13219933.46      2155867.43     13219926.73
       2155909.2     13219881.08      2156033.21     13219903.86
      2156281.14     13219844.21      2156809.23     13219590.51
       2156931.9     13219584.43      2157076.75     13219516.81
      2157368.94     13219507.01      2157946.79     13219373.67
      2158367.83     13219167.15      2158672.74     13219118.99
       2158846.8     13219016.44      2159130.83     13218976.87
      2159337.89      13218856.3      2159797.38     13218908.24
      2159955.48     13218986.35      2160277.72     13218916.85

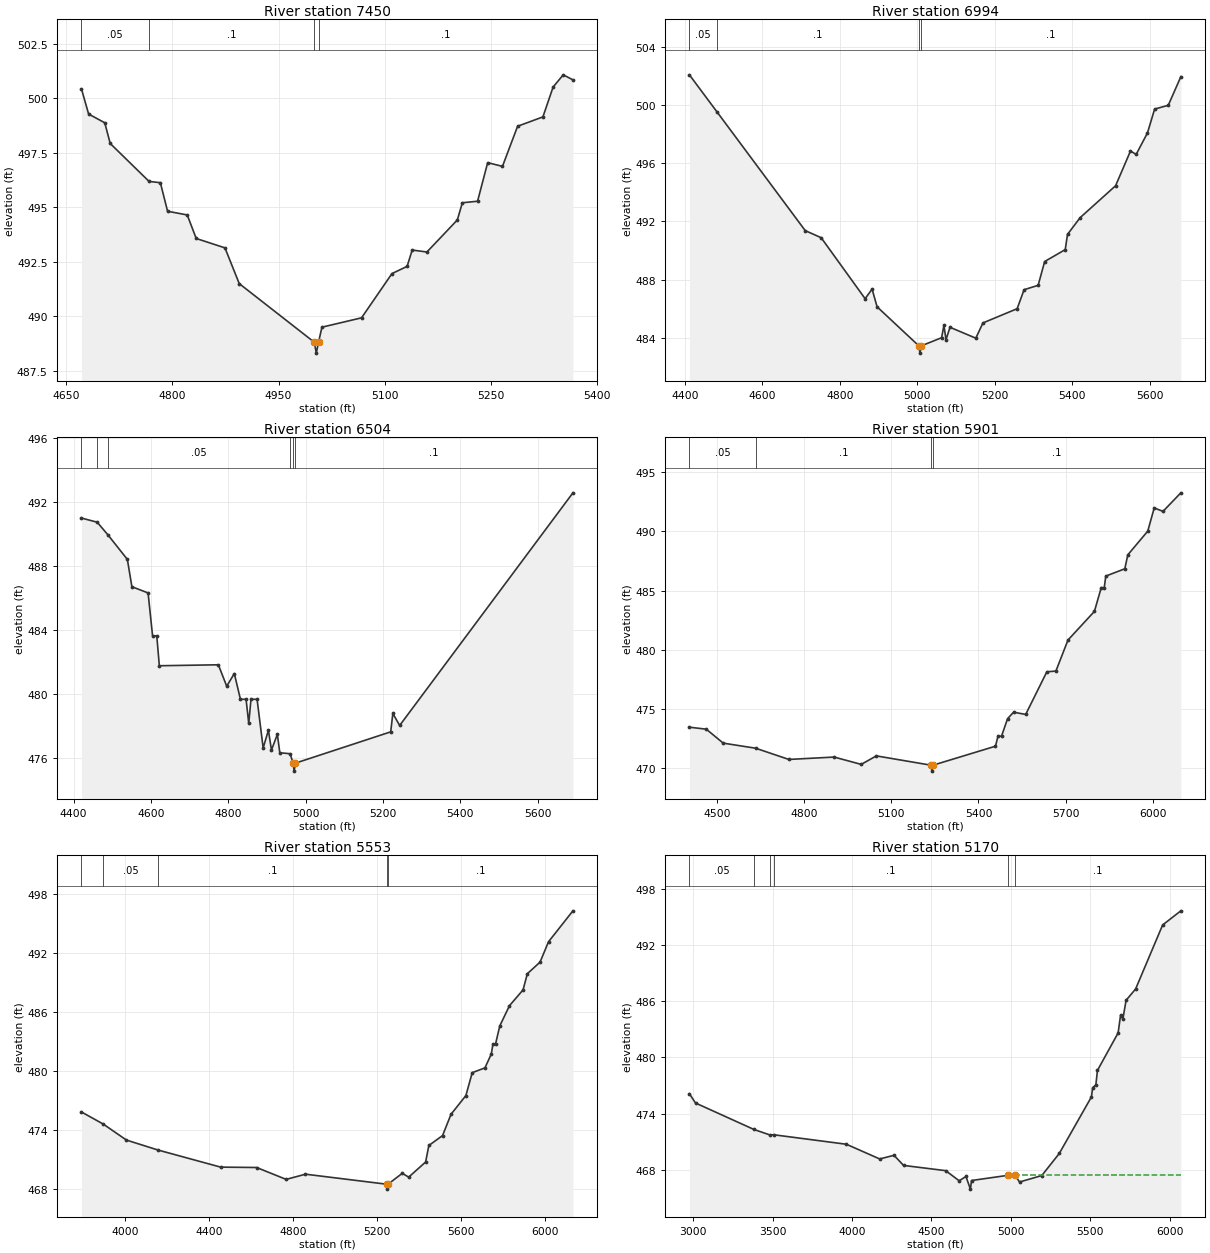
Type RM Length L Ch R = 1 ,7450    ,456,456,456
BEGIN DESCRIPTION:
UNT 119 IN LACR 3.0
END DESCRIPTION:
XS GIS Cut Line= 3
      2154137.72     13218746.85      2154437.72     13218696.85
      2154687.75     13218396.82
#Sta/Elev= 30
  4671.4  500.43  4681.5  499.28  4704.3  498.88    4712  497.93  4766.9  496.19
  4782.9  496.13  4793.1  494.82  4820.9  494.65  4833.6  493.57  4874.2  493.14
  4894.4   491.5  5000.5  488.81  5003.3  488.31  5006.5  488.81  5011.3   489.5
  5067.3  489.93  5110.3  491.96  5131.7  492.29  5138.9  493.04  5159.7  492.95
  5202.7  494.42  5209.8  495.21  5231.3  495.28  5245.6  497.05  5266.5  496.88
  5287.9  498.72  5323.7  499.15  5338.1  500.52  5352.4  501.08  5366.1  500.85
#Mann= 4 ,-1 , 0
  4671.4     .05       0  4766.9      .1       0  5000.5     .07       0
  5006.5      .1       0
Bank Sta=5000.5,5006.5
XS Rating Curve= 0 ,0
Exp/Cntr=0.3,0.1

Type RM Length L Ch R = 1 ,6994    ,490,490,490
BEGIN DESCRIPTION:
UNT 119 IN LACR 2.0
END DESCRIPTION:
XS GIS Cut Line= 3
      2154087.76     13218896.86      2154687.72     13219046.86
      2154937.71     13218446.88
#Sta/Elev= 30
  4412.1   502.1  4483.5  499.54    4711  491.37  4752.2  490.88  4865.6  486.68
  4883.6  487.34  4896.5  486.12  5004.3  483.43  5007.1  482.93  5010.3  483.43
    5063  483.99    5069  484.84  5074.4  483.86  5084.7  484.71  5151.3  483.96
  5169.7  485.01    5258  485.99  5275.9   487.3  5312.2   487.6    5329  489.24
  5382.1  490.06    5388  491.11  5420.5  492.26  5512.1  494.46  5550.5  496.85
  5565.2  496.62  5594.4   498.1  5612.8  499.74    5648     500  5680.5  501.97
#Mann= 4 ,-1 , 0
  4412.1     .05       0  4483.5      .1       0  5004.3     .07       0
  5010.3      .1       0
Bank Sta=5004.3,5010.3
XS Rating Curve= 0 ,0
Exp/Cntr=0.3,0.1

Type RM Length L Ch R = 1 ,6504    ,603,603,603
BEGIN DESCRIPTION:
Mapping XS 13007d2b
END DESCRIPTION:
XS GIS Cut Line= 4
      2154288.48     13219422.62      2154635.71     13219570.19
      2154965.57     13219379.22      2155173.91     13218910.47
#Sta/Elev= 30
  4420.2  491.01  4460.8  490.75  4488.5  489.96  4538.9  488.42  4550.6  486.71
  4592.5  486.32  4604.1  483.63    4615  483.63  4621.6  481.76  4774.3  481.82
  4795.9  480.48  4815.6  481.27  4831.4  479.66    4846  479.66  4852.9  478.15
  4858.7  479.66  4874.5  479.66  4890.2  476.61  4903.8  477.72  4911.7  476.48
  4926.9  477.46  4933.3  476.31    4960  476.25  4967.6  475.66  4970.3  475.16
  4973.6  475.66  5220.2  477.62  5225.7  478.77  5243.4  478.02  5691.6  492.59
#Mann= 6 ,-1 , 0
  4420.2     .05       0  4460.8      .1       0  4488.5     .05       0
    4960      .1       0  4967.6     .07       0  4973.6      .1       0
Bank Sta=4967.6,4973.6
XS Rating Curve= 0 ,0
Exp/Cntr=0.3,0.1

Type RM Length L Ch R = 1 ,5901    ,348,348,348
BEGIN DESCRIPTION:
Mapping XS a32a8e2a
END DESCRIPTION:
XS GIS Cut Line= 5
      2154351.28     13219978.37      2154633.43     13220097.75
      2155121.71     13219880.73      2155284.47     13219305.65
      2155317.03     13219056.03
#Sta/Elev= 30
  4405.8  473.43  4463.9  473.26  4522.1  472.08  4633.5  471.65  4747.8   470.7
  4903.7   470.9  4996.7  470.28  5048.7     471  5237.2  470.21  5239.9  469.71
  5243.2  470.21  5458.4  471.82  5467.1  472.67  5479.2  472.67    5500  474.15
  5520.7   474.7  5562.3  474.51  5635.1  478.12  5666.2  478.18  5707.8  480.81
  5798.6  483.23  5822.1  485.24  5832.5  485.24  5837.7  486.22  5903.2  486.84
  5913.5  488.02  5982.2  490.03  6004.3  491.99  6034.6   491.7  6095.9  493.27
#Mann= 4 ,-1 , 0
  4405.8     .05       0  4633.5      .1       0  5237.2     .07       0
  5243.2      .1       0
Bank Sta=5237.2,5243.2
XS Rating Curve= 0 ,0
Exp/Cntr=0.3,0.1

Type RM Length L Ch R = 1 ,5553    ,383,383,383
BEGIN DESCRIPTION:
Mapping XS 5b01d3fd
END DESCRIPTION:
XS GIS Cut Line= 5
        2154198.     13219873.87      2154586.91      13220248.9
      2154996.63     13220304.45       2155350.8     13219908.62
      2155461.88     13219061.67
#Sta/Elev= 30
    3793  475.79  3895.8  474.57  4007.1  472.93    4157  471.92  4455.2  470.18
  4626.7  470.14  4767.3  468.93  4859.2  469.46  5245.8  468.44  5248.5  467.94
  5251.8  468.44    5320  469.55  5350.3  469.16    5431   470.7  5446.3  472.38
  5511.6  473.39    5552  475.56  5622.6  477.46  5652.8  479.79  5713.4  480.28
  5743.6  481.69  5751.4  482.71  5763.8  482.71    5784  484.55  5830.2  486.61
  5894.9  488.22  5915.1  489.86  5975.6  491.04  6015.9  493.11  6132.1  496.26
#Mann= 5 ,-1 , 0
    3793      .1       0  3895.8     .05       0    4157      .1       0
  5245.8     .07       0  5251.8      .1       0
Bank Sta=5245.8,5251.8
XS Rating Curve= 0 ,0
Exp/Cntr=0.3,0.1

Type RM Length L Ch R = 1 ,5170    ,412,412,412
BEGIN DESCRIPTION:
Mapping XS bcad48cc
END DESCRIPTION:
XS GIS Cut Line= 5
      2154024.49     13219945.56      2154652.97      13220567.1
      2155236.31     13220553.21      2155507.14     13220258.07
      2155573.12     13219032.33
#Sta/Elev= 30
  2975.8  476.12  3014.3  475.13    3382  472.31    3483  471.72  3507.6  471.74
  3964.5  470.73  4174.5  469.16  4264.6  469.55  4324.6  468.47  4590.1  467.91
  4675.2  466.83  4717.7  467.29  4745.8  465.94  4752.9  466.86  4985.2  467.42
  5025.3  467.45  5055.3   466.7  5195.5  467.39  5305.7  469.75  5508.4  475.79
    5516  476.77    5536  477.07    5546  478.61  5676.2  482.61  5691.5  484.48
  5706.2  484.09  5726.3  486.09  5786.4   487.3  5956.6  494.13  6071.3  495.64
#Mann= 6 ,-1 , 0
  2975.8     .05       0    3382      .1       0    3483     .05       0
  3507.6      .1       0  4985.2     .07       0  5025.3      .1       0
#XS Ineff= 2 , 0
         4574.85  467.91 5034.73          467.45
Permanent Ineff=
       F       F
Bank Sta=4985.2,5025.3
XS Rating Curve= 0 ,0
Exp/Cntr=0.3,0.1

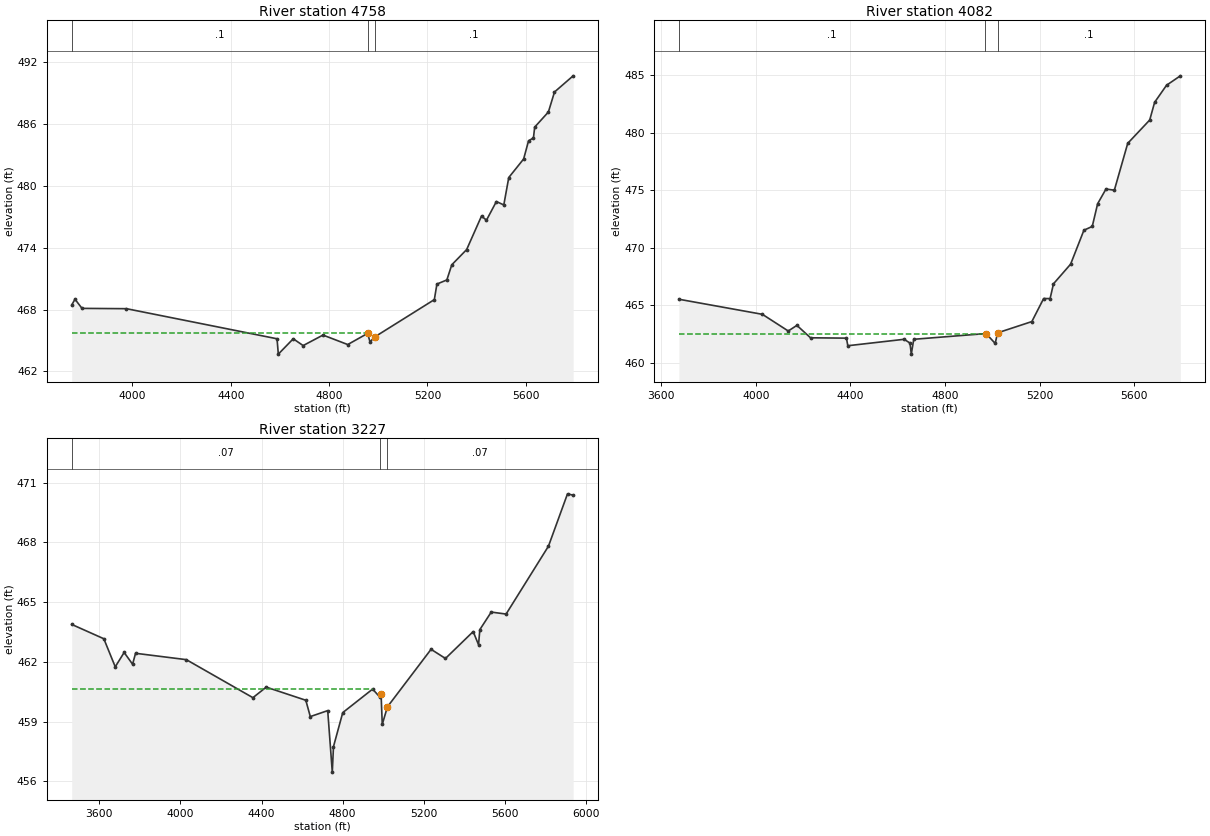
Type RM Length L Ch R = 1 ,4758    ,676,676,676
BEGIN DESCRIPTION:
Mapping XS 8b3b35a2
END DESCRIPTION:
XS GIS Cut Line= 3
      2155246.71     13220824.05       2155899.5     13220396.96
      2155743.26     13219146.98
#Sta/Elev= 30
  3753.1  468.44  3766.3     469  3794.9  468.11  3975.8  468.08  4588.3  465.16
  4593.5  463.67  4654.2  465.16  4694.5   464.5  4775.2  465.52  4875.9   464.6
  4956.6  465.68  4966.6  464.86  4986.4  465.35  5228.2  468.96  5238.7  470.47
  5279.1  470.87  5299.2  472.34  5359.7  473.82  5420.1  477.07  5440.3  476.67
  5480.6  478.48  5510.8  478.15    5531  480.81  5591.5  482.61  5611.6  484.38
  5631.4  484.65  5636.4   485.7  5692.2  487.17    5717  489.11  5792.9  490.68
#Mann= 3 , 0 , 0
  3753.1      .1       0  4956.6     .07       0  4986.4      .1       0
#XS Ineff= 2 , 0
       0 4956.24  465.69               0
Permanent Ineff=
       T       F
Bank Sta=4956.6,4986.4
XS Rating Curve= 0 ,0
Exp/Cntr=0.3,0.1

Type RM Length L Ch R = 1 ,4082    ,855,855,855
BEGIN DESCRIPTION:
Mapping XS d899f341
END DESCRIPTION:
XS GIS Cut Line= 5
      2155854.83     13220710.65      2156538.77     13220278.12
      2156451.59     13219726.82      2156010.61     13219153.91
      2155989.79     13219133.08
#Sta/Elev= 30
  3675.3  465.52  4028.1  464.21  4137.5  462.76    4174  463.25  4231.6  462.17
  4383.4  462.14  4389.3  461.48  4627.6  462.04  4652.1  461.71  4657.7  460.75
    4668  462.04  4969.1  462.53  4974.1  462.53  5012.3  461.68  5022.4   462.6
  5167.3  463.58  5217.1  465.58  5244.5  465.58  5258.7  466.86  5331.2  468.57
  5387.4  471.52  5422.7  471.85  5445.4  473.82  5480.7   475.1  5516.1     475
  5572.6  479.07  5665.6   481.1  5686.4  482.64  5736.7  484.12  5795.1  484.94
#Mann= 3 ,-1 , 0
  3675.3      .1       0  4969.1     .07       0  5022.4      .1       0
#XS Ineff= 2 , 0
       0 4968.12  462.53               0
Permanent Ineff=
       T       F
Bank Sta=4974.1,5022.4
XS Rating Curve= 0 ,0
Exp/Cntr=0.3,0.1

Type RM Length L Ch R = 1 ,3227    ,0,0,0
BEGIN DESCRIPTION:
UNT 119 IN LACR 1.0
END DESCRIPTION:
XS GIS Cut Line= 4
      2156300.07     13220619.56      2157034.85     13220074.23
      2157264.09     13219580.99       2156969.4     13218610.27
#Sta/Elev= 30
  3463.7  463.88    3622  463.16  3678.3  461.75  3722.2  462.47  3763.9  461.88
  3778.5  462.43  4028.9  462.11  4357.4   460.2  4423.3  460.73  4618.4  460.07
  4640.5  459.25  4726.4  459.55    4749  456.46  4754.8  457.74  4800.6  459.45
  4947.9  460.63  4982.7  460.24  4989.7  460.37  4995.5  458.86    5021  459.74
  5236.2  462.63  5307.2  462.17    5444  463.52  5470.4  462.86  5476.9  463.62
  5533.1   464.5  5606.3   464.4  5815.3  467.81  5909.3  470.44  5937.1  470.37
#Mann= 3 ,-1 , 0
  3463.7     .07       0  4982.7    .035       0    5021     .07       0
#XS Ineff= 2 , 0
       0  4948.3  460.63               0
Permanent Ineff=
       T       F
Bank Sta=4989.7,5021
XS Rating Curve= 0 ,0
Exp/Cntr=0.3,0.1

Chan Stop Cuts=-1
Use User Specified Reach Order=0
Composite Channel Slope=5

--- UNT 119 IN LACR.g02 (geometry) ---

Geom Title=Dummy
Program Version=4.10

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
River Reach=UNT 119 IN LACR ,Reach-1

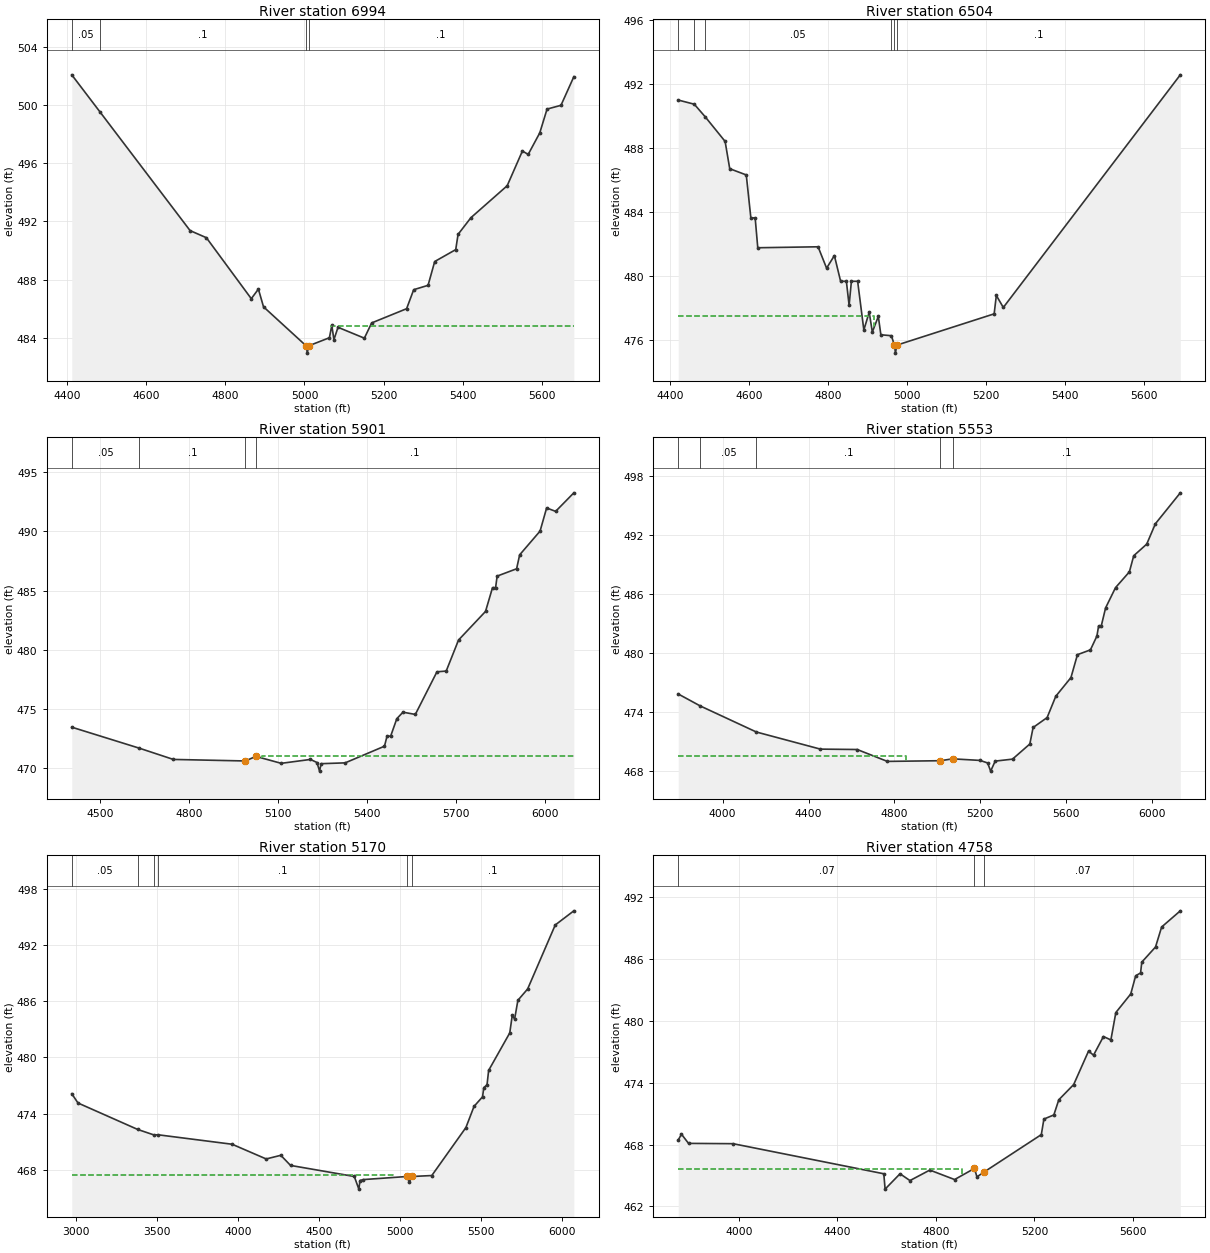
Type RM Length L Ch R = 1 ,6994    ,490,490,490
BEGIN DESCRIPTION:
UNT 119 IN LACR 2.0
END DESCRIPTION:
XS GIS Cut Line= 3
      2154087.76     13218896.86      2154687.72     13219046.86
      2154937.71     13218446.88
#Sta/Elev= 30
  4412.1   502.1  4483.5  499.54    4711  491.37  4752.2  490.88  4865.6  486.68
  4883.6  487.34  4896.5  486.12  5004.3  483.43  5007.1  482.93  5010.3  483.43
    5063  483.99    5069  484.84  5074.4  483.86  5084.7  484.71  5151.3  483.96
  5169.7  485.01    5258  485.99  5275.9   487.3  5312.2   487.6    5329  489.24
  5382.1  490.06    5388  491.11  5420.5  492.26  5512.1  494.46  5550.5  496.85
  5565.2  496.62  5594.4   498.1  5612.8  499.74    5648     500  5680.5  501.97
#Mann= 4 ,-1 , 0
  4412.1     .05       0  4483.5      .1       0  5004.3     .07       0
  5010.3      .1       0
#XS Ineff= 2 , 0
                         5068.18          484.82
Permanent Ineff=
       F       F
Bank Sta=5004.3,5010.3
XS Rating Curve= 0 ,0
Exp/Cntr=0.3,0.1

Type RM Length L Ch R = 1 ,6504    ,603,603,603
BEGIN DESCRIPTION:
Mapping XS 13007d2b
END DESCRIPTION:
XS GIS Cut Line= 4
      2154288.48     13219422.62      2154635.71     13219570.19
      2154965.57     13219379.22      2155173.91     13218910.47
#Sta/Elev= 30
  4420.2  491.01  4460.8  490.75  4488.5  489.96  4538.9  488.42  4550.6  486.71
  4592.5  486.32  4604.1  483.63    4615  483.63  4621.6  481.76  4774.3  481.82
  4795.9  480.48  4815.6  481.27  4831.4  479.66    4846  479.66  4852.9  478.15
  4858.7  479.66  4874.5  479.66  4890.2  476.61  4903.8  477.72  4911.7  476.48
  4926.9  477.46  4933.3  476.31    4960  476.25  4967.6  475.66  4970.3  475.16
  4973.6  475.66  5220.2  477.62  5225.7  478.77  5243.4  478.02  5691.6  492.59
#Mann= 6 ,-1 , 0
  4420.2     .05       0  4460.8      .1       0  4488.5     .05       0
    4960      .1       0  4967.6     .07       0  4973.6      .1       0
#XS Ineff= 2 , 0
         4917.05  477.48
Permanent Ineff=
       F       F
Bank Sta=4967.6,4973.6
XS Rating Curve= 0 ,0
Exp/Cntr=0.3,0.1

Type RM Length L Ch R = 1 ,5901    ,348,348,348
BEGIN DESCRIPTION:
Mapping XS a32a8e2a
END DESCRIPTION:
XS GIS Cut Line= 5
      2154351.28     13219978.37      2154633.43     13220097.75
      2155121.71     13219880.73      2155284.47     13219305.65
      2155317.03     13219056.03
#Sta/Elev= 30
  4405.8  473.43  4633.5  471.65  4747.8   470.7  4990.4  470.57  5025.4  470.96
  5110.8  470.37  5209.3   470.7  5231.2  470.44  5239.9  469.71  5245.1  470.34
  5326.1  470.41  5458.4  471.82  5467.1  472.67  5479.2  472.67    5500  474.15
  5520.7   474.7  5562.3  474.51  5635.1  478.12  5666.2  478.18  5707.8  480.81
  5798.6  483.23  5822.1  485.24  5832.5  485.24  5837.7  486.22  5903.2  486.84
  5913.5  488.02  5982.2  490.03  6004.3  491.99  6034.6   491.7  6095.9  493.27
#Mann= 4 ,-1 , 0
  4405.8     .05       0  4633.5      .1       0  4990.4     .07       0
  5025.4      .1       0
#XS Ineff= 2 , 0
                         5045.34          471.01
Permanent Ineff=
       F       F
Bank Sta=4990.4,5025.4
XS Rating Curve= 0 ,0
Exp/Cntr=0.3,0.1

Type RM Length L Ch R = 1 ,5553    ,383,383,383
BEGIN DESCRIPTION:
Mapping XS 5b01d3fd
END DESCRIPTION:
XS GIS Cut Line= 5
        2154198.     13219873.87      2154586.91      13220248.9
      2154996.63     13220304.45       2155350.8     13219908.62
      2155461.88     13219061.67
#Sta/Elev= 30
    3793  475.79  3895.8  474.57    4157  471.92  4455.2  470.18  4626.7  470.14
  4767.3  468.93  5014.7     469  5071.5  469.19  5199.4  469.03  5234.5  468.77
  5248.5  467.94  5269.7  468.96  5350.3  469.16    5431   470.7  5446.3  472.38
  5511.6  473.39    5552  475.56  5622.6  477.46  5652.8  479.79  5713.4  480.28
  5743.6  481.69  5751.4  482.71  5763.8  482.71    5784  484.55  5830.2  486.61
  5894.9  488.22  5915.1  489.86  5975.6  491.04  6015.9  493.11  6132.1  496.26
#Mann= 5 ,-1 , 0
    3793      .1       0  3895.8     .05       0    4157      .1       0
  5014.7     .07       0  5071.5      .1       0
#XS Ineff= 2 , 0
         4855.11  469.47
Permanent Ineff=
       F       F
Bank Sta=5014.7,5071.5
XS Rating Curve= 0 ,0
Exp/Cntr=0.3,0.1

Type RM Length L Ch R = 1 ,5170    ,412,412,412
BEGIN DESCRIPTION:
Mapping XS bcad48cc
END DESCRIPTION:
XS GIS Cut Line= 5
      2154024.49     13219945.56      2154652.97      13220567.1
      2155236.31     13220553.21      2155507.14     13220258.07
      2155573.12     13219032.33
#Sta/Elev= 30
  2975.8  476.12  3014.3  475.13    3382  472.31    3483  471.72  3507.6  471.74
  3964.5  470.73  4174.5  469.16  4264.6  469.55  4324.6  468.47  4717.7  467.29
  4745.8  465.94  4752.9  466.86  4774.4  466.96  5045.3  467.29  5055.3   466.7
  5075.3  467.29  5195.5  467.39  5405.8  472.51  5455.9  474.77  5508.4  475.79
    5516  476.77    5536  477.07    5546  478.61  5676.2  482.61  5691.5  484.48
  5706.2  484.09  5726.3  486.09  5786.4   487.3  5956.6  494.13  6071.3  495.64
#Mann= 6 ,-1 , 0
  2975.8     .05       0    3382      .1       0    3483     .05       0
  3507.6      .1       0  5045.3     .07       0  5075.3      .1       0
#XS Ineff= 2 , 0
       0 4954.55   467.5               0
Permanent Ineff=
       T       F
Bank Sta=5045.3,5075.3
XS Rating Curve= 0 ,0
Exp/Cntr=0.3,0.1

Type RM Length L Ch R = 1 ,4758    ,676,676,676
BEGIN DESCRIPTION:
Mapping XS 8b3b35a2
END DESCRIPTION:
XS GIS Cut Line= 3
      2155246.71     13220824.05       2155899.5     13220396.96
      2155743.26     13219146.98
#Sta/Elev= 30
  3753.1  468.44  3766.3     469  3794.9  468.11  3975.8  468.08  4588.3  465.16
  4593.5  463.67  4654.2  465.16  4694.5   464.5  4775.2  465.52  4875.9   464.6
  4956.6  465.68  4966.6  464.86  4996.9  465.35  5228.2  468.96  5238.7  470.47
  5279.1  470.87  5299.2  472.34  5359.7  473.82  5420.1  477.07  5440.3  476.67
  5480.6  478.48  5510.8  478.15    5531  480.81  5591.5  482.61  5611.6  484.38
  5631.4  484.65  5636.4   485.7  5692.2  487.17    5717  489.11  5792.9  490.68
#Mann= 3 , 0 , 0
  3753.1     .07       0  4956.6     .05       0  4996.9     .07       0
#XS Ineff= 2 , 0
       0 4906.25  465.61               0
Permanent Ineff=
       T       F
Bank Sta=4956.6,4996.9
XS Rating Curve= 0 ,0
Exp/Cntr=0.3,0.1

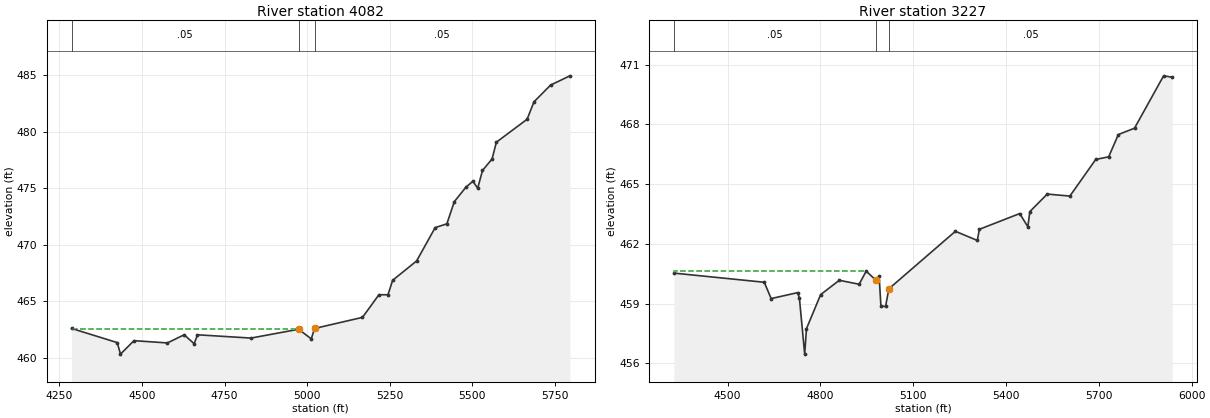
Type RM Length L Ch R = 1 ,4082    ,855,855,855
BEGIN DESCRIPTION:
Mapping XS d899f341
END DESCRIPTION:
XS GIS Cut Line= 4
      2156569.64     13220473.33      2156451.59     13219726.82
      2156010.61     13219153.91      2155989.79     13219133.08
#Sta/Elev= 30
  4286.9   462.6  4425.1  461.35  4434.9  460.33  4475.7  461.52  4576.9  461.32
  4627.6  462.04  4657.9  461.25    4668  462.04    4830  461.75  4974.1  462.53
  5012.3  461.68  5022.4   462.6  5167.3  463.58  5217.1  465.58  5244.5  465.58
  5258.7  466.86  5331.2  468.57  5387.4  471.52  5422.7  471.85  5445.4  473.82
  5480.7   475.1  5501.6  475.62  5516.1     475  5530.6  476.57  5559.6  477.59
  5572.6  479.07  5665.6   481.1  5686.4  482.64  5736.7  484.12  5795.1  484.94
#Mann= 3 , 0 , 0
  4286.9     .05       0  4974.1    .035       0  5022.4     .05       0
#XS Ineff= 2 , 0
       0 4969.09  462.53               0
Permanent Ineff=
       T       F
Bank Sta=4974.1,5022.4
XS Rating Curve= 0 ,0
Exp/Cntr=0.3,0.1

Type RM Length L Ch R = 1 ,3227    ,0,0,0
BEGIN DESCRIPTION:
UNT 119 IN LACR 1.0
END DESCRIPTION:
XS GIS Cut Line= 3
      2157012.71     13220121.87      2157264.09     13219580.99
       2156969.4     13218610.27
#Sta/Elev= 30
  4326.2  460.53  4618.4  460.07  4640.5  459.25  4726.4  459.55  4731.9  459.28
    4749  456.46  4754.8  457.74  4800.6  459.45    4861  460.17    4925  459.97
  4947.9  460.63  4979.2  460.17  4989.7  460.37  4995.5  458.86  5010.6  458.86
    5021  459.74  5236.2  462.63  5307.2  462.17  5313.6  462.73    5444  463.52
  5470.4  462.86  5476.9  463.62  5533.1   464.5  5606.3   464.4  5689.9  466.24
  5731.7  466.37    5763  467.49  5815.3  467.81  5909.3  470.44  5937.1  470.37
#Mann= 3 , 0 , 0
  4326.2     .05       0  4979.2    .035       0    5021     .05       0
#XS Ineff= 2 , 0
       0 4945.57  460.63               0
Permanent Ineff=
       T       F
Bank Sta=4979.2,5021
XS Rating Curve= 0 ,0
Exp/Cntr=0.3,0.1