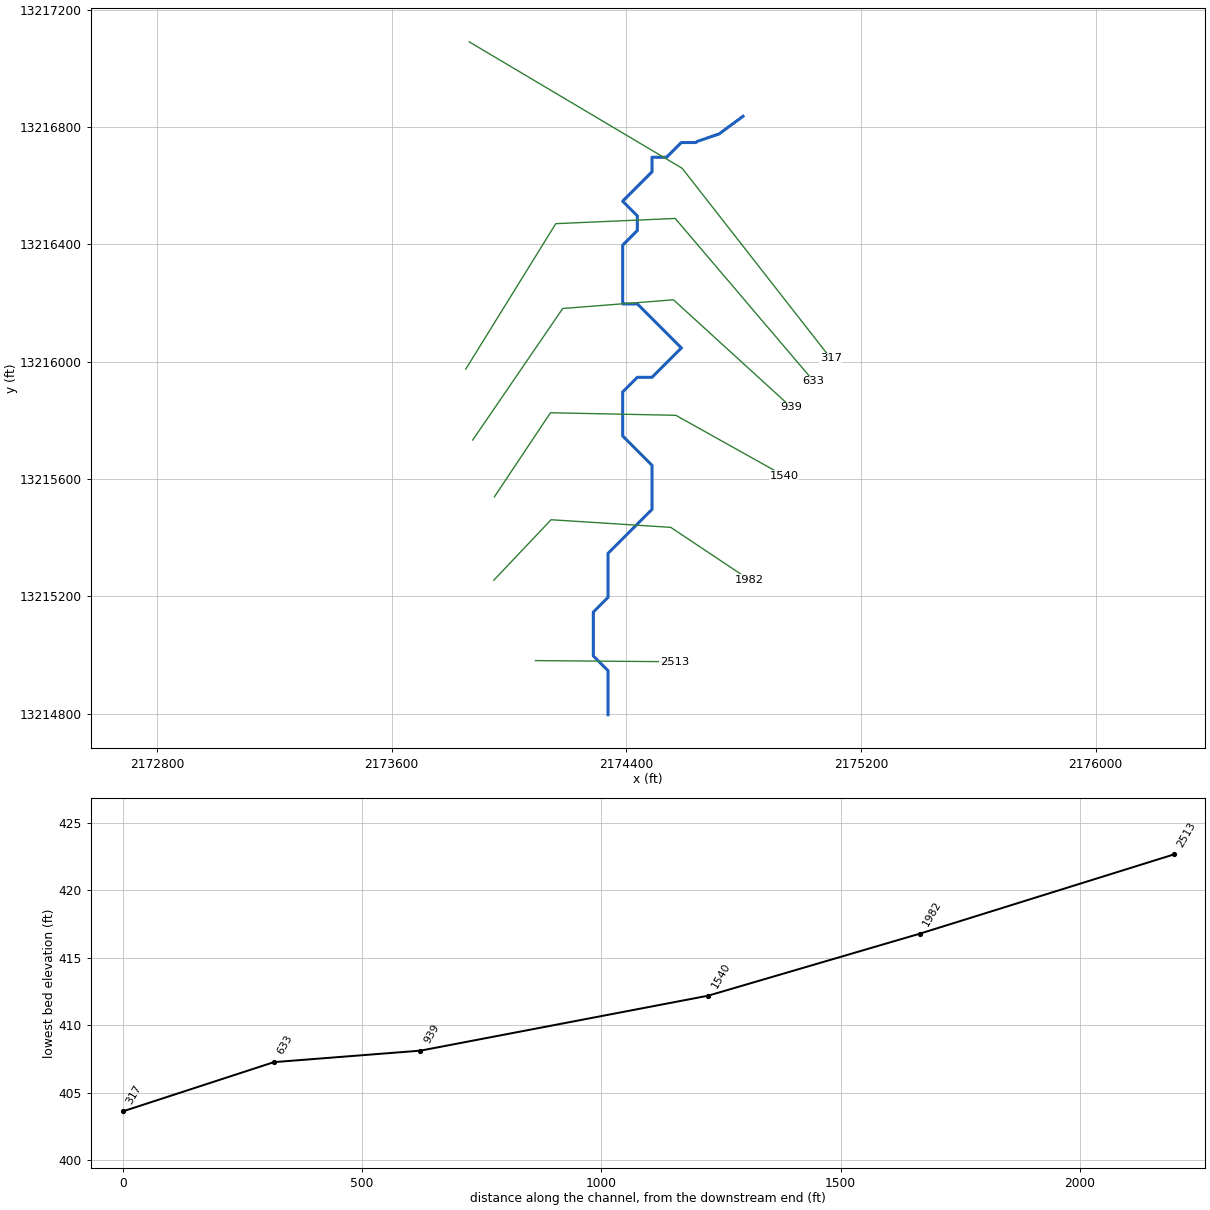
--- UNT 123 IN LACR.prj (project) ---

Proj Title=UNT 123 IN LACR Base Level Engineering
Current Plan=p01
Default Exp/Contr=0.3,0.1
English Units
Geom File=g01
Flow File=f01
Plan File=p01
BEGIN DESCRIPTION:
UNT 123 IN LACR
END DESCRIPTION:

--- UNT 123 IN LACR.p01 (plan) ---

Plan Title=Multiple Run
Short Identifier=Multiple
Geom File=g01
Flow File=f01
Subcritical Flow
K Sum by GR= 0
Std Step Tol= 0.01
Critical Tol= 0.01
Num of Std Step Trials= 20
Max Error Tol= 0.3
Flow Tol Ratio= 0.001
Split Flow NTrial= 30
Split Flow Tol= 0.02
Split Flow Ratio= 0.02
Log Output Level= 0
Friction Slope Method= 1
Unsteady Friction Slope Method= 2
Unsteady Bridges Friction Slope Method= 1
Parabolic Critical Depth
Global Vel Dist=  1 , 1 , 1
Global Log Level= 0
CheckData=True
Encroach Param= -1, 0, 0, 0
BEGIN DESCRIPTION:
Multiple Run
END DESCRIPTION:

--- UNT 123 IN LACR.f01 (steady flow) ---

Flow Title=Multiple
Number of Profiles=7
Profile Names=10-year,25-year,50-year,1pct_min,100-year,1pct_plu,500-year
River Rch & RM= UNT 123 IN LACR,Reach-1,2513
     131     178     215     192     260     352     385
Boundary for River Rch & Prof#=UNT 123 IN LACR,Reach-1,1
Up Type=0
Dn Type=3
Dn Slope=0.005
Boundary for River Rch & Prof#=UNT 123 IN LACR,Reach-1,2
Up Type=0
Dn Type=3
Dn Slope=0.005
Boundary for River Rch & Prof#=UNT 123 IN LACR,Reach-1,3
Up Type=0
Dn Type=3
Dn Slope=0.005
Boundary for River Rch & Prof#=UNT 123 IN LACR,Reach-1,4
Up Type=0
Dn Type=3
Dn Slope=0.005
Boundary for River Rch & Prof#=UNT 123 IN LACR,Reach-1,5
Up Type=0
Dn Type=3
Dn Slope=0.005
Boundary for River Rch & Prof#=UNT 123 IN LACR,Reach-1,6
Up Type=0
Dn Type=3
Dn Slope=0.005
Boundary for River Rch & Prof#=UNT 123 IN LACR,Reach-1,7
Up Type=0
Dn Type=3
Dn Slope=0.005

--- UNT 123 IN LACR.g01 (geometry) ---

Geom Title=Existing Conditions

River Reach=UNT 123 IN LACR,Reach-1
Reach XY= 30
      2174337.72     13214796.86      2174337.72     13214946.86
      2174287.72     13214996.85      2174287.72     13215146.85
      2174337.72     13215196.85      2174337.72     13215346.85
      2174437.72     13215446.86      2174487.72     13215496.85
      2174487.72     13215646.85      2174387.72     13215746.85
      2174387.72     13215896.85      2174437.72     13215946.86
      2174487.72     13215946.86      2174587.72     13216046.85
      2174537.72     13216096.86      2174437.72     13216196.85
      2174387.72     13216196.85      2174387.72     13216396.85
      2174437.72     13216446.86      2174437.72     13216496.85
      2174387.72     13216546.85      2174437.72     13216596.86
      2174487.72     13216646.85      2174487.72     13216696.85
      2174537.72     13216696.85      2174587.72     13216746.86
      2174637.72     13216746.86      2174641.40     13216750.53
      2174716.25     13216776.16      2174798.15     13216836.42

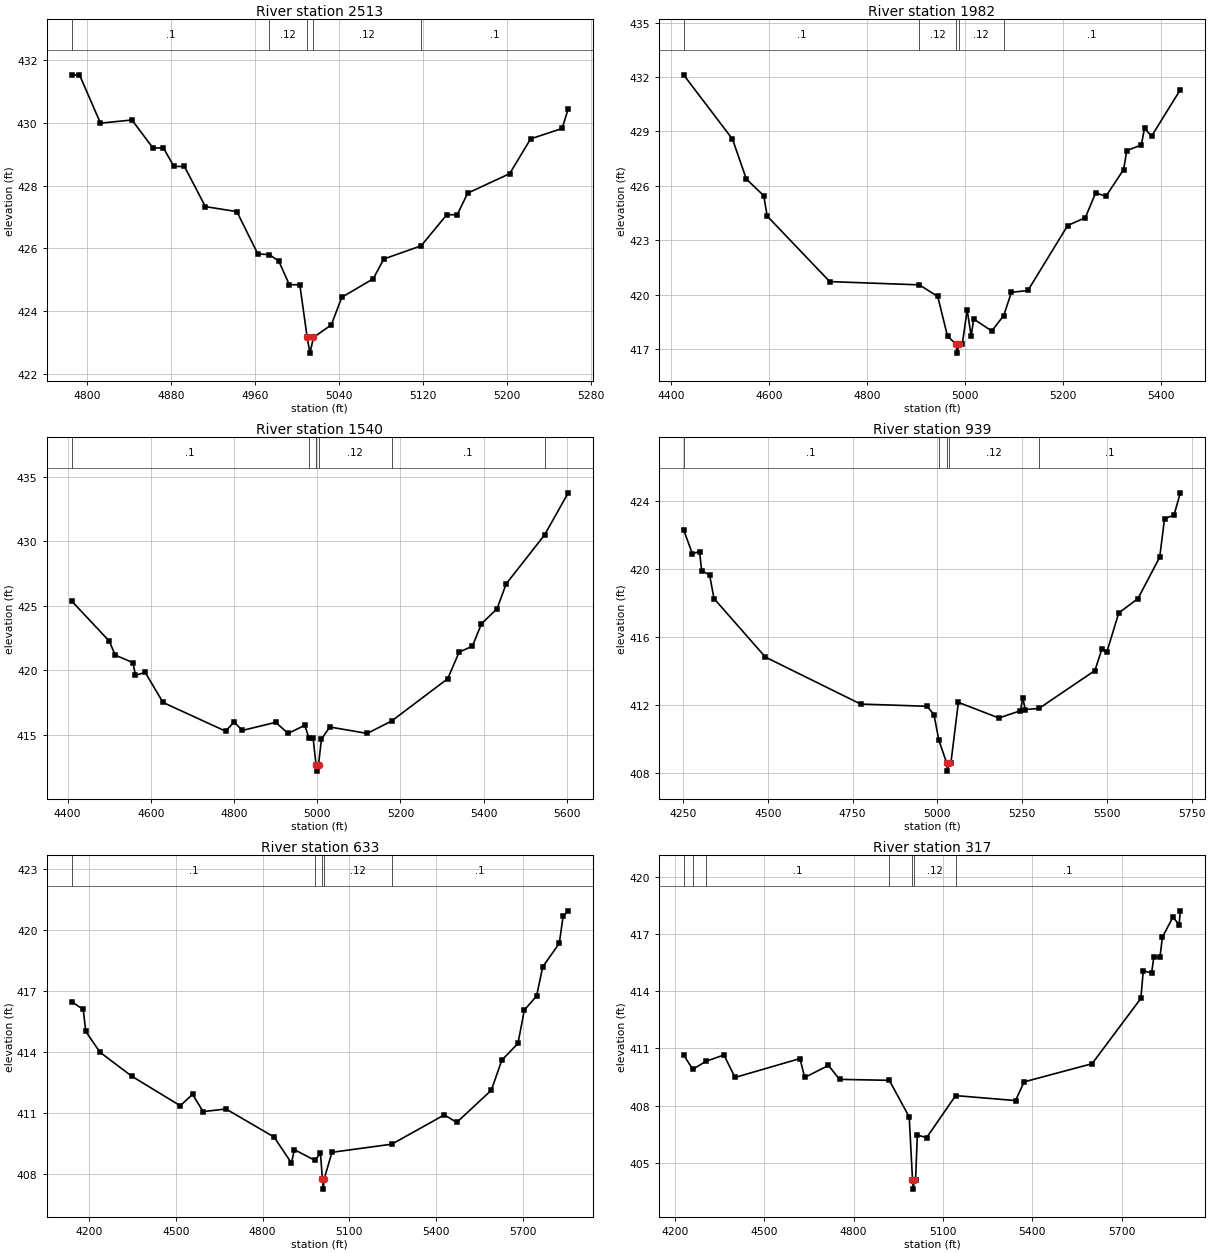
Type RM Length L Ch R = 1,2513,531,531,531
BEGIN DESCRIPTION:
UNT 124 IN LACR 4.0
END DESCRIPTION:
XS GIS Cut Line= 2
      2174090.13     13214981.22      2174563.52     13214977.32
#Sta/Elev= 30
  4785.0  431.53  4792.6  431.53  4812.6  429.99  4842.6  430.09  4862.6  429.20
  4872.6  429.20  4882.6  428.61  4892.6  428.61  4912.6  427.33  4942.6  427.17
  4962.6  425.82  4973.6  425.80  4982.6  425.59  4992.6  424.84  5002.6  424.84
  5009.6  423.16  5012.3  422.66  5015.6  423.16  5032.6  423.56  5042.6  424.44
  5072.6  425.03  5082.6  425.66  5118.2  426.08  5142.6  427.07  5152.6  427.07
  5162.6  427.76  5202.6  428.38  5222.6  429.49  5252.6  429.82  5258.4  430.45
#Mann=5,-1,0
  4785.0     0.1       0  4973.6    0.12       0  5009.6    0.07       0
  5015.6    0.12       0  5118.2     0.1       0
Bank Sta=5009.6,5015.6
Exp/Cntr=0.3,0.1

Type RM Length L Ch R = 1,1982,442,442,442
BEGIN DESCRIPTION:
UNT 124 IN LACR 3.0
END DESCRIPTION:
XS GIS Cut Line= 4
      2173948.28     13215255.16      2174143.62     13215461.35
      2174551.61     13215435.31      2174818.57     13215257.33
#Sta/Elev= 30
  4425.3  432.12  4525.0  428.58  4553.3  426.38  4588.9  425.46  4595.8  424.34
  4723.5  420.73  4906.5  420.55  4943.9  419.91  4963.9  417.72  4981.0  417.29
  4983.7  416.79  4987.0  417.29  4994.0  417.29  5004.0  419.16  5012.2  417.72
  5017.2  418.67  5054.1  418.01  5078.6  418.86  5094.2  420.14  5127.9  420.24
  5209.1  423.82  5245.1  424.25  5266.2  425.62  5287.2  425.43  5323.2  426.90
  5329.8  427.95  5359.3  428.25  5365.9  429.17  5380.3  428.74  5439.0  431.30
#Mann=5,-1,0
  4425.3     0.1       0  4906.5    0.12       0  4981.0    0.07       0
  4987.0    0.12       0  5078.6     0.1       0
Bank Sta=4981,4987
Exp/Cntr=0.3,0.1

Type RM Length L Ch R = 1,1540,601,601,601
BEGIN DESCRIPTION:
UNT 124 IN LACR 2.0
END DESCRIPTION:
XS GIS Cut Line= 4
      2173950.48     13215539.48      2174141.45     13215825.94
      2174568.97     13215817.26      2174937.19     13215611.48
#Sta/Elev= 30
  4409.4  425.39  4500.0  422.28  4514.4  421.19  4557.1  420.60  4563.1  419.62
  4586.5  419.85  4629.2  417.52  4780.0  415.29  4800.0  416.01  4820.0  415.35
  4900.0  415.98  4930.0  415.12  4970.0  415.75  4979.9  414.77  4990.0  414.76
  4997.0  412.70  4999.7  412.20  5003.0  412.70  5010.0  414.67  5030.0  415.62
  5120.0  415.12  5178.6  416.08  5313.5  419.36  5340.9  421.42  5372.9  421.88
  5394.6  423.62  5431.9  424.77  5454.0  426.71  5546.3  430.50  5603.1  433.76
#Mann=6,-1,0
  4409.4     0.1       0  4979.9    0.12       0  4997.0    0.07       0
  5003.0    0.12       0  5178.6     0.1       0  5546.3    0.05       0
Bank Sta=4997,5003
Exp/Cntr=0.3,0.1

Type RM Length L Ch R = 1,939,306,306,306
BEGIN DESCRIPTION:
Mapping XS dc570479
END DESCRIPTION:
XS GIS Cut Line= 4
      2173876.46     13215732.90      2174183.26     13216181.30
      2174560.89     13216210.80      2174962.14     13215844.95
#Sta/Elev= 30
  4251.6  422.31  4277.5  420.90  4298.5  421.03  4304.9  419.91  4328.3  419.65
  4341.2  418.27  4492.8  414.83  4773.8  412.07  4969.9  411.94  4990.0  411.45
  5004.4  409.95  5027.1  408.63  5029.8  408.13  5033.1  408.63  5040.1  408.63
  5062.0  412.17  5181.6  411.25  5245.1  411.68  5251.9  412.43  5259.3  411.75
  5299.7  411.81  5464.7  414.04  5485.6  415.32  5499.8  415.12  5535.0  417.42
  5591.7  418.27  5655.9  420.70  5670.1  422.97  5697.8  423.16  5716.7  424.48
#Mann=5,-1,0
  4251.6     0.1       0  5004.4    0.12       0  5027.1    0.07       0
  5033.1    0.12       0  5299.7     0.1       0
Bank Sta=5027.1,5033.1
Exp/Cntr=0.3,0.1

Type RM Length L Ch R = 1,633,316,316,316
BEGIN DESCRIPTION:
UNT 124 IN LACR 1.0
END DESCRIPTION:
XS GIS Cut Line= 4
      2173852.86     13215974.82      2174159.66     13216470.42
      2174566.79     13216488.12      2175038.82     13215933.48
#Sta/Elev= 30
  4138.8  416.50  4179.4  416.11  4188.2  415.03  4237.3  414.01  4347.3  412.83
  4515.1  411.38  4557.6  411.94  4594.2  411.09  4673.4  411.22  4839.8  409.84
  4899.9  408.56  4909.9  409.22  4981.7  408.69  5000.0  409.06  5007.0  407.78
  5009.8  407.28  5013.0  407.78  5040.0  409.09  5247.0  409.49  5428.9  410.93
  5471.7  410.56  5591.4  412.14  5627.7  413.62  5683.6  414.44  5705.6  416.08
  5748.0  416.77  5769.3  418.21  5826.5  419.36  5839.9  420.70  5857.5  420.96
#Mann=5,-1,0
  4138.8     0.1       0  4981.7    0.12       0  5007.0    0.07       0
  5013.0    0.12       0  5247.0     0.1       0
Bank Sta=5007,5013
Exp/Cntr=0.3,0.1

Type RM Length L Ch R = 1,317,0,0,0
BEGIN DESCRIPTION:
UNT 123 IN LACR 2.0
END DESCRIPTION:
XS GIS Cut Line= 3
      2173864.66     13217089.95      2174590.39     13216659.23
      2175097.16     13216011.04
#Sta/Elev= 30
  4229.8  410.66  4260.4  409.91  4305.5  410.33  4365.2  410.66  4402.2  409.48
  4620.4  410.47  4636.0  409.48  4715.9  410.11  4753.0  409.38  4920.0  409.33
  4986.8  407.41  4997.8  404.13  5000.6  403.63  5003.8  404.13  5008.2  404.13
  5014.0  406.46  5045.3  406.33  5142.5  408.53  5343.5  408.27  5372.4  409.25
  5600.3  410.20  5764.0  413.62  5772.1  415.06  5800.3  414.96  5807.4  415.78
  5828.2  415.78  5836.3  416.83  5871.6  417.88  5892.4  417.49  5896.5  418.21
#Mann=7,-1,0
  4229.8     0.1       0  4260.4    0.05       0  4305.5     0.1       0
  4920.0    0.12       0  4997.8    0.07       0  5003.8    0.12       0
  5142.5     0.1       0
Bank Sta=4997.8,5003.8
Exp/Cntr=0.3,0.1

Chan Stop Cuts=-1