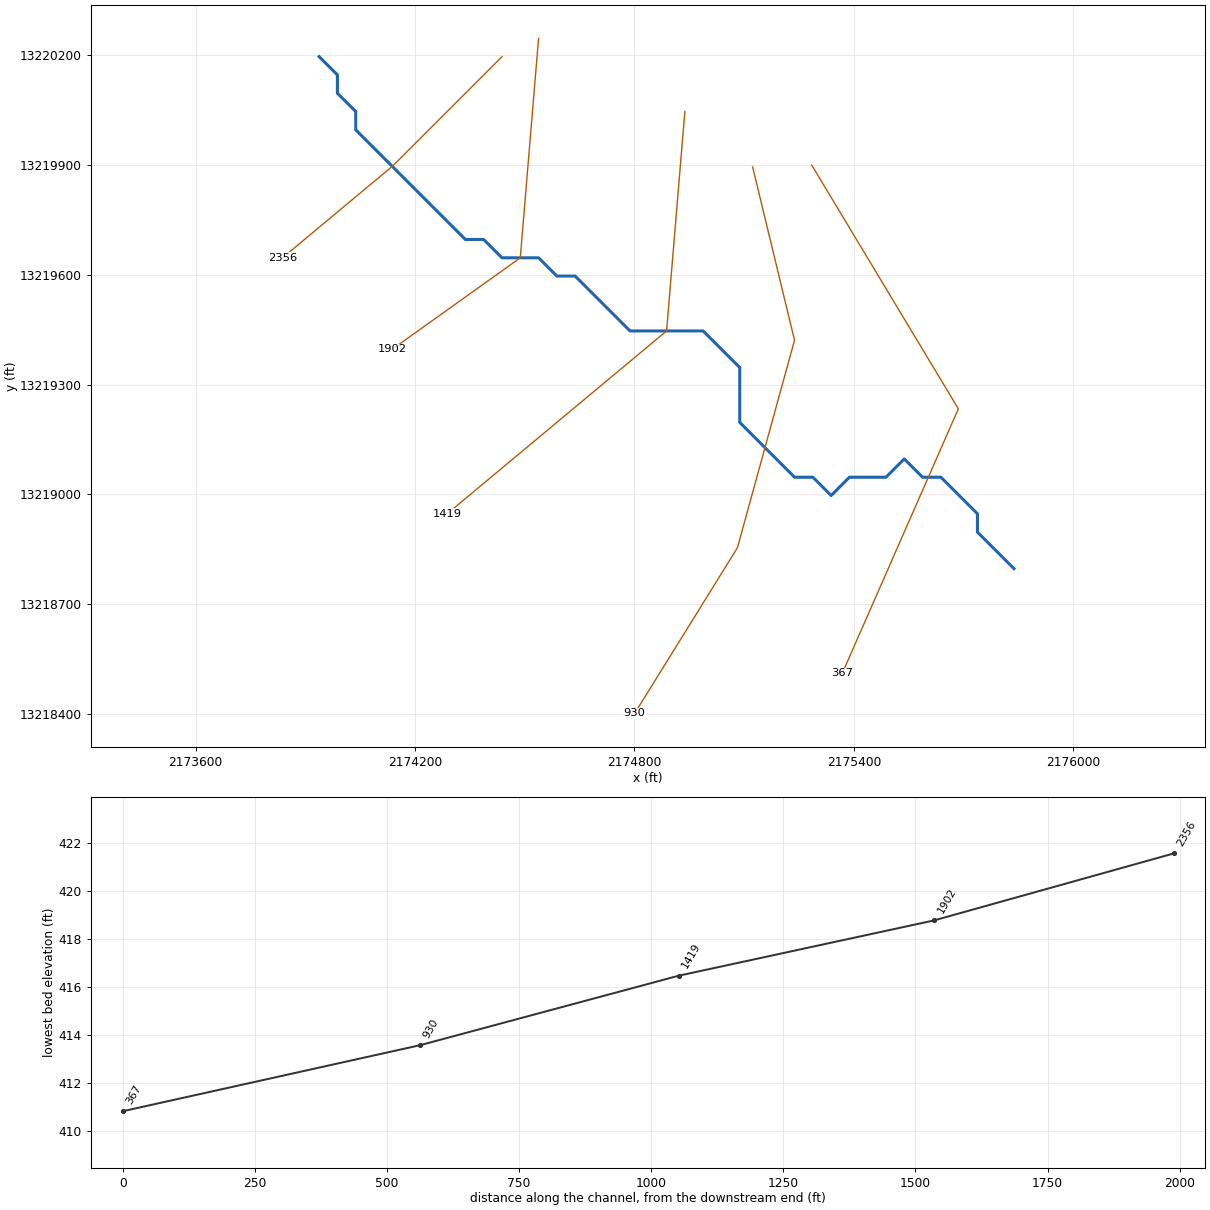
--- UNT 126 IN LACR.prj (project) ---

Proj Title=UNT 126 IN LACR Base Level Engineering
Current Plan=p01
Default Exp/Contr=0.3,0.1
English Units
Geom File=g01
Flow File=f01
Plan File=p01
BEGIN DESCRIPTION:
UNT 126 IN LACR
END DESCRIPTION:

--- UNT 126 IN LACR.p01 (plan) ---

Plan Title=Multiple Run
Short Identifier=Multiple
Geom File=g01
Flow File=f01
Subcritical Flow
K Sum by GR= 0
Std Step Tol= 0.01
Critical Tol= 0.01
Num of Std Step Trials= 20
Max Error Tol= 0.3
Flow Tol Ratio= 0.001
Split Flow NTrial= 30
Split Flow Tol= 0.02
Split Flow Ratio= 0.02
Log Output Level= 0
Friction Slope Method= 1
Unsteady Friction Slope Method= 2
Unsteady Bridges Friction Slope Method= 1
Parabolic Critical Depth
Global Vel Dist=  1 , 1 , 1
Global Log Level= 0
CheckData=True
Encroach Param= -1, 0, 0, 0
BEGIN DESCRIPTION:
Multiple Run
END DESCRIPTION:

--- UNT 126 IN LACR.f01 (steady flow) ---

Flow Title=Multiple
Number of Profiles=7
Profile Names=10-year,25-year,50-year,1pct_min,100-year,1pct_plu,500-year
River Rch & RM= UNT 126 IN LACR,Reach-1,2356
     125     168     202     180     243     329     356
Boundary for River Rch & Prof#=UNT 126 IN LACR,Reach-1,1
Up Type=0
Dn Type=3
Dn Slope=0.005
Boundary for River Rch & Prof#=UNT 126 IN LACR,Reach-1,2
Up Type=0
Dn Type=3
Dn Slope=0.005
Boundary for River Rch & Prof#=UNT 126 IN LACR,Reach-1,3
Up Type=0
Dn Type=3
Dn Slope=0.005
Boundary for River Rch & Prof#=UNT 126 IN LACR,Reach-1,4
Up Type=0
Dn Type=3
Dn Slope=0.005
Boundary for River Rch & Prof#=UNT 126 IN LACR,Reach-1,5
Up Type=0
Dn Type=3
Dn Slope=0.005
Boundary for River Rch & Prof#=UNT 126 IN LACR,Reach-1,6
Up Type=0
Dn Type=3
Dn Slope=0.005
Boundary for River Rch & Prof#=UNT 126 IN LACR,Reach-1,7
Up Type=0
Dn Type=3
Dn Slope=0.005

--- UNT 126 IN LACR.g01 (geometry) ---

Geom Title=Existing Conditions

River Reach=UNT 126 IN LACR,Reach-1
Reach XY= 30
      2173937.72     13220196.86      2173987.72     13220146.85
      2173987.72     13220096.85      2174037.72     13220046.86
      2174037.72     13219996.85      2174287.72     13219746.85
      2174337.72     13219696.86      2174387.72     13219696.86
      2174437.72     13219646.85      2174537.72     13219646.85
      2174587.72     13219596.85      2174637.72     13219596.85
      2174687.72     13219546.86      2174787.72     13219446.85
      2174987.72     13219446.85      2175037.72     13219396.86
      2175087.72     13219346.85      2175087.72     13219196.85
      2175187.72     13219096.85      2175237.72     13219046.86
      2175287.72     13219046.86      2175337.72     13218996.85
      2175387.72     13219046.86      2175487.72     13219046.86
      2175537.72     13219096.85      2175587.72     13219046.86
      2175637.72     13219046.86      2175737.72     13218946.85
      2175737.72     13218896.86      2175837.72     13218796.85

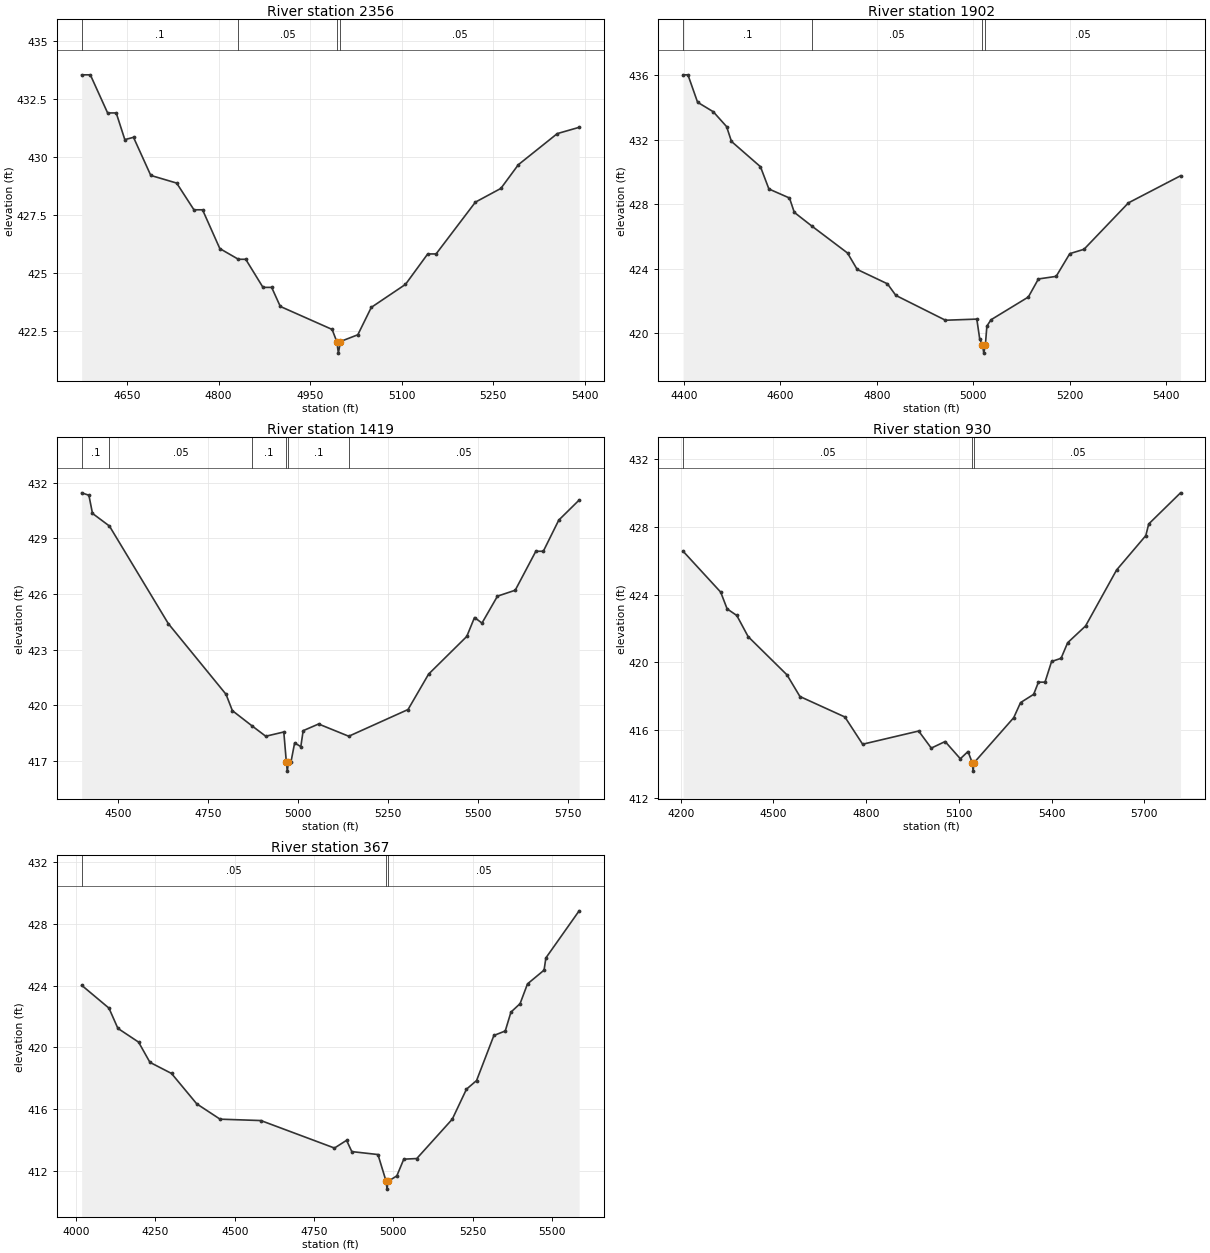
Type RM Length L Ch R = 1,2356,454,454,454
BEGIN DESCRIPTION:
UNT 126 IN LACR 4.0
END DESCRIPTION:
XS GIS Cut Line= 3
      2174437.75     13220196.88      2174137.72     13219896.85
      2173837.73     13219646.86
#Sta/Elev= 30
  4575.7  433.53  4589.9  433.53  4618.2  431.89  4632.3  431.89  4646.4  430.74
  4660.6  430.84  4688.9  429.20  4731.3  428.87  4759.6  427.72  4773.7  427.72
  4802.0  426.05  4832.4  425.59  4844.4  425.59  4872.7  424.38  4886.9  424.38
  4901.0  423.56  4985.9  422.57  4993.5  422.05  4996.2  421.55  4999.5  422.05
  5028.0  422.34  5050.1  423.52  5106.1  424.51  5142.5  425.82  5156.2  425.82
  5220.6  428.05  5262.3  428.64  5290.9  429.66  5354.7  431.00  5390.5  431.27
#Mann=4,-1,0
  4575.7     0.1       0  4832.4    0.05       0  4993.5    0.03       0
  4999.5    0.05       0
Bank Sta=4993.5,4999.5
Exp/Cntr=0.3,0.1

Type RM Length L Ch R = 1,1902,483,483,483
BEGIN DESCRIPTION:
UNT 126 IN LACR 3.0
END DESCRIPTION:
XS GIS Cut Line= 3
      2174537.72     13220246.88      2174487.72     13219646.85
      2174137.73     13219396.86
#Sta/Elev= 30
  4397.9  436.02  4408.0  436.02  4428.0  434.32  4460.6  433.73  4488.2  432.81
  4498.3  431.89  4558.5  430.32  4576.0  428.94  4618.7  428.38  4628.7  427.49
  4665.1  426.64  4739.1  424.97  4759.2  423.95  4821.9  423.06  4839.4  422.34
  4942.3  420.80  5007.4  420.87  5013.5  419.62  5019.1  419.26  5021.9  418.76
  5025.1  419.26  5028.3  420.44  5036.9  420.83  5114.3  422.24  5135.2  423.36
  5172.0  423.52  5200.3  424.93  5229.8  425.20  5322.0  428.08  5430.1  429.76
#Mann=4,-1,0
  4397.9     0.1       0  4665.1    0.05       0  5019.1    0.03       0
  5025.1    0.05       0
Bank Sta=5019.1,5025.1
Exp/Cntr=0.3,0.1

Type RM Length L Ch R = 1,1419,489,489,489
BEGIN DESCRIPTION:
UNT 126 IN LACR 2.0
END DESCRIPTION:
XS GIS Cut Line= 3
      2174937.72     13220046.88      2174887.72     13219446.85
      2174287.74     13218946.87
#Sta/Elev= 30
  4397.9  431.46  4418.0  431.33  4428.0  430.35  4475.1  429.67  4638.8  424.41
  4799.3  420.60  4816.9  419.72  4871.5  418.90  4909.7  418.34  4959.9  418.57
  4966.9  416.96  4969.6  416.46  4972.9  416.96  4979.9  416.96  4990.0  417.98
  5007.2  417.78  5013.7  418.64  5056.6  419.00  5140.5  418.34  5305.3  419.78
  5362.5  421.69  5468.6  423.72  5490.1  424.74  5510.9  424.44  5553.9  425.89
  5603.3  426.21  5660.6  428.31  5681.4  428.31  5724.4  429.99  5781.0  431.07
#Mann=6,-1,0
  4397.9     0.1       0  4475.1    0.05       0  4871.5     0.1       0
  4966.9    0.07       0  4972.9     0.1       0  5140.5    0.05       0
Bank Sta=4966.9,4972.9
Exp/Cntr=0.3,0.1

Type RM Length L Ch R = 1,930,563,563,563
BEGIN DESCRIPTION:
Mapping XS 53254e31
END DESCRIPTION:
XS GIS Cut Line= 4
      2175122.97     13219895.35      2175237.55     13219421.39
      2175081.30     13218853.68      2174800.45     13218401.19
#Sta/Elev= 30
  4207.9  426.57  4329.6  424.15  4350.4  423.16  4381.7  422.77  4418.4  421.52
  4544.0  419.26  4585.9  417.98  4731.3  416.77  4788.7  415.16  4969.9  415.94
  5010.7  414.93  5055.5  415.32  5104.7  414.30  5129.5  414.73  5143.2  414.07
  5146.0  413.57  5149.2  414.07  5277.4  416.73  5299.4  417.62  5341.9  418.11
  5357.3  418.83  5378.5  418.83  5399.8  420.05  5430.5  420.24  5451.8  421.16
  5509.7  422.15  5610.1  425.46  5704.5  427.49  5714.0  428.18  5816.9  430.02
#Mann=3,-1,0
  4207.9    0.05       0  5143.2    0.03       0  5149.2    0.05       0
Bank Sta=5143.2,5149.2
Exp/Cntr=0.3,0.1

Type RM Length L Ch R = 1,367,0,0,0
BEGIN DESCRIPTION:
UNT 126 IN LACR 1.0
END DESCRIPTION:
XS GIS Cut Line= 3
      2175284.45     13219900.51      2175685.47     13219233.89
      2175368.19     13218510.89
#Sta/Elev= 30
  4017.8  424.02  4103.8  422.54  4131.9  421.23  4197.1  420.34  4232.9  419.03
  4300.9  418.31  4380.5  416.34  4453.9  415.35  4582.5  415.26  4814.4  413.48
  4852.5  413.98  4869.0  413.25  4951.4  413.06  4977.2  411.32  4980.0  410.82
  4983.2  411.32  5010.9  411.68  5032.8  412.76  5073.7  412.80  5185.6  415.35
  5230.2  417.29  5262.1  417.85  5316.7  420.77  5352.5  421.06  5370.4  422.28
  5399.2  422.83  5422.6  424.11  5474.8  425.00  5480.5  425.79  5585.3  428.84
#Mann=3,-1,0
  4017.8    0.05       0  4977.2    0.03       0  4983.2    0.05       0
Bank Sta=4977.2,4983.2
Exp/Cntr=0.3,0.1

Chan Stop Cuts=-1