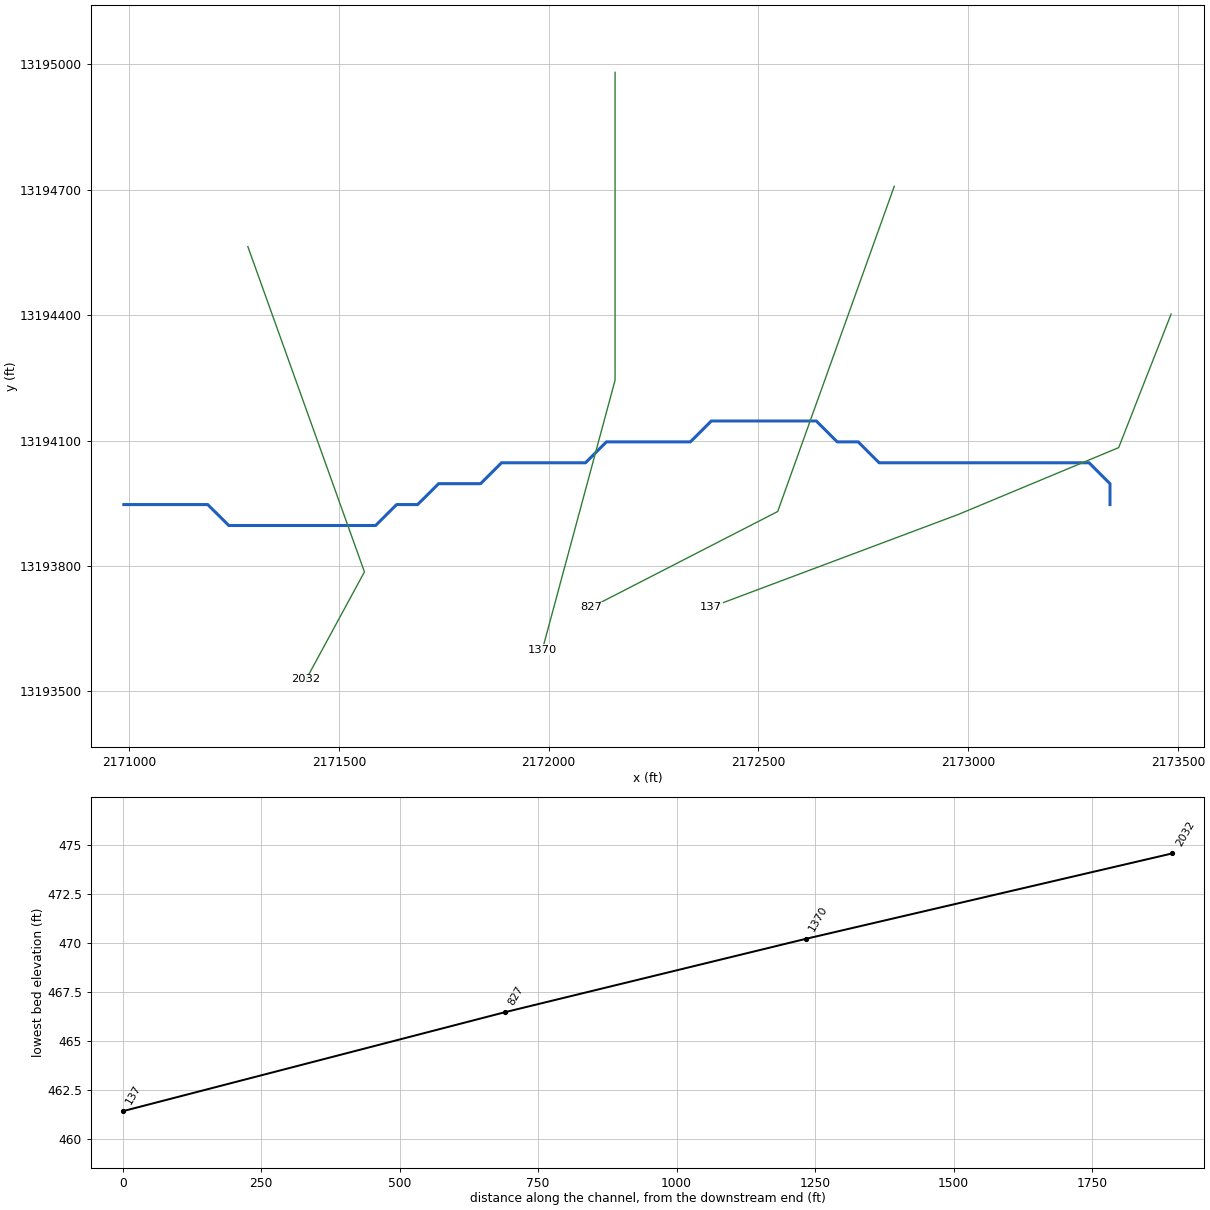
--- UNT 130 IN LACR.prj (project) ---

Proj Title=UNT 130 IN LACR Base Level Engineering
Current Plan=p01
Default Exp/Contr=0.3,0.1
English Units
Geom File=g01
Flow File=f01
Plan File=p01
Y Axis Title=Elevation
X Axis Title(PF)=Main Channel Distance
X Axis Title(XS)=Station
BEGIN DESCRIPTION:
UNT 130 IN LACR
END DESCRIPTION:
DSS Export Rating Curves= 0
DSS Export Rating Curve Sorted= 0
DSS Export Volume Flow Curves= 0
DXF OffsetX= 0
DXF OffsetY= 0
DXF ScaleX= 1
DXF ScaleY= 10

--- UNT 130 IN LACR.p01 (plan) ---

Plan Title=Multiple Run
Short Identifier=Multiple
Geom File=g01
Flow File=f01
Subcritical Flow
K Sum by GR= 0
Std Step Tol= 0.01
Critical Tol= 0.01
Num of Std Step Trials= 20
Max Error Tol= 0.3
Flow Tol Ratio= 0.001
Split Flow NTrial= 30
Split Flow Tol= 0.02
Split Flow Ratio= 0.02
Log Output Level= 0
Friction Slope Method= 1
Unsteady Friction Slope Method= 2
Unsteady Bridges Friction Slope Method= 1
Parabolic Critical Depth
Global Vel Dist=  1 , 1 , 1
Global Log Level= 0
CheckData=True
Encroach Param= -1, 0, 0, 0
BEGIN DESCRIPTION:
Multiple Run
END DESCRIPTION:

--- UNT 130 IN LACR.f01 (steady flow) ---

Flow Title=Multiple
Program Version=4.10
Number of Profiles= 7
Profile Names=10-year,25-year,50-year,1pct_min,100-year,1pct_plu,500-year
River Rch & RM=UNT 130 IN LACR,Reach-1         ,2032
     156     215     263     237     321     434     487
River Rch & RM=UNT 130 IN LACR,Reach-1         ,137
     156     215     263     237     321     434     487
Boundary for River Rch & Prof#=UNT 130 IN LACR,Reach-1         , 1
Up Type= 0
Dn Type= 3
Dn Slope=0.008
Boundary for River Rch & Prof#=UNT 130 IN LACR,Reach-1         , 2
Up Type= 0
Dn Type= 3
Dn Slope=0.008
Boundary for River Rch & Prof#=UNT 130 IN LACR,Reach-1         , 3
Up Type= 0
Dn Type= 3
Dn Slope=0.008
Boundary for River Rch & Prof#=UNT 130 IN LACR,Reach-1         , 4
Up Type= 0
Dn Type= 3
Dn Slope=0.008
Boundary for River Rch & Prof#=UNT 130 IN LACR,Reach-1         , 5
Up Type= 0
Dn Type= 3
Dn Slope=0.008
Boundary for River Rch & Prof#=UNT 130 IN LACR,Reach-1         , 6
Up Type= 0
Dn Type= 3
Dn Slope=0.008
Boundary for River Rch & Prof#=UNT 130 IN LACR,Reach-1         , 7
Up Type= 0
Dn Type= 3
Dn Slope=0.008
DSS Import GetInterval= 0
DSS Import GetPeak= 0
DSS Import FillOption= 0

--- UNT 130 IN LACR.g01 (geometry) ---

Geom Title=Existing Conditions
Program Version=4.10

River Reach=UNT 130 IN LACR ,Reach-1
Reach XY= 20
      2170987.72     13193946.86      2171187.72     13193946.86
      2171237.72     13193896.85      2171587.72     13193896.85
      2171637.72     13193946.86      2171687.72     13193946.86
      2171737.72     13193996.85      2171837.72     13193996.85
      2171887.72     13194046.85      2172087.72     13194046.85
      2172137.72     13194096.85      2172337.72     13194096.85
      2172387.72     13194146.85      2172637.72     13194146.85
      2172687.72     13194096.85      2172737.72     13194096.85
      2172787.72     13194046.85      2173287.72     13194046.85
      2173337.72     13193996.85      2173337.72     13193946.86

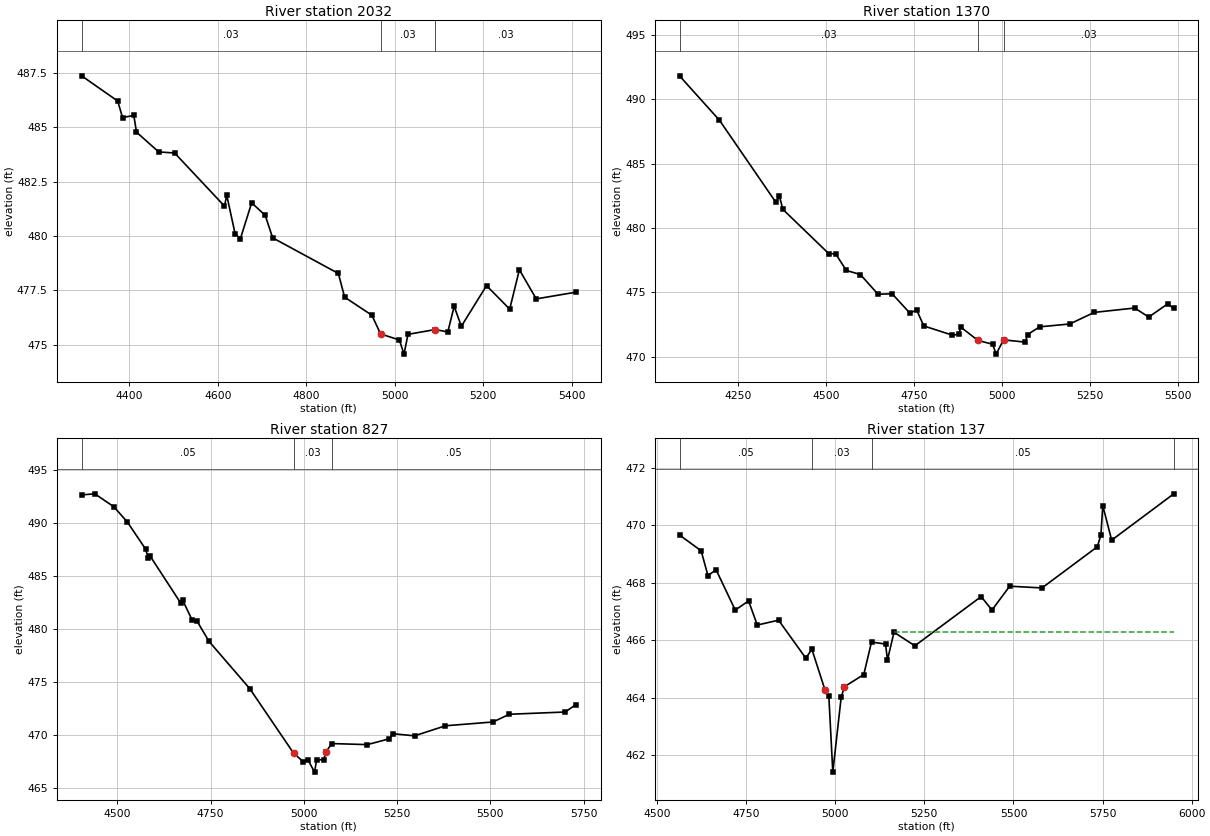
Type RM Length L Ch R = 1 ,2032    ,662,662,662
BEGIN DESCRIPTION:
UNT 130 IN LACR 2.0
END DESCRIPTION:
XS GIS Cut Line= 3
      2171283.27      13194563.7      2171561.04     13193785.95
      2171422.17     13193529.05
#Sta/Elev= 30
  4291.9  487.37  4373.5  486.21  4384.4  485.45  4409.9  485.55    4416  484.78
  4466.2  483.87  4502.3  483.82  4614.9  481.38  4620.2  481.87    4639  480.11
    4651  479.88  4676.5  481.53  4707.2  480.95  4723.9  479.92  4872.6  478.28
  4886.7  477.19  4948.3  476.36  4968.1   475.5  5010.6  475.22    5021  474.57
  5030.1  475.48  5091.6   475.7  5120.1  475.59  5134.5  476.77  5150.7  475.85
  5207.7  477.72  5260.1  476.64    5282  478.45  5320.1  477.11  5409.8  477.42
#Mann= 3 , 0 , 0
  4291.9     .03       0  4968.1     .03       0  5091.6     .03       0
Bank Sta=4968.1,5091.6
XS Rating Curve= 0 ,0
Exp/Cntr=0.3,0.1

Type RM Length L Ch R = 1 ,1370    ,543,543,543
BEGIN DESCRIPTION:
Mapping XS e962824e
END DESCRIPTION:
XS GIS Cut Line= 3
      2172158.26     13194980.39      2172158.26     13194244.29
      2171985.11     13193600.15
#Sta/Elev= 30
  4084.2  491.82  4197.7  488.37  4357.7     482  4367.7  482.48  4377.7  481.45
  4507.7  478.02  4527.7  477.99  4557.7  476.71  4597.7  476.39  4647.7  474.86
  4687.7   474.9  4737.7  473.41  4757.7  473.62  4777.7   472.4  4859.1  471.68
  4877.4  471.76  4882.6  472.31  4931.5  471.27    4973  470.98  4983.1  470.21
    5004  471.32  5066.2  471.14  5072.1  471.73  5106.8  472.33    5192  472.55
  5261.5  473.45  5376.3  473.79  5416.3  473.09    5470  474.11  5487.3  473.76
#Mann= 3 , 0 , 0
  4084.2     .03       0  4931.5     .03       0    5004     .03       0
Bank Sta=4931.5,5004
XS Rating Curve= 0 ,0
Exp/Cntr=0.3,0.1

Type RM Length L Ch R = 1 ,827     ,690,690,690
BEGIN DESCRIPTION:
Mapping XS cd980680
END DESCRIPTION:
XS GIS Cut Line= 3
      2172823.57     13194708.13      2172545.78     13193930.31
      2172102.04     13193701.51
#Sta/Elev= 30
    4404  492.67  4439.4  492.77  4490.3  491.55  4526.5  490.11  4575.3  487.56
  4582.7  486.69  4588.1  486.86  4669.8  482.44  4675.1   482.7  4700.6  480.82
  4713.3  480.75  4745.2  478.84  4854.6  474.37  4972.5  468.25  4997.9  467.47
  5010.6  467.65  5028.5  466.47    5034  467.61  5053.1  467.66  5059.5  468.38
  5074.3  469.17  5169.9  469.07  5229.1  469.62    5239   470.1  5296.5   469.9
  5379.5  470.85  5506.8  471.21  5551.1  471.94  5700.3  472.15  5729.2  472.85
#Mann= 3 ,-1 , 0
    4404     .05       0  4972.5     .03       0  5074.3     .05       0
Bank Sta=4972.5,5059.5
XS Rating Curve= 0 ,0
Exp/Cntr=0.3,0.1

Type RM Length L Ch R = 1 ,137     ,0,0,0
BEGIN DESCRIPTION:
UNT 130 IN LACR 1.0
END DESCRIPTION:
XS GIS Cut Line= 4
      2173483.26     13194402.49      2173358.28     13194083.09
      2172976.34     13193923.37        2172387.      13193701.5
#Sta/Elev= 30
  4563.1  469.66  4623.8  469.11  4642.9  468.25  4665.8  468.45  4719.5  467.05
  4756.9  467.37  4781.3  466.53    4841   466.7  4917.5  465.38  4934.5  465.69
  4971.7  464.26  4982.1  464.06  4993.2  461.42  5016.7  464.02  5025.9  464.39
  5080.1  464.81  5101.8  465.94  5141.1  465.87  5146.6  465.32  5164.9  466.28
  5223.4  465.81  5409.5  467.52  5439.7  467.05  5489.4  467.88  5580.1  467.82
  5735.3  469.25  5745.4  469.66  5750.7  470.68  5775.6  469.48  5949.8  471.09
#Mann= 4 ,-1 , 0
  4563.1     .05       0  4934.5     .03       0  5101.8     .05       0
  5949.8      .1       0
#XS Ineff= 2 , 0
                         5164.96          466.28
Permanent Ineff=
       F       F
Bank Sta=4971.7,5025.9
XS Rating Curve= 0 ,0
Exp/Cntr=0.3,0.1

Chan Stop Cuts=-1
Use User Specified Reach Order=0
Composite Channel Slope=5