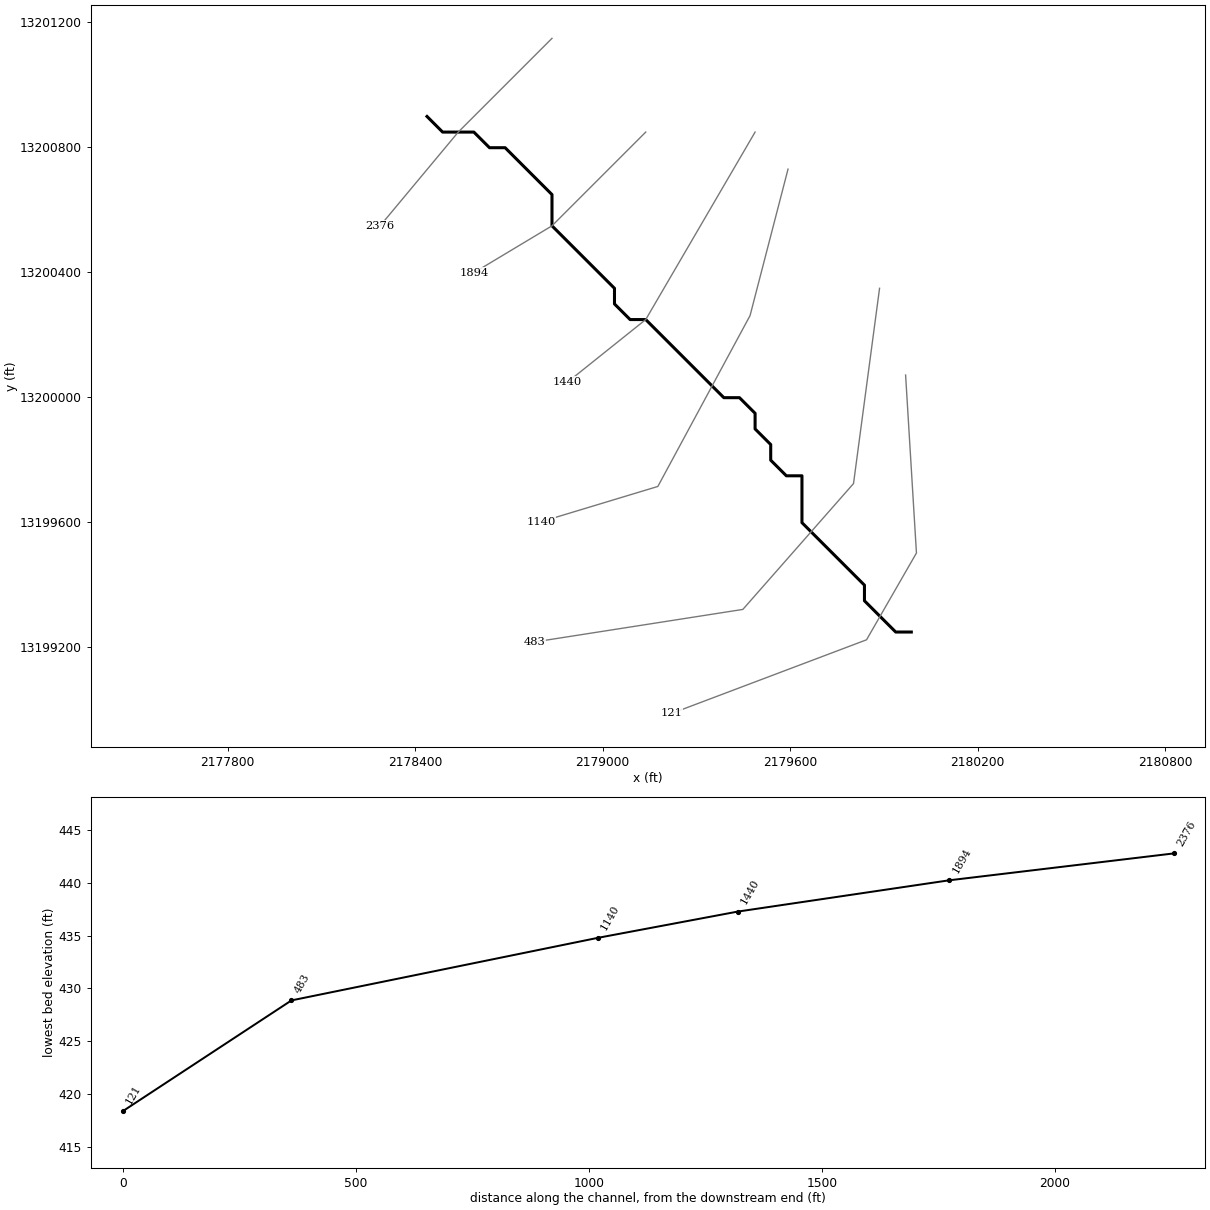
--- UNT 131 IN LACR.prj (project) ---

Proj Title=UNT 131 IN LACR Base Level Engineering
Current Plan=p01
Default Exp/Contr=0.3,0.1
English Units
Geom File=g01
Flow File=f01
Plan File=p01
Y Axis Title=Elevation
X Axis Title(PF)=Main Channel Distance
X Axis Title(XS)=Station
BEGIN DESCRIPTION:
UNT 131 IN LACR
END DESCRIPTION:
DSS Export Rating Curves= 0
DSS Export Rating Curve Sorted= 0
DSS Export Volume Flow Curves= 0
DXF OffsetX= 0
DXF OffsetY= 0
DXF ScaleX= 1
DXF ScaleY= 10

--- UNT 131 IN LACR.p01 (plan) ---

Plan Title=Multiple Run
Short Identifier=Multiple
Geom File=g01
Flow File=f01
Subcritical Flow
K Sum by GR= 0
Std Step Tol= 0.01
Critical Tol= 0.01
Num of Std Step Trials= 20
Max Error Tol= 0.3
Flow Tol Ratio= 0.001
Split Flow NTrial= 30
Split Flow Tol= 0.02
Split Flow Ratio= 0.02
Log Output Level= 0
Friction Slope Method= 1
Unsteady Friction Slope Method= 2
Unsteady Bridges Friction Slope Method= 1
Parabolic Critical Depth
Global Vel Dist=  1 , 1 , 1
Global Log Level= 0
CheckData=True
Encroach Param= -1, 0, 0, 0
BEGIN DESCRIPTION:
Multiple Run
END DESCRIPTION:

--- UNT 131 IN LACR.f01 (steady flow) ---

Flow Title=Multiple
Program Version=4.10
Number of Profiles= 7
Profile Names=10-year,25-year,50-year,1pct_min,100-year,1pct_plu,500-year
River Rch & RM=UNT 131 IN LACR,Reach-1         ,2376
     152     209     256     231     313     423     474
River Rch & RM=UNT 131 IN LACR,Reach-1         ,121
     860    1279    1650    1559    2109    2852    3506
Boundary for River Rch & Prof#=UNT 131 IN LACR,Reach-1         , 1
Up Type= 0
Dn Type= 3
Dn Slope=0.03
Boundary for River Rch & Prof#=UNT 131 IN LACR,Reach-1         , 2
Up Type= 0
Dn Type= 3
Dn Slope=0.03
Boundary for River Rch & Prof#=UNT 131 IN LACR,Reach-1         , 3
Up Type= 0
Dn Type= 3
Dn Slope=0.03
Boundary for River Rch & Prof#=UNT 131 IN LACR,Reach-1         , 4
Up Type= 0
Dn Type= 3
Dn Slope=0.03
Boundary for River Rch & Prof#=UNT 131 IN LACR,Reach-1         , 5
Up Type= 0
Dn Type= 3
Dn Slope=0.03
Boundary for River Rch & Prof#=UNT 131 IN LACR,Reach-1         , 6
Up Type= 0
Dn Type= 3
Dn Slope=0.03
Boundary for River Rch & Prof#=UNT 131 IN LACR,Reach-1         , 7
Up Type= 0
Dn Type= 3
Dn Slope=0.03
DSS Import GetInterval= 0
DSS Import GetPeak= 0
DSS Import FillOption= 0

--- UNT 131 IN LACR.g01 (geometry) ---

Geom Title=Existing Conditions
Program Version=4.10

River Reach=UNT 131 IN LACR ,Reach-1
Reach XY= 30
      2178437.72     13200896.85      2178487.72     13200846.86
      2178587.72     13200846.86      2178637.72     13200796.85
      2178687.72     13200796.85      2178787.72     13200696.86
      2178837.72     13200646.85      2178837.72     13200546.85
      2178987.72     13200396.85      2179037.72     13200346.86
      2179037.72     13200296.85      2179087.72     13200246.85
      2179137.72     13200246.85      2179187.72     13200196.86
      2179237.72     13200146.85      2179387.72     13199996.85
      2179437.72     13199996.85      2179487.72     13199946.85
      2179487.72     13199896.85      2179537.72     13199846.86
      2179537.72     13199796.85      2179587.72     13199746.85
      2179637.72     13199746.85      2179637.72     13199596.85
      2179687.72     13199546.86      2179737.72     13199496.85
      2179837.72     13199396.85      2179837.72     13199346.85
      2179937.72     13199246.85      2179987.72     13199246.85

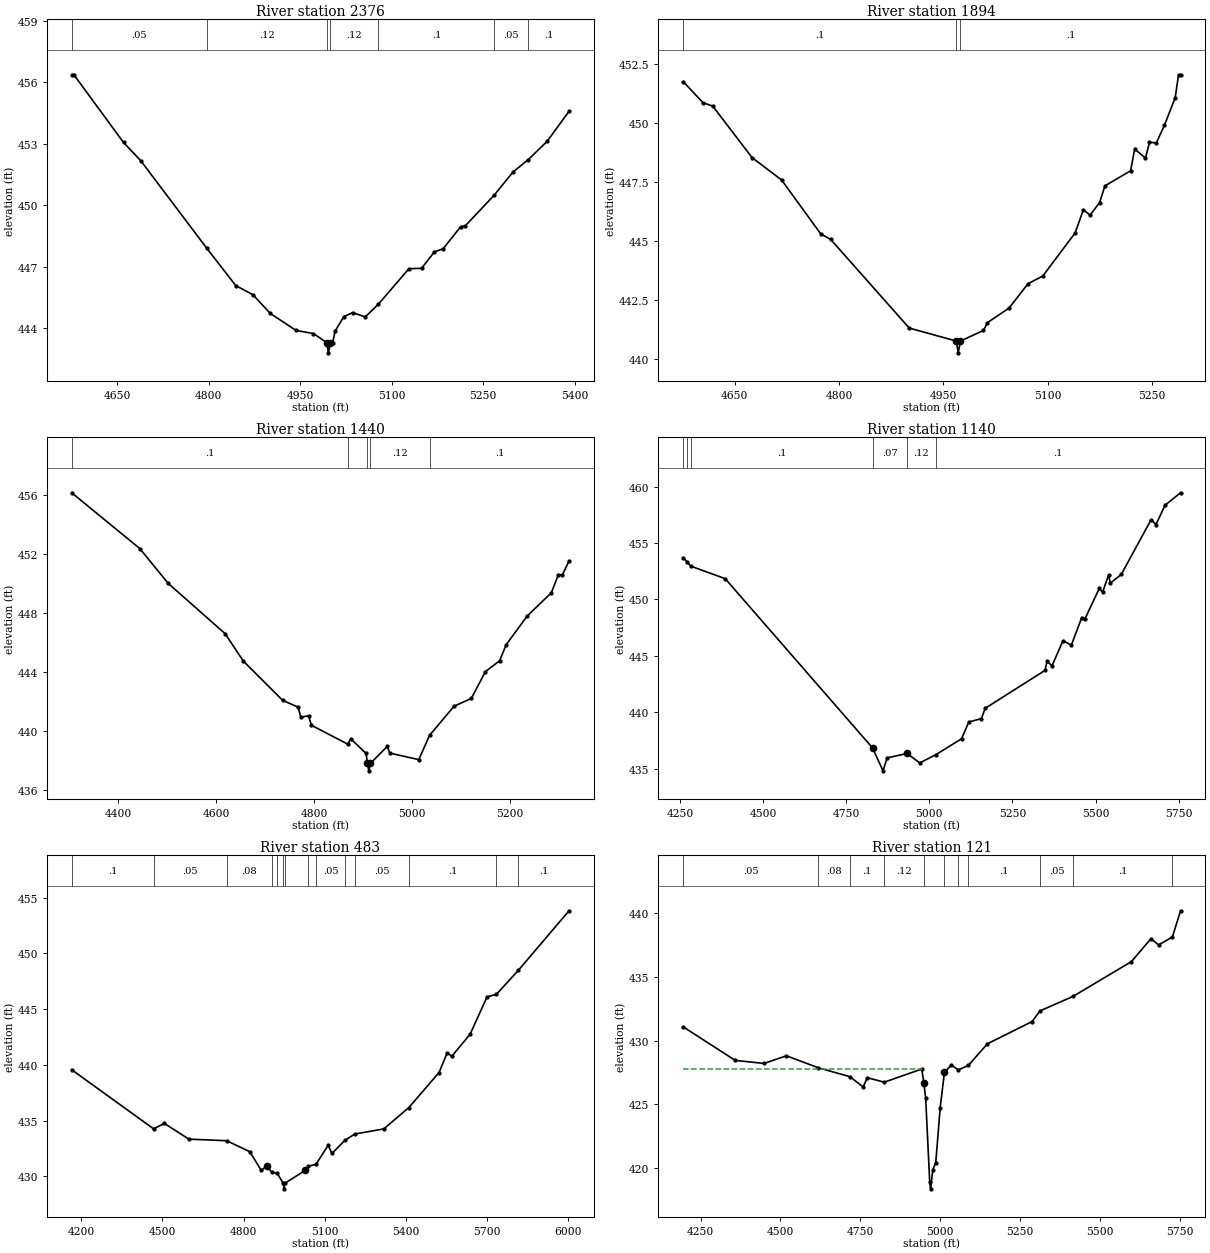
Type RM Length L Ch R = 1 ,2376    ,482,482,482
BEGIN DESCRIPTION:
UNT 131 IN LACR 4.0
END DESCRIPTION:
XS GIS Cut Line= 3
      2178837.75     13201146.88      2178537.72     13200846.86
      2178287.73     13200546.86
#Sta/Elev= 30
  4575.7  456.36  4579.3  456.36  4660.6  453.06  4688.9  452.17  4796.9  447.91
  4844.4  446.09  4872.7  445.64    4901  444.73  4943.4   443.9  4971.7  443.75
  4993.5  443.31  4996.2  442.81  4999.5  443.31  5003.3  443.31  5007.2  443.87
  5021.5  444.57  5035.8  444.77  5056.6  444.56  5078.1  445.18  5128.2  446.91
    5149  446.93  5169.9  447.73  5184.2  447.88  5212.8  448.95  5220.6     449
  5268.1   450.5  5298.7  451.62  5323.5  452.22  5354.7  453.12  5390.5  454.58
#Mann= 7 ,-1 , 0
  4575.7     .05       0  4796.9     .12       0  4993.5     .07       0
  4999.5     .12       0  5078.1      .1       0  5268.1     .05       0
  5323.5      .1       0
Bank Sta=4993.5,4999.5
XS Rating Curve= 0 ,0
Exp/Cntr=0.3,0.1

Type RM Length L Ch R = 1 ,1894    ,454,454,454
BEGIN DESCRIPTION:
UNT 131 IN LACR 3.0
END DESCRIPTION:
XS GIS Cut Line= 3
      2179137.75     13200846.88      2178837.72     13200546.85
      2178587.76     13200396.88
#Sta/Elev= 30
  4575.7  451.76    4604  450.87  4618.2  450.72  4674.7  448.54  4717.2  447.59
  4773.7   445.3  4787.9  445.07    4901  441.31  4968.7  440.76  4971.5  440.26
  4974.7  440.76  5007.8  441.21  5013.6  441.54  5044.7  442.16  5071.9  443.19
  5093.3  443.52  5139.9  445.35  5151.6  446.33  5161.3   446.1  5174.9  446.63
  5182.7  447.34  5219.6  447.98  5225.5   448.9    5241  448.52  5246.8  449.19
  5256.6  449.16  5268.2   449.9  5283.8  451.08  5288.6  452.05  5291.5  452.05
#Mann= 3 ,-1 , 0
  4575.7      .1       0  4968.7     .07       0  4974.7      .1       0
Bank Sta=4968.7,4974.7
XS Rating Curve= 0 ,0
Exp/Cntr=0.3,0.1

Type RM Length L Ch R = 1 ,1440    ,300,300,300
BEGIN DESCRIPTION:
UNT 131 IN LACR 2.0
END DESCRIPTION:
XS GIS Cut Line= 3
      2179487.71     13200846.84      2179137.72     13200246.85
      2178887.69     13200046.83
#Sta/Elev= 30
  4305.4  456.14  4444.3  452.36  4502.2     450  4618.4  446.59  4655.6  444.73
  4735.8  442.07  4767.2  441.61    4773  440.92  4788.7  441.03  4794.5  440.38
  4868.6   439.1  4874.7  439.46  4906.1  438.47  4908.9  437.79  4911.7  437.29
  4914.9  437.79  4949.1  438.94  4954.9  438.49  5013.6  438.05  5035.7   439.7
  5085.6  441.67  5120.9   442.2  5149.7  444.02  5178.5  444.75  5192.1  445.85
  5234.5  447.77  5284.1  449.36  5298.5  450.59  5306.5  450.56  5320.2  451.52
#Mann= 5 ,-1 , 0
  4305.4      .1       0  4868.6     .12       0  4908.9     .07       0
  4914.9     .12       0  5035.7      .1       0
Bank Sta=4908.9,4914.9
XS Rating Curve= 0 ,0
Exp/Cntr=0.3,0.1

Type RM Length L Ch R = 1 ,1140    ,657,657,657
BEGIN DESCRIPTION:
Mapping XS 92105cb0
END DESCRIPTION:
XS GIS Cut Line= 4
      2179593.16     13200728.36      2179471.63     13200259.61
      2179176.49     13199712.73      2178803.26      13199599.9
#Sta/Elev= 30
  4259.9  453.71    4271  453.33    4283  452.94  4385.9  451.84  4829.3  436.83
  4860.7   434.8  4873.1  435.95  4933.1  436.34  4971.2   435.5  5018.8  436.22
  5096.8  437.64  5118.7  439.13  5156.4  439.43  5168.2  440.35  5348.2  443.71
  5353.8   444.5  5369.1  444.12    5402  446.34    5427  445.94  5458.3  448.38
  5467.9  448.27  5511.3  450.98    5521  450.63    5539  452.17  5544.3  451.44
  5577.2  452.21  5667.3  457.08  5681.3  456.62    5709  458.35  5755.5  459.45
#Mann= 6 ,-1 , 0
  4259.9      .1       0    4271     .08       0    4283      .1       0
  4829.3     .07       0  4933.1     .12       0  5018.8      .1       0
#XS Ineff= 2 , 0
         4829.19  436.82 4932.88          436.33
Permanent Ineff=
       F       F
Bank Sta=4829.3,4933.1
XS Rating Curve= 0 ,0
Exp/Cntr=0.3,0.1

Type RM Length L Ch R = 1 ,483     ,362,362,362
BEGIN DESCRIPTION:
Mapping XS 9faa877b
END DESCRIPTION:
XS GIS Cut Line= 4
      2179886.06     13200346.97      2179802.72     13199721.98
      2179448.56      13199319.2      2178782.31      13199215.1
#Sta/Elev= 30
  4163.9  439.56  4466.9  434.26    4507  434.74  4597.8  433.33  4737.2  433.19
    4823  432.21  4865.7  430.53  4886.5  430.92  4905.1  430.34  4924.6  430.27
  4947.1  429.37  4949.9  428.87  4953.1  429.37  5027.9  430.52  5040.3   430.9
  5068.3  431.07  5113.3  432.78  5127.5  432.05  5175.5  433.23    5212  433.79
  5319.2  434.25  5411.8  436.16  5523.9  439.31  5554.3  441.09  5571.1  440.77
  5638.9  442.75  5701.6   446.1  5736.3  446.33    5818   448.5  6005.1  453.83
#Mann= 14 ,-1 , 0
  4163.9      .1       0  4466.9     .05       0  4737.2     .08       0
  4905.1     .12       0  4924.6     .05       0  4947.1     .04       0
  4953.1     .05       0  5040.3      .1       0  5068.3     .05       0
  5175.5      .1       0    5212     .05       0  5411.8      .1       0
  5736.3     .05       0    5818      .1       0
Bank Sta=4886.5,5027.9
XS Rating Curve= 0 ,0
Exp/Cntr=0.3,0.1

Type RM Length L Ch R = 1 ,121     ,0,0,0
BEGIN DESCRIPTION:
UNT 131 IN LACR 1.0
END DESCRIPTION:
XS GIS Cut Line= 4
      2179969.39     13200069.25      2180004.11     13199499.75
      2179844.39     13199221.98      2179221.06      13198986.5
#Sta/Elev= 30
  4195.6  431.07  4358.3  428.44  4448.5   428.2  4518.6   428.8  4618.7  427.86
  4717.5  427.16    4759  426.36  4772.1  427.08    4825  426.73  4942.5  427.76
  4948.9  426.69  4954.7  425.49  4967.5  418.86  4970.2  418.36  4977.1  419.86
  4986.3  420.41  5000.2  424.73  5013.6  427.52  5035.2  428.07  5057.1   427.7
  5088.3  428.04    5148  429.74  5288.2  431.49  5312.4  432.32  5416.1  433.46
  5598.9  436.19  5660.3  437.99  5684.1   437.5  5727.3  438.12  5752.9  440.18
#Mann= 11 ,-1 , 0
  4195.6     .05       0  4618.7     .08       0  4717.5      .1       0
    4825     .12       0  4948.9     .07       0  5013.6     .12       0
  5057.1     .16       0  5088.3      .1       0  5312.4     .05       0
  5416.1      .1       0  5727.3     .05       0
#XS Ineff= 2 , 0
         4941.93   427.8
Permanent Ineff=
       F       F
Bank Sta=4948.9,5013.6
XS Rating Curve= 0 ,0
Exp/Cntr=0.3,0.1

Chan Stop Cuts=-1
Use User Specified Reach Order=0
Composite Channel Slope=5