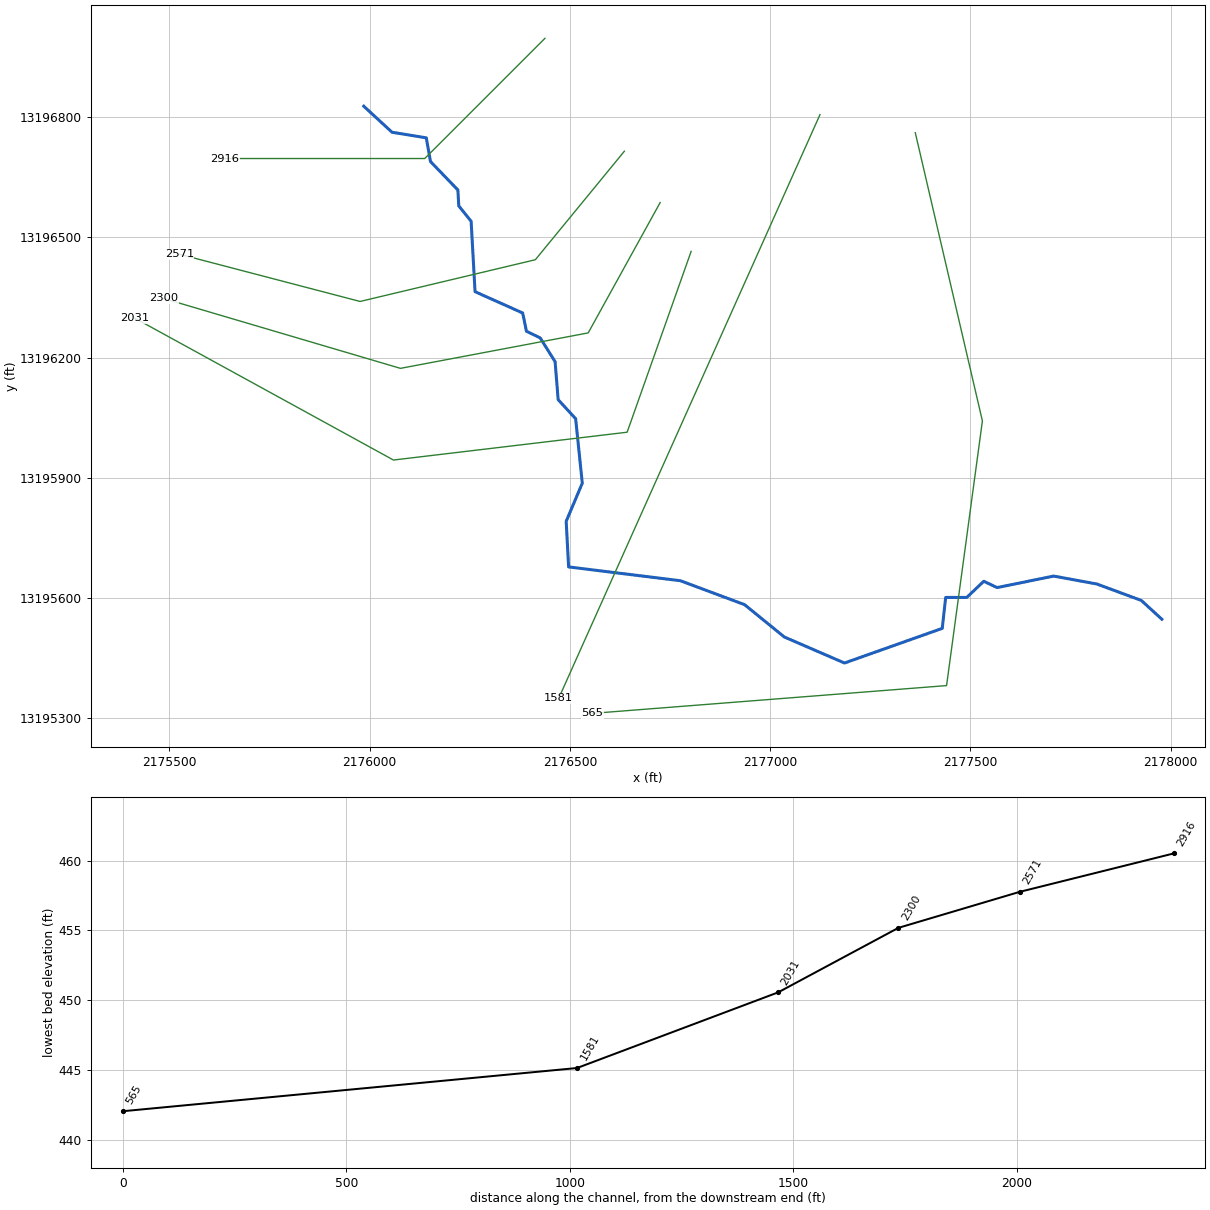
--- UNT 132 IN LACR.prj (project) ---

Proj Title=UNT 132 IN LACR Base Level Engineering
Current Plan=p01
Default Exp/Contr=0.3,0.1
English Units
Geom File=g01
Flow File=f01
Plan File=p01
Y Axis Title=Elevation
X Axis Title(PF)=Main Channel Distance
X Axis Title(XS)=Station
BEGIN DESCRIPTION:
UNT 132 IN LACR
END DESCRIPTION:
DSS Export Rating Curves= 0
DSS Export Rating Curve Sorted= 0
DSS Export Volume Flow Curves= 0
DXF OffsetX= 0
DXF OffsetY= 0
DXF ScaleX= 1
DXF ScaleY= 10

--- UNT 132 IN LACR.p01 (plan) ---

Plan Title=Multiple Run
Short Identifier=Multiple
Geom File=g01
Flow File=f01
Subcritical Flow
K Sum by GR= 0
Std Step Tol= 0.01
Critical Tol= 0.01
Num of Std Step Trials= 20
Max Error Tol= 0.3
Flow Tol Ratio= 0.001
Split Flow NTrial= 30
Split Flow Tol= 0.02
Split Flow Ratio= 0.02
Log Output Level= 0
Friction Slope Method= 1
Unsteady Friction Slope Method= 2
Unsteady Bridges Friction Slope Method= 1
Parabolic Critical Depth
Global Vel Dist=  1 , 1 , 1
Global Log Level= 0
CheckData=True
Encroach Param= -1, 0, 0, 0
BEGIN DESCRIPTION:
Multiple Run
END DESCRIPTION:

--- UNT 132 IN LACR.f01 (steady flow) ---

Flow Title=Multiple
Number of Profiles=7
Profile Names=10-year,25-year,50-year,1pct_min,100-year,1pct_plu,500-year
River Rch & RM= UNT 132 IN LACR,Reach-1,2916
     103     137     165     146     198     267     288
Boundary for River Rch & Prof#=UNT 132 IN LACR,Reach-1,1
Up Type=0
Dn Type=3
Dn Slope=0.005
Boundary for River Rch & Prof#=UNT 132 IN LACR,Reach-1,2
Up Type=0
Dn Type=3
Dn Slope=0.005
Boundary for River Rch & Prof#=UNT 132 IN LACR,Reach-1,3
Up Type=0
Dn Type=3
Dn Slope=0.005
Boundary for River Rch & Prof#=UNT 132 IN LACR,Reach-1,4
Up Type=0
Dn Type=3
Dn Slope=0.005
Boundary for River Rch & Prof#=UNT 132 IN LACR,Reach-1,5
Up Type=0
Dn Type=3
Dn Slope=0.005
Boundary for River Rch & Prof#=UNT 132 IN LACR,Reach-1,6
Up Type=0
Dn Type=3
Dn Slope=0.005
Boundary for River Rch & Prof#=UNT 132 IN LACR,Reach-1,7
Up Type=0
Dn Type=3
Dn Slope=0.005

--- UNT 132 IN LACR.g01 (geometry) ---

Geom Title=Existing Conditions
Program Version=4.10

River Reach=UNT 132 IN LACR ,Reach-1
Reach XY= 30
      2175985.46     13196827.47      2176056.16     13196762.38
      2176141.59     13196748.51      2176152.08     13196689.31
      2176220.43     13196618.34       2176222.7     13196578.48
      2176253.52      13196540.2      2176263.32     13196364.45
      2176382.22     13196311.25      2176391.57     13196265.74
      2176425.95     13196249.02      2176463.13     13196189.71
      2176470.78     13196094.91      2176514.41     13196047.33
      2176531.04     13195886.43      2176490.82     13195791.21
      2176496.88     13195677.38      2176776.06     13195642.85
      2176936.21     13195583.13       2177035.3     13195502.47
      2177185.57     13195437.48      2177429.58     13195523.96
      2177438.17     13195601.17      2177490.82     13195601.26
      2177533.21      13195641.5      2177566.56      13195625.8
      2177707.72     13195654.49      2177815.59      13195634.7
       2177926.4     13195593.76      2177977.72     13195546.85

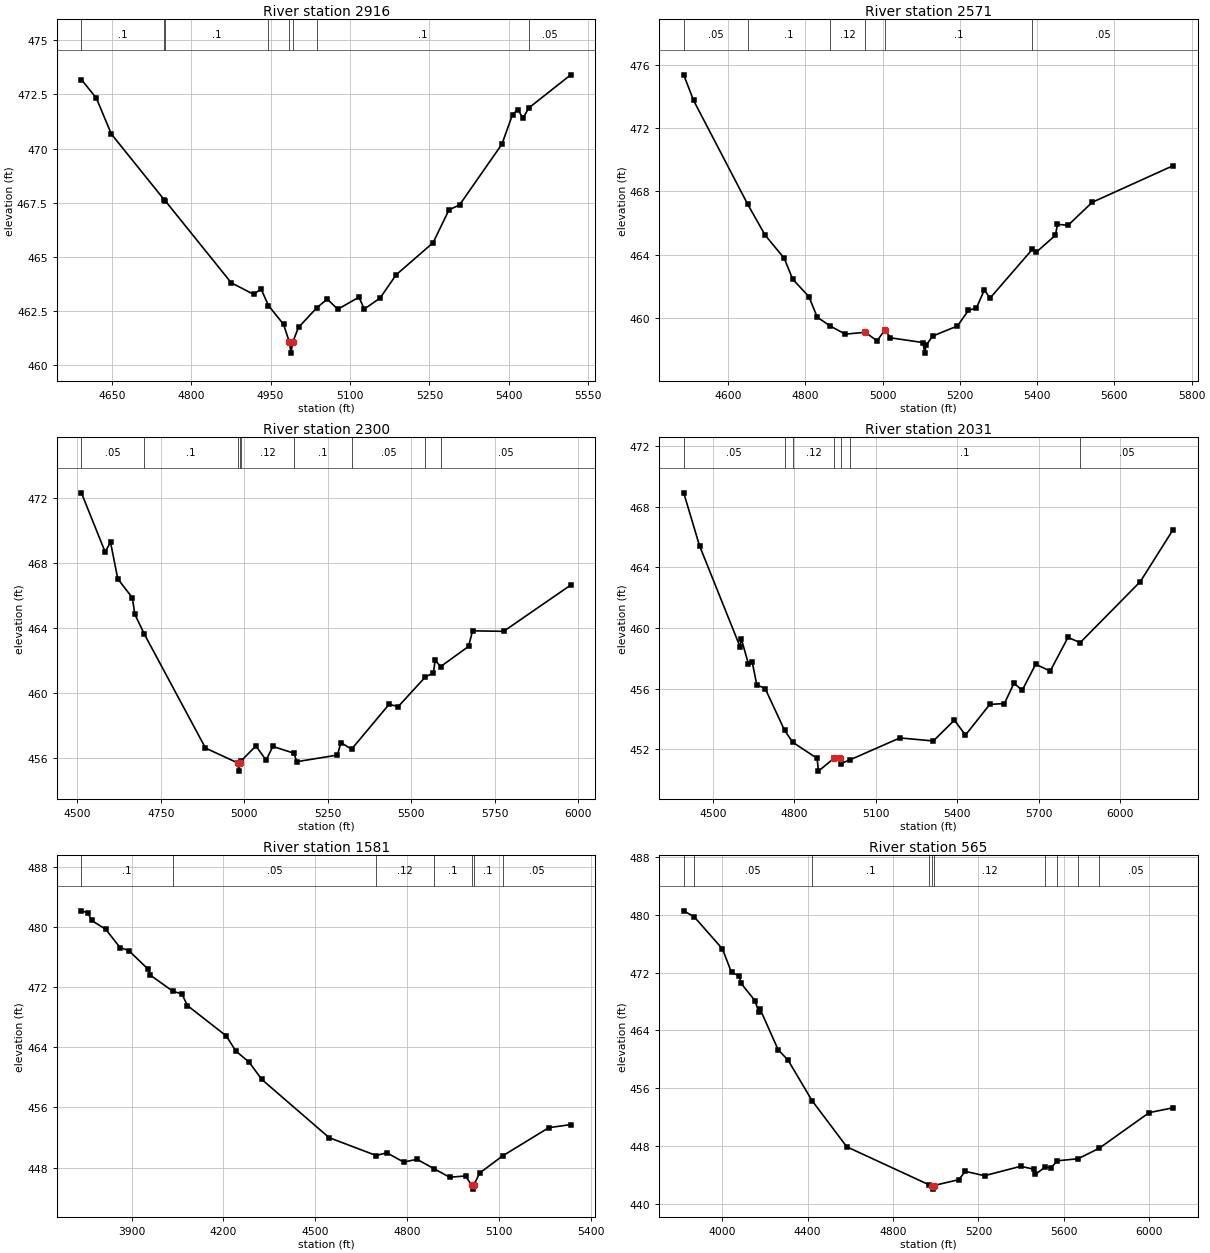
Type RM Length L Ch R = 1 ,2916    ,345,345,345
BEGIN DESCRIPTION:
UNT 132 IN LACR 2.0
END DESCRIPTION:
XS GIS Cut Line= 3
      2176437.74     13196996.87      2176137.72     13196696.85
      2175637.71     13196696.85
#Sta/Elev= 30
  4592.6  473.19  4620.9  472.33  4649.2  470.67    4749  467.63  4751.3  467.57
  4875.5  463.79  4917.9  463.25    4932   463.5    4946  462.73  4974.5  461.86
  4985.6  461.03  4988.4  460.53  4991.6  461.03  5002.7  461.72  5036.9  462.62
  5056.9  463.03  5076.9  462.56  5116.9  463.12  5126.9  462.57  5156.9  463.08
  5186.9  464.15  5256.9  465.64  5286.9  467.16  5306.9  467.39  5386.9   470.2
  5406.9  471.57  5416.9   471.8  5426.9   471.4  5437.3  471.87  5516.9  473.41
#Mann= 8 ,-1 , 0
  4592.6      .1       0    4749     .05       0  4751.3      .1       0
    4946     .12       0  4985.6     .07       0  4991.6     .12       0
  5036.9      .1       0  5437.3     .05       0
Bank Sta=4985.6,4991.6
XS Rating Curve= 0 ,0
Exp/Cntr=0.3,0.1

Type RM Length L Ch R = 1 ,2571    ,271,271,271
BEGIN DESCRIPTION:
Mapping XS 7fcb347f
END DESCRIPTION:
XS GIS Cut Line= 4
      2176636.06     13196715.04      2176413.84      13196444.2
      2175976.34     13196340.03      2175524.98     13196458.08
#Sta/Elev= 30
  4485.3  475.38  4510.8  473.76  4650.9  467.19  4695.9  465.24  4745.5  463.77
  4767.5  462.44  4809.3  461.35  4830.7  460.05  4864.2  459.49  4903.6  458.97
    4955  459.09  4985.8  458.55  5006.4  459.25  5020.1  458.74  5104.4  458.44
  5109.3  457.77  5112.6  458.27  5129.7  458.85  5193.9  459.49  5222.3  460.48
  5242.8  460.62  5263.4  461.77  5278.2  461.25    5388  464.35  5397.6  464.15
  5447.4  465.23  5452.6  465.92  5480.3  465.86  5542.3  467.31  5751.9  469.63
#Mann= 6 ,-1 , 0
  4485.3     .05       0  4650.9      .1       0  4864.2     .12       0
    4955     .07       0  5006.4      .1       0    5388     .05       0
Bank Sta=4955,5006.4
XS Rating Curve= 0 ,0
Exp/Cntr=0.3,0.1

Type RM Length L Ch R = 1 ,2300    ,269,269,269
BEGIN DESCRIPTION:
Mapping XS 834155ac
END DESCRIPTION:
XS GIS Cut Line= 4
      2176725.48     13196587.05      2176545.81     13196261.58
      2176077.06     13196173.03      2175485.89     13196347.52
#Sta/Elev= 30
    4512  472.33  4583.1  468.69  4599.2  469.29    4621  467.03  4664.5  465.87
  4672.1  464.85  4699.9  463.65  4883.6  456.61  4980.6  455.69  4983.4  455.19
  4986.6  455.69  4990.1  455.82  5034.5  456.74    5065  455.87  5085.4  456.71
  5148.8  456.29  5156.7  455.77  5278.7  456.18  5288.9  456.95    5321  456.54
  5433.1   459.3  5460.9  459.17  5541.1  460.97    5566  461.25  5571.2  462.01
  5587.8  461.63  5671.1  462.87  5683.3  463.83  5776.3   463.8  5977.2  466.65
#Mann= 9 ,-1 , 0
    4512     .05       0  4699.9      .1       0  4980.6     .07       0
  4986.6      .1       0  4990.1     .12       0  5148.8      .1       0
    5321     .05       0  5541.1      .1       0  5587.8     .05       0
Bank Sta=4980.6,4986.6
XS Rating Curve= 0 ,0
Exp/Cntr=0.3,0.1

Type RM Length L Ch R = 1 ,2031    ,450,450,450
BEGIN DESCRIPTION:
Mapping XS 8341599e
END DESCRIPTION:
XS GIS Cut Line= 4
      2176802.72     13196465.01        2176643.     13196013.64
      2176059.67      13195944.2      2175413.84     13196298.36
#Sta/Elev= 30
  4392.4  468.92  4450.6  465.43  4599.8  458.77  4605.1  459.26  4630.7  457.64
    4645  457.74  4661.6  456.25  4692.5  456.01  4763.7  453.26  4793.6  452.47
  4883.9   451.4  4888.7  450.56    4947  451.42  4966.5   451.4  4971.5  451.06
  5004.4   451.3  5188.7  452.75  5311.9  452.55  5389.5  453.92  5430.4  452.94
  5519.9  454.96  5573.9  455.02  5609.1  456.36  5639.3  455.89    5689  457.61
  5742.6  457.16    5808  459.38  5853.1  459.04  6074.4  463.06  6195.2  466.49
#Mann= 7 ,-1 , 0
  4392.4     .05       0  4763.7      .1       0  4793.6     .12       0
    4947     .07       0  4971.5     .12       0  5004.4      .1       0
  5853.1     .05       0
Bank Sta=4947,4966.5
XS Rating Curve= 0 ,0
Exp/Cntr=0.3,0.1

Type RM Length L Ch R = 1 ,1581    ,1016,1016,1016
BEGIN DESCRIPTION:
Mapping XS 67552634
END DESCRIPTION:
XS GIS Cut Line= 2
      2177124.42     13196806.51      2176472.16     13195349.33
#Sta/Elev= 30
  3736.4  482.13  3757.9  481.86  3769.7  480.86  3816.1  479.66  3862.5  477.25
  3891.2  476.84  3955.1  474.33  3960.7   473.6  4033.8  471.46  4064.7  471.07
  4082.2  469.54  4209.1   465.5    4240  463.51  4284.2  461.98  4325.1  459.71
  4544.8  451.97    4698   449.6    4733  449.96  4787.7  448.73  4831.6  449.09
  4887.7  447.83  4937.8  446.71  4989.7  446.88  5009.9  445.63  5012.6  445.13
  5015.9  445.63  5036.1  447.28  5110.7  449.55  5261.3   453.3  5332.9  453.71
#Mann= 7 ,-1 , 0
  3736.4      .1       0  4033.8     .05       0    4698     .12       0
  4887.7      .1       0  5009.9     .07       0  5015.9      .1       0
  5110.7     .05       0
Bank Sta=5009.9,5015.9
XS Rating Curve= 0 ,0
Exp/Cntr=0.3,0.1

Type RM Length L Ch R = 1 ,565     ,0,0,0
BEGIN DESCRIPTION:
UNT 132 IN LACR 1.0
END DESCRIPTION:
XS GIS Cut Line= 4
      2177362.25     13196761.36      2177529.81      13196041.8
      2177440.38     13195381.14        2176556.     13195311.77
#Sta/Elev= 30
  3819.5  480.57  3869.5  479.71  4000.9   475.3  4043.5  472.03  4080.8  471.55
    4086  470.61  4152.7  468.15  4171.2  466.58  4176.3  467.02  4261.5  461.36
  4309.2  459.85  4420.4   454.3  4583.5  447.89  4968.1  442.64    4985  442.53
  4987.8  442.03    4991  442.53  5108.2  443.34  5138.5  444.49  5228.8  443.89
  5398.2  445.19  5458.4   444.8  5467.5  444.07    5514  445.13  5538.6  444.91
    5569  445.95  5667.2  446.24  5765.4  447.68    6000  452.62  6112.1   453.3
#Mann= 10 ,-1 , 0
  3819.5      .1       0  3869.5     .05       0  4420.4      .1       0
  4968.1     .12       0    4985     .07       0    4991     .12       0
    5514      .1       0    5569     .12       0  5667.2      .1       0
  5765.4     .05       0
Bank Sta=4985,4991
XS Rating Curve= 0 ,0
Exp/Cntr=0.3,0.1

Chan Stop Cuts=-1
Use User Specified Reach Order=0
Composite Channel Slope=5