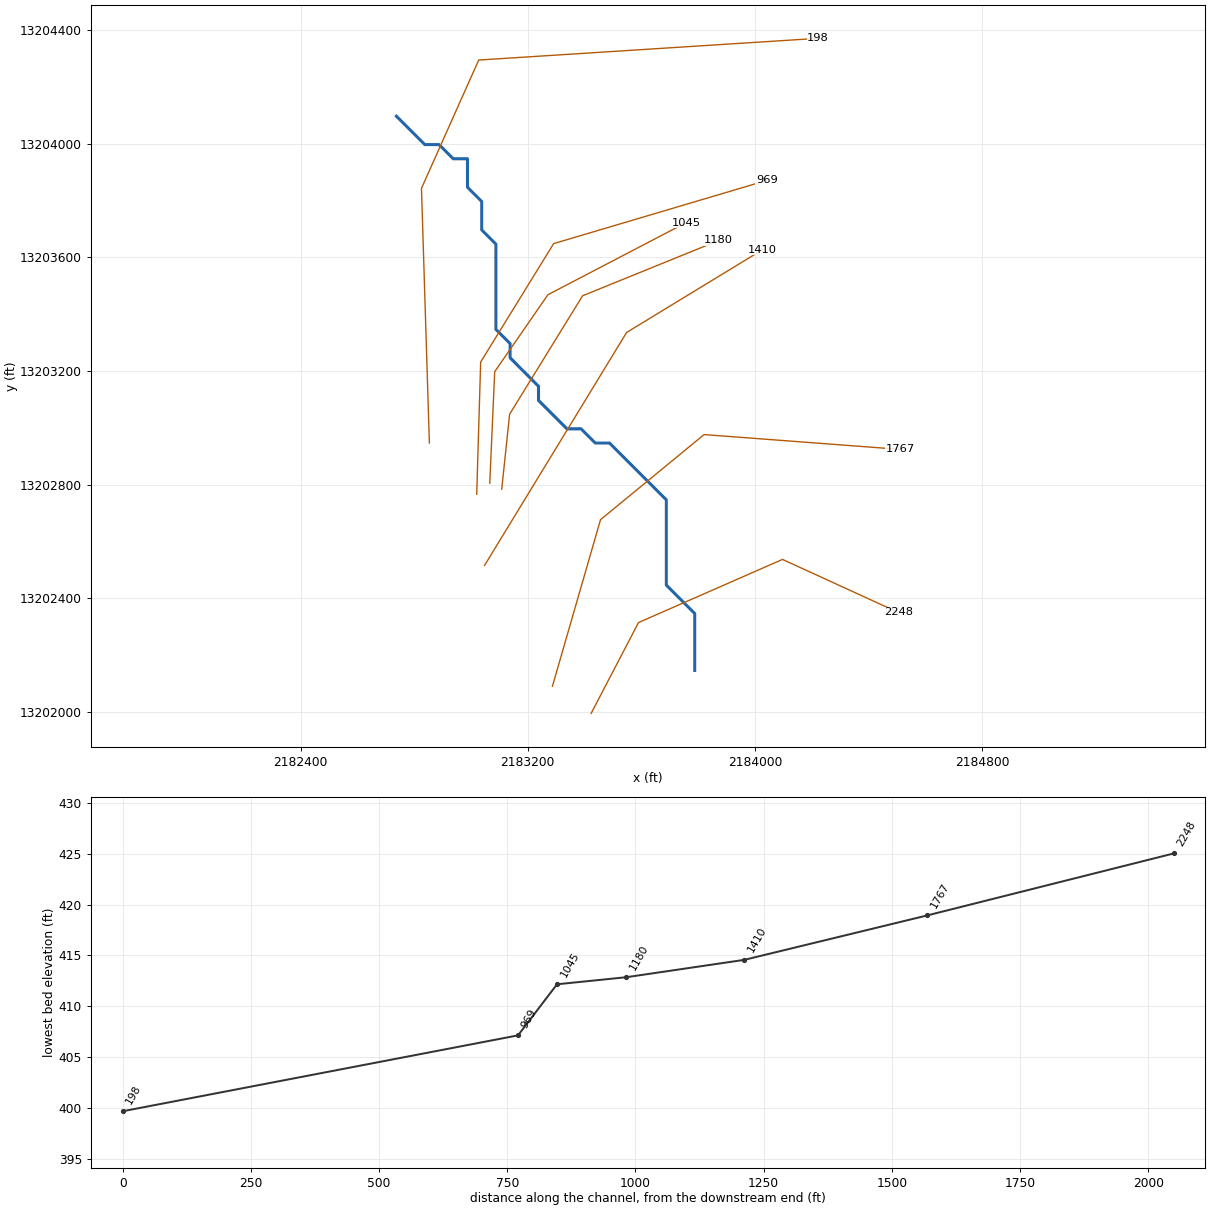
--- UNT 134 IN LACR.prj (project) ---

Proj Title=UNT 134 IN LACR Base Level Engineering
Current Plan=p01
Default Exp/Contr=0.3,0.1
English Units
Geom File=g01
Flow File=f01
Plan File=p01
Y Axis Title=Elevation
X Axis Title(PF)=Main Channel Distance
X Axis Title(XS)=Station
BEGIN DESCRIPTION:
UNT 134 IN LACR
END DESCRIPTION:
DSS Export Rating Curves= 0
DSS Export Rating Curve Sorted= 0
DSS Export Volume Flow Curves= 0
DXF OffsetX= 0
DXF OffsetY= 0
DXF ScaleX= 1
DXF ScaleY= 10

--- UNT 134 IN LACR.p01 (plan) ---

Plan Title=Multiple Run
Short Identifier=Multiple
Geom File=g01
Flow File=f01
Subcritical Flow
K Sum by GR= 0
Std Step Tol= 0.01
Critical Tol= 0.01
Num of Std Step Trials= 20
Max Error Tol= 0.3
Flow Tol Ratio= 0.001
Split Flow NTrial= 30
Split Flow Tol= 0.02
Split Flow Ratio= 0.02
Log Output Level= 0
Friction Slope Method= 1
Unsteady Friction Slope Method= 2
Unsteady Bridges Friction Slope Method= 1
Parabolic Critical Depth
Global Vel Dist=  1 , 1 , 1
Global Log Level= 0
CheckData=True
Encroach Param= -1, 0, 0, 0
BEGIN DESCRIPTION:
Multiple Run
END DESCRIPTION:

--- UNT 134 IN LACR.f01 (steady flow) ---

Flow Title=Multiple
Number of Profiles=7
Profile Names=10-year,25-year,50-year,1pct_min,100-year,1pct_plu,500-year
River Rch & RM= UNT 134 IN LACR,Reach-1,2248
      88     116     139     123     166     225     241
Boundary for River Rch & Prof#=UNT 134 IN LACR,Reach-1,1
Up Type=0
Dn Type=3
Dn Slope=0.005
Boundary for River Rch & Prof#=UNT 134 IN LACR,Reach-1,2
Up Type=0
Dn Type=3
Dn Slope=0.005
Boundary for River Rch & Prof#=UNT 134 IN LACR,Reach-1,3
Up Type=0
Dn Type=3
Dn Slope=0.005
Boundary for River Rch & Prof#=UNT 134 IN LACR,Reach-1,4
Up Type=0
Dn Type=3
Dn Slope=0.005
Boundary for River Rch & Prof#=UNT 134 IN LACR,Reach-1,5
Up Type=0
Dn Type=3
Dn Slope=0.005
Boundary for River Rch & Prof#=UNT 134 IN LACR,Reach-1,6
Up Type=0
Dn Type=3
Dn Slope=0.005
Boundary for River Rch & Prof#=UNT 134 IN LACR,Reach-1,7
Up Type=0
Dn Type=3
Dn Slope=0.005

--- UNT 134 IN LACR.g01 (geometry) ---

Geom Title=Existing Conditions
Program Version=4.10

River Reach=UNT 134 IN LACR ,Reach-1
Reach XY= 26
      2183787.72     13202146.86      2183787.72     13202346.85
      2183687.72     13202446.85      2183687.72     13202746.85
      2183637.72     13202796.86      2183587.72     13202846.85
      2183487.72     13202946.85      2183437.72     13202946.85
      2183387.72     13202996.86      2183337.72     13202996.86
      2183287.72     13203046.85      2183237.72     13203096.85
      2183237.72     13203146.86      2183187.72     13203196.85
      2183137.72     13203246.85      2183137.72     13203296.86
      2183087.72     13203346.85      2183087.72     13203646.86
      2183037.72     13203696.85      2183037.72     13203796.86
      2182987.72     13203846.85      2182987.72     13203946.86
      2182937.72     13203946.86      2182887.72     13203996.85
      2182837.72     13203996.85      2182737.72     13204096.85

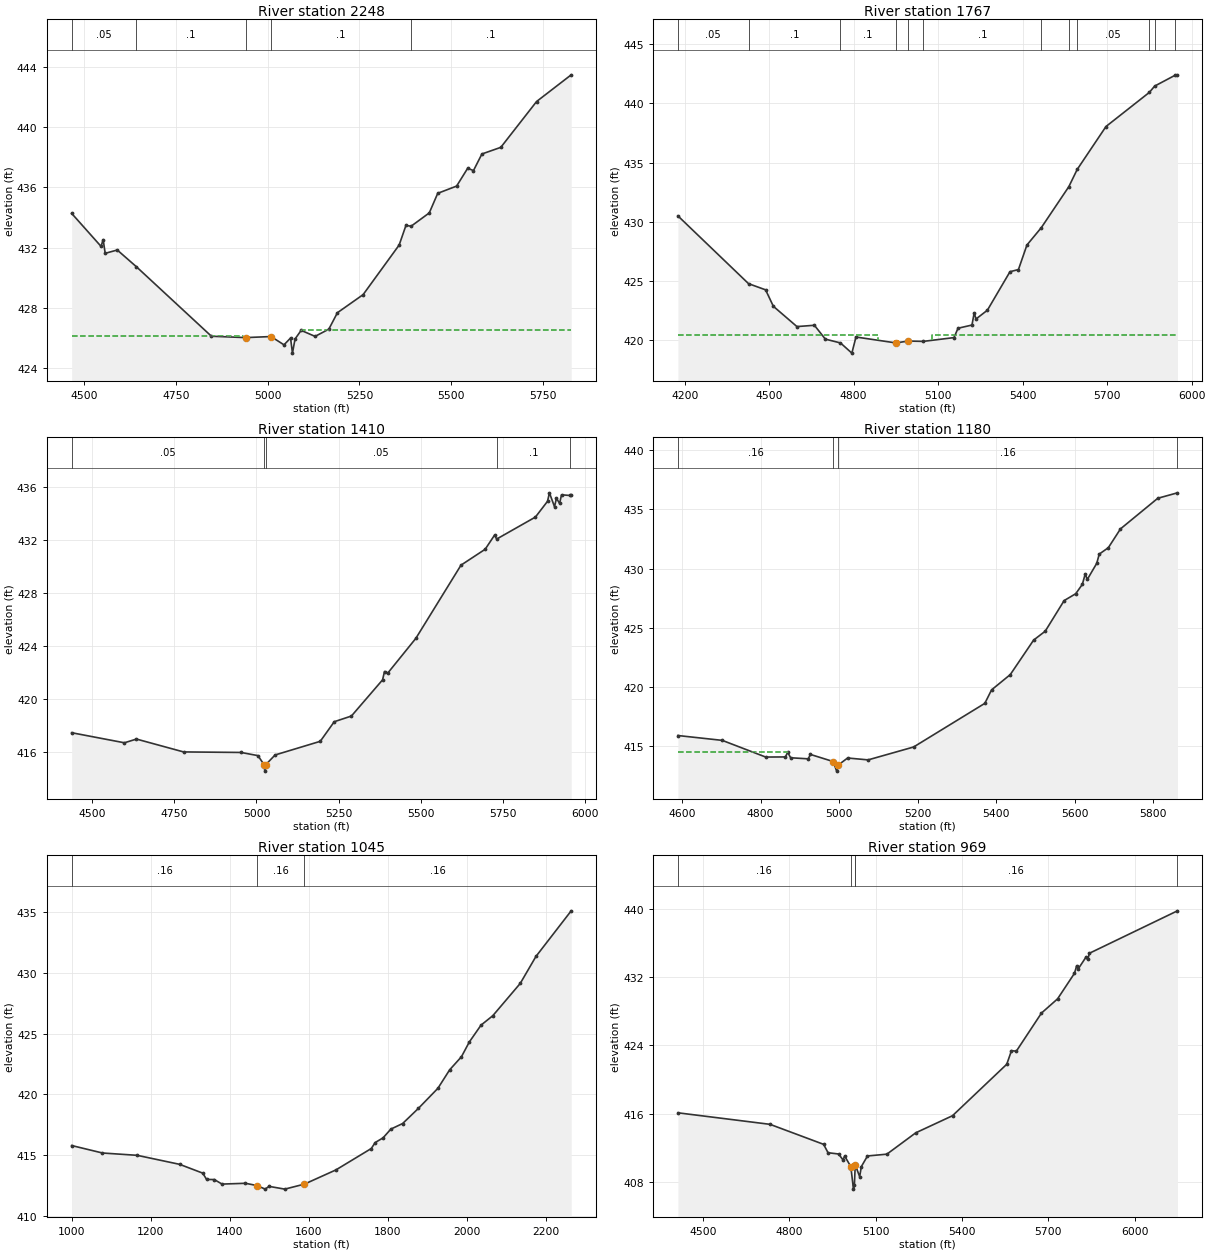
Type RM Length L Ch R = 1 ,2248    ,481,481,481
BEGIN DESCRIPTION:
UNT 134 IN LACR 3.0
END DESCRIPTION:
XS GIS Cut Line= 4
      2183423.02     13201995.71      2183589.69     13202315.16
      2184096.63     13202537.39      2184504.52     13202350.72
#Sta/Elev= 30
  4465.3  434.28  4545.5  432.09  4551.2  432.54  4556.8  431.63  4589.7  431.85
  4641.9  430.74  4846.5  426.13    4940  426.04  5009.1  426.11  5044.4  425.56
  5062.3  426.01  5067.5  425.01  5074.6  425.95  5091.2  426.52  5129.2  426.12
  5166.7   426.6  5190.1  427.69  5260.2  428.89  5358.5  432.18    5377  433.48
  5391.2  433.43  5440.6  434.31  5463.7  435.61  5515.2  436.09  5545.3  437.27
  5561.2  437.12  5584.2  438.22  5635.7  438.66  5733.3   441.7  5827.7  443.47
#Mann= 5 ,-1 , 0
  4465.3     .05       0  4641.9      .1       0    4940     .07       0
  5009.1      .1       0  5391.2      .1       0
#XS Ineff= 2 , 0
       0 4932.42  426.17 5090.73       0  426.52
Permanent Ineff=
       T       T
Bank Sta=4940,5009.1
XS Rating Curve= 0 ,0
Exp/Cntr=0.3,0.1

Type RM Length L Ch R = 1 ,1767    ,357,357,357
BEGIN DESCRIPTION:
Mapping XS 3208d831
END DESCRIPTION:
XS GIS Cut Line= 4
      2183286.72     13202091.17      2183456.01     13202677.14
      2183820.59     13202976.62      2184510.68     13202924.54
#Sta/Elev= 30
  4175.9  430.51  4426.8  424.79  4487.3  424.27  4514.9  422.88  4598.6  421.17
  4660.6  421.28  4699.5  420.11  4753.2  419.79  4793.6  418.93  4808.2  420.29
  4950.3  419.79  4993.4  419.95  5047.1  419.92  5156.2  420.24  5170.6  421.03
  5220.1   421.3    5228  422.33  5234.5  421.81  5274.8  422.55  5355.1   425.8
  5385.1  425.98  5415.2  428.05  5466.4  429.52  5563.9  432.97  5593.8  434.43
    5696  438.05    5850  440.93  5868.8  441.46  5940.3  442.36  5949.7  442.41
#Mann= 12 ,-1 , 0
  4175.9     .05       0  4426.8      .1       0  4753.2      .1       0
  4950.3     .03       0  4993.4      .1       0  5047.1      .1       0
  5466.4     .05       0  5563.9      .1       0  5593.8     .05       0
    5850      .1       0  5868.8     .05       0  5940.3      .1       0
#XS Ineff= 2 , 0
       0 4885.83  420.43 5077.82       0  420.43
Permanent Ineff=
       T       T
Bank Sta=4950.3,4993.4
XS Rating Curve= 0 ,0
Exp/Cntr=0.3,0.1

Type RM Length L Ch R = 1 ,1410    ,230,230,230
BEGIN DESCRIPTION:
UNT 134 IN LACR 2.0
END DESCRIPTION:
XS GIS Cut Line= 3
      2183047.99     13202516.51      2183548.02       13203336.
      2184027.15     13203627.64
#Sta/Elev= 30
  4437.3  417.47  4597.9  416.71  4634.7  416.99    4778  416.02  4953.1  415.98
  5004.5  415.74  5022.8  415.07  5025.6  414.57  5028.8  415.07  5056.7  415.79
  5194.2  416.82  5236.8   418.3  5289.1  418.73  5383.9  421.46  5389.8  422.09
    5400  421.98  5485.1  424.59  5622.7  430.12  5696.3  431.32  5724.7  432.38
  5731.3  432.09  5849.3  433.75  5886.1  434.94  5891.9  435.58  5907.4  434.53
  5913.3  435.17  5922.9  434.78  5928.7  435.43  5955.1  435.38  5958.2  435.39
#Mann= 5 ,-1 , 0
  4437.3     .05       0  5022.8     .03       0  5028.8     .05       0
  5731.3      .1       0  5955.1     .05       0
Bank Sta=5022.8,5028.8
XS Rating Curve= 0 ,0
Exp/Cntr=0.3,0.1

Type RM Length L Ch R = 1 ,1180    ,135,135,135
BEGIN DESCRIPTION:
Mapping XS fffd0b97
END DESCRIPTION:
XS GIS Cut Line= 4
      2183108.28     13202784.48      2183136.06     13203048.37
        2183393.     13203465.03      2183872.18     13203659.48
#Sta/Elev= 30
  4589.2  415.88  4702.2  415.47  4812.8  414.06  4862.9  414.07  4868.8  414.46
  4876.3     414  4920.9  413.91  4926.8  414.28  4984.7  413.68  4993.5  412.87
  4996.8  413.37  5021.4  413.98  5073.5  413.82  5189.4  414.91  5370.7   418.6
  5387.9  419.74  5435.5  421.03    5495  423.95  5524.5   424.7  5572.7  427.29
  5602.2  427.87    5619  428.66  5626.3  429.53  5631.7  429.08  5655.7  430.44
  5662.1  431.22  5685.2  431.76  5716.1  433.35  5811.1  435.94  5861.2   436.4
#Mann= 4 ,-1 , 0
  4589.2     .16       0  4984.7     .07       0  4996.8     .16       0
  5861.2     .05       0
#XS Ineff= 2 , 0
       0 4869.09  414.45               0
Permanent Ineff=
       F       F
Bank Sta=4984.7,4996.8
XS Rating Curve= 0 ,0
Exp/Cntr=0.3,0.1

Type RM Length L Ch R = 1 ,1045    ,76,76,76
BEGIN DESCRIPTION:
Mapping XS 681fb0ea
END DESCRIPTION:
XS GIS Cut Line= 4
     2183066.175    13202805.565     2183083.537    13203197.927
     2183271.037     13203468.76     2183757.148    13203722.232
#Sta/Elev= 30
    1000415.7717  1078.1415.1552 1165.97414.9638 1273.36414.2216 1331.93413.4959
 1341.69412.9756 1361.22412.9671 1380.75 412.594  1440.1412.6595 1469.97412.4679
 1489.88412.1793 1499.83412.4052 1539.66412.1782 1589.44412.5919 1669.09413.7617
 1758.61 415.525 1768.53 416.017 1788.38416.4026 1808.23417.1254 1838.01417.5851
 1877.71418.8267 1927.33420.4891 1957.11422.0122 1986.88423.0875 2006.73424.2993
 2036.51425.6948 2066.28426.4698 2135.76429.1305 2175.46431.3514 2264.78435.1135
#Mann= 3 , 0 , 0
    1000     .16       0 1469.97     .16       0 1589.44     .16       0
Bank Sta=1469.97,1589.44
XS Rating Curve= 0 ,0
Exp/Cntr=0.3,0.1

Type RM Length L Ch R = 1 ,969     ,771,771,771
BEGIN DESCRIPTION:
Mapping XS df98cf0c
END DESCRIPTION:
XS GIS Cut Line= 4
      2183020.24     13202766.57      2183034.13     13203231.83
      2183291.07      13203648.5      2184041.06     13203870.71
#Sta/Elev= 30
    4412   416.1  4732.4  414.75  4918.7  412.41  4934.1  411.43  4970.8  411.28
  4986.2  410.59    4992  411.04  5013.3   409.8  5022.6  407.17  5025.8  407.67
  5028.7  410.02  5028.8  410.01  5044.1  408.63    5050  409.81  5071.3  411.05
  5138.7  411.26  5239.2  413.76    5367  415.76  5555.6  421.78  5572.1  423.37
  5588.9  423.31  5676.4  427.77  5732.3  429.43  5791.1  432.42  5798.8  433.31
    5804  432.93    5832  434.36  5837.2  434.04  5843.3  434.77  6149.2  439.73
#Mann= 5 ,-1 , 0
    4412     .16       0  5013.3     .07       0  5028.8     .05       0
  5028.8     .16       0  6149.2     .05       0
#XS Ineff= 2 , 0
       0                 5029.34       0  409.96
Permanent Ineff=
       F       T
Bank Sta=5013.3,5028.7
XS Rating Curve= 0 ,0
Exp/Cntr=0.3,0.1

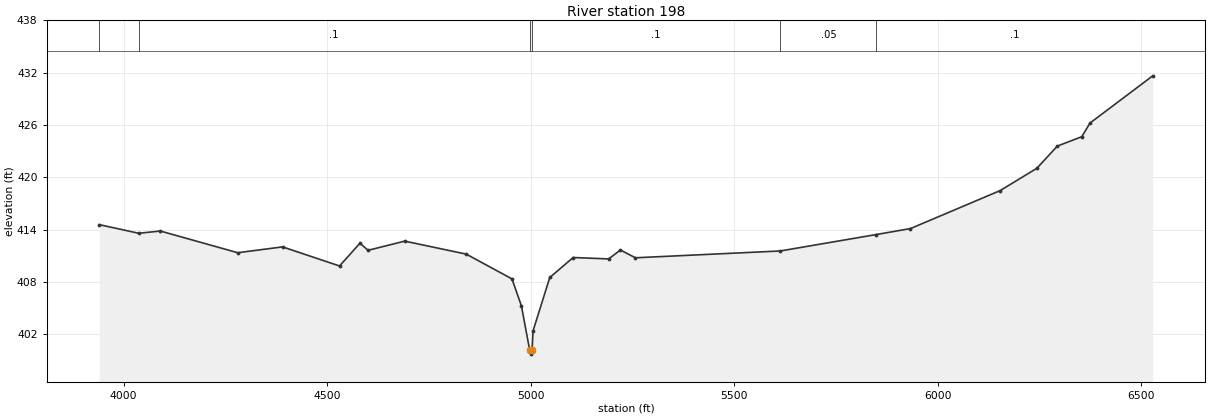
Type RM Length L Ch R = 1 ,198     ,0,0,0
BEGIN DESCRIPTION:
UNT 134 IN LACR 1.0
END DESCRIPTION:
XS GIS Cut Line= 4
      2182853.58      13202947.1       2182825.8     13203842.94
      2183027.19     13204294.33       2184221.6     13204370.72
#Sta/Elev= 30
  3940.3  414.58  4037.2  413.59  4090.1  413.85  4280.2  411.36  4390.3  412.03
  4530.3  409.84  4580.4  412.45  4600.4  411.64  4690.4  412.69  4841.5   411.2
  4953.8  408.36    4977  405.27  4997.2  400.23    5000  399.73  5003.2  400.23
  5005.7  402.41  5046.7  408.52  5104.1  410.81  5191.3  410.65  5220.2  411.67
    5257  410.78  5612.6  411.56  5849.1  413.45  5932.6  414.13  6153.1  418.49
  6243.2  421.05  6293.3  423.59  6353.5  424.67  6373.5  426.23  6527.7  431.65
#Mann= 6 ,-1 , 0
  3940.3     .05       0  4037.2      .1       0  4997.2     .07       0
  5003.2      .1       0  5612.6     .05       0  5849.1      .1       0
Bank Sta=4997.2,5003.2
XS Rating Curve= 0 ,0
Exp/Cntr=0.3,0.1

Chan Stop Cuts=-1
Use User Specified Reach Order=0
Composite Channel Slope=5