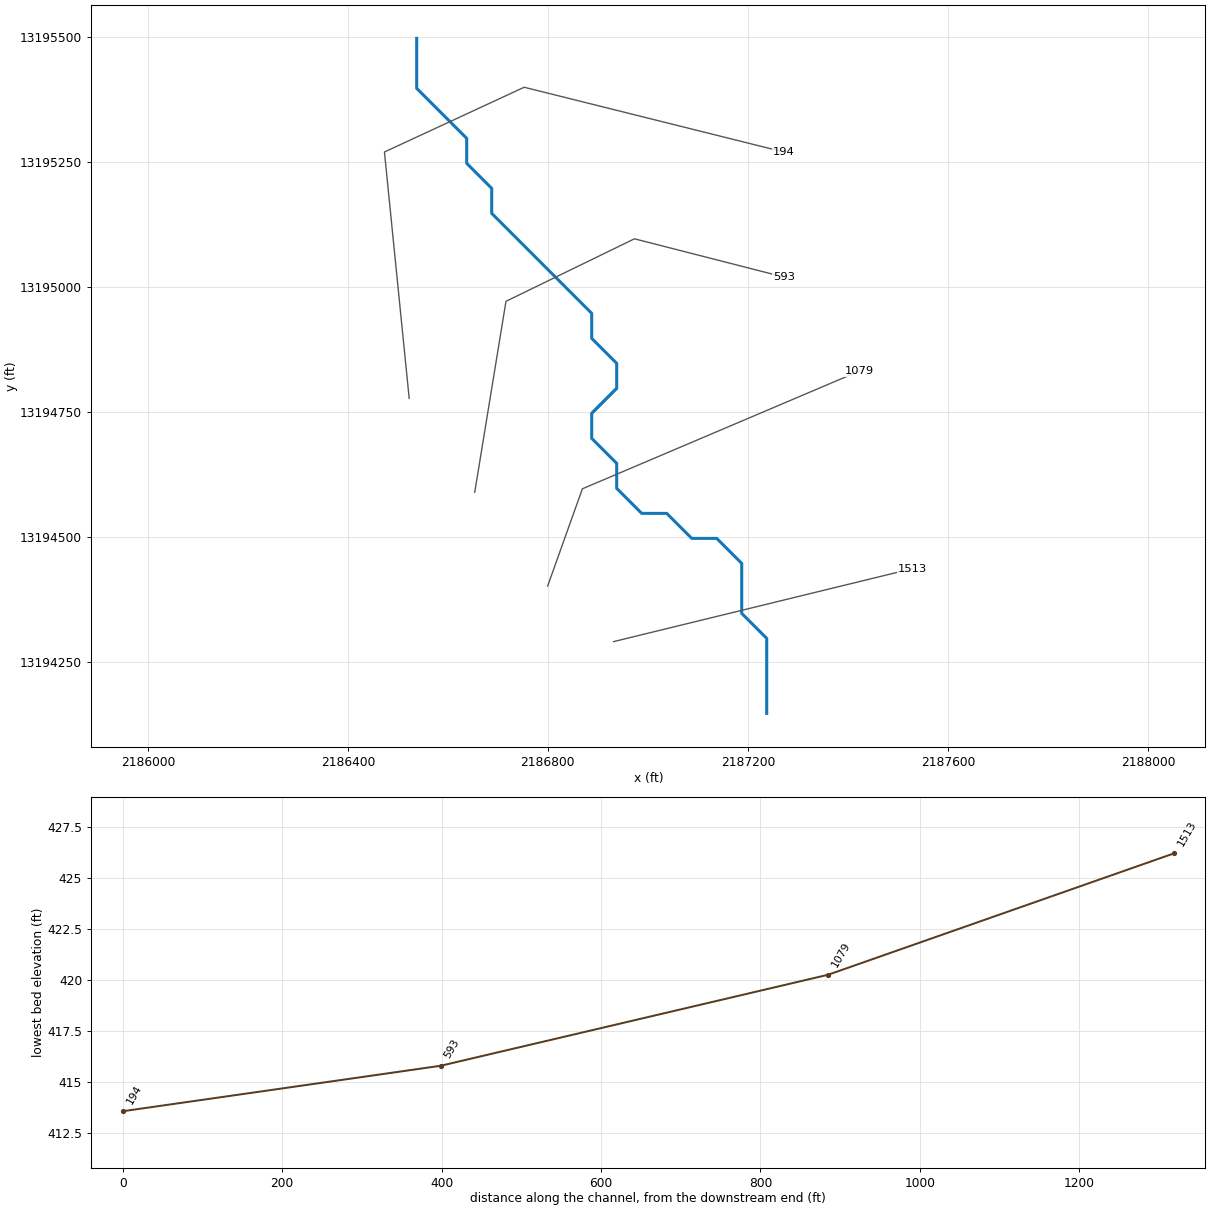
--- UNT 137 IN LACR.prj (project) ---

Proj Title=UNT 137 IN LACR Base Level Engineering
Current Plan=p01
Default Exp/Contr=0.3,0.1
English Units
Geom File=g01
Flow File=f01
Plan File=p01
BEGIN DESCRIPTION:
UNT 137 IN LACR
END DESCRIPTION:

--- UNT 137 IN LACR.p01 (plan) ---

Plan Title=Multiple Run
Short Identifier=Multiple
Geom File=g01
Flow File=f01
Subcritical Flow
K Sum by GR= 0
Std Step Tol= 0.01
Critical Tol= 0.01
Num of Std Step Trials= 20
Max Error Tol= 0.3
Flow Tol Ratio= 0.001
Split Flow NTrial= 30
Split Flow Tol= 0.02
Split Flow Ratio= 0.02
Log Output Level= 0
Friction Slope Method= 1
Unsteady Friction Slope Method= 2
Unsteady Bridges Friction Slope Method= 1
Parabolic Critical Depth
Global Vel Dist=  1 , 1 , 1
Global Log Level= 0
CheckData=True
Encroach Param= -1, 0, 0, 0
BEGIN DESCRIPTION:
Multiple Run
END DESCRIPTION:

--- UNT 137 IN LACR.f01 (steady flow) ---

Flow Title=Multiple
Number of Profiles=7
Profile Names=10-year,25-year,50-year,1pct_min,100-year,1pct_plu,500-year
River Rch & RM= UNT 137 IN LACR,Reach-1,1513
      74      97     115     102     138     186     198
Boundary for River Rch & Prof#=UNT 137 IN LACR,Reach-1,1
Up Type=0
Dn Type=3
Dn Slope=0.005
Boundary for River Rch & Prof#=UNT 137 IN LACR,Reach-1,2
Up Type=0
Dn Type=3
Dn Slope=0.005
Boundary for River Rch & Prof#=UNT 137 IN LACR,Reach-1,3
Up Type=0
Dn Type=3
Dn Slope=0.005
Boundary for River Rch & Prof#=UNT 137 IN LACR,Reach-1,4
Up Type=0
Dn Type=3
Dn Slope=0.005
Boundary for River Rch & Prof#=UNT 137 IN LACR,Reach-1,5
Up Type=0
Dn Type=3
Dn Slope=0.005
Boundary for River Rch & Prof#=UNT 137 IN LACR,Reach-1,6
Up Type=0
Dn Type=3
Dn Slope=0.005
Boundary for River Rch & Prof#=UNT 137 IN LACR,Reach-1,7
Up Type=0
Dn Type=3
Dn Slope=0.005

--- UNT 137 IN LACR.g01 (geometry) ---

Geom Title=Existing Conditions

River Reach=UNT 137 IN LACR,Reach-1
Reach XY= 30
      2187237.72     13194146.85      2187237.72     13194196.85
      2187237.72     13194246.85      2187237.72     13194296.86
      2187187.72     13194346.85      2187187.72     13194396.85
      2187187.72     13194446.86      2187137.72     13194496.85
      2187087.72     13194496.85      2187037.72     13194546.85
      2186987.72     13194546.85      2186937.72     13194596.86
      2186937.72     13194646.85      2186887.72     13194696.85
      2186887.72     13194746.85      2186937.72     13194796.86
      2186937.72     13194846.85      2186887.72     13194896.85
      2186887.72     13194946.86      2186837.72     13194996.85
      2186787.72     13195046.85      2186737.72     13195096.86
      2186687.72     13195146.85      2186687.72     13195196.85
      2186637.72     13195246.85      2186637.72     13195296.85
      2186587.72     13195346.85      2186537.72     13195396.85
      2186537.72     13195446.86      2186537.72     13195496.85

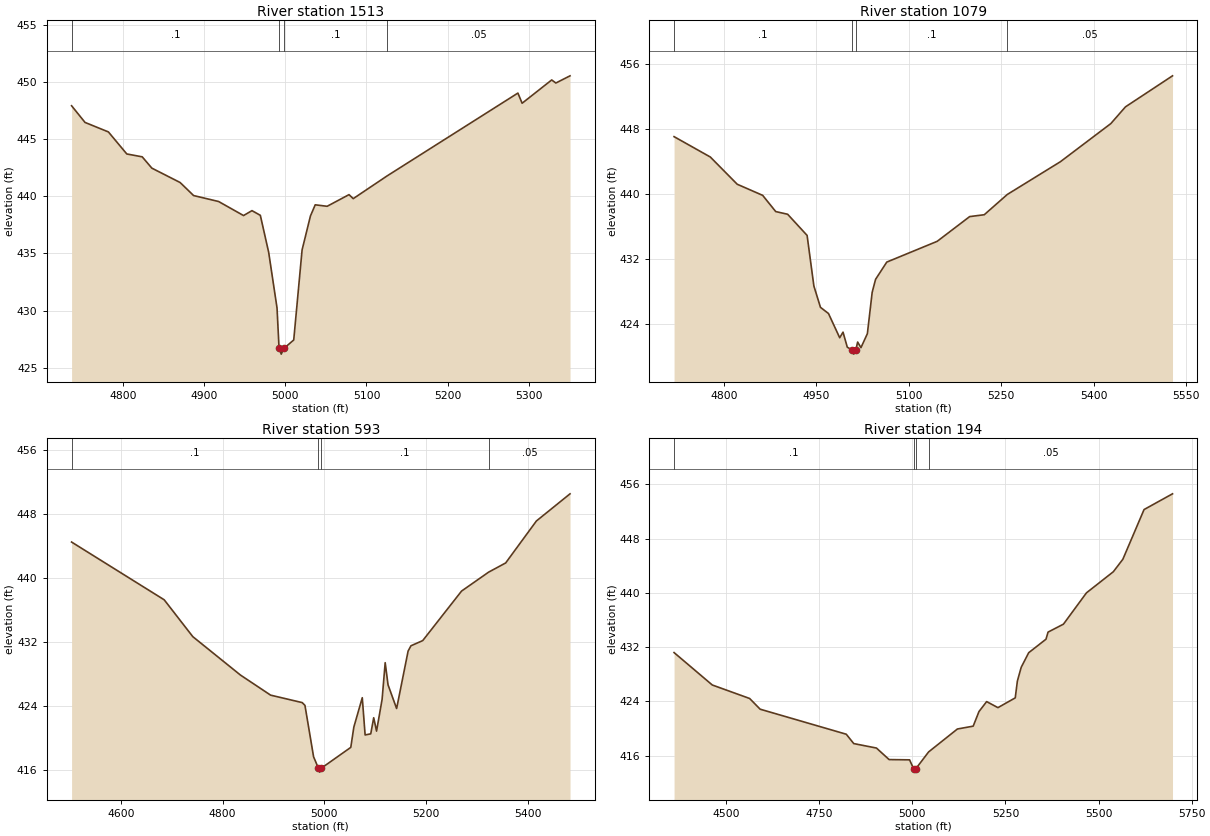
Type RM Length L Ch R = 1,1513,434,434,434
BEGIN DESCRIPTION:
UNT 137 IN LACR 3.0
END DESCRIPTION:
XS GIS Cut Line= 2
      2186931.55     13194290.37      2187528.80     13194436.21
#Sta/Elev= 30
  4736.3  447.93  4752.9  446.47  4781.7  445.64  4804.4  443.71  4823.4  443.46
  4835.3  442.47  4870.2  441.21  4886.8  440.07  4917.6  439.55  4948.4  438.32
  4958.8  438.75  4969.1  438.34  4979.4  435.10  4989.7  430.23  4992.2  426.69
  4994.9  426.19  4998.2  426.69  5010.3  427.43  5020.6  435.31  5030.9  438.28
  5036.8  439.26  5051.5  439.13  5078.5  440.15  5083.7  439.80  5125.7  441.80
  5286.8  449.04  5292.0  448.15  5328.5  450.19  5333.6  449.92  5351.1  450.55
#Mann=4,-1,0
  4736.3     0.1       0  4992.2    0.07       0  4998.2     0.1       0
  5125.7    0.05       0
Bank Sta=4992.2,4998.2
Exp/Cntr=0.3,0.1

Type RM Length L Ch R = 1,1079,486,486,486
BEGIN DESCRIPTION:
Mapping XS 1eb22fd2
END DESCRIPTION:
XS GIS Cut Line= 3
      2186799.60     13194401.48      2186869.04     13194595.93
      2187423.47     13194831.56
#Sta/Elev= 30
  4718.9  447.06  4777.7  444.55  4821.4  441.19  4862.7  439.82  4883.9  437.82
  4903.2  437.49  4934.8  434.88  4945.8  428.64  4956.5  426.01  4969.5  425.25
  4987.7  422.26  4993.1  422.95  5000.0  421.10  5007.9  420.74  5010.6  420.24
  5013.9  420.74  5016.8  421.73  5022.2  421.04  5032.6  422.76  5040.4  427.86
  5045.9  429.46  5064.1  431.59  5145.9  434.15  5198.6  437.20  5222.3  437.43
  5259.7  439.93  5345.9  443.97  5427.7  448.67  5451.4  450.73  5527.8  454.56
#Mann=4,-1,0
  4718.9     0.1       0  5007.9    0.07       0  5013.9     0.1       0
  5259.7    0.05       0
Bank Sta=5007.9,5013.9
Exp/Cntr=0.3,0.1

Type RM Length L Ch R = 1,593,399,399,399
BEGIN DESCRIPTION:
UNT 137 IN LACR 2.0
END DESCRIPTION:
XS GIS Cut Line= 4
      2186653.76     13194588.96      2186716.27     13194970.93
      2186973.21     13195095.93      2187271.82     13195019.54
#Sta/Elev= 30
  4502.7  444.50  4685.0  437.29  4741.3  432.69  4835.0  427.90  4894.4  425.39
  4956.5  424.46  4962.0  424.11  4979.0  417.69  4988.4  416.28  4991.2  415.78
  4994.4  416.28  5052.2  418.87  5058.2  421.40  5074.8  425.07  5080.4  420.42
  5091.5  420.56  5097.3  422.57  5102.9  420.90  5113.8  424.85  5119.9  429.44
  5125.5  426.68  5142.4  423.72  5165.0  430.89  5170.6  431.55  5193.8  432.20
  5270.2  438.38  5323.4  440.74  5357.0  441.89  5417.5  447.13  5483.7  450.52
#Mann=4,-1,0
  4502.7     0.1       0  4988.4    0.07       0  4994.4     0.1       0
  5323.4    0.05       0
Bank Sta=4988.4,4994.4
Exp/Cntr=0.3,0.1

Type RM Length L Ch R = 1,194,0,0,0
BEGIN DESCRIPTION:
UNT 137 IN LACR 1.0
END DESCRIPTION:
XS GIS Cut Line= 4
      2186522.69     13194776.89      2186473.21     13195269.54
      2186752.70     13195399.02      2187271.85     13195269.53
#Sta/Elev= 30
  4360.4  431.18  4463.0  426.40  4563.3  424.41  4591.5  422.83  4822.7  419.14
  4842.8  417.76  4903.8  417.10  4937.8  415.40  4992.7  415.36  5003.5  414.05
  5006.3  413.55  5009.5  414.05  5043.8  416.53  5121.1  419.91  5163.5  420.33
  5179.0  422.48  5199.6  423.95  5229.9  423.06  5276.4  424.50  5282.1  426.98
  5292.4  429.01  5312.5  431.16  5358.9  433.15  5364.5  434.20  5405.8  435.37
  5467.6  439.99  5539.7  443.10  5565.3  444.94  5622.2  452.27  5698.6  454.59
#Mann=4,-1,0
  4360.4     0.1       0  5003.5    0.07       0  5009.5     0.1       0
  5043.8    0.05       0
Bank Sta=5003.5,5009.5
Exp/Cntr=0.3,0.1

Chan Stop Cuts=-1