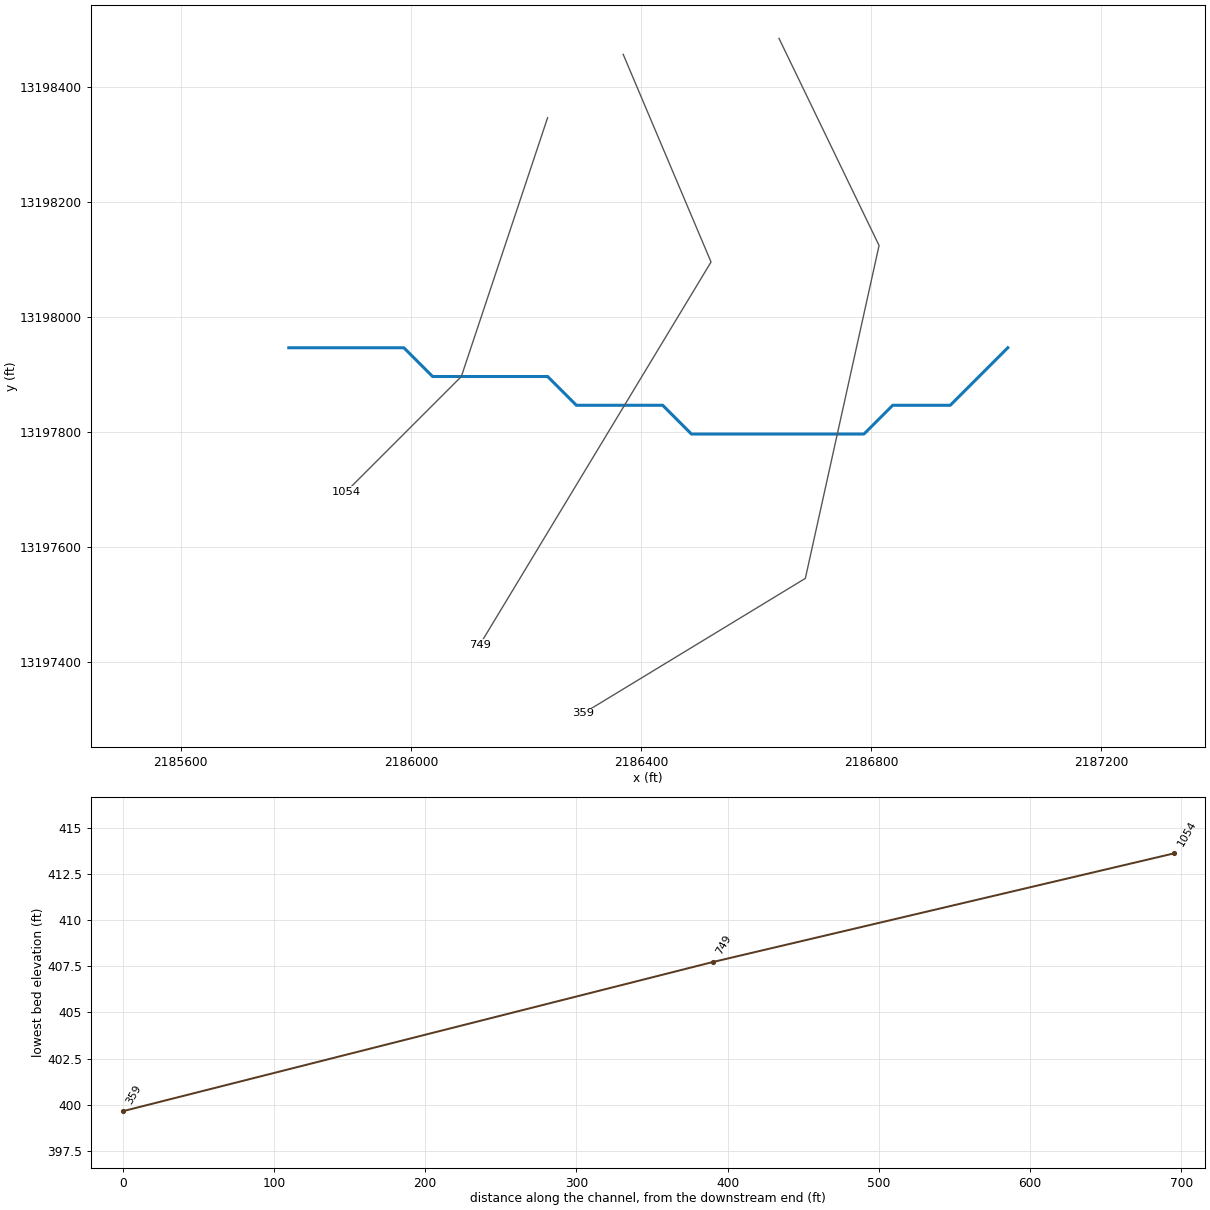
--- UNT 139 IN LACR.prj (project) ---

Proj Title=UNT 139 IN LACR Base Level Engineering
Current Plan=p01
Default Exp/Contr=0.3,0.1
English Units
Geom File=g01
Flow File=f01
Plan File=p01
BEGIN DESCRIPTION:
UNT 139 IN LACR
END DESCRIPTION:

--- UNT 139 IN LACR.p01 (plan) ---

Plan Title=Multiple Run
Short Identifier=Multiple
Geom File=g01
Flow File=f01
Subcritical Flow
K Sum by GR= 0
Std Step Tol= 0.01
Critical Tol= 0.01
Num of Std Step Trials= 20
Max Error Tol= 0.3
Flow Tol Ratio= 0.001
Split Flow NTrial= 30
Split Flow Tol= 0.02
Split Flow Ratio= 0.02
Log Output Level= 0
Friction Slope Method= 1
Unsteady Friction Slope Method= 2
Unsteady Bridges Friction Slope Method= 1
Parabolic Critical Depth
Global Vel Dist=  1 , 1 , 1
Global Log Level= 0
CheckData=True
Encroach Param= -1, 0, 0, 0
BEGIN DESCRIPTION:
Multiple Run
END DESCRIPTION:

--- UNT 139 IN LACR.f01 (steady flow) ---

Flow Title=Multiple
Number of Profiles=7
Profile Names=10-year,25-year,50-year,1pct_min,100-year,1pct_plu,500-year
River Rch & RM= UNT 139 IN LACR,Reach-1,1054
      82     108     129     115     155     210     225
Boundary for River Rch & Prof#=UNT 139 IN LACR,Reach-1,1
Up Type=0
Dn Type=3
Dn Slope=0.005
Boundary for River Rch & Prof#=UNT 139 IN LACR,Reach-1,2
Up Type=0
Dn Type=3
Dn Slope=0.005
Boundary for River Rch & Prof#=UNT 139 IN LACR,Reach-1,3
Up Type=0
Dn Type=3
Dn Slope=0.005
Boundary for River Rch & Prof#=UNT 139 IN LACR,Reach-1,4
Up Type=0
Dn Type=3
Dn Slope=0.005
Boundary for River Rch & Prof#=UNT 139 IN LACR,Reach-1,5
Up Type=0
Dn Type=3
Dn Slope=0.005
Boundary for River Rch & Prof#=UNT 139 IN LACR,Reach-1,6
Up Type=0
Dn Type=3
Dn Slope=0.005
Boundary for River Rch & Prof#=UNT 139 IN LACR,Reach-1,7
Up Type=0
Dn Type=3
Dn Slope=0.005

--- UNT 139 IN LACR.g01 (geometry) ---

Geom Title=Existing Conditions

River Reach=UNT 139 IN LACR,Reach-1
Reach XY= 26
      2185787.72     13197946.85      2185837.72     13197946.85
      2185887.72     13197946.85      2185937.72     13197946.85
      2185987.72     13197946.85      2186037.72     13197896.86
      2186087.72     13197896.86      2186137.72     13197896.86
      2186187.72     13197896.86      2186237.72     13197896.86
      2186287.72     13197846.85      2186337.72     13197846.85
      2186387.72     13197846.85      2186437.72     13197846.85
      2186487.72     13197796.85      2186537.72     13197796.85
      2186587.72     13197796.85      2186637.72     13197796.85
      2186687.72     13197796.85      2186737.72     13197796.85
      2186787.72     13197796.85      2186837.72     13197846.85
      2186887.72     13197846.85      2186937.72     13197846.85
      2186987.72     13197896.86      2187037.72     13197946.85

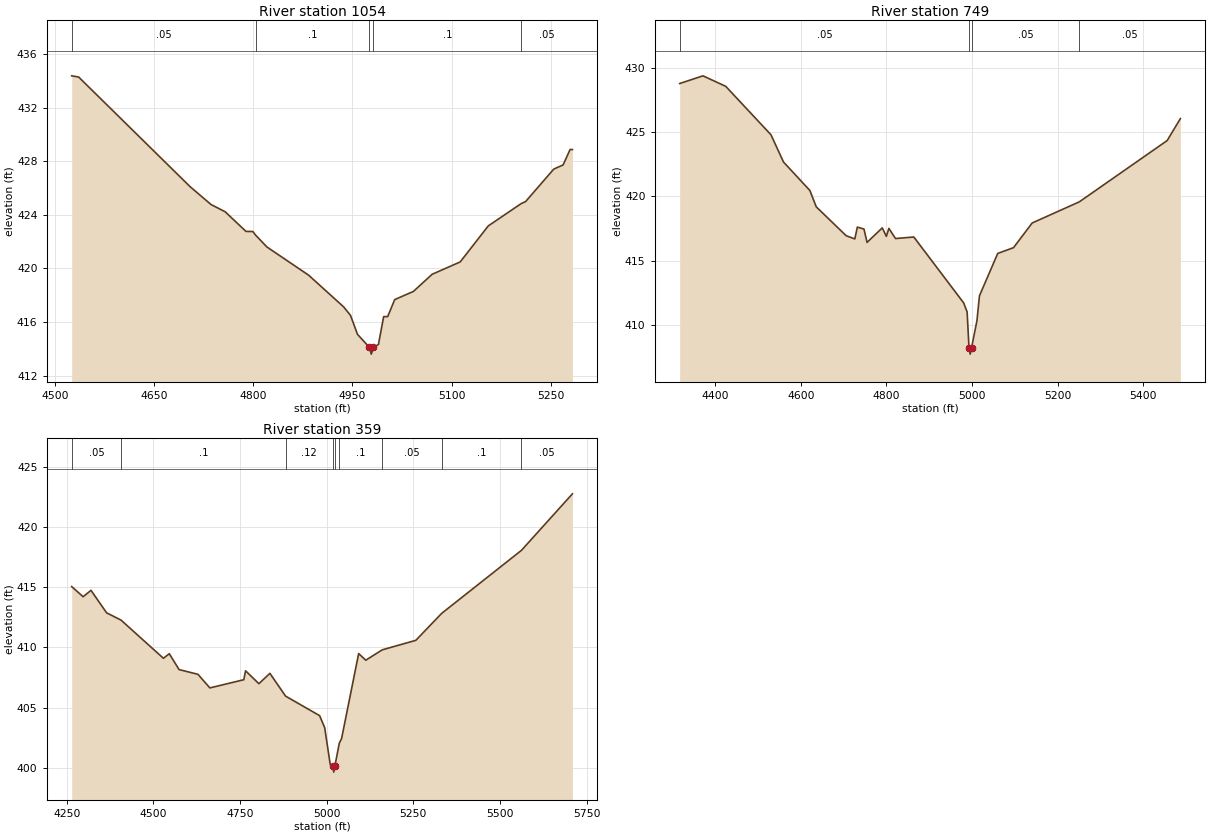
Type RM Length L Ch R = 1,1054,305,305,305
BEGIN DESCRIPTION:
UNT 139 IN LACR 2.0
END DESCRIPTION:
XS GIS Cut Line= 3
      2186237.71     13198346.82      2186087.72     13197896.86
      2185887.75     13197696.89
#Sta/Elev= 30
  4525.7  434.37  4536.2  434.28  4704.9  426.09  4736.5  424.76  4757.6  424.23
  4789.2  422.76  4799.7  422.75  4803.8  422.48  4820.8  421.60  4884.0  419.49
  4936.8  417.13  4947.3  416.49  4957.8  415.08  4975.9  414.10  4978.7  413.60
  4981.9  414.10  4989.5  414.32  4997.4  416.40  5003.5  416.40  5014.1  417.67
  5042.4  418.28  5070.7  419.56  5113.1  420.48  5155.6  423.17  5205.2  424.83
  5212.1  424.99  5254.6  427.41  5268.7  427.72  5279.3  428.87  5282.8  428.87
#Mann=5,-1,0
  4525.7    0.05       0  4803.8     0.1       0  4975.9    0.07       0
  4981.9     0.1       0  5205.2    0.05       0
Bank Sta=4975.9,4981.9
Exp/Cntr=0.3,0.1

Type RM Length L Ch R = 1,749,390,390,390
BEGIN DESCRIPTION:
Mapping XS 60f150e5
END DESCRIPTION:
XS GIS Cut Line= 3
      2186369.04     13198457.04      2186521.82     13198095.93
      2186119.82     13197430.54
#Sta/Elev= 30
  4316.9  428.79  4371.4  429.39  4424.6  428.57  4530.2  424.80  4559.4  422.68
  4621.1  420.46  4635.9  419.19  4705.8  416.94  4726.0  416.69  4731.9  417.61
  4747.4  417.46  4754.6  416.42  4790.1  417.55  4799.7  416.89  4805.6  417.51
  4821.1  416.72  4863.8  416.84  4980.2  411.71  4988.3  411.01  4992.7  408.22
  4995.5  407.72  4998.7  408.22  5011.3  410.33  5017.1  412.26  5059.8  415.56
  5096.7  416.01  5140.2  417.93  5250.5  419.58  5455.6  424.35  5486.4  426.06
#Mann=4,-1,0
  4316.9    0.05       0  4992.7    0.07       0  4998.7    0.05       0
  5250.5    0.05       0
Bank Sta=4992.7,4998.7
Exp/Cntr=0.3,0.1

Type RM Length L Ch R = 1,359,0,0,0
BEGIN DESCRIPTION:
UNT 139 IN LACR 1.0
END DESCRIPTION:
XS GIS Cut Line= 4
      2186639.90     13198484.77      2186813.92     13198124.63
      2186685.74     13197545.87      2186299.62     13197311.22
#Sta/Elev= 30
  4264.3  415.05  4297.3  414.21  4319.9  414.74  4365.1  412.87  4406.6  412.27
  4528.9  409.10  4545.9  409.48  4574.1  408.16  4628.5  407.77  4662.9  406.64
  4760.8  407.32  4765.9  408.06  4804.4  406.99  4836.1  407.85  4881.3  405.96
  4979.5  404.34  4994.2  403.34  5010.2  400.28  5017.5  400.15  5020.2  399.65
  5023.5  400.15  5036.5  402.07  5042.9  402.43  5092.2  409.49  5112.7  408.94
  5160.2  409.80  5257.1  410.59  5331.8  412.83  5561.9  418.06  5708.9  422.75
#Mann=9,-1,0
  4264.3    0.05       0  4406.6     0.1       0  4881.3    0.12       0
  5017.5    0.07       0  5023.5    0.12       0  5036.5     0.1       0
  5160.2    0.05       0  5331.8     0.1       0  5561.9    0.05       0
Bank Sta=5017.5,5023.5
Exp/Cntr=0.3,0.1

Chan Stop Cuts=-1