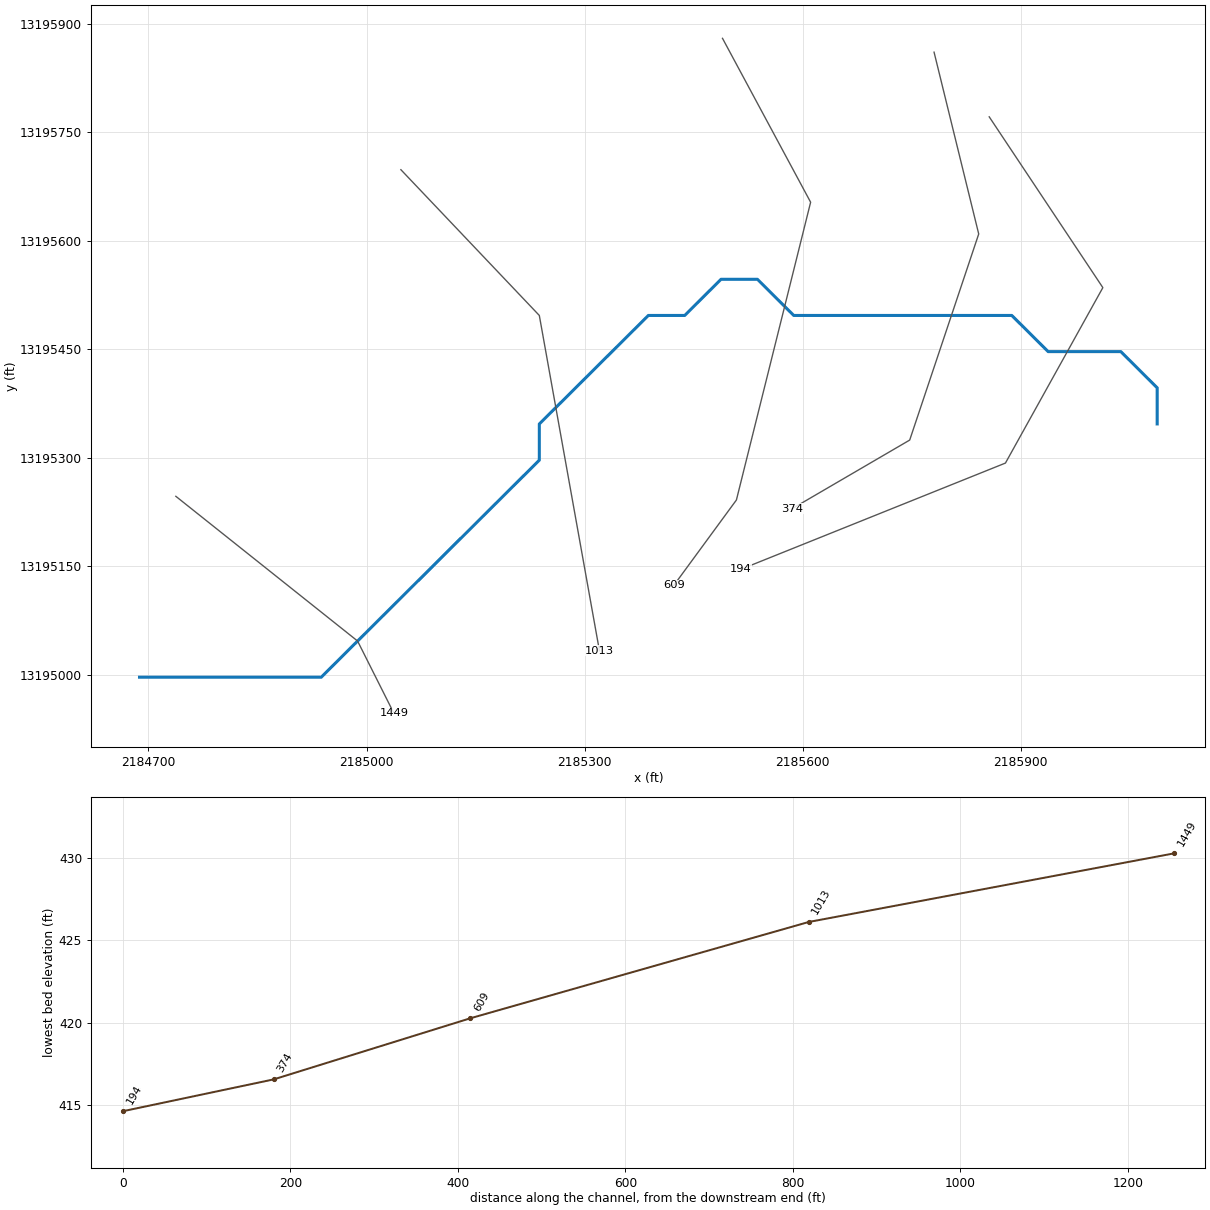
--- UNT 140 IN LACR.prj (project) ---

Proj Title=UNT 140 IN LACR Base Level Engineering
Current Plan=p01
Default Exp/Contr=0.3,0.1
English Units
Geom File=g01
Flow File=f01
Plan File=p01
Y Axis Title=Elevation
X Axis Title(PF)=Main Channel Distance
X Axis Title(XS)=Station
BEGIN DESCRIPTION:
UNT 140 IN LACR
END DESCRIPTION:
DSS Export Rating Curves= 0
DSS Export Rating Curve Sorted= 0
DSS Export Volume Flow Curves= 0
DXF OffsetX= 0
DXF OffsetY= 0
DXF ScaleX= 1
DXF ScaleY= 10

--- UNT 140 IN LACR.p01 (plan) ---

Plan Title=Multiple Run
Short Identifier=Multiple
Geom File=g01
Flow File=f01
Subcritical Flow
K Sum by GR= 0
Std Step Tol= 0.01
Critical Tol= 0.01
Num of Std Step Trials= 20
Max Error Tol= 0.3
Flow Tol Ratio= 0.001
Split Flow NTrial= 30
Split Flow Tol= 0.02
Split Flow Ratio= 0.02
Log Output Level= 0
Friction Slope Method= 1
Unsteady Friction Slope Method= 2
Unsteady Bridges Friction Slope Method= 1
Parabolic Critical Depth
Global Vel Dist=  1 , 1 , 1
Global Log Level= 0
CheckData=True
Encroach Param= -1, 0, 0, 0
BEGIN DESCRIPTION:
Multiple Run
END DESCRIPTION:

--- UNT 140 IN LACR.f01 (steady flow) ---

Flow Title=Multiple
Number of Profiles=7
Profile Names=10-year,25-year,50-year,1pct_min,100-year,1pct_plu,500-year
River Rch & RM= UNT 140 IN LACR,Reach-1,1449
      77     101     119     105     142     192     203
Boundary for River Rch & Prof#=UNT 140 IN LACR,Reach-1,1
Up Type=0
Dn Type=3
Dn Slope=0.005
Boundary for River Rch & Prof#=UNT 140 IN LACR,Reach-1,2
Up Type=0
Dn Type=3
Dn Slope=0.005
Boundary for River Rch & Prof#=UNT 140 IN LACR,Reach-1,3
Up Type=0
Dn Type=3
Dn Slope=0.005
Boundary for River Rch & Prof#=UNT 140 IN LACR,Reach-1,4
Up Type=0
Dn Type=3
Dn Slope=0.005
Boundary for River Rch & Prof#=UNT 140 IN LACR,Reach-1,5
Up Type=0
Dn Type=3
Dn Slope=0.005
Boundary for River Rch & Prof#=UNT 140 IN LACR,Reach-1,6
Up Type=0
Dn Type=3
Dn Slope=0.005
Boundary for River Rch & Prof#=UNT 140 IN LACR,Reach-1,7
Up Type=0
Dn Type=3
Dn Slope=0.005

--- UNT 140 IN LACR.g01 (geometry) ---

Geom Title=Existing Conditions
Program Version=4.10

River Reach=UNT 140 IN LACR ,Reach-1
Reach XY= 19
      2184687.72     13194996.85      2184937.72     13194996.85
      2184987.72     13195046.85      2185037.72     13195096.86
      2185087.72     13195146.85      2185237.72     13195296.85
      2185237.72     13195346.85      2185287.72     13195396.85
      2185337.72     13195446.86      2185387.72     13195496.85
      2185437.72     13195496.85      2185487.72     13195546.85
      2185537.72     13195546.85      2185587.72     13195496.85
      2185887.72     13195496.85      2185937.72     13195446.86
      2186037.72     13195446.86      2186087.72     13195396.85
      2186087.72     13195346.85

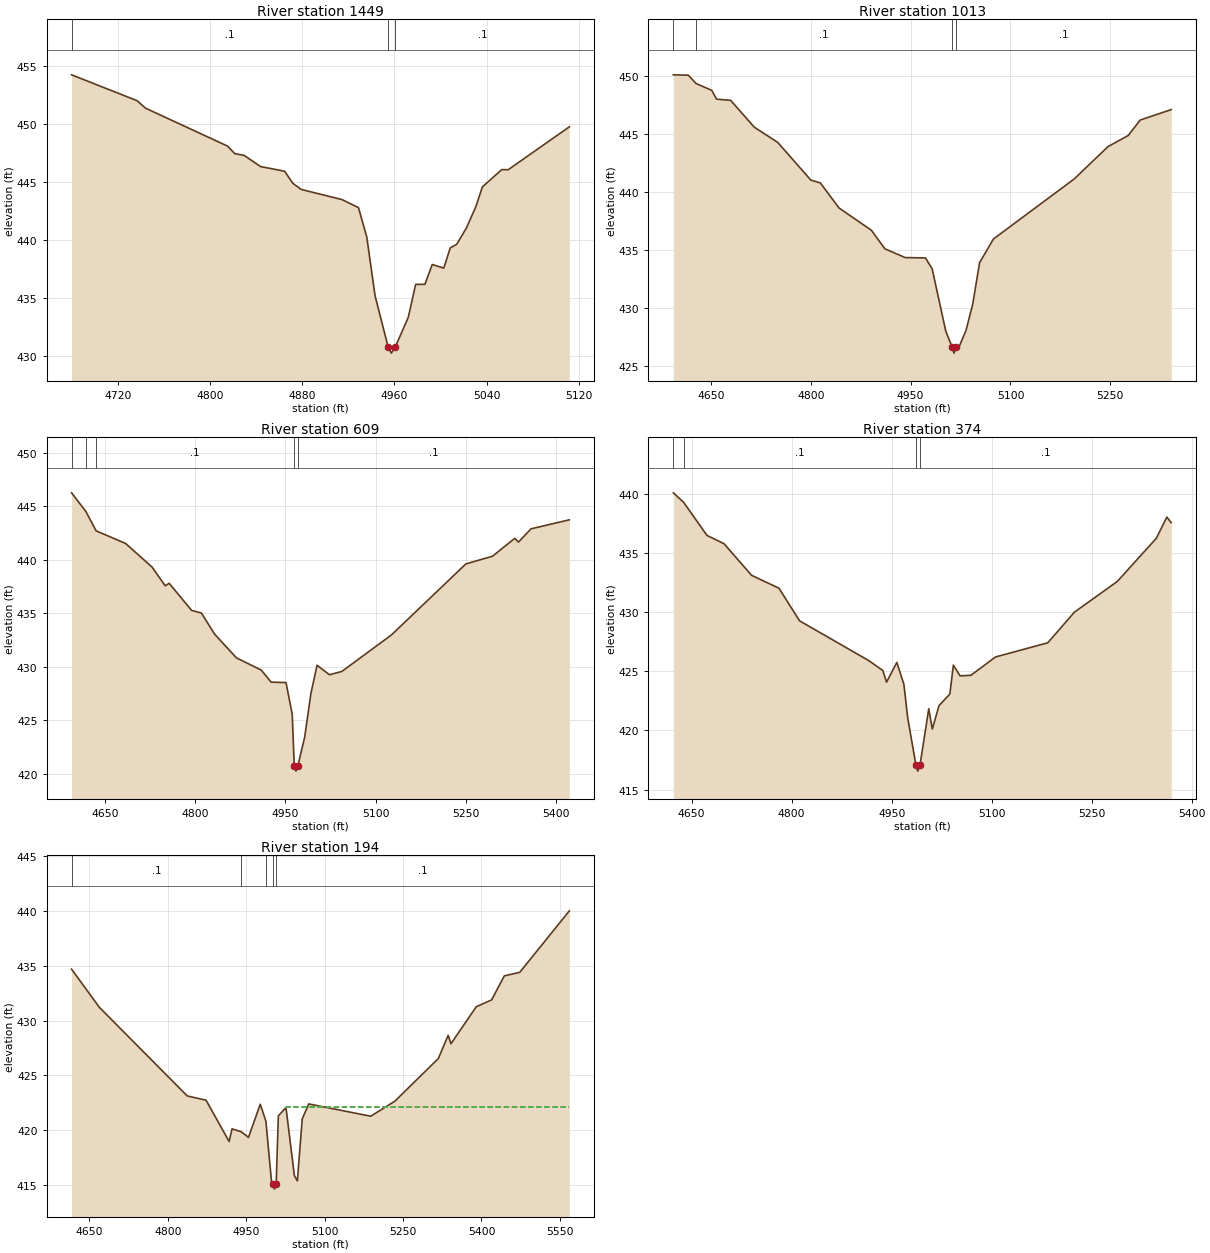
Type RM Length L Ch R = 1 ,1449    ,436,436,436
BEGIN DESCRIPTION:
UNT 140 IN LACR 3.0
END DESCRIPTION:
XS GIS Cut Line= 3
      2184737.69     13195246.88      2184987.72     13195046.85
      2185037.72     13194946.86
#Sta/Elev= 30
  4679.8  454.26  4736.7  452.03  4743.9  451.39  4815.1  448.12  4821.5  447.46
  4829.5  447.32  4843.9  446.35  4864.7  445.95  4871.9   444.9  4879.1  444.38
  4914.4  443.51  4928.8  442.81    4936  440.27  4943.2   435.2  4954.6  430.77
  4957.3  430.27  4960.6  430.77    4972  433.36  4978.4   436.2  4986.4   436.2
  4992.8  437.91  5002.8   437.6  5008.4  439.34    5014  439.65  5022.4  441.05
  5030.7  442.91  5036.3   444.6  5053.1  446.09  5058.7  446.08  5111.8  449.78
#Mann= 3 ,-1 , 0
  4679.8      .1       0  4954.6     .07       0  4960.6      .1       0
Bank Sta=4954.6,4960.6
XS Rating Curve= 0 ,0
Exp/Cntr=0.3,0.1

Type RM Length L Ch R = 1 ,1013    ,404,404,404
BEGIN DESCRIPTION:
UNT 140 IN LACR 2.0
END DESCRIPTION:
XS GIS Cut Line= 3
       2185047.3      13195698.3      2185237.72     13195496.85
      2185320.44     13195033.38
#Sta/Elev= 30
  4593.5  450.11    4616  450.08  4627.7  449.36  4651.2  448.77  4658.5  448.01
  4679.6  447.91  4715.2  445.59  4750.4  444.28  4800.1  441.03  4814.3  440.79
  4842.6  438.62    4891  436.71  4911.3  435.11  4941.8  434.35  4972.3  434.32
  4982.4  433.37  5002.8  428.01  5012.5  426.61  5015.2  426.11  5018.5  426.61
  5023.1   426.7  5033.2  428.06  5043.4  430.36  5053.6  433.91  5074.4  435.95
  5195.8  441.13  5246.6  443.92    5277  444.88  5294.9  446.21  5341.5  447.11
#Mann= 4 ,-1 , 0
  4593.5     .05       0  4627.7      .1       0  5012.5     .07       0
  5018.5      .1       0
Bank Sta=5012.5,5018.5
XS Rating Curve= 0 ,0
Exp/Cntr=0.3,0.1

Type RM Length L Ch R = 1 ,609     ,235,235,235
BEGIN DESCRIPTION:
Mapping XS da3a5f82
END DESCRIPTION:
XS GIS Cut Line= 4
      2185489.72     13195879.87      2185610.96     13195653.35
      2185508.86     13195241.78      2185422.72     13195123.74
#Sta/Elev= 30
  4594.7  446.26  4618.5  444.52  4635.5  442.71  4684.5  441.53  4728.4  439.33
  4750.3  437.58  4756.9  437.81  4794.2  435.28  4810.5  435.03  4832.4  433.06
  4868.6  430.85  4909.8  429.71  4926.3  428.58    4951  428.54  4961.3  425.59
  4964.7  420.77  4967.5  420.27  4970.7  420.77    4982  423.44  4992.3   427.5
  5002.6  430.16  5023.2  429.27  5043.8  429.58  5126.2  432.99  5249.8  439.62
  5294.1  440.34    5331  442.01  5337.2  441.66  5358.1   442.9  5421.8  443.74
#Mann= 5 ,-1 , 0
  4594.7      .1       0  4618.5     .05       0  4635.5      .1       0
  4964.7     .07       0  4970.7      .1       0
Bank Sta=4964.7,4970.7
XS Rating Curve= 0 ,0
Exp/Cntr=0.3,0.1

Type RM Length L Ch R = 1 ,374     ,180,180,180
BEGIN DESCRIPTION:
Mapping XS 19275d7a
END DESCRIPTION:
XS GIS Cut Line= 4
      2185780.76     13195860.76      2185842.19     13195609.46
      2185747.24      13195324.6      2185585.28     13195229.66
#Sta/Elev= 30
  4622.6  440.11    4638  439.31    4673  436.51  4698.7   435.8  4739.9  433.13
    4781  432.04  4811.9  429.28  4916.1   425.9  4936.8  425.07  4942.4  424.09
  4957.8  425.76  4968.4   423.9  4974.1  421.07  4986.5  417.06  4989.2  416.56
  4992.5  417.06  5005.7  421.84    5011  420.12  5021.1  422.11  5037.3  423.08
  5042.6  425.53  5052.7  424.62  5068.9  424.67  5105.8  426.22  5184.2  427.42
  5224.1  430.01  5288.5  432.61  5347.1  436.27  5362.8  438.06  5369.3  437.58
#Mann= 4 ,-1 , 0
  4622.6     .08       0    4638      .1       0  4986.5     .07       0
  4992.5      .1       0
#XS Ineff= 2 , 0
                         5005.91          421.76
Permanent Ineff=
       F       F
Bank Sta=4986.5,4992.5
XS Rating Curve= 0 ,0
Exp/Cntr=0.3,0.1

Type RM Length L Ch R = 1 ,194     ,0,0,0
BEGIN DESCRIPTION:
UNT 140 IN LACR 1.0
END DESCRIPTION:
XS GIS Cut Line= 4
      2185856.64     13195771.38      2186012.96     13195535.31
      2185878.96     13195292.83      2185515.23     13195146.06
#Sta/Elev= 30
  4615.8  434.69  4669.2   431.2  4837.1  423.13  4873.1  422.74  4917.2  418.98
  4922.9  420.13  4940.5  419.86  4954.3  419.35  4976.8  422.37  4987.6  420.83
  4998.5  415.23  5001.3  415.13    5004  414.63  5007.3  415.13  5011.4  421.31
    5026  422.07  5042.1  415.87  5047.8  415.38  5057.1  421.03  5069.5   422.4
  5188.1  421.28  5234.3  422.65  5317.5  426.54  5336.3  428.66  5341.7  427.89
    5390  431.26  5419.5  431.89  5443.7  434.08  5473.2   434.4  5568.2  440.01
#Mann= 5 ,-1 , 0
  4615.8      .1       0  4940.5     .12       0  4987.6      .1       0
  5001.3     .07       0  5007.3      .1       0
#XS Ineff= 2 , 0
                         5025.57          422.09
Permanent Ineff=
       F       F
Bank Sta=5001.3,5007.3
XS Rating Curve= 0 ,0
Exp/Cntr=0.3,0.1

Chan Stop Cuts=-1
Use User Specified Reach Order=0
Composite Channel Slope=5