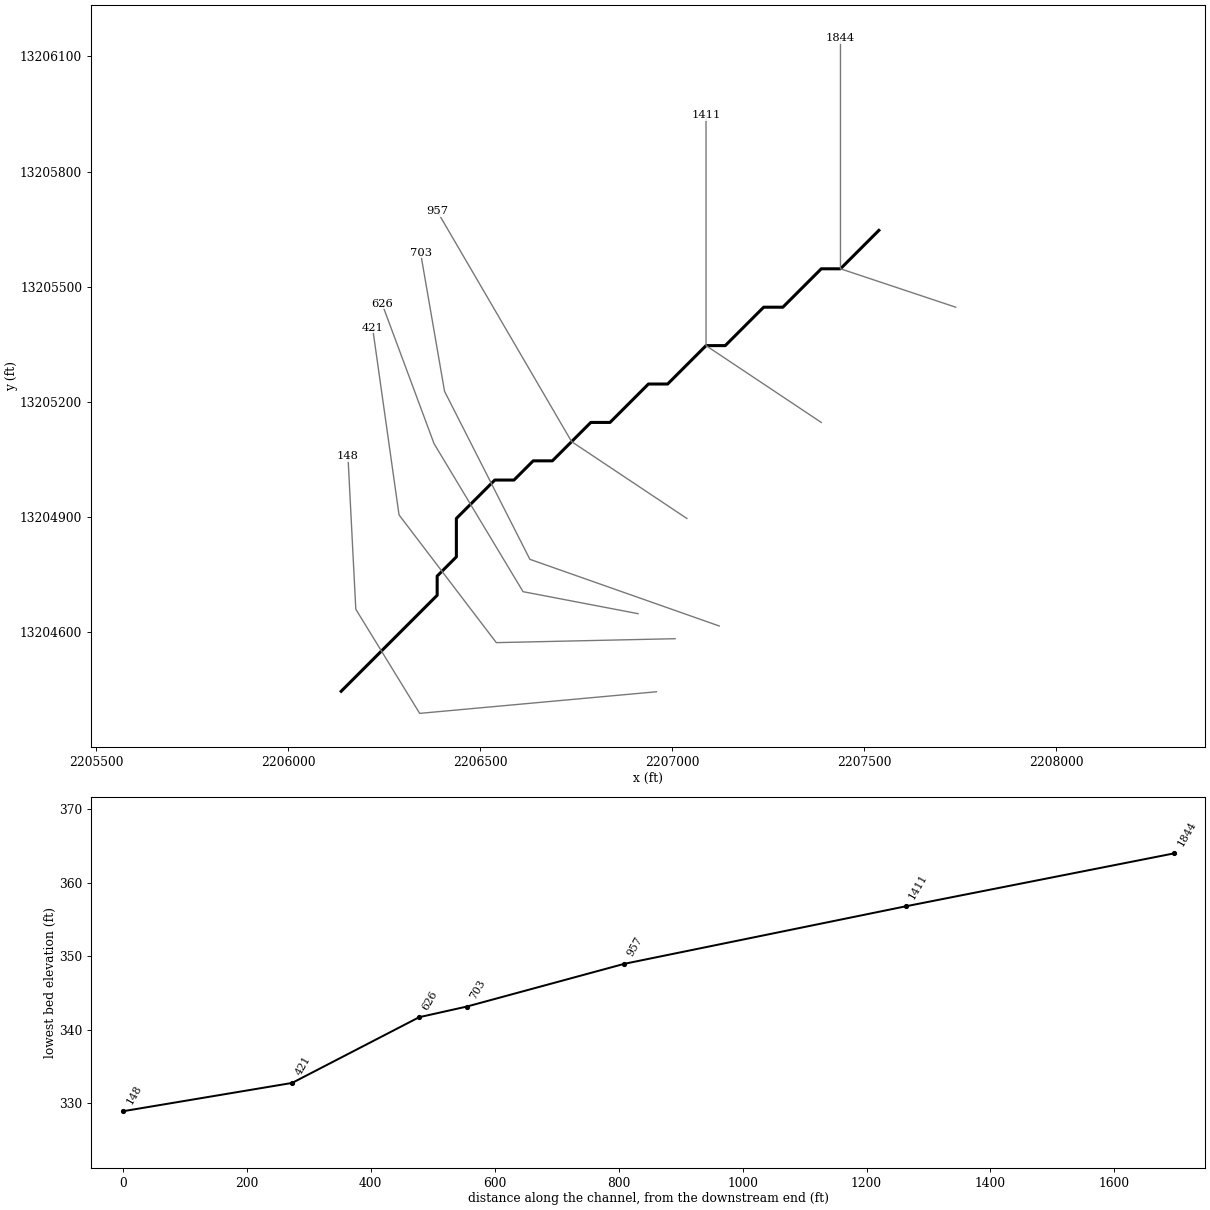
--- UNT 143 IN LACR.prj (project) ---

Proj Title=UNT 143 IN LACR Base Level Engineering
Current Plan=p01
Default Exp/Contr=0.3,0.1
English Units
Geom File=g01
Flow File=f01
Plan File=p01
Y Axis Title=Elevation
X Axis Title(PF)=Main Channel Distance
X Axis Title(XS)=Station
BEGIN DESCRIPTION:
UNT 143 IN LACR
END DESCRIPTION:
DSS Export Rating Curves= 0
DSS Export Rating Curve Sorted= 0
DSS Export Volume Flow Curves= 0
DXF OffsetX= 0
DXF OffsetY= 0
DXF ScaleX= 1
DXF ScaleY= 10

--- UNT 143 IN LACR.p01 (plan) ---

Plan Title=Multiple Run
Short Identifier=Multiple
Geom File=g01
Flow File=f01
Subcritical Flow
K Sum by GR= 0
Std Step Tol= 0.01
Critical Tol= 0.01
Num of Std Step Trials= 20
Max Error Tol= 0.3
Flow Tol Ratio= 0.001
Split Flow NTrial= 30
Split Flow Tol= 0.02
Split Flow Ratio= 0.02
Log Output Level= 0
Friction Slope Method= 1
Unsteady Friction Slope Method= 2
Unsteady Bridges Friction Slope Method= 1
Parabolic Critical Depth
Global Vel Dist=  1 , 1 , 1
Global Log Level= 0
CheckData=True
Encroach Param= -1, 0, 0, 0
BEGIN DESCRIPTION:
Multiple Run
END DESCRIPTION:

--- UNT 143 IN LACR.f01 (steady flow) ---

Flow Title=Multiple
Number of Profiles=7
Profile Names=10-year,25-year,50-year,1pct_min,100-year,1pct_plu,500-year
River Rch & RM= UNT 143 IN LACR,Reach-1,1844
      72      94     112      98     133     180     190
Boundary for River Rch & Prof#=UNT 143 IN LACR,Reach-1,1
Up Type=0
Dn Type=3
Dn Slope=0.005
Boundary for River Rch & Prof#=UNT 143 IN LACR,Reach-1,2
Up Type=0
Dn Type=3
Dn Slope=0.005
Boundary for River Rch & Prof#=UNT 143 IN LACR,Reach-1,3
Up Type=0
Dn Type=3
Dn Slope=0.005
Boundary for River Rch & Prof#=UNT 143 IN LACR,Reach-1,4
Up Type=0
Dn Type=3
Dn Slope=0.005
Boundary for River Rch & Prof#=UNT 143 IN LACR,Reach-1,5
Up Type=0
Dn Type=3
Dn Slope=0.005
Boundary for River Rch & Prof#=UNT 143 IN LACR,Reach-1,6
Up Type=0
Dn Type=3
Dn Slope=0.005
Boundary for River Rch & Prof#=UNT 143 IN LACR,Reach-1,7
Up Type=0
Dn Type=3
Dn Slope=0.005

--- UNT 143 IN LACR.g01 (geometry) ---

Geom Title=Existing Conditions
Program Version=4.10

River Reach=UNT 143 IN LACR ,Reach-1
Reach XY= 26
      2207537.72     13205646.85      2207487.72     13205596.86
      2207437.72     13205546.85      2207387.72     13205546.85
      2207337.72     13205496.85      2207287.72     13205446.86
      2207237.72     13205446.86      2207187.72     13205396.85
      2207137.72     13205346.85      2207087.72     13205346.85
      2206987.72     13205246.85      2206937.72     13205246.85
      2206837.72     13205146.85      2206787.72     13205146.85
      2206737.72     13205096.86      2206687.72     13205046.85
      2206637.72     13205046.85      2206587.72     13204996.85
      2206537.72     13204996.85      2206487.72     13204946.86
      2206437.72     13204896.85      2206437.72     13204796.86
      2206387.72     13204746.85      2206387.72     13204696.85
      2206187.72     13204496.85      2206137.72     13204446.86

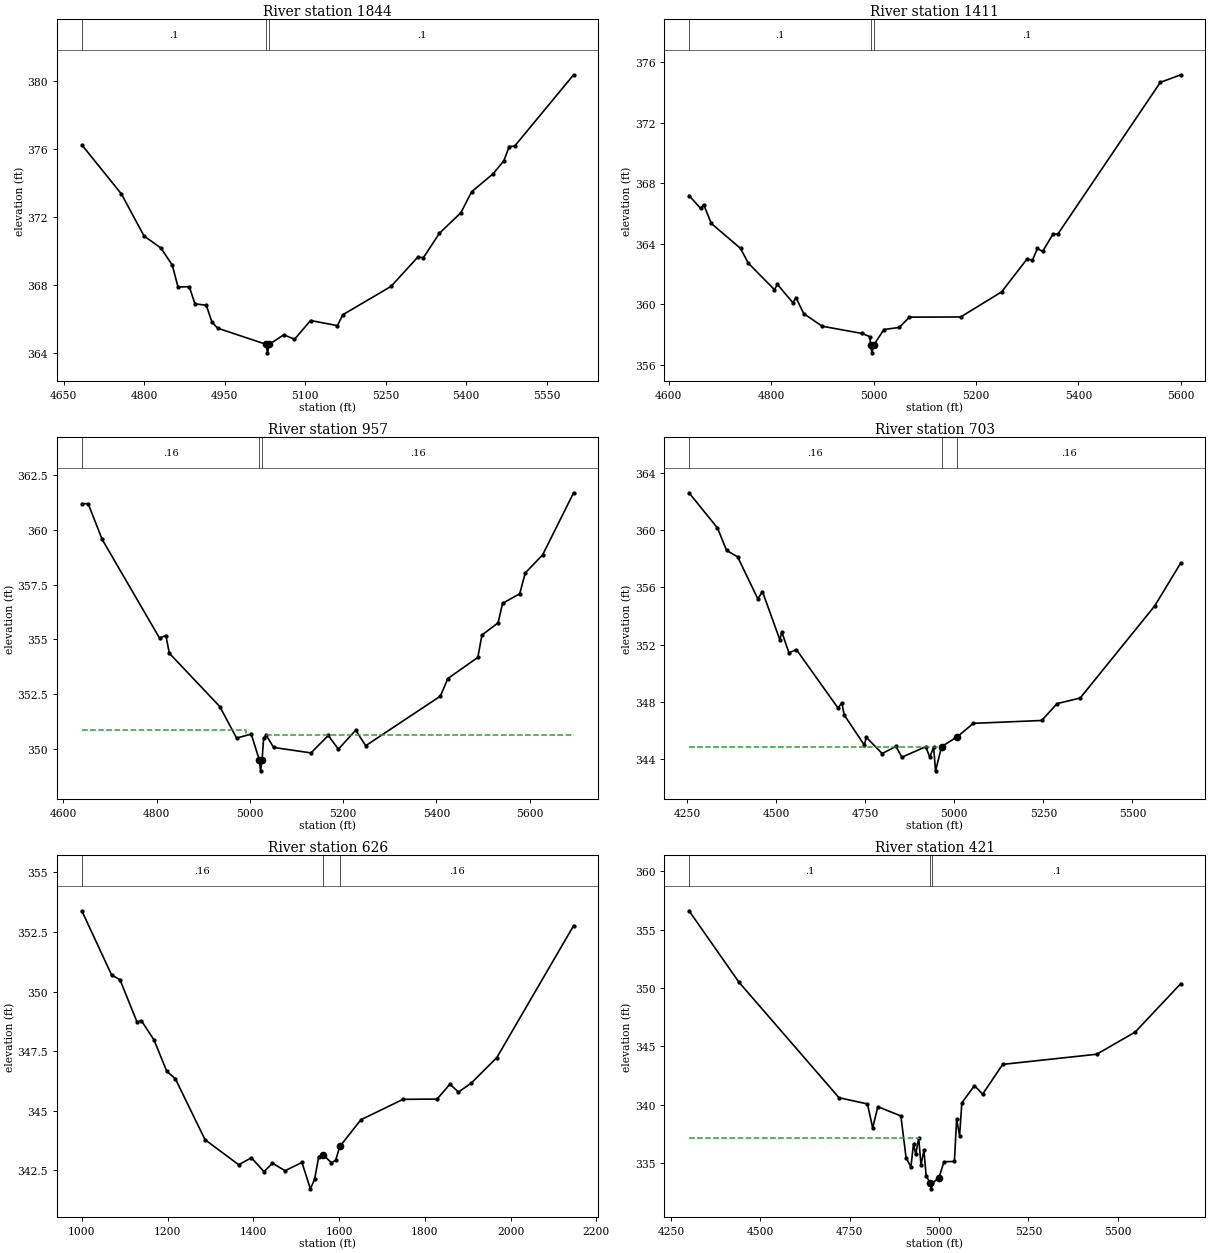
Type RM Length L Ch R = 1 ,1844    ,433,433,433
BEGIN DESCRIPTION:
UNT 143 IN LACR 4.0
END DESCRIPTION:
XS GIS Cut Line= 3
      2207737.69     13205446.86      2207437.72     13205546.85
      2207437.72     13206146.85
#Sta/Elev= 30
  4683.8  376.23  4757.6  373.34  4799.7  370.87  4831.3  370.16  4852.4  369.15
    4863  367.87    4884  367.89  4894.6  366.88  4915.7   366.8  4926.2  365.81
  4936.8  365.45    5027   364.5  5029.7     364    5033   364.5    5060  365.06
    5080   364.8    5110   365.9    5160   365.6    5170  366.24    5260  367.91
    5310  369.64    5320  369.59    5350  371.03    5390  372.24    5410  373.47
    5450  374.53    5470  375.29    5480  376.13    5490  376.15    5600  380.35
#Mann= 3 ,-1 , 0
  4683.8      .1       0    5027     .07       0    5033      .1       0
Bank Sta=5027,5033
XS Rating Curve= 0 ,0
Exp/Cntr=0.3,0.1

Type RM Length L Ch R = 1 ,1411    ,454,454,454
BEGIN DESCRIPTION:
UNT 143 IN LACR 3.0
END DESCRIPTION:
XS GIS Cut Line= 3
      2207387.76     13205146.83      2207087.72     13205346.85
      2207087.72     13205946.85
#Sta/Elev= 30
  4639.4   367.2    4662  366.35    4668   366.6    4683  365.35  4740.1   363.7
  4755.1  362.73  4806.2  360.98  4812.2  361.32  4842.3  360.11  4848.3  360.45
  4863.3   359.4  4899.3  358.56  4977.5  358.08  4992.5  357.87    4994   357.3
  4996.7   356.8    5000   357.3    5020  358.34    5050  358.48    5070  359.16
    5170  359.17    5250  360.83    5300  363.02    5310  362.91    5320   363.7
    5330   363.5    5350  364.63    5360  364.66    5560  374.68    5600  375.18
#Mann= 3 ,-1 , 0
  4639.4      .1       0    4994     .07       0    5000      .1       0
Bank Sta=4994,5000
XS Rating Curve= 0 ,0
Exp/Cntr=0.3,0.1

Type RM Length L Ch R = 1 ,957     ,254,254,254
BEGIN DESCRIPTION:
UNT 143 IN LACR 2.0
END DESCRIPTION:
XS GIS Cut Line= 3
      2207037.76     13204896.83      2206737.72     13205096.86
      2206387.73     13205696.84
#Sta/Elev= 30
  4639.4   361.2    4653   361.2    4683  359.57  4806.2  355.05  4819.7  355.17
  4827.2  354.36  4935.4  351.92  4971.5  350.48  5002.9  350.66  5020.2  349.48
  5022.9  348.98  5026.2  349.48  5029.4  350.47  5035.1  350.61  5050.9  350.05
  5131.1   349.8  5168.3   350.6  5189.8  349.97    5227  350.84  5248.5  350.13
  5408.9   352.4  5424.6   353.2  5489.1  354.17  5497.8  355.19  5532.5  355.75
  5542.1  356.64  5578.9  357.08  5590.8  358.03  5628.1  358.86  5694.6   361.7
#Mann= 3 ,-1 , 0
  4639.4     .16       0  5020.2     .07       0  5026.2     .16       0
#XS Ineff= 2 , 0
         4992.37  350.87 5035.06          350.61
Permanent Ineff=
       F       F
Bank Sta=5020.2,5026.2
XS Rating Curve= 0 ,0
Exp/Cntr=0.3,0.1

Type RM Length L Ch R = 1 ,703     ,77,77,77
BEGIN DESCRIPTION:
Mapping XS ee8f907f
END DESCRIPTION:
XS GIS Cut Line= 4
      2207122.13     13204616.84      2206629.11     13204790.44
      2206406.89     13205227.94      2206344.38     13205589.08
#Sta/Elev= 30
  4255.8  362.61  4335.6  360.15  4361.2  358.58  4392.2  358.13  4448.8   355.2
  4461.9   355.7  4510.7  352.33    4516  352.88  4536.1  351.43  4557.3  351.64
  4673.9  347.56  4684.6  347.93  4691.1  347.08  4747.7  344.97  4753.1  345.52
  4797.6  344.38  4836.5  344.88    4853  344.12  4919.9  344.86  4931.5  344.12
  4942.1  344.83  4947.5  343.17  4964.4  344.86  5008.9  345.56  5053.4  346.49
  5245.5  346.69  5288.4  347.87  5353.3  348.26  5562.4   354.7  5635.7  357.71
#Mann= 3 , 0 , 0
  4255.8     .16       0  4964.4     .07       0  5008.9     .16       0
#XS Ineff= 2 , 0
       0 4964.21  344.87               0
Permanent Ineff=
       T       F
Bank Sta=4964.4,5008.9
XS Rating Curve= 0 ,0
Exp/Cntr=0.3,0.1

Type RM Length L Ch R = 1 ,626     ,205,205,205
BEGIN DESCRIPTION:
Mapping XS 3843fa37
END DESCRIPTION:
XS GIS Cut Line= 4
     2206910.822    13204648.923     2206611.343    13204706.214
     2206379.572    13205091.631     2206244.155    13205456.214
#Sta/Elev= 30
    1000353.3914 1069.36350.7015 1089.17350.4915  1128.8348.7193 1138.71348.7847
 1168.44347.9682 1198.16346.6516 1217.98346.3471 1287.33343.7837 1366.02342.7299
  1395.5343.0265 1424.98342.4388 1444.63342.7954 1474.11342.4809 1513.41 342.829
 1533.07341.7199 1542.89342.1218 1552.72343.0751 1562.54343.1602  1582.2342.8125
 1592.02342.9211 1601.85343.5011 1650.98344.6207 1749.24345.4765 1828.71345.4888
 1858.56 346.113 1878.46345.7814 1908.31346.1587    1968347.2301 2147.09352.7667
#Mann= 3 , 0 , 0
    1000     .16       0 1562.54     .07       0 1601.85     .16       0
#XS Ineff= 2 , 0
       0 1553.99  343.06               0
Permanent Ineff=
       T       F
Bank Sta=1562.54,1601.85
XS Rating Curve= 0 ,0
Exp/Cntr=0.3,0.1

Type RM Length L Ch R = 1 ,421     ,273,273,273
BEGIN DESCRIPTION:
Mapping XS 0f41fb52
END DESCRIPTION:
XS GIS Cut Line= 4
      2207007.24     13204583.77      2206541.68     13204573.54
      2206288.43     13204906.09      2206219.57     13205393.28
#Sta/Elev= 30
  4300.8  356.62  4440.4   350.5  4720.4  340.59  4799.9  340.06  4814.5  338.01
    4829  339.82  4893.4  339.03    4908  335.44  4921.5  334.66  4928.8  336.65
  4935.1  335.74  4943.3  337.15  4949.6  334.84  4957.9  336.07  4964.1  333.88
  4975.7  333.28  4978.4  332.78  4981.7  333.28  4999.5  333.71    5014   335.1
  5043.1  335.13  5049.4  338.75  5057.7  337.34  5063.9  340.15  5099.3  341.63
  5122.1   340.9  5178.3  343.45  5441.2  344.32  5548.8  346.22  5676.5  350.38
#Mann= 3 ,-1 , 0
  4300.8      .1       0  4975.7     .07       0  4981.7      .1       0
#XS Ineff= 2 , 0
         4943.64   337.1
Permanent Ineff=
       F       F
Bank Sta=4975.7,4999.5
XS Rating Curve= 0 ,0
Exp/Cntr=0.3,0.1

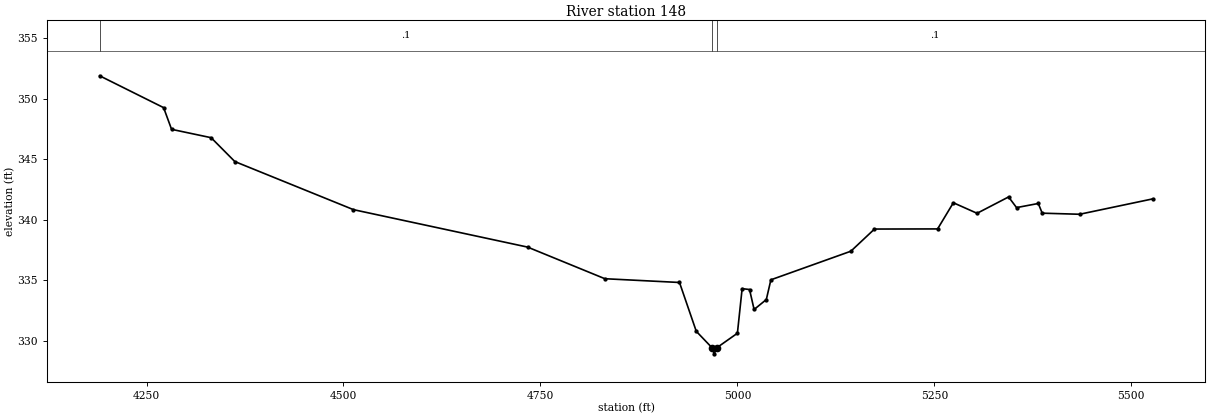
Type RM Length L Ch R = 1 ,148     ,0,0,0
BEGIN DESCRIPTION:
UNT 143 IN LACR 1.0
END DESCRIPTION:
XS GIS Cut Line= 4
      2206958.63     13204445.64      2206342.15     13204389.36
      2206175.88     13204660.51      2206155.42     13205059.58
#Sta/Elev= 30
  4190.5  351.88  4271.7  349.25  4281.8  347.46    4332  346.77  4362.1   344.8
  4512.7  340.83  4733.7  337.74  4831.8  335.13  4926.5  334.82  4947.8  330.79
  4967.8  329.43  4970.6  328.93  4973.8  329.43    5000  330.63    5006  334.31
  5015.4  334.24  5021.2  332.59  5036.7  333.41  5042.5  335.04    5144   337.4
    5174  339.23  5254.1  339.24  5274.1   341.4  5304.2  340.53  5344.2  341.88
  5354.3     341  5381.9  341.34  5386.9  340.54  5434.4  340.45  5527.2  341.72
#Mann= 3 ,-1 , 0
  4190.5      .1       0  4967.8     .07       0  4973.8      .1       0
Bank Sta=4967.8,4973.8
XS Rating Curve= 0 ,0
Exp/Cntr=0.3,0.1

Chan Stop Cuts=-1
Use User Specified Reach Order=0
Composite Channel Slope=5