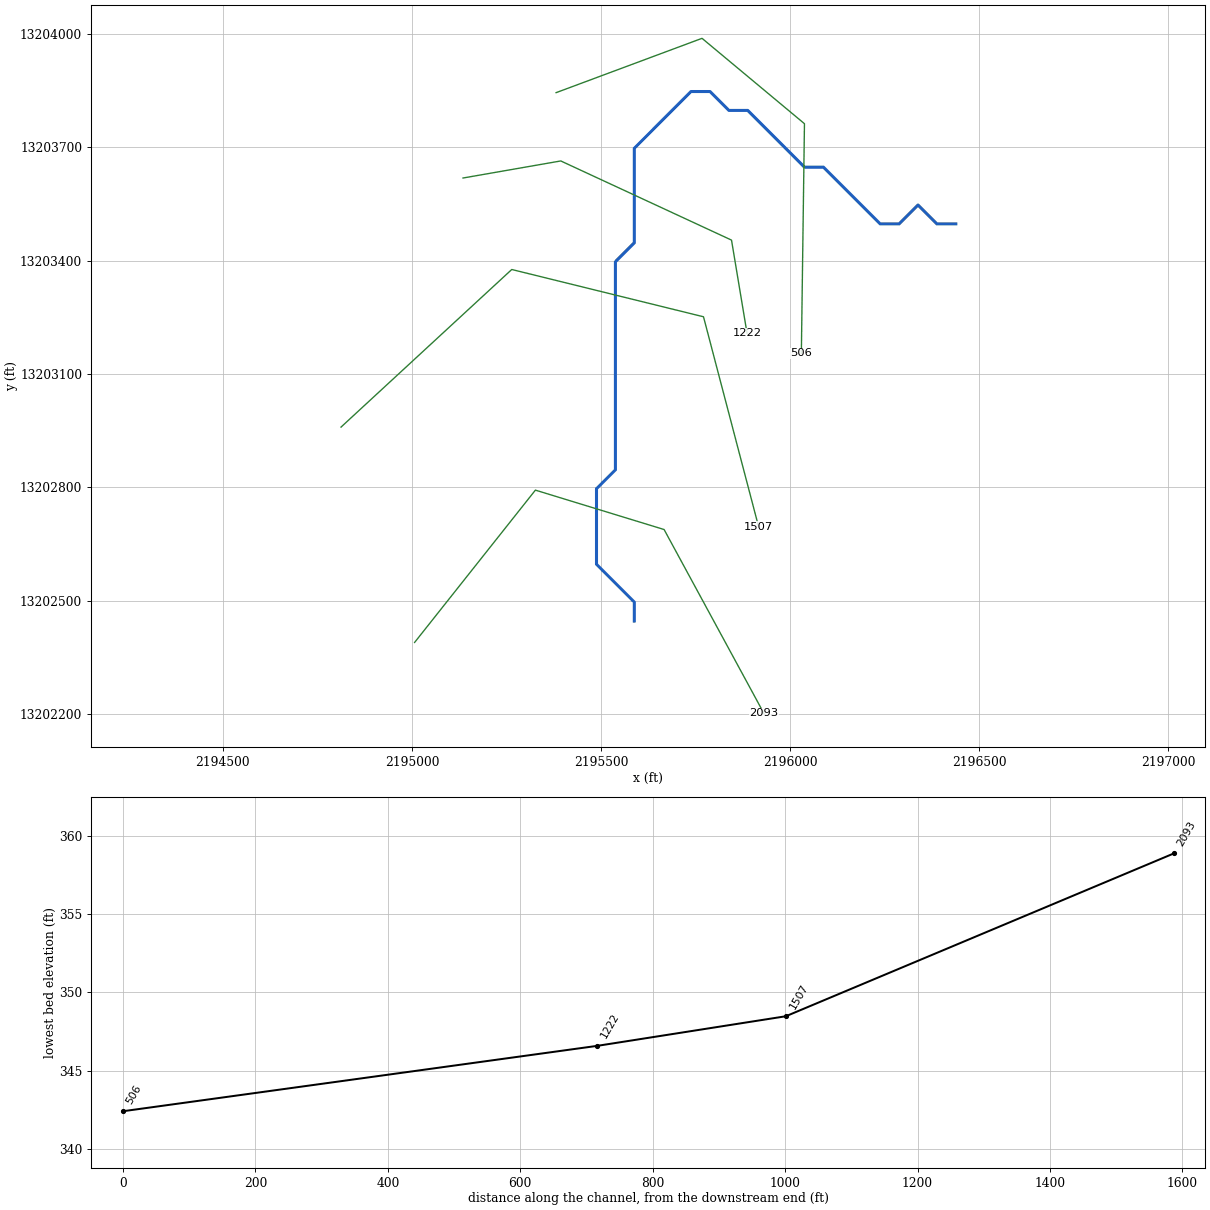
--- UNT 146 IN LACR.prj (project) ---

Proj Title=UNT 146 IN LACR Base Level Engineering
Current Plan=p01
Default Exp/Contr=0.3,0.1
English Units
Geom File=g01
Flow File=f01
Plan File=p01
Y Axis Title=Elevation
X Axis Title(PF)=Main Channel Distance
X Axis Title(XS)=Station
BEGIN DESCRIPTION:
UNT 146 IN LACR
END DESCRIPTION:
DSS Export Rating Curves= 0
DSS Export Rating Curve Sorted= 0
DSS Export Volume Flow Curves= 0
DXF OffsetX= 0
DXF OffsetY= 0
DXF ScaleX= 1
DXF ScaleY= 10

--- UNT 146 IN LACR.p01 (plan) ---

Plan Title=Multiple Run
Short Identifier=Multiple
Geom File=g01
Flow File=f01
Subcritical Flow
K Sum by GR= 0
Std Step Tol= 0.01
Critical Tol= 0.01
Num of Std Step Trials= 20
Max Error Tol= 0.3
Flow Tol Ratio= 0.001
Split Flow NTrial= 30
Split Flow Tol= 0.02
Split Flow Ratio= 0.02
Log Output Level= 0
Friction Slope Method= 1
Unsteady Friction Slope Method= 2
Unsteady Bridges Friction Slope Method= 1
Parabolic Critical Depth
Global Vel Dist=  1 , 1 , 1
Global Log Level= 0
CheckData=True
Encroach Param= -1, 0, 0, 0
BEGIN DESCRIPTION:
Multiple Run
END DESCRIPTION:

--- UNT 146 IN LACR.f01 (steady flow) ---

Flow Title=Multiple
Number of Profiles=7
Profile Names=10-year,25-year,50-year,1pct_min,100-year,1pct_plu,500-year
River Rch & RM= UNT 146 IN LACR,Reach-1,2093
      87     115     137     121     163     221     235
Boundary for River Rch & Prof#=UNT 146 IN LACR,Reach-1,1
Up Type=0
Dn Type=3
Dn Slope=0.005
Boundary for River Rch & Prof#=UNT 146 IN LACR,Reach-1,2
Up Type=0
Dn Type=3
Dn Slope=0.005
Boundary for River Rch & Prof#=UNT 146 IN LACR,Reach-1,3
Up Type=0
Dn Type=3
Dn Slope=0.005
Boundary for River Rch & Prof#=UNT 146 IN LACR,Reach-1,4
Up Type=0
Dn Type=3
Dn Slope=0.005
Boundary for River Rch & Prof#=UNT 146 IN LACR,Reach-1,5
Up Type=0
Dn Type=3
Dn Slope=0.005
Boundary for River Rch & Prof#=UNT 146 IN LACR,Reach-1,6
Up Type=0
Dn Type=3
Dn Slope=0.005
Boundary for River Rch & Prof#=UNT 146 IN LACR,Reach-1,7
Up Type=0
Dn Type=3
Dn Slope=0.005

--- UNT 146 IN LACR.g01 (geometry) ---

Geom Title=Existing Conditions
Program Version=4.10

River Reach=UNT 146 IN LACR ,Reach-1
Reach XY= 25
      2195587.72     13202446.85      2195587.72     13202496.86
      2195537.72     13202546.85      2195487.72     13202596.85
      2195487.72     13202796.86      2195537.72     13202846.85
      2195537.72     13203396.85      2195587.72     13203446.85
      2195587.72     13203696.85      2195637.72     13203746.85
      2195687.72     13203796.86      2195737.72     13203846.85
      2195787.72     13203846.85      2195837.72     13203796.86
      2195887.72     13203796.86      2195937.72     13203746.85
      2195987.72     13203696.85      2196037.72     13203646.86
      2196087.72     13203646.86      2196137.72     13203596.85
      2196237.72     13203496.85      2196287.72     13203496.85
      2196337.72     13203546.85      2196387.72     13203496.85
      2196437.72     13203496.85

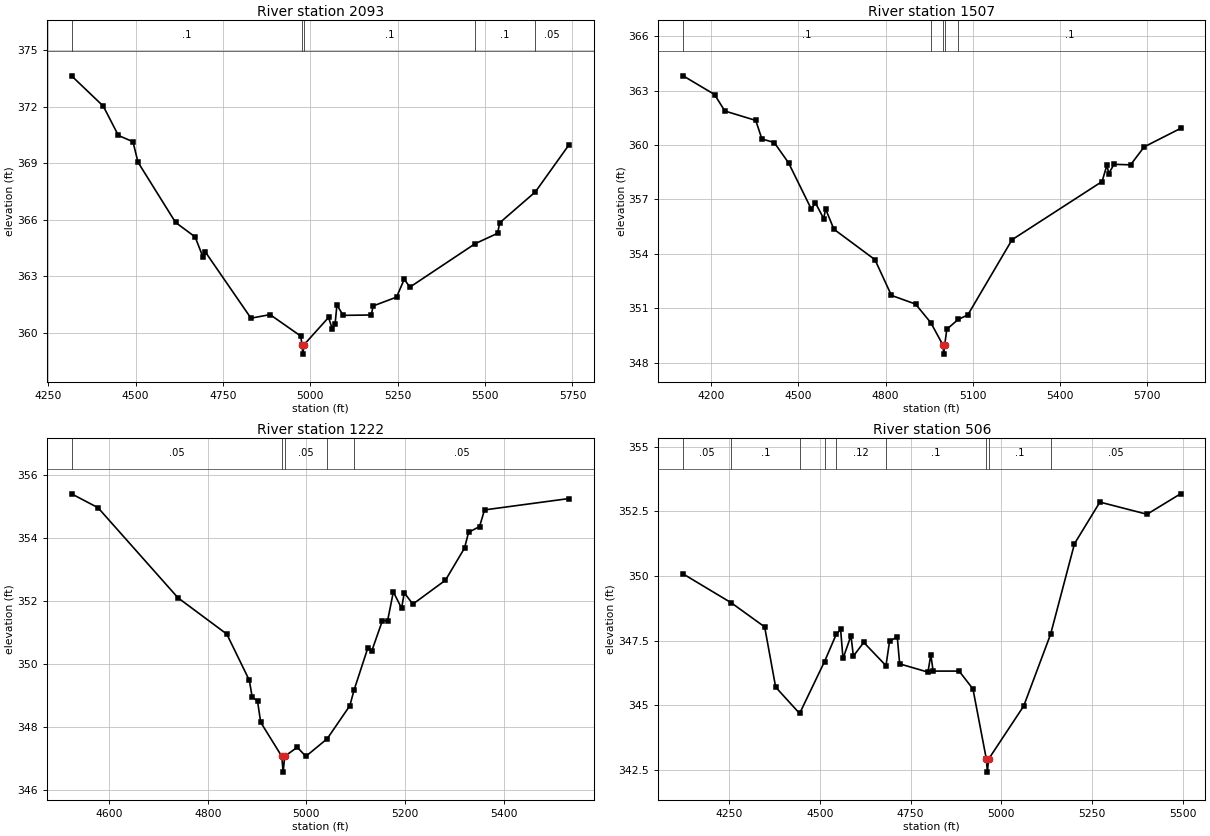
Type RM Length L Ch R = 1 ,2093    ,586,586,586
BEGIN DESCRIPTION:
UNT 146 IN LACR 2.0
END DESCRIPTION:
XS GIS Cut Line= 4
      2195006.74     13202390.22      2195326.16     13202792.97
      2195666.44     13202688.81      2195930.32     13202202.72
#Sta/Elev= 30
    4317  373.65  4407.8  372.04    4451  370.48  4492.7  370.15  4507.1  369.06
  4614.5  365.86  4670.5  365.09    4693  364.02  4699.4   364.3  4830.3  360.77
    4885  360.96  4972.7  359.82  4976.1  359.36  4978.8  358.86  4982.1  359.36
  5052.3  360.81  5062.7  360.21    5071  360.46  5076.2  361.47  5094.1  360.92
  5174.5  360.94  5179.8  361.42  5246.8  361.89  5268.8  362.84  5284.9  362.42
  5471.7  364.73  5535.8  365.28  5541.9  365.84  5643.8  367.48    5740  369.98
#Mann= 5 ,-1 , 0
    4317      .1       0  4976.1     .05       0  4982.1      .1       0
  5471.7      .1       0  5643.8     .05       0
Bank Sta=4976.1,4982.1
XS Rating Curve= 0 ,0
Exp/Cntr=0.3,0.1

Type RM Length L Ch R = 1 ,1507    ,285,285,285
BEGIN DESCRIPTION:
Mapping XS f6d51345
END DESCRIPTION:
XS GIS Cut Line= 4
      2194812.25     13202959.62      2195263.66     13203376.31
      2195770.61     13203251.31      2195916.43     13202695.79
#Sta/Elev= 30
  4103.4  363.82  4211.4  362.79  4246.9  361.88  4353.2  361.36  4374.2  360.34
  4416.7  360.14    4466  359.02  4544.3  356.47  4558.4  356.81  4586.8  355.95
  4593.6  356.47  4621.9  355.36  4763.1  353.68  4819.8  351.71  4902.8  351.23
  4955.4   350.2    4997  348.97  4999.7  348.47    5003  348.97  5010.3  349.84
  5049.1  350.38  5082.4  350.63  5234.7  354.78  5544.3  357.99  5561.5  358.92
  5566.7  358.42  5585.6  358.94  5642.3  358.91    5689   359.9  5814.2  360.92
#Mann= 5 ,-1 , 0
  4103.4      .1       0  4955.4     .12       0    4997     .07       0
    5003     .12       0  5049.1      .1       0
Bank Sta=4997,5003
XS Rating Curve= 0 ,0
Exp/Cntr=0.3,0.1

Type RM Length L Ch R = 1 ,1222    ,716,716,716
BEGIN DESCRIPTION:
Mapping XS 4a93c44c
END DESCRIPTION:
XS GIS Cut Line= 4
      2195134.81     13203618.17      2195393.29      13203663.3
      2195844.68     13203454.02      2195885.71     13203207.85
#Sta/Elev= 30
  4523.3  355.41    4577  354.97  4739.4  352.11  4838.4  350.96  4884.2  349.49
  4889.8  348.97  4900.8  348.83  4907.2  348.16    4950  347.08  4952.7  346.58
    4956  347.08  4981.4  347.37  4998.8  347.08  5042.2  347.64  5088.2  348.69
  5096.4  349.17  5124.4  350.51  5132.3  350.41  5154.3  351.39  5164.7  351.38
  5176.4   352.3  5193.1  351.78  5198.6  352.27    5216  351.91  5282.2  352.67
  5320.9  353.69  5329.1  354.19  5351.3  354.37  5361.5   354.9  5532.8  355.26
#Mann= 5 ,-1 , 0
  4523.3     .05       0    4950     .03       0    4956     .05       0
  5042.2     .12       0  5096.4     .05       0
Bank Sta=4950,4956
XS Rating Curve= 0 ,0
Exp/Cntr=0.3,0.1

Type RM Length L Ch R = 1 ,506     ,0,0,0
BEGIN DESCRIPTION:
UNT 146 IN LACR 1.0
END DESCRIPTION:
XS GIS Cut Line= 4
      2195380.96     13203843.85      2195766.71     13203987.48
      2196037.55     13203761.79      2196029.34     13203154.51
#Sta/Elev= 30
  4122.6  350.08  4255.6  348.96  4347.4  348.03  4377.7   345.7  4443.8  344.68
  4512.5  346.69  4544.7  347.74  4556.8  347.93  4563.4  346.81  4585.5  347.69
    4592   346.9  4620.6  347.43  4681.9  346.53  4691.7  347.47    4713  347.65
  4719.6   346.6  4797.7  346.28  4805.5  346.95    4812  346.32  4883.6  346.32
  4921.7  345.63  4958.7  342.91  4961.5  342.41  4964.7  342.91  5061.7  344.97
  5135.9  347.75  5201.7  351.25  5271.7  352.86  5401.7  352.39  5494.1  353.18
#Mann= 9 ,-1 , 0
  4122.6     .05       0  4255.6      .1       0  4443.8     .12       0
  4512.5      .1       0  4544.7     .12       0  4681.9      .1       0
  4958.7     .07       0  4964.7      .1       0  5135.9     .05       0
Bank Sta=4958.7,4964.7
XS Rating Curve= 0 ,0
Exp/Cntr=0.3,0.1

Chan Stop Cuts=-1
Use User Specified Reach Order=0
Composite Channel Slope=5