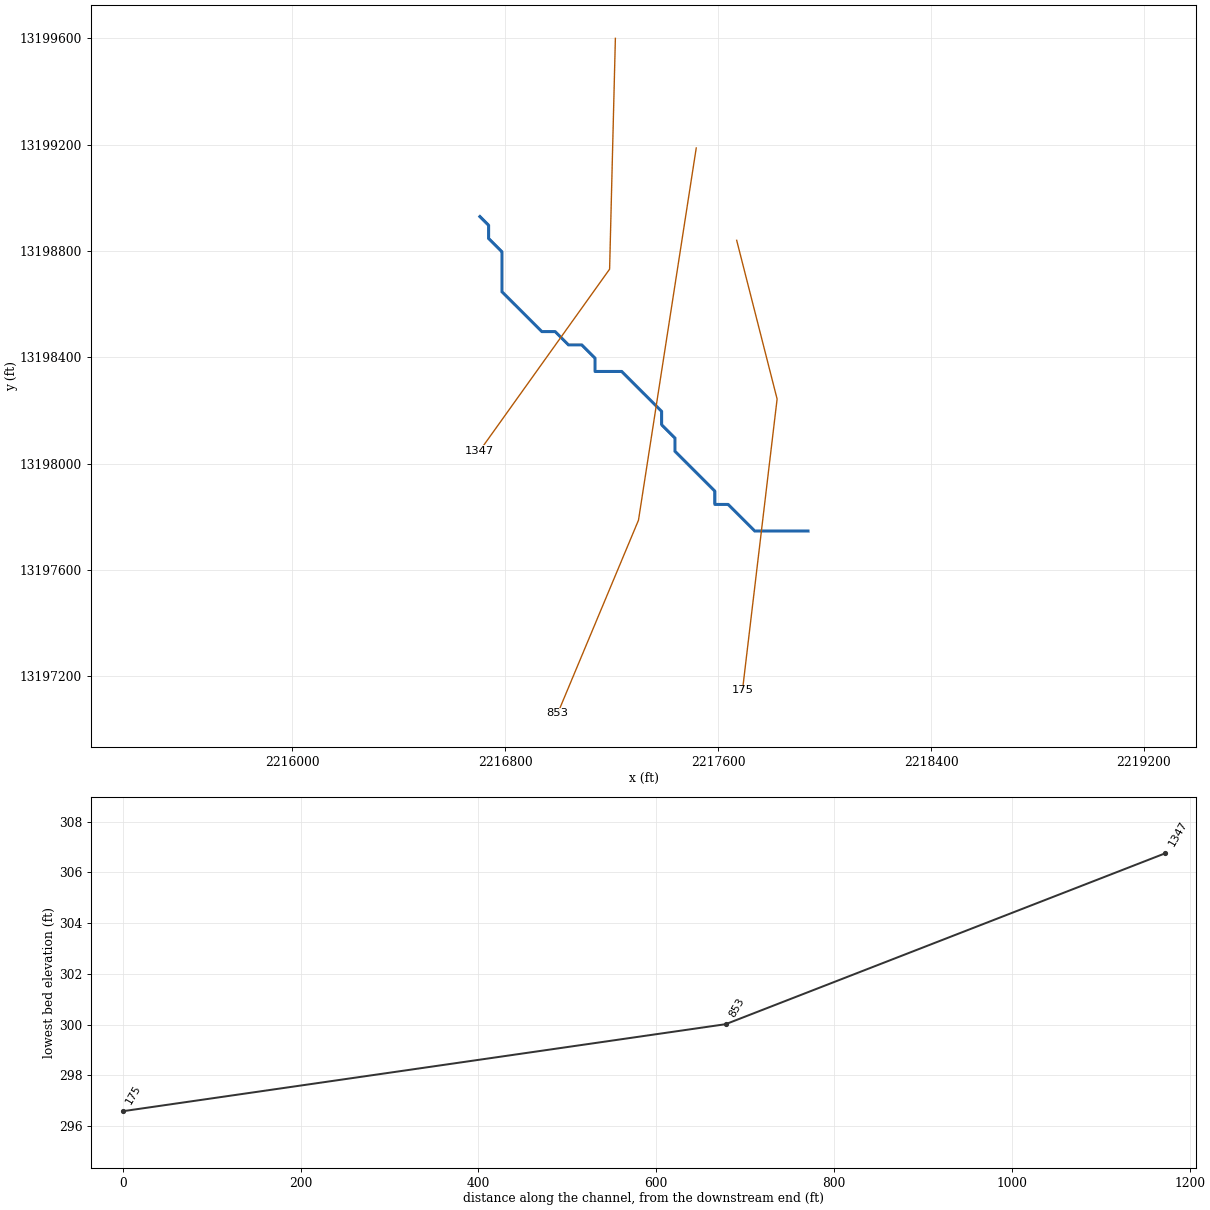
--- UNT 147 IN LACR.prj (project) ---

Proj Title=UNT 147 IN LACR Base Level Engineering
Current Plan=p01
Default Exp/Contr=0.3,0.1
English Units
Geom File=g01
Flow File=f01
Plan File=p01
Y Axis Title=Elevation
X Axis Title(PF)=Main Channel Distance
X Axis Title(XS)=Station
BEGIN DESCRIPTION:
UNT 147 IN LACR
END DESCRIPTION:
DSS Export Rating Curves= 0
DSS Export Rating Curve Sorted= 0
DSS Export Volume Flow Curves= 0
DXF OffsetX= 0
DXF OffsetY= 0
DXF ScaleX= 1
DXF ScaleY= 10

--- UNT 147 IN LACR.p01 (plan) ---

Plan Title=Multiple Run
Short Identifier=Multiple
Geom File=g01
Flow File=f01
Subcritical Flow
K Sum by GR= 0
Std Step Tol= 0.01
Critical Tol= 0.01
Num of Std Step Trials= 20
Max Error Tol= 0.3
Flow Tol Ratio= 0.001
Split Flow NTrial= 30
Split Flow Tol= 0.02
Split Flow Ratio= 0.02
Log Output Level= 0
Friction Slope Method= 1
Unsteady Friction Slope Method= 2
Unsteady Bridges Friction Slope Method= 1
Parabolic Critical Depth
Global Vel Dist=  1 , 1 , 1
Global Log Level= 0
CheckData=True
Encroach Param= -1, 0, 0, 0
BEGIN DESCRIPTION:
Multiple Run
END DESCRIPTION:

--- UNT 147 IN LACR.f01 (steady flow) ---

Flow Title=Multiple
Number of Profiles=7
Profile Names=10-year,25-year,50-year,1pct_min,100-year,1pct_plu,500-year
River Rch & RM= UNT 147 IN LACR,Reach-1,1347
     129     173     208     184     249     337     363
Boundary for River Rch & Prof#=UNT 147 IN LACR,Reach-1,1
Up Type=0
Dn Type=3
Dn Slope=0.005
Boundary for River Rch & Prof#=UNT 147 IN LACR,Reach-1,2
Up Type=0
Dn Type=3
Dn Slope=0.005
Boundary for River Rch & Prof#=UNT 147 IN LACR,Reach-1,3
Up Type=0
Dn Type=3
Dn Slope=0.005
Boundary for River Rch & Prof#=UNT 147 IN LACR,Reach-1,4
Up Type=0
Dn Type=3
Dn Slope=0.005
Boundary for River Rch & Prof#=UNT 147 IN LACR,Reach-1,5
Up Type=0
Dn Type=3
Dn Slope=0.005
Boundary for River Rch & Prof#=UNT 147 IN LACR,Reach-1,6
Up Type=0
Dn Type=3
Dn Slope=0.005
Boundary for River Rch & Prof#=UNT 147 IN LACR,Reach-1,7
Up Type=0
Dn Type=3
Dn Slope=0.005

--- UNT 147 IN LACR.g01 (geometry) ---

Geom Title=Existing Conditions
Program Version=4.10

River Reach=UNT 147 IN LACR ,Reach-1
Reach XY= 26
      2216705.08      13198929.5      2216737.72     13198896.86
      2216737.72     13198846.85      2216787.72     13198796.85
      2216787.72     13198646.85      2216837.72     13198596.85
      2216887.72     13198546.86      2216937.72     13198496.85
      2216987.72     13198496.85      2217037.72     13198446.85
      2217087.72     13198446.85      2217137.72     13198396.86
      2217137.72     13198346.85      2217237.72     13198346.85
      2217387.72     13198196.85      2217387.72     13198146.85
      2217437.72     13198096.85      2217437.72     13198046.86
      2217487.72     13197996.85      2217537.72     13197946.85
      2217587.72     13197896.86      2217587.72     13197846.85
      2217637.72     13197846.85      2217687.72     13197796.85
      2217737.72     13197746.86      2217937.72     13197746.86

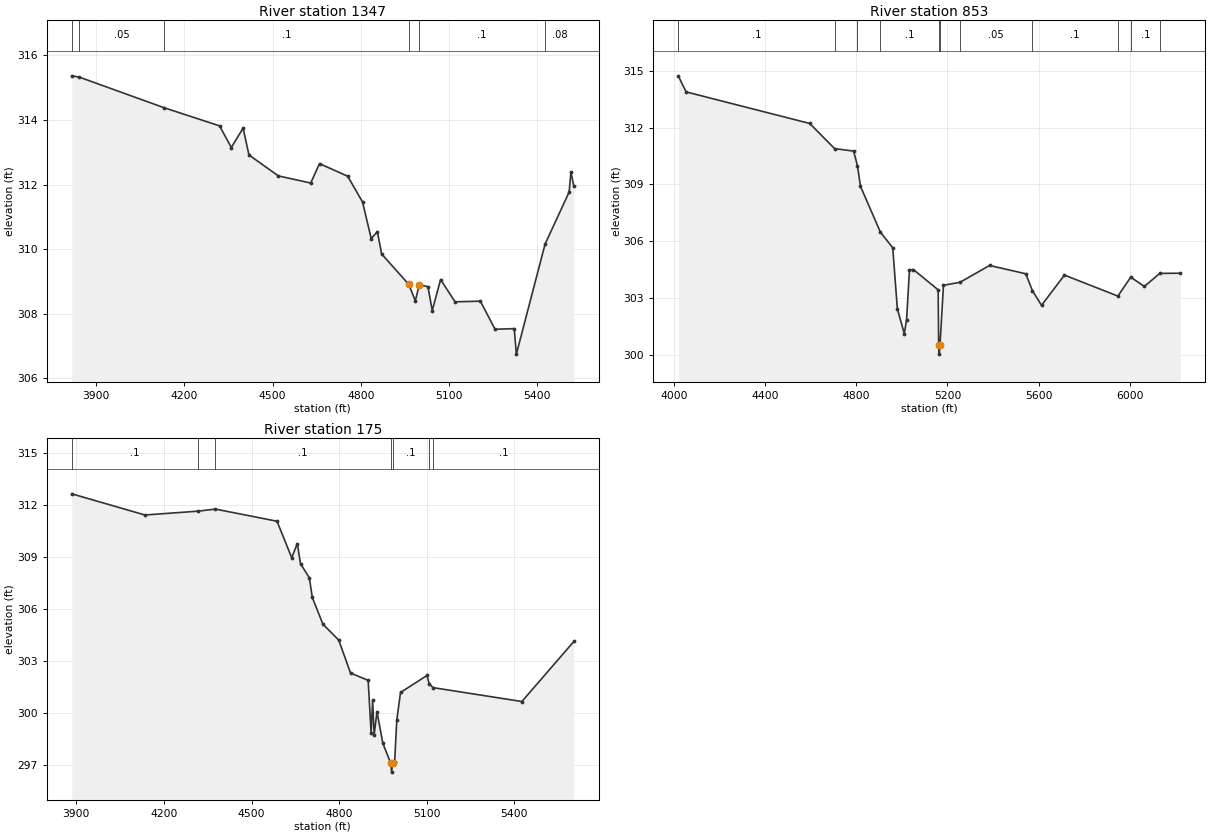
Type RM Length L Ch R = 1 ,1347    ,494,494,494
BEGIN DESCRIPTION:
UNT 147 IN LACR 2.0
END DESCRIPTION:
XS GIS Cut Line= 3
      2217214.02     13199599.56      2217192.32     13198731.55
      2216704.02     13198047.92
#Sta/Elev= 30
  3816.8  315.37  3842.4  315.33  4131.6  314.38  4319.7  313.82  4359.7  313.15
  4399.7  313.75  4419.7  312.92  4519.7  312.27  4629.8  312.05  4659.8  312.65
  4755.8  312.26  4806.2  311.46  4835.7  310.33  4856.6  310.54  4871.3  309.85
  4963.5  308.91  4985.8   308.4  4999.2   308.9  5028.6  308.84  5043.4   308.1
  5071.8  309.06    5121  308.37    5207  308.39  5257.2  307.52  5322.4  307.54
  5329.6  306.75  5427.4  310.16  5509.2  311.77  5515.3  312.39  5525.2  311.95
#Mann= 6 ,-1 , 0
  3816.8      .1       0  3842.4     .05       0  4131.6      .1       0
  4963.5     .07       0  4999.2      .1       0  5427.4     .08       0
Bank Sta=4963.5,4999.2
XS Rating Curve= 0 ,0
Exp/Cntr=0.3,0.1

Type RM Length L Ch R = 1 ,853     ,678,678,678
BEGIN DESCRIPTION:
Mapping XS 0da5abc2
END DESCRIPTION:
XS GIS Cut Line= 3
      2217517.84     13199187.25      2217300.83     13197787.54
      2216997.27     13197061.15
#Sta/Elev= 30
  4018.3  314.74  4052.9  313.89  4595.5  312.22  4704.5  310.89  4787.8  310.76
  4804.9  309.99  4818.1   308.9  4905.4  306.48  4959.8  305.64  4980.1  302.41
  5010.4  301.11  5020.5  301.84  5033.2  304.47  5050.9  304.49  5159.2  303.42
  5161.3  300.52    5164  300.02  5167.3  300.52  5182.4  303.66  5255.3  303.82
  5384.8  304.71  5543.9  304.27  5572.7  303.38  5612.8   302.6  5713.5   304.2
    5948  303.09  6004.4  304.09  6064.1   303.6  6132.1  304.29    6222   304.3
#Mann= 11 ,-1 , 0
  4018.3      .1       0  4704.5     .08       0  4804.9     .05       0
  4905.4      .1       0  5161.3     .07       0  5167.3      .1       0
  5255.3     .05       0  5572.7      .1       0    5948     .08       0
  6004.4      .1       0  6132.1     .16       0
Bank Sta=5161.3,5167.3
XS Rating Curve= 0 ,0
Exp/Cntr=0.3,0.1

Type RM Length L Ch R = 1 ,175     ,0,0,0
BEGIN DESCRIPTION:
UNT 147 IN LACR 1.0
END DESCRIPTION:
XS GIS Cut Line= 3
      2217669.76     13198840.03      2217821.66     13198243.26
      2217691.46     13197147.37
#Sta/Elev= 30
  3884.3  312.63  4134.8  311.41  4316.3  311.63  4376.3  311.75  4587.1  311.05
  4637.5  308.95  4656.6  309.76  4667.7   308.6  4697.9  307.79    4708  306.66
  4744.3  305.12  4798.6   304.2  4838.9   302.3  4899.3  301.88  4909.4  298.86
  4914.7  300.74  4919.7  298.72  4929.5  300.07  4949.6  298.25  4976.9  297.09
  4979.6  296.59  4982.9  297.09  4989.9  297.15  4997.3  299.58  5010.1  301.18
  5100.7  302.16  5108.5  301.67  5121.5  301.46  5425.7  300.66  5603.7  304.12
#Mann= 7 ,-1 , 0
  3884.3      .1       0  4316.3     .05       0  4376.3      .1       0
  4976.9     .07       0  4982.9      .1       0  5108.5     .05       0
  5121.5      .1       0
Bank Sta=4976.9,4982.9
XS Rating Curve= 0 ,0
Exp/Cntr=0.3,0.1

Chan Stop Cuts=-1
Use User Specified Reach Order=0
Composite Channel Slope=5