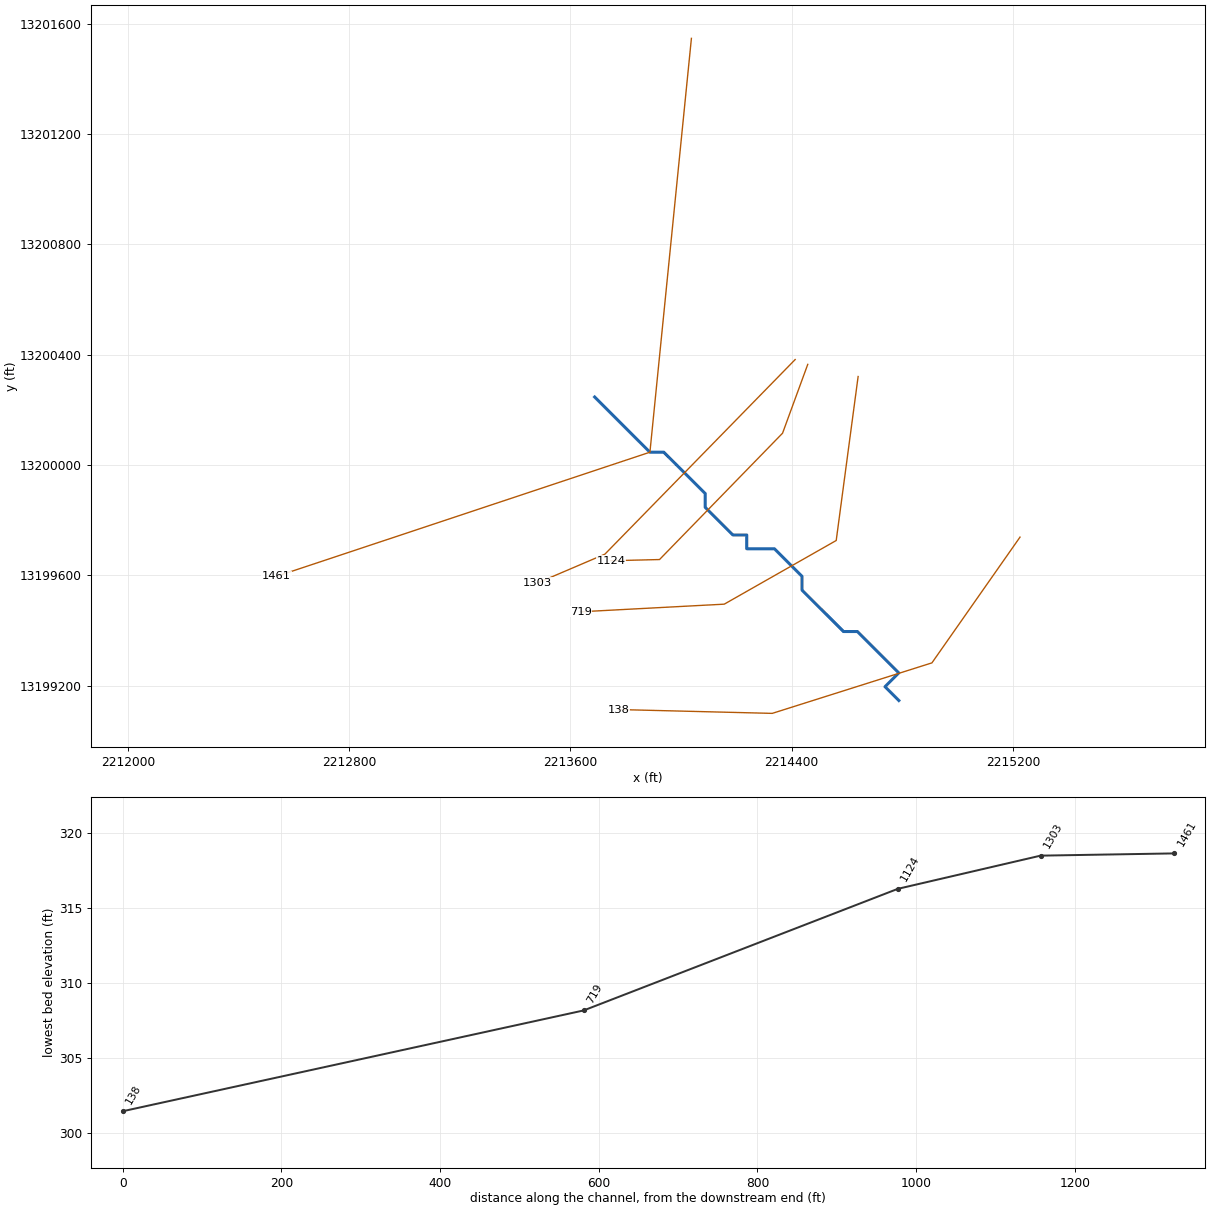
--- UNT 148 IN LACR.prj (project) ---

Proj Title=UNT 148 IN LACR Base Level Engineering
Current Plan=p01
Default Exp/Contr=0.3,0.1
English Units
Geom File=g01
Flow File=f01
Plan File=p01
Y Axis Title=Elevation
X Axis Title(PF)=Main Channel Distance
X Axis Title(XS)=Station
BEGIN DESCRIPTION:
UNT 148 IN LACR
END DESCRIPTION:
DSS Export Rating Curves= 0
DSS Export Rating Curve Sorted= 0
DSS Export Volume Flow Curves= 0
DXF OffsetX= 0
DXF OffsetY= 0
DXF ScaleX= 1
DXF ScaleY= 10

--- UNT 148 IN LACR.p01 (plan) ---

Plan Title=Multiple Run
Short Identifier=Multiple
Geom File=g01
Flow File=f01
Subcritical Flow
K Sum by GR= 0
Std Step Tol= 0.01
Critical Tol= 0.01
Num of Std Step Trials= 20
Max Error Tol= 0.3
Flow Tol Ratio= 0.001
Split Flow NTrial= 30
Split Flow Tol= 0.02
Split Flow Ratio= 0.02
Log Output Level= 0
Friction Slope Method= 1
Unsteady Friction Slope Method= 2
Unsteady Bridges Friction Slope Method= 1
Parabolic Critical Depth
Global Vel Dist=  1 , 1 , 1
Global Log Level= 0
CheckData=True
Encroach Param= -1, 0, 0, 0
BEGIN DESCRIPTION:
Multiple Run
END DESCRIPTION:

--- UNT 148 IN LACR.f01 (steady flow) ---

Flow Title=Multiple
Number of Profiles=7
Profile Names=10-year,25-year,50-year,1pct_min,100-year,1pct_plu,500-year
River Rch & RM= UNT 148 IN LACR,Reach-1,1461
     196     272     336     306     414     560     636
Boundary for River Rch & Prof#=UNT 148 IN LACR,Reach-1,1
Up Type=0
Dn Type=3
Dn Slope=0.005
Boundary for River Rch & Prof#=UNT 148 IN LACR,Reach-1,2
Up Type=0
Dn Type=3
Dn Slope=0.005
Boundary for River Rch & Prof#=UNT 148 IN LACR,Reach-1,3
Up Type=0
Dn Type=3
Dn Slope=0.005
Boundary for River Rch & Prof#=UNT 148 IN LACR,Reach-1,4
Up Type=0
Dn Type=3
Dn Slope=0.005
Boundary for River Rch & Prof#=UNT 148 IN LACR,Reach-1,5
Up Type=0
Dn Type=3
Dn Slope=0.005
Boundary for River Rch & Prof#=UNT 148 IN LACR,Reach-1,6
Up Type=0
Dn Type=3
Dn Slope=0.005
Boundary for River Rch & Prof#=UNT 148 IN LACR,Reach-1,7
Up Type=0
Dn Type=3
Dn Slope=0.005

--- UNT 148 IN LACR.g01 (geometry) ---

Geom Title=Existing Conditions
Program Version=4.10

River Reach=UNT 148 IN LACR ,Reach-1
Reach XY= 23
      2213687.72     13200246.85      2213887.72     13200046.85
      2213937.72     13200046.85      2214087.72     13199896.85
      2214087.72     13199846.86      2214137.72     13199796.85
      2214187.72     13199746.85      2214237.72     13199746.85
      2214237.72     13199696.86      2214287.72     13199696.86
      2214337.72     13199696.86      2214387.72     13199646.85
      2214437.72     13199596.85      2214437.72     13199546.86
      2214487.72     13199496.85      2214537.72     13199446.85
      2214587.72     13199396.85      2214637.72     13199396.85
      2214687.72     13199346.85      2214737.72     13199296.85
      2214787.72     13199246.85      2214737.72     13199196.86
      2214787.72     13199146.85

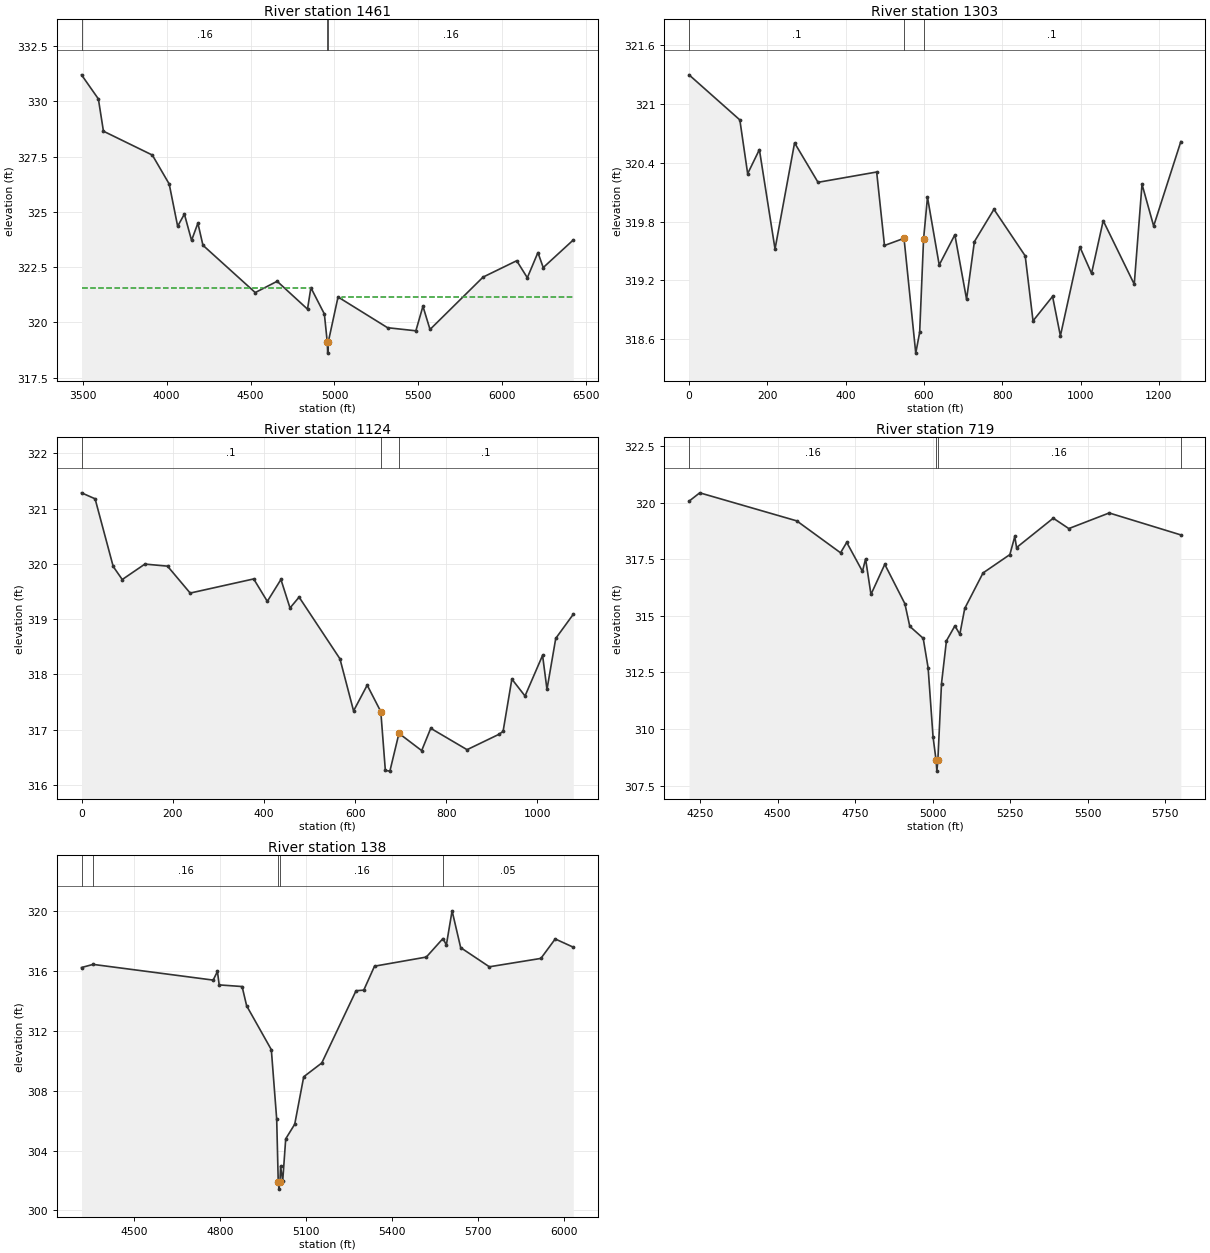
Type RM Length L Ch R = 1 ,1461    ,168,168,168
BEGIN DESCRIPTION:
UNT 148 IN LACR 3.0
END DESCRIPTION:
XS GIS Cut Line= 3
      2214037.72     13201546.87      2213887.72     13200046.85
      2212537.74     13199596.86
#Sta/Elev= 30
  3492.5   331.2    3593  330.11  3623.2  328.65  3914.6  327.57  4015.1  326.26
  4065.4  324.35  4105.6   324.9  4148.3  323.71    4186  324.49  4216.1  323.49
  4527.7  321.35  4658.3  321.86  4839.2   320.6  4859.3  321.57  4939.7  320.38
  4956.8  319.11  4959.6  318.61  4962.8  319.11    4964  319.15  5021.1  321.15
  5316.2  319.76  5484.9  319.62    5527  320.73  5569.2  319.68  5885.4  322.05
  6085.7  322.79    6149  322.02  6212.2  323.16  6243.8  322.48    6423  323.73
#Mann= 3 ,-1 , 0
  3492.5     .16       0  4956.8     .07       0    4964     .16       0
#XS Ineff= 2 , 0
       0 4861.36  321.57 5042.33       0  321.17
Permanent Ineff=
       T       T
Bank Sta=4956.8,4962.8
XS Rating Curve= 0 ,0
Exp/Cntr=0.3,0.1

Type RM Length L Ch R = 1 ,1303    ,180,180,180
XS GIS Cut Line= 3
     2214412.858    13200382.591     2213724.924    13199677.296
     2213482.533      13199573.4
#Sta/Elev= 30
       0321.2928129.7798320.8339149.7459320.2868179.6951320.5319219.6273319.5202
269.5427320.6003 329.441 320.199 479.187320.3039499.1531319.5562  549.06319.6292
579.0176318.4609589.0006318.6725  598.98319.6215608.9667320.0478 638.916319.3579
678.8482319.6652708.7974319.0091728.7635319.5955778.6788319.9241858.5433319.4502
878.5094 318.789928.4247 319.038948.3909318.6365998.2354319.54041027.972 319.272
1057.709319.80861137.007319.16191156.832320.17941186.569319.75421255.955320.6135
#Mann= 3 , 0 , 0
       0      .1       0  549.06    .035       0  598.98      .1       0
Bank Sta=549.06,598.98
XS Rating Curve= 0 ,0
Exp/Cntr=0.3,0.1

Type RM Length L Ch R = 1 ,1124    ,396,396,396
XS GIS Cut Line= 4
     2214458.431     13200365.23     2214367.285    13200115.664
     2213922.406    13199657.764     2213746.625    13199653.424
#Sta/Elev= 30
       0321.286129.78954 321.17869.50893319.952789.36863319.7163139.0179 319.996
188.6671319.9585238.3163319.4712377.6245319.7272407.4932319.3205437.3619319.7174
457.2744319.2013477.1869319.3982 566.793318.2805596.6617317.3376626.5305317.8039
  656.39317.3249666.3554316.2603676.3116316.2474  696.22316.9313746.0052316.6189
765.9177317.0226845.5676316.6356914.9304316.9117924.5557316.9668943.8063 317.914
972.6822317.60751011.183318.34411020.809317.72681040.059318.6506 1078.56319.0876
#Mann= 3 , 0 , 0
       0      .1       0  656.39    .035       0  696.22      .1       0
Bank Sta=656.39,696.22
XS Rating Curve= 0 ,0
Exp/Cntr=0.3,0.1

Type RM Length L Ch R = 1 ,719     ,581,581,581
BEGIN DESCRIPTION:
UNT 148 IN LACR 2.0
END DESCRIPTION:
XS GIS Cut Line= 4
      2214640.54     13200321.16      2214561.32      13199726.8
      2214156.47     13199496.04      2213637.01     13199468.41
#Sta/Elev= 30
  4214.5  320.07  4249.1  320.44  4561.9   319.2  4703.1  317.79    4723  318.25
  4773.7  316.97  4783.8  317.52  4801.2  315.95  4845.7  317.28  4910.5  315.54
  4926.3  314.54  4969.6  314.01  4985.4  312.71  5001.3  309.66  5010.9  308.64
  5013.7  308.14  5016.9  308.64  5028.6  312.01  5044.5   313.9  5071.8  314.56
  5087.7  314.19  5103.5  315.33  5162.6   316.9    5249  317.71  5264.9  318.51
  5270.6  318.02    5389  319.32  5439.1  318.86  5569.3  319.55  5800.3  318.58
#Mann= 4 ,-1 , 0
  4214.5     .16       0  5010.9     .07       0  5016.9     .16       0
  5800.3     .05       0
Bank Sta=5010.9,5016.9
XS Rating Curve= 0 ,0
Exp/Cntr=0.3,0.1

Type RM Length L Ch R = 1 ,138     ,0,0,0
BEGIN DESCRIPTION:
UNT 148 IN LACR 1.0
END DESCRIPTION:
XS GIS Cut Line= 4
      2215225.91     13199739.08      2214907.35     13199283.24
      2214330.08     13199100.21      2213774.57      13199114.1
#Sta/Elev= 30
    4316  316.23  4356.5  316.44  4775.8  315.39  4790.7  315.97  4796.8  315.07
  4876.8  314.96  4892.7  313.67  4978.9  310.74  4997.6   306.1    5003  301.92
  5005.7  301.42    5009  301.92  5011.2  302.95  5018.6  301.96  5029.1  304.78
  5060.6  305.76    5092  308.93    5155  309.85  5274.7  314.68  5301.7  314.72
  5339.2  316.32  5520.1  316.93  5578.3  318.17  5590.1  317.74  5610.1  320.02
  5640.1  317.56  5740.2  316.28  5920.2  316.84  5970.2  318.14  6033.4  317.59
#Mann= 5 ,-1 , 0
    4316     .05       0  4356.5     .16       0    5003     .07       0
    5009     .16       0  5578.3     .05       0
Bank Sta=5003,5009
XS Rating Curve= 0 ,0
Exp/Cntr=0.3,0.1

Chan Stop Cuts=-1
Use User Specified Reach Order=0
Composite Channel Slope=5