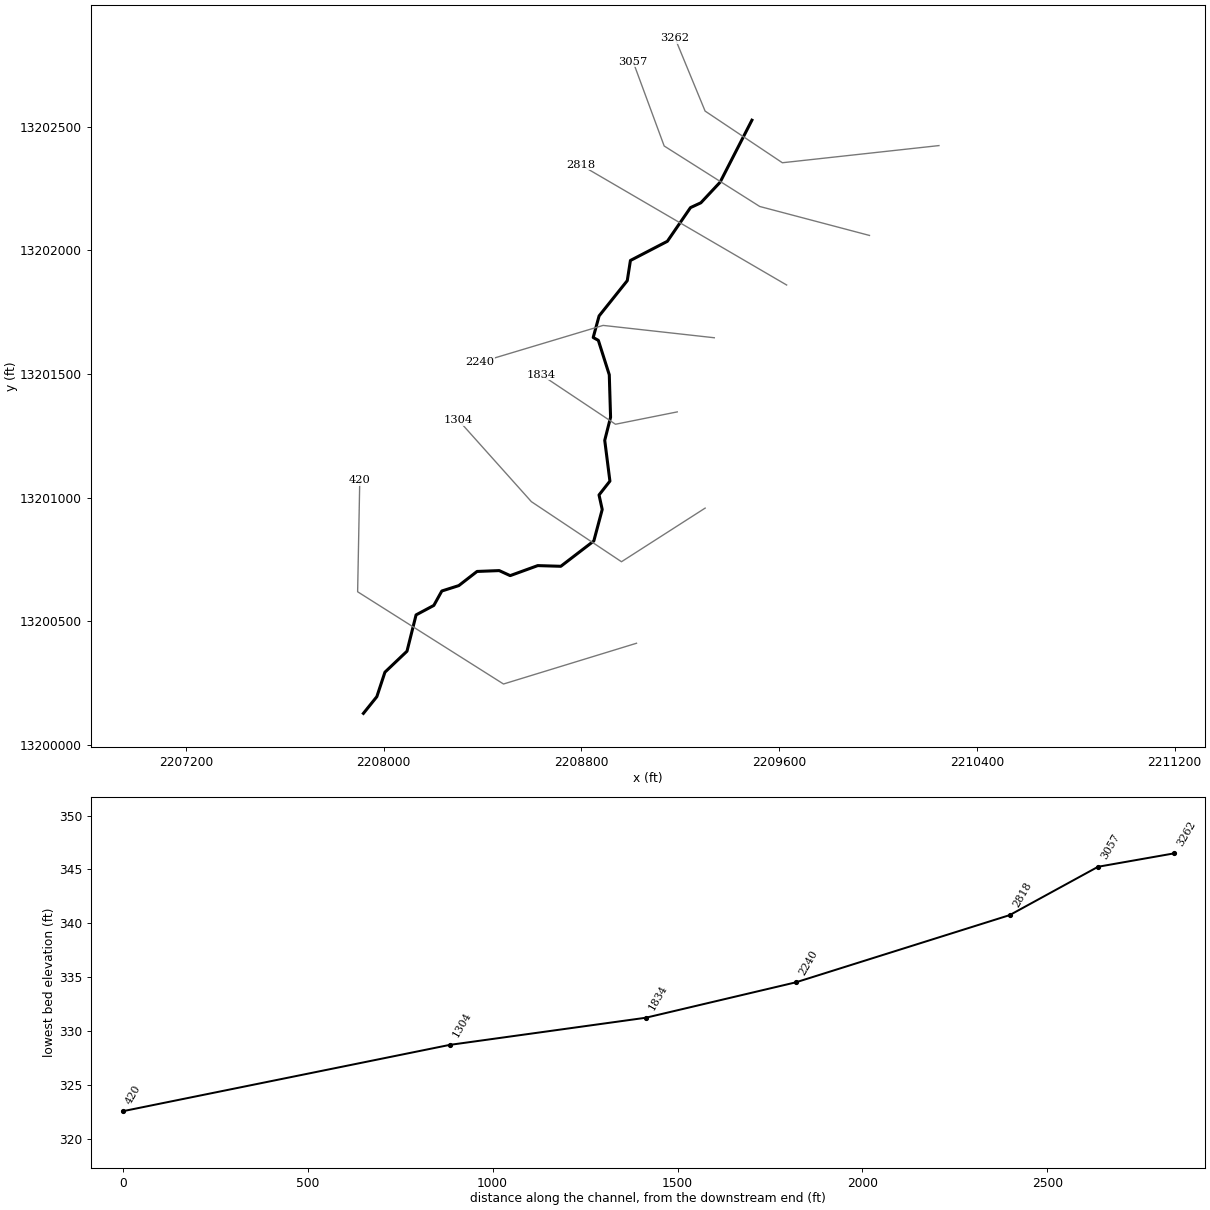
--- UNT 149 IN LACR.prj (project) ---

Proj Title=UNT 149 IN LACR Base Level Engineering
Current Plan=p01
Default Exp/Contr=0.3,0.1
English Units
Geom File=g01
Geom File=g02
Flow File=f01
Plan File=p01
Y Axis Title=Elevation
X Axis Title(PF)=Main Channel Distance
X Axis Title(XS)=Station
BEGIN DESCRIPTION:
UNT 149 IN LACR
END DESCRIPTION:
DSS Export Rating Curves= 0
DSS Export Rating Curve Sorted= 0
DSS Export Volume Flow Curves= 0
DXF OffsetX= 0
DXF OffsetY= 0
DXF ScaleX= 1
DXF ScaleY= 10

--- UNT 149 IN LACR.p01 (plan) ---

Plan Title=Multiple Run
Short Identifier=Multiple
Geom File=g01
Flow File=f01
Subcritical Flow
K Sum by GR= 0
Std Step Tol= 0.01
Critical Tol= 0.01
Num of Std Step Trials= 20
Max Error Tol= 0.3
Flow Tol Ratio= 0.001
Split Flow NTrial= 30
Split Flow Tol= 0.02
Split Flow Ratio= 0.02
Log Output Level= 0
Friction Slope Method= 1
Unsteady Friction Slope Method= 2
Unsteady Bridges Friction Slope Method= 1
Parabolic Critical Depth
Global Vel Dist=  1 , 1 , 1
Global Log Level= 0
CheckData=True
Encroach Param= -1, 0, 0, 0
BEGIN DESCRIPTION:
Multiple Run
END DESCRIPTION:

--- UNT 149 IN LACR.f01 (steady flow) ---

Flow Title=Multiple
Number of Profiles=7
Profile Names=10-year,25-year,50-year,1pct_min,100-year,1pct_plu,500-year
River Rch & RM= UNT 149 IN LACR,Reach-1,3262
     157     216     264     238     322     436     488
Boundary for River Rch & Prof#=UNT 149 IN LACR,Reach-1,1
Up Type=0
Dn Type=3
Dn Slope=0.005
Boundary for River Rch & Prof#=UNT 149 IN LACR,Reach-1,2
Up Type=0
Dn Type=3
Dn Slope=0.005
Boundary for River Rch & Prof#=UNT 149 IN LACR,Reach-1,3
Up Type=0
Dn Type=3
Dn Slope=0.005
Boundary for River Rch & Prof#=UNT 149 IN LACR,Reach-1,4
Up Type=0
Dn Type=3
Dn Slope=0.005
Boundary for River Rch & Prof#=UNT 149 IN LACR,Reach-1,5
Up Type=0
Dn Type=3
Dn Slope=0.005
Boundary for River Rch & Prof#=UNT 149 IN LACR,Reach-1,6
Up Type=0
Dn Type=3
Dn Slope=0.005
Boundary for River Rch & Prof#=UNT 149 IN LACR,Reach-1,7
Up Type=0
Dn Type=3
Dn Slope=0.005

--- UNT 149 IN LACR.g01 (geometry) ---

Geom Title=Existing Conditions
Program Version=4.10

River Reach=UNT 149 IN LACR ,Reach-1
Reach XY= 30
      2209489.87     13202527.27      2209360.92     13202275.98
      2209283.22     13202192.97      2209241.32     13202173.53
      2209147.71      13202037.2      2208998.22     13201959.55
      2208985.46     13201877.95      2208871.45     13201735.21
       2208847.6     13201647.87      2208868.43      13201636.3
       2208912.7     13201496.97      2208917.91      13201325.1
      2208894.28     13201231.72      2208915.22     13201066.75
      2208871.21     13201010.71      2208884.09     13200951.81
       2208850.1     13200824.47      2208716.58     13200722.05
      2208623.27     13200724.83       2208511.6     13200684.26
       2208467.3     13200704.64      2208377.57      13200701.2
      2208303.71     13200643.89      2208235.03     13200622.06
       2208202.7     13200563.75      2208130.85     13200525.32
       2208094.1     13200378.44       2208004.8     13200293.49
      2207972.06     13200194.49      2207917.72     13200126.85

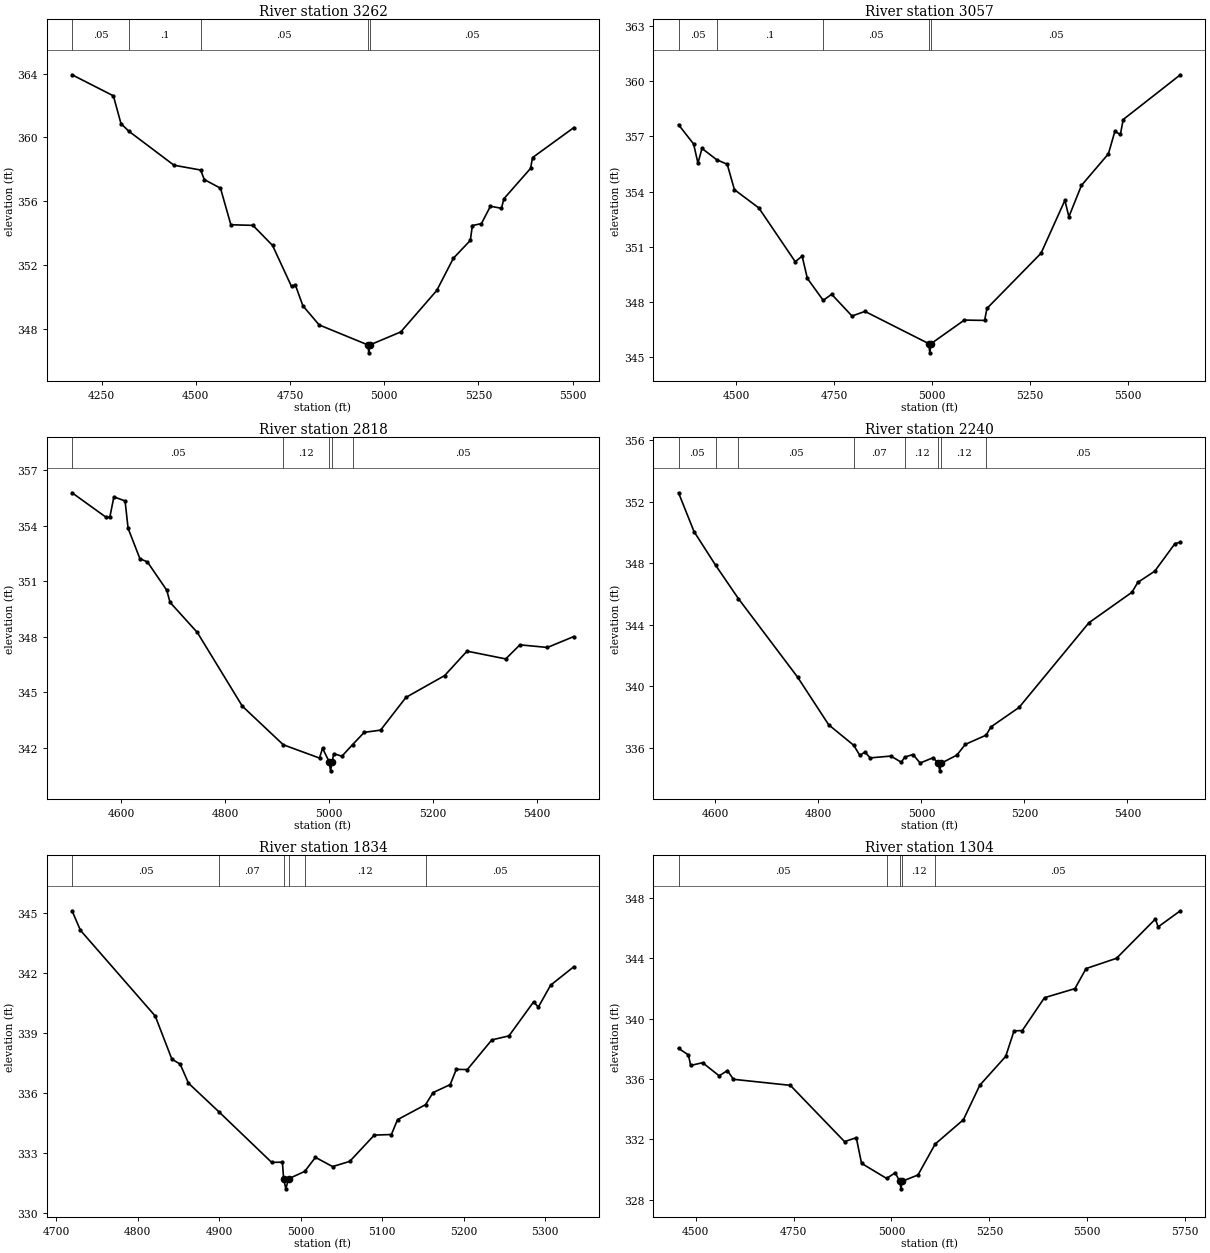
Type RM Length L Ch R = 1 ,3262    ,205,205,205
BEGIN DESCRIPTION:
UNT 149 IN LACR 5.0
END DESCRIPTION:
XS GIS Cut Line= 4
      2210246.76     13202424.52      2209613.07     13202355.07
      2209300.44     13202564.13      2209179.05     13202858.52
#Sta/Elev= 30
  4171.6  363.92  4281.3   362.6  4301.4  360.86  4322.4  360.38  4442.2  358.25
  4512.8  357.95  4522.7  357.35  4565.6  356.81  4593.1  354.52  4651.7  354.48
  4703.8  353.22  4754.1  350.65  4764.2  350.75  4784.3  349.44  4827.5  348.24
  4956.5  346.99  4959.3  346.49  4962.5  346.99  5044.1   347.8  5139.7   350.4
  5183.8  352.42  5228.8  353.54  5234.2  354.47  5258.2  354.59  5282.1  355.68
  5311.4  355.55  5317.9  356.15  5388.6  358.05    5394  358.73  5503.6  360.61
#Mann= 5 ,-1 , 0
  4171.6     .05       0  4322.4      .1       0  4512.8     .05       0
  4956.5     .03       0  4962.5     .05       0
Bank Sta=4956.5,4962.5
XS Rating Curve= 0 ,0
Exp/Cntr=0.3,0.1

Type RM Length L Ch R = 1 ,3057    ,239,239,239
BEGIN DESCRIPTION:
Mapping XS 47c0c984
END DESCRIPTION:
XS GIS Cut Line= 4
      2209965.59     13202060.89      2209521.53     13202178.09
      2209134.82     13202422.88      2209009.15      13202763.6
#Sta/Elev= 30
  4352.7  357.64  4391.2  356.59  4402.2  355.55  4412.5  356.35  4449.9  355.74
  4476.9  355.49  4495.3  354.11  4557.5  353.12  4650.4   350.2    4668   350.5
  4681.4  349.29  4721.8   348.1  4743.3  348.43  4795.2  347.25  4828.3   347.5
    4991  345.75  4993.7  345.25    4997  345.75  5081.8  347.03  5133.5  347.01
  5139.4  347.66  5277.5  350.66  5338.3  353.53  5348.5  352.64  5380.5  354.34
  5449.4  356.06  5465.7  357.27  5479.9  357.11  5487.1  357.92  5632.8  360.35
#Mann= 5 ,-1 , 0
  4352.7     .05       0  4449.9      .1       0  4721.8     .05       0
    4991     .03       0    4997     .05       0
Bank Sta=4991,4997
XS Rating Curve= 0 ,0
Exp/Cntr=0.3,0.1

Type RM Length L Ch R = 1 ,2818    ,578,578,578
BEGIN DESCRIPTION:
UNT 149 IN LACR 4.0
END DESCRIPTION:
XS GIS Cut Line= 2
      2209630.39      13201860.3       2208797.1     13202346.39
#Sta/Elev= 30
  4505.8  355.79  4570.5  354.48  4578.3  354.46  4586.2  355.57  4607.7  355.35
  4613.5  353.87  4636.2  352.23  4650.7  352.05  4687.9  350.52  4694.1  349.87
  4746.6  348.24    4833  344.26  4911.8  342.17  4981.5  341.45  4987.3  341.98
    5000  341.26  5002.7  340.76    5006  341.26  5008.8  341.69  5024.5  341.55
  5045.2  342.18  5067.5  342.84  5098.9  342.96  5147.7  344.73  5222.1  345.91
  5265.1  347.23  5339.5  346.81  5366.8  347.57  5419.7  347.43  5470.5  348.02
#Mann= 5 ,-1 , 0
  4505.8     .05       0  4911.8     .12       0    5000     .07       0
    5006     .12       0  5045.2     .05       0
Bank Sta=5000,5006
XS Rating Curve= 0 ,0
Exp/Cntr=0.3,0.1

Type RM Length L Ch R = 1 ,2240    ,406,406,406
BEGIN DESCRIPTION:
UNT 149 IN LACR 3.0
END DESCRIPTION:
XS GIS Cut Line= 3
      2209337.67     13201646.86      2208887.72     13201696.85
      2208387.75     13201546.87
#Sta/Elev= 30
  4528.2  352.58  4558.3  350.06  4600.3  347.87  4644.4  345.71  4759.6   340.6
  4819.9  337.51  4868.5  336.18  4880.3  335.53  4890.4  335.74  4900.4  335.36
  4940.7  335.48  4960.8  335.08  4967.6  335.41  4983.5  335.58  4997.5  335.03
  5022.7  335.37  5032.7  335.02  5035.5  334.52  5038.7  335.02  5068.8  335.54
  5085.3  336.24  5125.8  336.84  5134.9  337.37  5189.7  338.64  5325.4  344.14
    5409  346.12  5420.3  346.76  5453.3  347.49  5492.5  349.28  5502.9  349.37
#Mann= 8 ,-1 , 0
  4528.2     .05       0  4600.3     .07       0  4644.4     .05       0
  4868.5     .07       0  4967.6     .12       0  5032.7     .07       0
  5038.7     .12       0  5125.8     .05       0
Bank Sta=5032.7,5038.7
XS Rating Curve= 0 ,0
Exp/Cntr=0.3,0.1

Type RM Length L Ch R = 1 ,1834    ,530,530,530
BEGIN DESCRIPTION:
UNT 149 IN LACR 2.0
END DESCRIPTION:
XS GIS Cut Line= 3
      2209187.75     13201346.86      2208937.72     13201296.85
      2208637.75     13201496.83
#Sta/Elev= 30
  4719.7   345.1  4729.9  344.13  4821.7  339.85  4842.1   337.7  4852.3  337.45
  4862.5   336.5  4900.4  335.05  4964.5  332.55  4977.7  332.56  4979.2  331.73
  4981.9  331.23  4985.2  331.73  5005.1   332.1  5018.2   332.8  5039.3  332.34
  5060.3   332.6  5090.4  333.91  5111.4  333.94  5118.9  334.68  5153.3  335.43
  5162.5  336.03  5183.5  336.43    5191  337.19  5204.5  337.18  5234.6  338.66
  5255.6  338.86  5285.7  340.55  5291.7   340.3  5306.7  341.39  5335.2  342.31
#Mann= 6 ,-1 , 0
  4719.7     .05       0  4900.4     .07       0  4979.2     .07       0
  4985.2     .07       0  5005.1     .12       0  5153.3     .05       0
Bank Sta=4979.2,4985.2
XS Rating Curve= 0 ,0
Exp/Cntr=0.3,0.1

Type RM Length L Ch R = 1 ,1304    ,884,884,884
BEGIN DESCRIPTION:
Mapping XS da5add7d
END DESCRIPTION:
XS GIS Cut Line= 4
      2209300.59     13200957.51      2208962.03     13200740.49
      2208597.44     13200983.54       2208303.2      13201312.4
#Sta/Elev= 30
  4456.1  338.02  4481.2  337.59  4487.2  336.89  4517.6  337.07  4559.9   336.2
    4581  336.55  4596.2  335.97  4741.6  335.57  4880.1  331.84  4910.1   332.1
  4923.5   330.4  4987.5   329.4  5009.3  329.77  5021.3  329.21  5024.1  328.71
  5027.3  329.21  5067.7  329.63  5111.6  331.68  5183.6  333.29  5225.6  335.58
  5291.7  337.49    5313  339.18    5334   339.2  5390.8  341.38  5468.5  341.98
    5497  343.31  5574.7  343.99  5674.2   346.6  5680.9  346.07  5737.7  347.14
#Mann= 5 ,-1 , 0
  4456.1     .05       0  4987.5     .12       0  5021.3     .07       0
  5027.3     .12       0  5111.6     .05       0
Bank Sta=5021.3,5027.3
XS Rating Curve= 0 ,0
Exp/Cntr=0.3,0.1

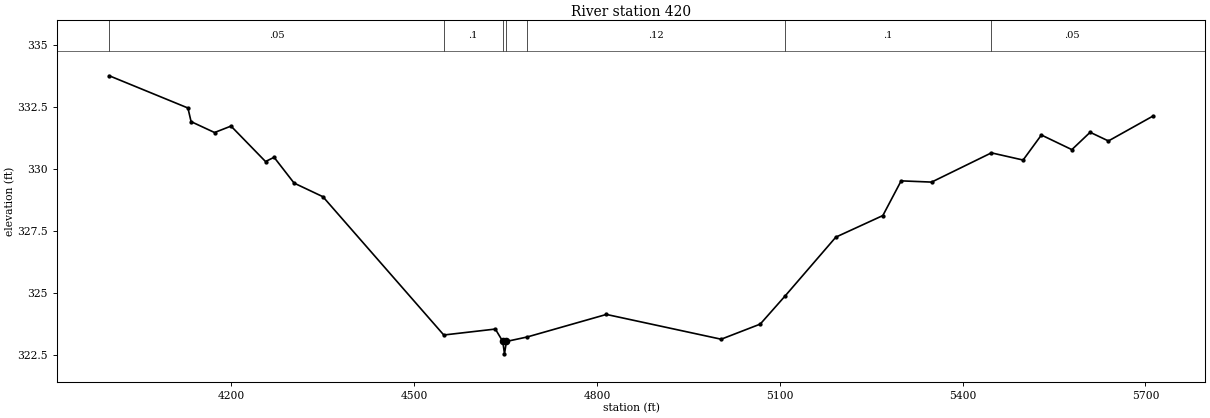
Type RM Length L Ch R = 1 ,420     ,0,0,0
BEGIN DESCRIPTION:
UNT 149 IN LACR 1.0
END DESCRIPTION:
XS GIS Cut Line= 4
      2209022.81     13200410.63       2208484.6      13200245.7
      2207894.32     13200618.96        2207903.     13201070.36
#Sta/Elev= 30
  3999.9  333.77  4128.9  332.47  4134.1  331.92  4172.6  331.48  4199.6  331.74
  4256.2  330.31  4270.3  330.48  4303.1  329.44  4350.4  328.89  4548.7  323.31
  4633.3  323.55  4645.5  323.05  4648.3  322.55  4651.5  323.05  4685.5  323.23
  4815.5  324.14  5003.8  323.14  5067.9  323.75  5108.9  324.89    5192  327.26
  5269.1  328.13  5299.1  329.53  5349.1  329.48  5447.2  330.66  5499.2  330.37
  5529.2  331.38  5579.2  330.79  5609.2  331.49  5639.2  331.14  5712.7  332.15
#Mann= 7 ,-1 , 0
  3999.9     .05       0  4548.7      .1       0  4645.5     .07       0
  4651.5      .1       0  4685.5     .12       0  5108.9      .1       0
  5447.2     .05       0
Bank Sta=4645.5,4651.5
XS Rating Curve= 0 ,0
Exp/Cntr=0.3,0.1

Chan Stop Cuts=-1
Use User Specified Reach Order=0
Composite Channel Slope=5

--- UNT 149 IN LACR.g02 (geometry) ---

Geom Title=Dummy
Program Version=4.10

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
River Reach=UNT 149 IN LACR ,Reach-1
Reach XY= 30
      2209474.07      13202533.2      2209437.72     13202496.86
      2209437.72      13202402.5      2209433.25     13202392.38
      2209187.72     13202146.86      2209187.72     13202060.91
      2209174.94     13202046.86      2209137.72     13202046.85
      2208887.72     13201796.85      2208887.72     13201696.85
      2208837.72     13201646.86      2208887.72     13201596.85
      2208887.72     13201546.85      2208937.72     13201496.86
      2208937.72     13201296.85      2208887.72     13201246.85
      2208887.72     13200846.86      2208737.72     13200696.86
      2208687.72     13200746.85      2208637.72     13200746.85
      2208587.72     13200696.86      2208387.72     13200696.86
      2208337.72     13200646.85      2208287.72     13200646.85
      2208087.72     13200446.85      2208087.72     13200396.85
      2207987.72     13200296.85      2207987.72     13200196.86
      2207937.72     13200146.85      2207937.72     13200096.85

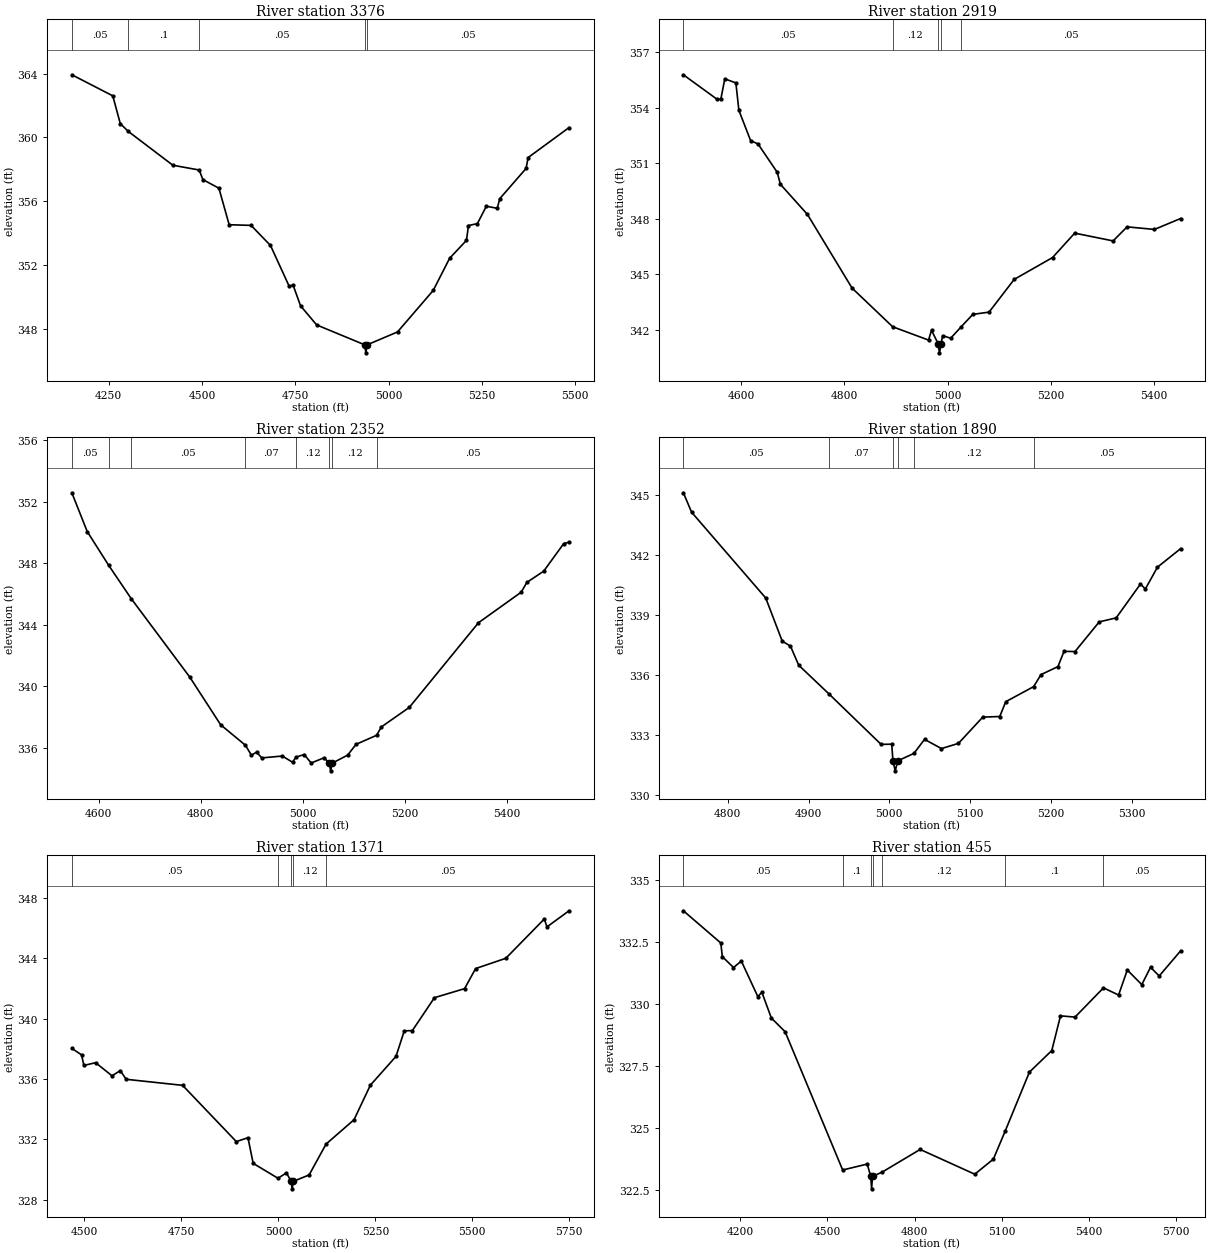
Type RM Length L Ch R = 1 ,3376    ,457,457,457
BEGIN DESCRIPTION:
UNT 149 IN LACR 5.0
END DESCRIPTION:
XS GIS Cut Line= 4
      2210246.73     13202424.51      2209613.07     13202355.07
      2209300.44     13202564.13      2209179.04     13202858.54
#Sta/Elev= 30
  4151.6  363.92  4261.3   362.6  4281.4  360.86  4302.3  360.38  4422.2  358.25
  4492.8  357.95  4502.7  357.35  4545.6  356.81  4573.1  354.52  4631.7  354.48
  4683.8  353.22  4734.1  350.65  4744.1  350.75  4764.3  349.44  4807.5  348.24
  4936.5  346.99  4939.3  346.49  4942.5  346.99  5024.1   347.8  5119.7   350.4
  5163.8  352.42  5208.8  353.54  5214.2  354.47  5238.1  354.59  5262.1  355.68
  5291.4  355.55  5297.9  356.15  5368.6  358.05    5374  358.73  5483.6  360.61
#Mann= 5 ,-1 , 0
  4151.6     .05       0  4302.3      .1       0  4492.8     .05       0
  4936.5     .03       0  4942.5     .05       0
Bank Sta=4936.5,4942.5
XS Rating Curve= 0 ,0
Exp/Cntr=0.3,0.1

Type RM Length L Ch R = 1 ,2919    ,567,567,567
BEGIN DESCRIPTION:
UNT 149 IN LACR 4.0
END DESCRIPTION:
XS GIS Cut Line= 2
      2209630.41     13201860.29      2208797.12     13202346.38
#Sta/Elev= 30
  4487.5  355.79  4552.2  354.48  4560.1  354.46  4567.9  355.57  4589.4  355.35
  4595.2  353.87    4618  352.23  4632.4  352.05  4669.6  350.52  4675.8  349.87
  4728.3  348.24  4814.8  344.26  4893.6  342.17  4963.2  341.45    4969  341.98
  4981.7  341.26  4984.4  340.76  4987.7  341.26  4990.5  341.69  5006.2  341.55
  5026.9  342.18  5049.2  342.84  5080.6  342.96  5129.4  344.73  5203.8  345.91
  5246.8  347.23  5321.3  346.81  5348.5  347.57  5401.5  347.43  5452.2  348.02
#Mann= 5 ,-1 , 0
  4487.5     .05       0  4893.6     .12       0  4981.7     .07       0
  4987.7     .12       0  5026.9     .05       0
Bank Sta=4981.7,4987.7
XS Rating Curve= 0 ,0
Exp/Cntr=0.3,0.1

Type RM Length L Ch R = 1 ,2352    ,462,462,462
BEGIN DESCRIPTION:
UNT 149 IN LACR 3.0
END DESCRIPTION:
XS GIS Cut Line= 3
      2209337.75     13201646.85      2208887.72     13201696.85
      2208387.74     13201546.86
#Sta/Elev= 30
  4547.2  352.58  4577.4  350.06  4619.4  347.87  4663.5  345.71  4778.6   340.6
    4839  337.51  4887.6  336.18  4899.4  335.53  4909.4  335.74  4919.5  335.36
  4959.8  335.48  4979.9  335.08  4986.7  335.41  5002.6  335.58  5016.5  335.03
  5041.8  335.37  5051.8  335.02  5054.6  334.52  5057.8  335.02  5087.9  335.54
  5104.4  336.24  5144.8  336.83    5154  337.37  5208.8  338.64  5344.5  344.14
  5428.1  346.12  5439.4  346.76  5472.4  347.49  5511.6  349.28    5522  349.37
#Mann= 8 ,-1 , 0
  4547.2     .05       0  4619.4     .07       0  4663.5     .05       0
  4887.6     .07       0  4986.7     .12       0  5051.8     .07       0
  5057.8     .12       0  5144.8     .05       0
Bank Sta=5051.8,5057.8
XS Rating Curve= 0 ,0
Exp/Cntr=0.3,0.1

Type RM Length L Ch R = 1 ,1890    ,519,519,519
BEGIN DESCRIPTION:
UNT 149 IN LACR 2.0
END DESCRIPTION:
XS GIS Cut Line= 3
      2209187.77     13201346.86      2208937.72     13201296.85
      2208637.68     13201496.88
#Sta/Elev= 30
    4745   345.1  4755.2  344.13    4847  339.85  4867.4   337.7  4877.6  337.45
  4887.8   336.5  4925.7  335.05  4989.8  332.55    5003  332.56  5004.5  331.73
  5007.3  331.23  5010.5  331.73  5030.5   332.1  5043.6   332.8  5064.6  332.34
  5085.6   332.6  5115.7  333.91  5136.7  333.94  5144.2  334.68  5178.7  335.43
  5187.8  336.03  5208.8  336.43  5216.3  337.19  5229.9  337.18  5259.9  338.66
  5280.9  338.86    5311  340.55    5317   340.3    5332  341.39  5360.6  342.31
#Mann= 6 ,-1 , 0
    4745     .05       0  4925.7     .07       0  5004.5     .07       0
  5010.5     .07       0  5030.5     .12       0  5178.7     .05       0
Bank Sta=5004.5,5010.5
XS Rating Curve= 0 ,0
Exp/Cntr=0.3,0.1

Type RM Length L Ch R = 1 ,1371    ,916,916,916
BEGIN DESCRIPTION:
Mapping XS da5add7d
END DESCRIPTION:
XS GIS Cut Line= 4
      2209300.56     13200957.49      2208962.03     13200740.49
      2208597.44     13200983.54      2208303.18     13201312.43
#Sta/Elev= 30
  4467.6  338.02  4492.7  337.59  4498.6  336.89    4529  337.07  4571.3   336.2
  4592.5  336.55  4607.7  335.97  4753.1  335.57  4891.6  331.84  4921.6   332.1
    4935   330.4    4999  329.41  5020.8  329.77  5032.8  329.21  5035.5  328.71
  5038.8  329.21  5079.2  329.63    5123  331.68    5195  333.29  5237.1  335.58
  5303.2  337.49  5324.5  339.18  5345.4   339.2  5402.3  341.38    5480  341.98
  5508.4  343.31  5586.2  343.99  5685.6   346.6  5692.3  346.07  5749.2  347.14
#Mann= 5 ,-1 , 0
  4467.6     .05       0    4999     .12       0  5032.8     .07       0
  5038.8     .12       0    5123     .05       0
Bank Sta=5032.8,5038.8
XS Rating Curve= 0 ,0
Exp/Cntr=0.3,0.1

Type RM Length L Ch R = 1 ,455     ,0,0,0
BEGIN DESCRIPTION:
UNT 149 IN LACR 1.0
END DESCRIPTION:
XS GIS Cut Line= 4
      2209022.82     13200410.64       2208484.6      13200245.7
      2207894.32     13200618.96        2207903.     13201070.35
#Sta/Elev= 30
  4003.6  333.77  4132.6  332.47  4137.8  331.92  4176.3  331.48  4203.3  331.74
    4260  330.31  4274.1  330.48  4306.8  329.44  4354.1  328.89  4552.4  323.31
    4637  323.55  4649.2  323.05    4652  322.55  4655.2  323.05  4689.2  323.23
  4819.3  324.14  5007.5  323.14  5071.6  323.75  5112.6  324.89  5195.7  327.26
  5272.8  328.13  5302.8  329.53  5352.8  329.48  5450.9  330.66  5502.9  330.37
  5532.9  331.38  5582.9  330.79  5612.9  331.49  5642.9  331.14  5716.4  332.15
#Mann= 7 ,-1 , 0
  4003.6     .05       0  4552.4      .1       0  4649.2     .07       0
  4655.2      .1       0  4689.2     .12       0  5112.6      .1       0
  5450.9     .05       0
Bank Sta=4649.2,4655.2
XS Rating Curve= 0 ,0
Exp/Cntr=0.3,0.1