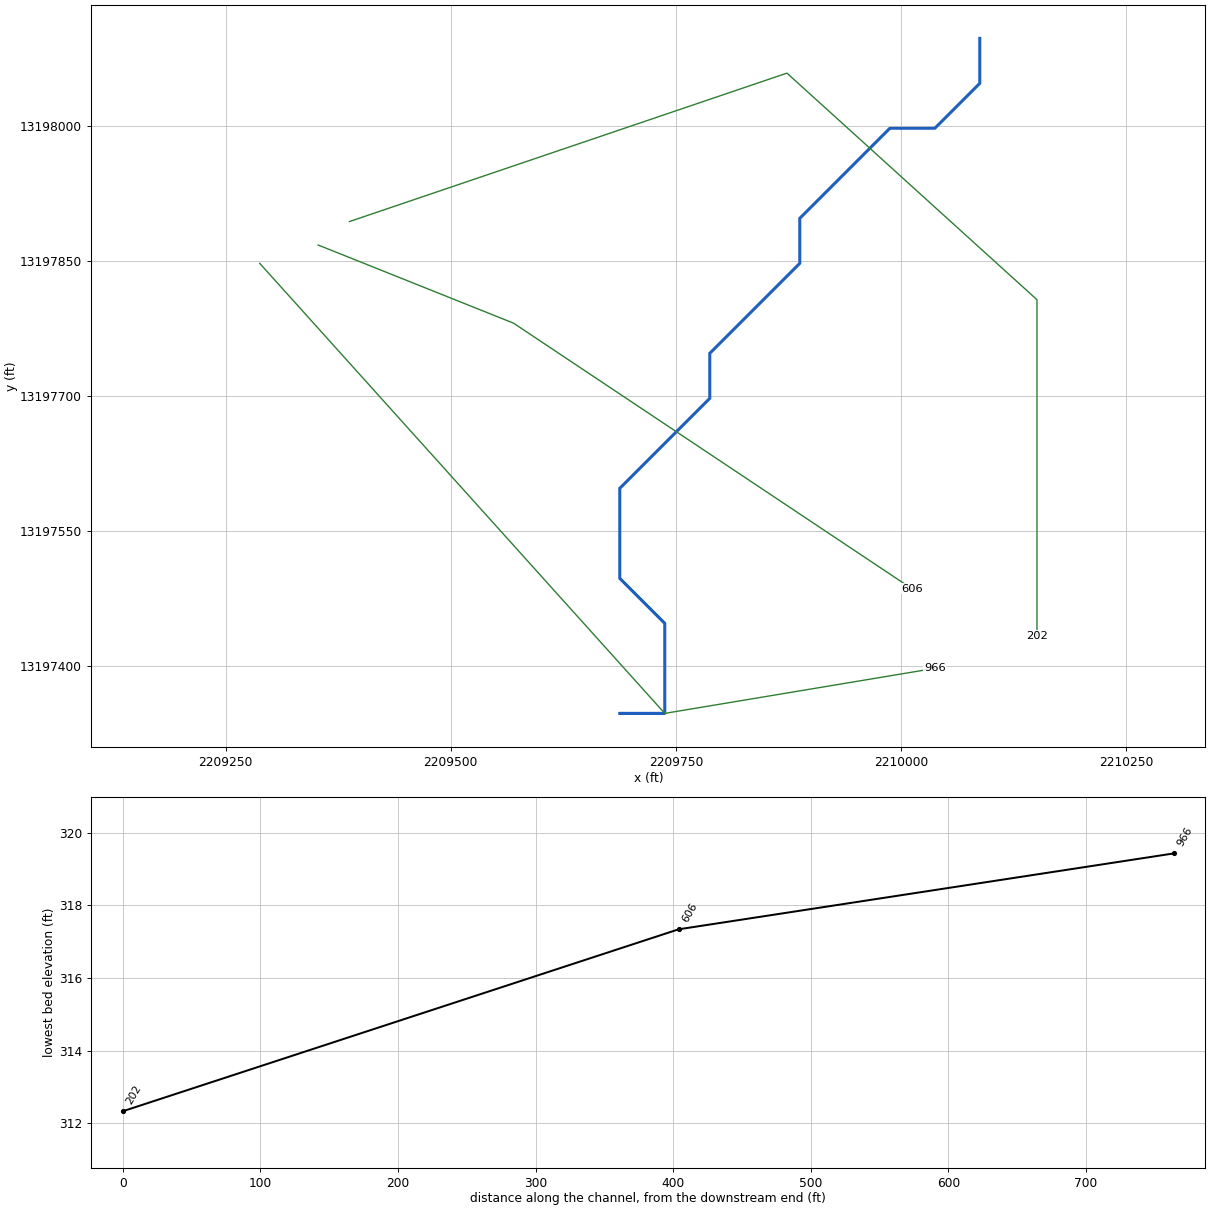
--- UNT 151 IN LACR.prj (project) ---

Proj Title=UNT 151 IN LACR Base Level Engineering
Current Plan=p01
Default Exp/Contr=0.3,0.1
English Units
Geom File=g01
Flow File=f01
Plan File=p01
Y Axis Title=Elevation
X Axis Title(PF)=Main Channel Distance
X Axis Title(XS)=Station
BEGIN DESCRIPTION:
UNT 151 IN LACR
END DESCRIPTION:
DSS Export Rating Curves= 0
DSS Export Rating Curve Sorted= 0
DSS Export Volume Flow Curves= 0
DXF OffsetX= 0
DXF OffsetY= 0
DXF ScaleX= 1
DXF ScaleY= 10

--- UNT 151 IN LACR.p01 (plan) ---

Plan Title=Multiple Run
Short Identifier=Multiple
Geom File=g01
Flow File=f01
Subcritical Flow
K Sum by GR= 0
Std Step Tol= 0.01
Critical Tol= 0.01
Num of Std Step Trials= 20
Max Error Tol= 0.3
Flow Tol Ratio= 0.001
Split Flow NTrial= 30
Split Flow Tol= 0.02
Split Flow Ratio= 0.02
Log Output Level= 0
Friction Slope Method= 1
Unsteady Friction Slope Method= 2
Unsteady Bridges Friction Slope Method= 1
Parabolic Critical Depth
Global Vel Dist=  1 , 1 , 1
Global Log Level= 0
CheckData=True
Encroach Param= -1, 0, 0, 0
BEGIN DESCRIPTION:
Multiple Run
END DESCRIPTION:

--- UNT 151 IN LACR.f01 (steady flow) ---

Flow Title=Multiple
Number of Profiles=7
Profile Names=10-year,25-year,50-year,1pct_min,100-year,1pct_plu,500-year
River Rch & RM= UNT 151 IN LACR,Reach-1,966
      62      80      95      83     112     151     157
Boundary for River Rch & Prof#=UNT 151 IN LACR,Reach-1,1
Up Type=0
Dn Type=3
Dn Slope=0.005
Boundary for River Rch & Prof#=UNT 151 IN LACR,Reach-1,2
Up Type=0
Dn Type=3
Dn Slope=0.005
Boundary for River Rch & Prof#=UNT 151 IN LACR,Reach-1,3
Up Type=0
Dn Type=3
Dn Slope=0.005
Boundary for River Rch & Prof#=UNT 151 IN LACR,Reach-1,4
Up Type=0
Dn Type=3
Dn Slope=0.005
Boundary for River Rch & Prof#=UNT 151 IN LACR,Reach-1,5
Up Type=0
Dn Type=3
Dn Slope=0.005
Boundary for River Rch & Prof#=UNT 151 IN LACR,Reach-1,6
Up Type=0
Dn Type=3
Dn Slope=0.005
Boundary for River Rch & Prof#=UNT 151 IN LACR,Reach-1,7
Up Type=0
Dn Type=3
Dn Slope=0.005

--- UNT 151 IN LACR.g01 (geometry) ---

Geom Title=Existing Conditions
Program Version=4.10

River Reach=UNT 151 IN LACR ,Reach-1
Reach XY= 18
      2209687.72     13197346.85      2209737.72     13197346.85
      2209737.72     13197396.86      2209737.72     13197446.85
      2209687.72     13197496.85      2209687.72     13197546.86
      2209687.72     13197596.85      2209737.72     13197646.85
      2209787.72     13197696.85      2209787.72     13197746.86
      2209837.72     13197796.85      2209887.72     13197846.85
      2209887.72     13197896.86      2209937.72     13197946.85
      2209987.72     13197996.85      2210037.72     13197996.85
      2210087.72     13198046.86      2210087.72     13198096.85

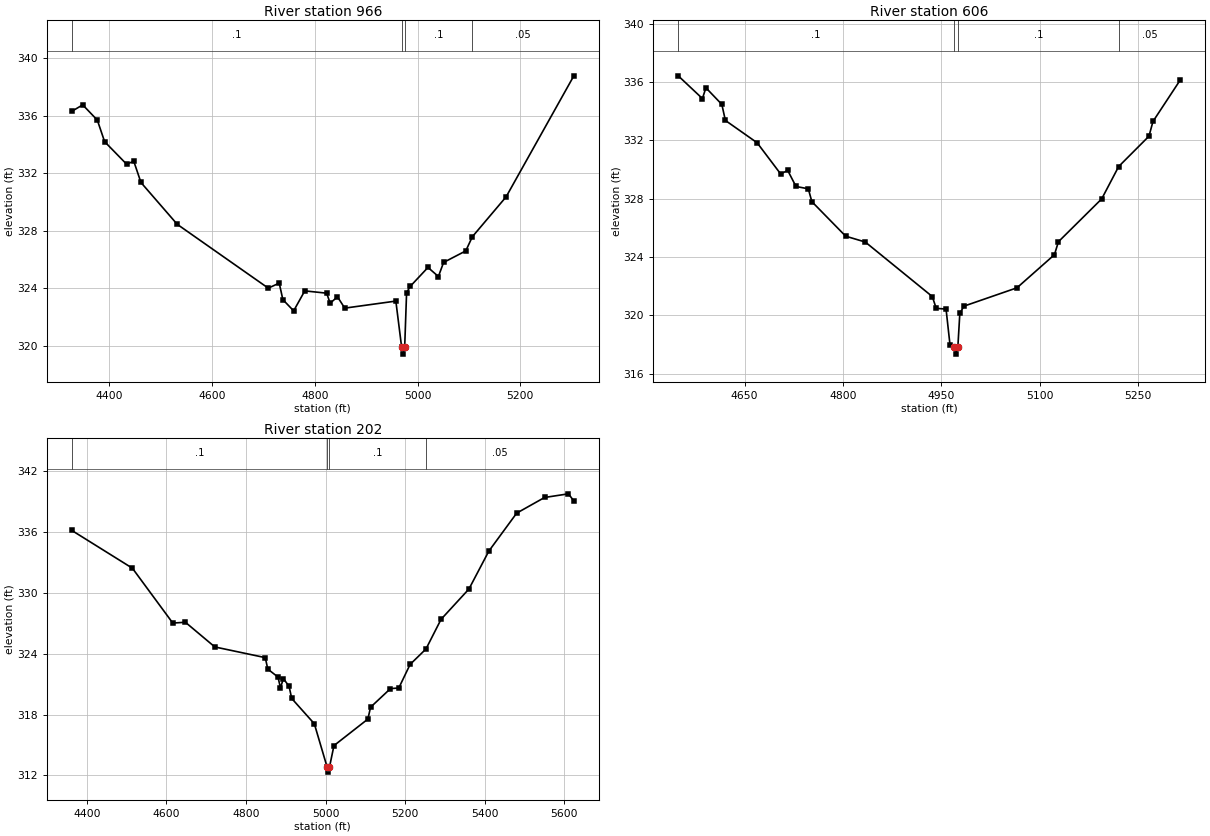
Type RM Length L Ch R = 1 ,966     ,360,360,360
BEGIN DESCRIPTION:
UNT 151 IN LACR 2.0
END DESCRIPTION:
XS GIS Cut Line= 3
      2209287.71     13197846.87      2209737.72     13197346.85
      2210037.68     13197396.85
#Sta/Elev= 30
  4327.3  336.32  4348.6  336.77    4377  335.71  4391.2  334.21  4433.8  332.65
    4448  332.84  4461.9  331.37  4532.5  328.46  4709.6  324.02  4730.9  324.37
    4738  323.22    4759  322.44  4780.6  323.83  4823.2  323.67    4830  322.97
  4844.2  323.42  4858.4  322.63  4957.8  323.12    4969  319.93  4971.7  319.43
    4975  319.93  4978.7  323.71  4986.2  324.16  5020.3  325.46  5040.6  324.83
  5050.7  325.81  5093.8  326.61  5106.7   327.6  5172.3  330.37  5304.1  338.79
#Mann= 4 ,-1 , 0
  4327.3      .1       0    4969     .07       0    4975      .1       0
  5106.7     .05       0
#XS Ineff= 1 ,-1
  4327.3 4780.91  323.82
Permanent Ineff=
       F
Bank Sta=4969,4975
XS Rating Curve= 0 ,0
Exp/Cntr=0.3,0.1

Type RM Length L Ch R = 1 ,606     ,404,404,404
BEGIN DESCRIPTION:
Mapping XS f33538e8
END DESCRIPTION:
XS GIS Cut Line= 3
      2209352.68     13197867.21      2209569.67     13197780.42
       2210012.4     13197485.26
#Sta/Elev= 30
  4548.8  336.43  4585.7  334.87    4591  335.61  4615.3  334.47  4620.7  333.37
  4669.1  331.84    4705   329.7  4715.8  329.94  4728.4  328.84  4747.2  328.68
  4752.6   327.8  4804.2  325.43  4834.1  325.03  4936.3  321.29  4942.3  320.48
  4957.3  320.43  4963.3  317.98  4969.3  317.84  4972.1  317.34  4975.3  317.84
  4978.3  320.13  4984.5  320.63  5065.5  321.89  5122.6  324.16  5128.7  325.05
  5194.7  327.99  5220.6  330.21  5266.8  332.29  5272.9   333.3  5314.6  336.15
#Mann= 4 ,-1 , 0
  4548.8      .1       0  4969.3     .07       0  4975.3      .1       0
  5220.6     .05       0
Bank Sta=4969.3,4975.3
XS Rating Curve= 0 ,0
Exp/Cntr=0.3,0.1

Type RM Length L Ch R = 1 ,202     ,0,0,0
BEGIN DESCRIPTION:
UNT 151 IN LACR 1.0
END DESCRIPTION:
XS GIS Cut Line= 4
       2209387.4     13197893.27      2209873.48      13198058.2
      2210151.26     13197806.46      2210151.26     13197433.23
#Sta/Elev= 30
  4362.4  336.12  4514.7   332.4  4616.2     327  4647.9  327.08  4721.8  324.65
  4848.5   323.6  4854.9  322.47  4880.4  321.69  4886.7  320.64  4894.1  321.53
  4908.3  320.78    4915  319.58  4971.8  317.09  5003.9  312.83  5006.7  312.33
  5009.9  312.83  5021.1  314.94  5106.3  317.55  5113.1  318.72  5163.1  320.55
    5184  320.61  5212.4  322.93  5252.3  324.45  5290.2  327.37  5360.2  330.35
  5410.2  334.08  5480.2  337.82  5550.2  339.36  5610.2  339.72  5623.8  339.02
#Mann= 4 ,-1 , 0
  4362.4      .1       0  5003.9     .07       0  5009.9      .1       0
  5252.3     .05       0
Bank Sta=5003.9,5009.9
XS Rating Curve= 0 ,0
Exp/Cntr=0.3,0.1

Chan Stop Cuts=-1
Use User Specified Reach Order=0
Composite Channel Slope=5