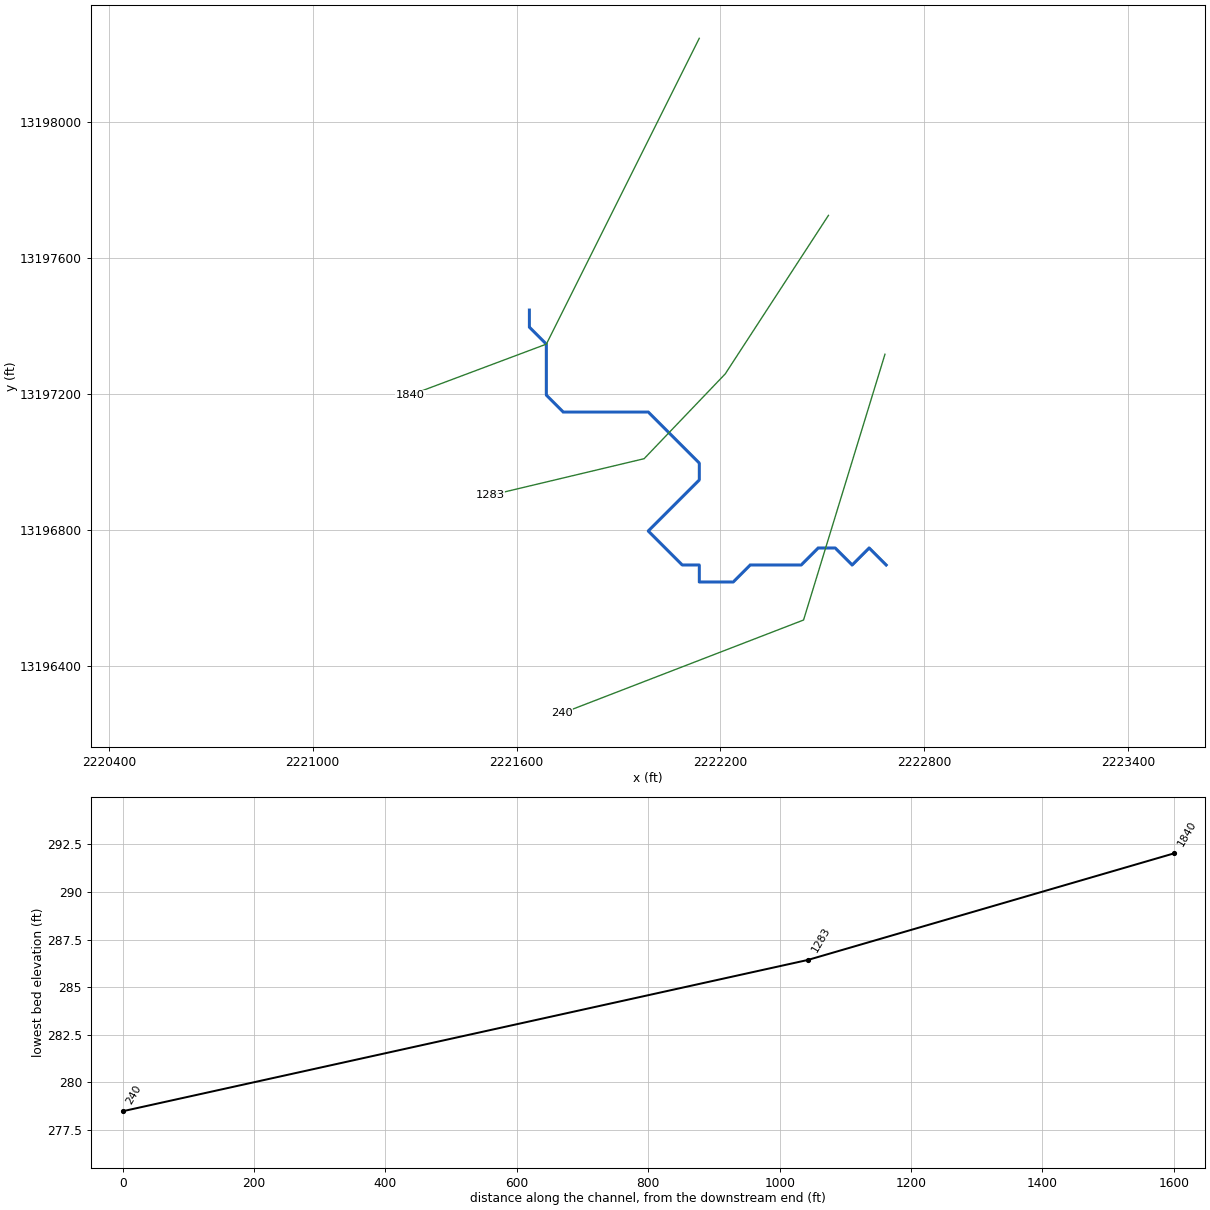
--- UNT 152 IN LACR.prj (project) ---

Proj Title=UNT 152 IN LACR Base Level Engineering
Current Plan=p01
Default Exp/Contr=0.3,0.1
English Units
Geom File=g01
Flow File=f01
Plan File=p01
BEGIN DESCRIPTION:
UNT 152 IN LACR
END DESCRIPTION:

--- UNT 152 IN LACR.p01 (plan) ---

Plan Title=Multiple Run
Short Identifier=Multiple
Geom File=g01
Flow File=f01
Subcritical Flow
K Sum by GR= 0
Std Step Tol= 0.01
Critical Tol= 0.01
Num of Std Step Trials= 20
Max Error Tol= 0.3
Flow Tol Ratio= 0.001
Split Flow NTrial= 30
Split Flow Tol= 0.02
Split Flow Ratio= 0.02
Log Output Level= 0
Friction Slope Method= 1
Unsteady Friction Slope Method= 2
Unsteady Bridges Friction Slope Method= 1
Parabolic Critical Depth
Global Vel Dist=  1 , 1 , 1
Global Log Level= 0
CheckData=True
Encroach Param= -1, 0, 0, 0
BEGIN DESCRIPTION:
Multiple Run
END DESCRIPTION:

--- UNT 152 IN LACR.f01 (steady flow) ---

Flow Title=Multiple
Number of Profiles=7
Profile Names=10-year,25-year,50-year,1pct_min,100-year,1pct_plu,500-year
River Rch & RM= UNT 152 IN LACR,Reach-1,1840
     120     162     196     174     236     319     347
Boundary for River Rch & Prof#=UNT 152 IN LACR,Reach-1,1
Up Type=0
Dn Type=3
Dn Slope=0.005
Boundary for River Rch & Prof#=UNT 152 IN LACR,Reach-1,2
Up Type=0
Dn Type=3
Dn Slope=0.005
Boundary for River Rch & Prof#=UNT 152 IN LACR,Reach-1,3
Up Type=0
Dn Type=3
Dn Slope=0.005
Boundary for River Rch & Prof#=UNT 152 IN LACR,Reach-1,4
Up Type=0
Dn Type=3
Dn Slope=0.005
Boundary for River Rch & Prof#=UNT 152 IN LACR,Reach-1,5
Up Type=0
Dn Type=3
Dn Slope=0.005
Boundary for River Rch & Prof#=UNT 152 IN LACR,Reach-1,6
Up Type=0
Dn Type=3
Dn Slope=0.005
Boundary for River Rch & Prof#=UNT 152 IN LACR,Reach-1,7
Up Type=0
Dn Type=3
Dn Slope=0.005

--- UNT 152 IN LACR.g01 (geometry) ---

Geom Title=Existing Conditions

River Reach=UNT 152 IN LACR,Reach-1
Reach XY= 26
      2221637.72     13197446.85      2221637.72     13197396.86
      2221687.72     13197346.85      2221687.72     13197196.85
      2221737.72     13197146.85      2221987.72     13197146.85
      2222137.72     13196996.85      2222137.72     13196946.85
      2222087.72     13196896.86      2222037.72     13196846.85
      2221987.72     13196796.85      2222037.72     13196746.86
      2222087.72     13196696.85      2222137.72     13196696.85
      2222137.72     13196646.85      2222187.72     13196646.85
      2222237.72     13196646.85      2222287.72     13196696.85
      2222337.72     13196696.85      2222387.72     13196696.85
      2222437.72     13196696.85      2222487.72     13196746.86
      2222537.72     13196746.86      2222587.72     13196696.85
      2222637.72     13196746.86      2222687.72     13196696.85

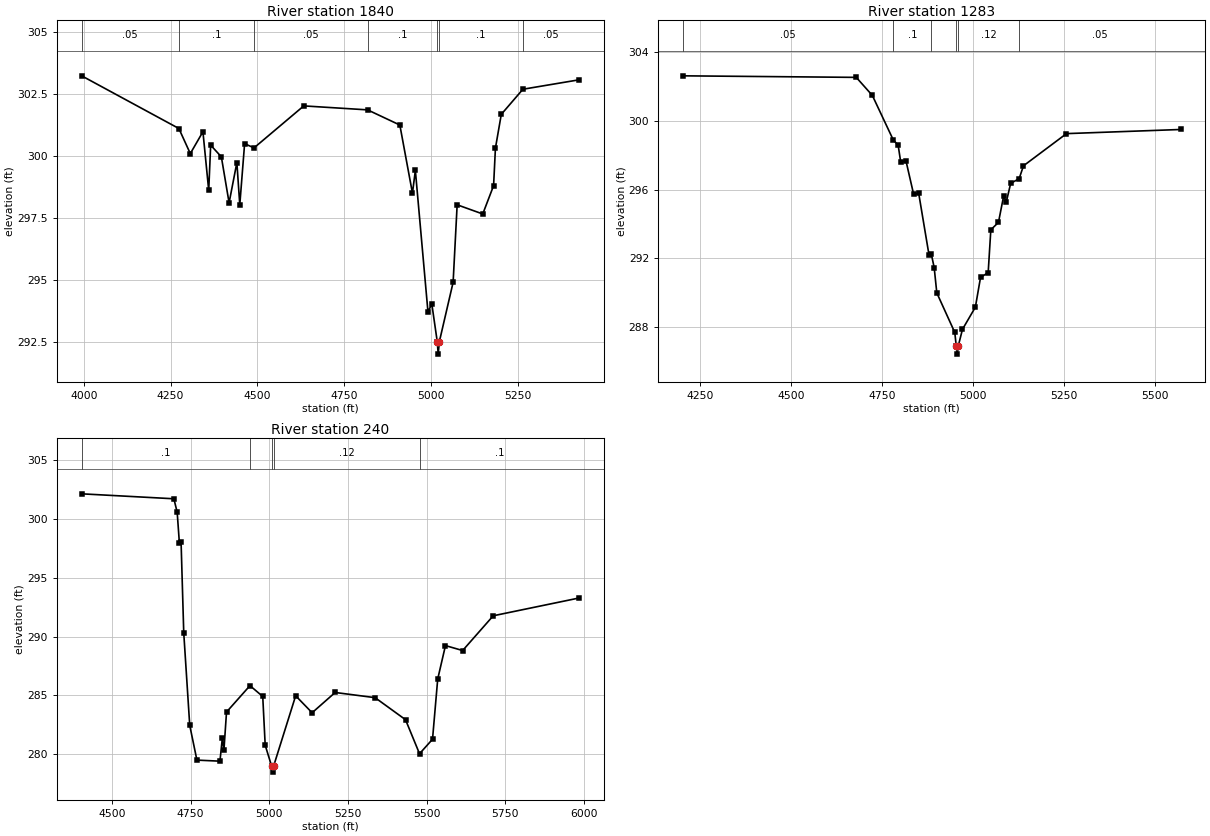
Type RM Length L Ch R = 1,1840,557,557,557
BEGIN DESCRIPTION:
UNT 152 IN LACR 2.0
END DESCRIPTION:
XS GIS Cut Line= 3
      2222137.71     13198246.83      2221687.72     13197346.85
      2221287.72     13197196.86
#Sta/Elev= 30
  3993.8  303.22  4273.9  301.10  4306.8  300.09  4343.2  300.97  4359.9  298.61
  4365.5  300.43  4396.3  299.96  4418.6  298.11  4441.0  299.73  4449.4  298.03
  4463.3  300.49  4490.4  300.32  4633.8  302.01  4817.7  301.85  4910.6  301.24
  4946.9  298.50  4955.3  299.41  4991.6  293.72  5002.7  294.04  5018.4  292.52
  5021.1  292.02  5024.4  292.52  5064.1  294.91  5075.7  298.03  5149.5  297.66
  5180.7  298.80  5186.0  300.31  5202.9  301.67  5265.2  302.68  5427.2  303.06
#Mann=7,-1,0
  3993.8    0.05       0  4273.9     0.1       0  4490.4    0.05       0
  4817.7     0.1       0  5018.4    0.07       0  5024.4     0.1       0
  5265.2    0.05       0
Bank Sta=5018.4,5024.4
Exp/Cntr=0.3,0.1

Type RM Length L Ch R = 1,1283,1043,1043,1043
BEGIN DESCRIPTION:
Mapping XS a98bfdb2
END DESCRIPTION:
XS GIS Cut Line= 4
      2222517.97     13197725.79      2222214.17     13197259.24
      2221975.45     13197009.67      2221522.71     13196901.88
#Sta/Elev= 30
  4203.6  302.61  4679.7  302.52  4723.9  301.47  4781.5  298.88  4794.8  298.58
  4802.0  297.58  4816.2  297.68  4837.3  295.73  4851.4  295.77  4879.7  292.19
  4886.2  292.23  4893.9  291.46  4901.1  289.99  4950.5  287.69  4954.4  286.93
  4957.2  286.43  4960.4  286.93  4971.6  287.87  5007.1  289.16  5021.3  290.89
  5042.3  291.17  5049.6  293.66  5070.6  294.09  5084.8  295.62  5092.0  295.27
  5104.2  296.36  5127.4  296.63  5139.4  297.38  5257.6  299.25  5571.1  299.49
#Mann=6,-1,0
  4203.6    0.05       0  4781.5     0.1       0  4886.2    0.12       0
  4954.4    0.07       0  4960.4    0.12       0  5127.4    0.05       0
Bank Sta=4954.4,4960.4
Exp/Cntr=0.3,0.1

Type RM Length L Ch R = 1,240,0,0,0
BEGIN DESCRIPTION:
UNT 152 IN LACR 1.0
END DESCRIPTION:
XS GIS Cut Line= 3
      2222684.26     13197317.01      2222444.70     13196534.92
      2221733.07     13196260.13
#Sta/Elev= 30
  4403.7  302.11  4696.7  301.69  4707.2  300.55  4714.3  297.90  4719.6  298.01
  4728.1  290.30  4747.1  282.46  4769.9  279.51  4843.1  279.42  4850.6  281.35
  4855.8  280.37  4864.0  283.59  4938.5  285.83  4979.1  284.91  4986.9  280.77
  5007.5  278.99  5010.2  278.49  5013.5  278.99  5083.7  284.97  5136.0  283.53
  5209.2  285.25  5336.1  284.81  5432.8  282.94  5477.3  280.05  5518.6  281.28
  5535.1  286.39  5559.7  289.23  5614.3  288.81  5711.5  291.76  5984.5  293.27
#Mann=5,-1,0
  4403.7     0.1       0  4938.5    0.12       0  5007.5    0.07       0
  5013.5    0.12       0  5477.3     0.1       0
Bank Sta=5007.5,5013.5
Exp/Cntr=0.3,0.1

Chan Stop Cuts=-1