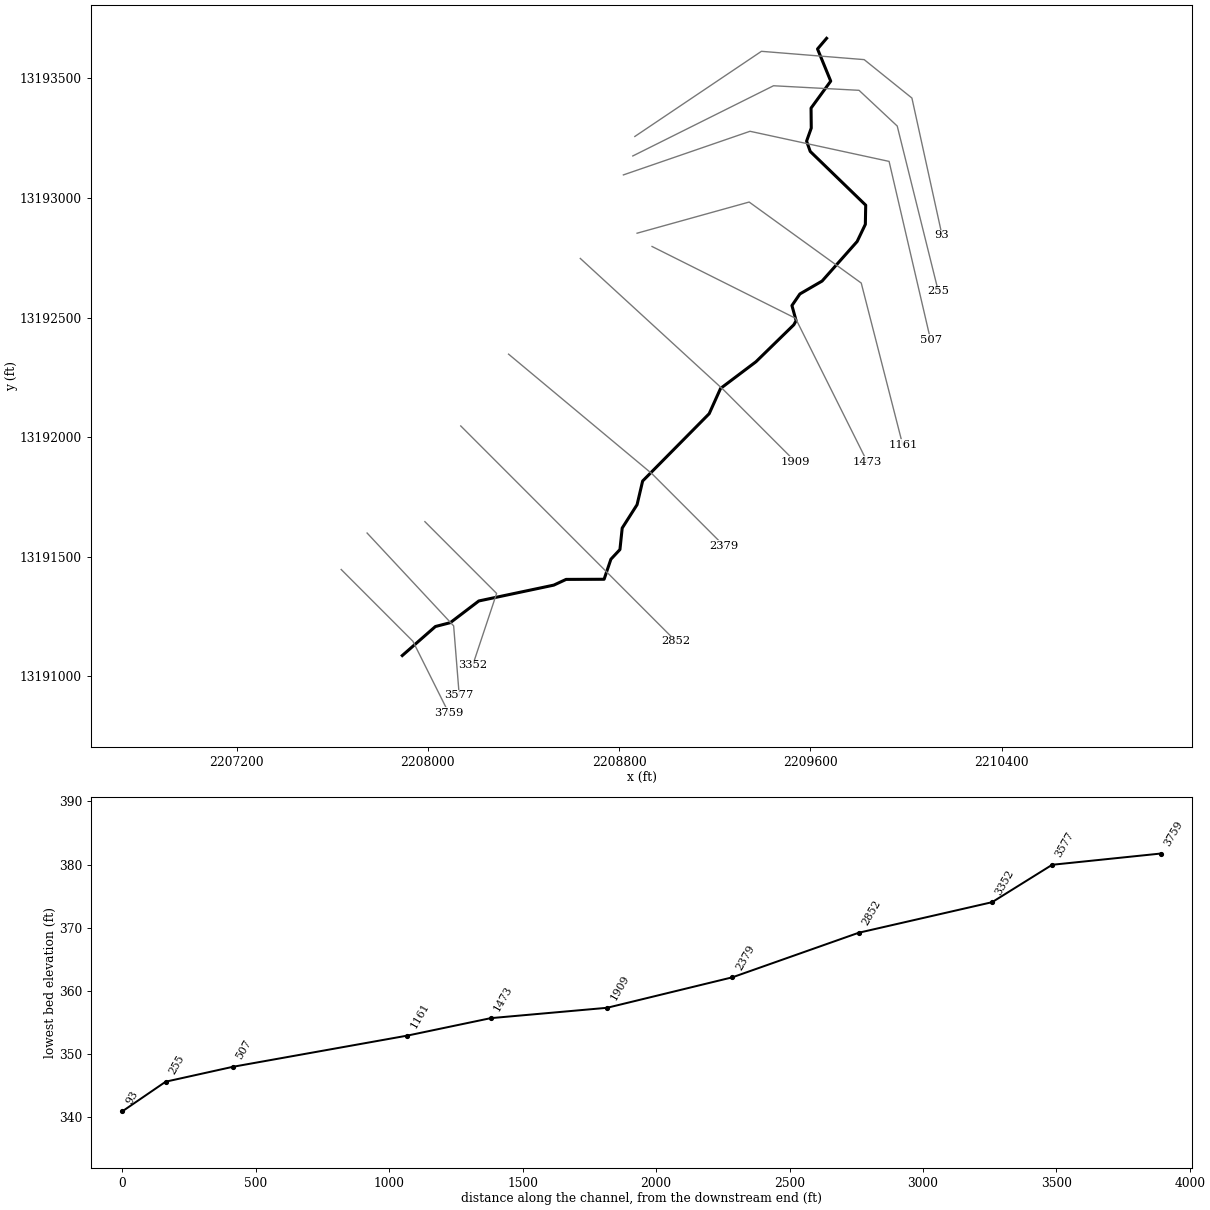
--- UNT 153 IN LACR.prj (project) ---

Proj Title=UNT 153 IN LACR Base Level Engineering
Current Plan=p01
Default Exp/Contr=0.3,0.1
English Units
Geom File=g01
Geom File=g02
Flow File=f01
Plan File=p01
Y Axis Title=Elevation
X Axis Title(PF)=Main Channel Distance
X Axis Title(XS)=Station
BEGIN DESCRIPTION:
UNT 153 IN LACR
END DESCRIPTION:
DSS Export Rating Curves= 0
DSS Export Rating Curve Sorted= 0
DSS Export Volume Flow Curves= 0
DXF OffsetX= 0
DXF OffsetY= 0
DXF ScaleX= 1
DXF ScaleY= 10

--- UNT 153 IN LACR.p01 (plan) ---

Plan Title=Multiple Run
Short Identifier=Multiple
Geom File=g01
Flow File=f01
Subcritical Flow
K Sum by GR= 0
Std Step Tol= 0.01
Critical Tol= 0.01
Num of Std Step Trials= 20
Max Error Tol= 0.3
Flow Tol Ratio= 0.001
Split Flow NTrial= 30
Split Flow Tol= 0.02
Split Flow Ratio= 0.02
Log Output Level= 0
Friction Slope Method= 1
Unsteady Friction Slope Method= 2
Unsteady Bridges Friction Slope Method= 1
Parabolic Critical Depth
Global Vel Dist=  1 , 1 , 1
Global Log Level= 0
CheckData=True
Encroach Param= -1, 0, 0, 0
BEGIN DESCRIPTION:
Multiple Run
END DESCRIPTION:

--- UNT 153 IN LACR.f01 (steady flow) ---

Flow Title=Multiple
Number of Profiles=7
Profile Names=10-year,25-year,50-year,1pct_min,100-year,1pct_plu,500-year
River Rch & RM= UNT 153 IN LACR,Reach-1,3759
     125     169     205     184     248     336     370
Boundary for River Rch & Prof#=UNT 153 IN LACR,Reach-1,1
Up Type=0
Dn Type=3
Dn Slope=0.005
Boundary for River Rch & Prof#=UNT 153 IN LACR,Reach-1,2
Up Type=0
Dn Type=3
Dn Slope=0.005
Boundary for River Rch & Prof#=UNT 153 IN LACR,Reach-1,3
Up Type=0
Dn Type=3
Dn Slope=0.005
Boundary for River Rch & Prof#=UNT 153 IN LACR,Reach-1,4
Up Type=0
Dn Type=3
Dn Slope=0.005
Boundary for River Rch & Prof#=UNT 153 IN LACR,Reach-1,5
Up Type=0
Dn Type=3
Dn Slope=0.005
Boundary for River Rch & Prof#=UNT 153 IN LACR,Reach-1,6
Up Type=0
Dn Type=3
Dn Slope=0.005
Boundary for River Rch & Prof#=UNT 153 IN LACR,Reach-1,7
Up Type=0
Dn Type=3
Dn Slope=0.005

--- UNT 153 IN LACR.g01 (geometry) ---

Geom Title=Existing Conditions
Program Version=4.10

River Reach=UNT 153 IN LACR ,Reach-1
Reach XY= 30
      2207893.17     13191087.27      2208031.72      13191208.6
      2208093.94     13191224.66      2208213.28      13191315.4
      2208526.84     13191381.61      2208578.31     13191405.52
      2208737.21     13191406.07      2208765.67     13191489.89
      2208803.45     13191530.29      2208812.93     13191620.07
      2208875.16     13191717.83      2208898.36     13191816.65
      2209176.63     13192097.91      2209224.29     13192203.63
      2209372.33     13192315.13      2209530.65     13192469.57
      2209540.21     13192486.88      2209522.79     13192549.93
      2209556.07      13192598.5      2209648.87     13192652.38
      2209795.52     13192817.76      2209829.82     13192889.41
      2209831.31     13192969.51      2209599.25     13193194.19
      2209584.05      13193237.1       2209603.6     13193291.85
      2209602.73     13193375.21        2209685.     13193487.98
      2209629.81     13193622.39      2209667.72     13193666.85

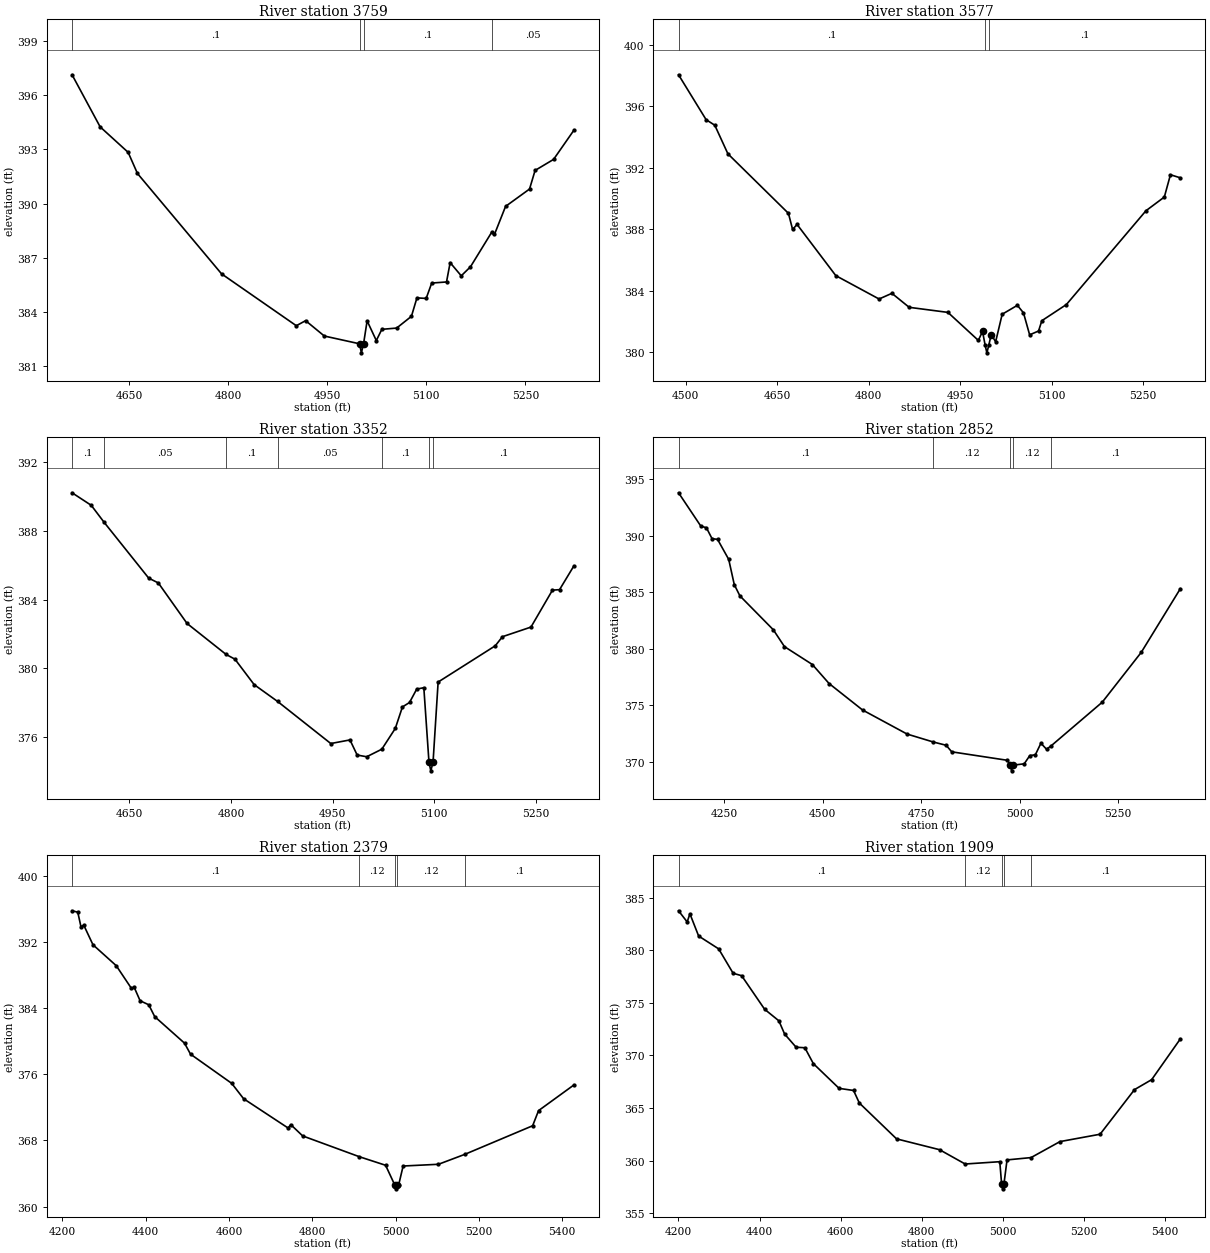
Type RM Length L Ch R = 1 ,3759    ,407,407,407
BEGIN DESCRIPTION:
UNT 153 IN LACR 7.0
END DESCRIPTION:
XS GIS Cut Line= 3
      2207637.69     13191446.89      2207937.72     13191146.86
      2208087.71     13190846.87
#Sta/Elev= 30
  4563.7  397.12  4606.2  394.24  4648.6  392.83  4662.7  391.66    4790  386.11
  4903.2  383.24  4917.3  383.52  4945.6  382.67    4999  382.24  5001.7  381.74
    5005  382.24  5010.4  383.51  5024.3  382.42  5032.7  383.04  5055.1  383.11
  5077.5  383.76  5085.8  384.78  5099.8  384.75  5108.2   385.6  5130.6  385.66
  5136.1  386.73  5152.9     386  5166.9   386.5    5199  388.41  5203.2  388.29
    5220  389.84  5256.3   390.8  5264.7  391.83  5292.7  392.44  5323.4  394.05
#Mann= 4 ,-1 , 0
  4563.7      .1       0    4999     .07       0    5005      .1       0
    5199     .05       0
Bank Sta=4999,5005
XS Rating Curve= 0 ,0
Exp/Cntr=0.3,0.1

Type RM Length L Ch R = 1 ,3577    ,225,225,225
BEGIN DESCRIPTION:
Mapping XS e512db8e
END DESCRIPTION:
XS GIS Cut Line= 3
      2207746.01     13191599.34        2208108.     13191211.31
      2208131.35     13190920.71
#Sta/Elev= 30
  4488.5  398.04  4533.7  395.12  4547.9  394.76  4569.4   392.9  4668.6  389.03
  4675.4  387.98  4682.7  388.31  4746.2  384.98  4817.1  383.46  4838.1  383.83
  4866.4  382.92  4929.9  382.59  4979.7  380.77  4986.6  381.35  4990.9  380.46
  4993.7  379.96  4996.9  380.46  5000.8  381.15  5008.1  380.68  5018.8  382.47
  5043.7  383.05  5053.7  382.56  5063.8  381.13  5078.4  381.38  5083.8  382.05
    5124   383.1  5254.4   389.2  5284.5  390.09  5294.5  391.54  5310.7  391.34
#Mann= 3 ,-1 , 0
  4488.5      .1       0  4990.9     .07       0  4996.9      .1       0
#XS Ineff= 2 , 0
       0                 5043.75       0  383.01
Permanent Ineff=
       F       T
Bank Sta=4986.6,5000.8
XS Rating Curve= 0 ,0
Exp/Cntr=0.3,0.1

Type RM Length L Ch R = 1 ,3352    ,500,500,500
BEGIN DESCRIPTION:
UNT 153 IN LACR 6.0
END DESCRIPTION:
XS GIS Cut Line= 3
      2207987.73     13191646.85      2208287.72     13191346.86
      2208187.71     13191046.84
#Sta/Elev= 30
  4565.6  390.23  4593.9   389.5  4612.9  388.51  4678.7  385.26  4692.9  384.98
  4735.3  382.62  4792.8  380.82    4806  380.54  4834.3  379.06  4868.9  378.08
  4947.4  375.63  4975.7  375.84  4986.3  374.96  5000.4  374.86  5022.7   375.3
  5042.6  376.51  5053.1  377.76  5063.6  378.02  5074.2   378.8  5084.7  378.88
  5092.3  374.54    5095  374.04  5098.3  374.54  5105.8  379.21  5190.1  381.32
  5200.7  381.85  5242.8  382.41  5274.5  384.56    5285  384.59  5306.1  385.97
#Mann= 7 ,-1 , 0
  4565.6      .1       0  4612.9     .05       0  4792.8      .1       0
  4868.9     .05       0  5022.7      .1       0  5092.3     .03       0
  5098.3      .1       0
Bank Sta=5092.3,5098.3
XS Rating Curve= 0 ,0
Exp/Cntr=0.3,0.1

Type RM Length L Ch R = 1 ,2852    ,473,473,473
BEGIN DESCRIPTION:
UNT 153 IN LACR 5.0
END DESCRIPTION:
XS GIS Cut Line= 3
      2208137.72     13192046.86      2208737.72     13191446.85
      2209037.72     13191146.85
#Sta/Elev= 30
  4134.7  393.78  4191.3  390.83  4205.4  390.69  4219.6  389.73  4233.7  389.66
    4262  387.89  4276.1  385.66  4290.3  384.67  4375.1  381.67  4403.4  380.18
  4474.1   378.6  4516.5  376.92  4601.4  374.58  4714.5  372.45  4780.8  371.75
  4813.5  371.46  4827.7  370.88  4969.1  370.13  4976.7   369.7  4979.4   369.2
  4982.7   369.7  5011.5  369.82  5025.7  370.55  5039.8  370.62  5053.9  371.64
  5068.1  371.11  5079.5   371.4  5209.5  375.27  5308.5  379.68  5407.5   385.3
#Mann= 5 ,-1 , 0
  4134.7      .1       0  4780.8     .12       0  4976.7     .07       0
  4982.7     .12       0  5079.5      .1       0
Bank Sta=4976.7,4982.7
XS Rating Curve= 0 ,0
Exp/Cntr=0.3,0.1

Type RM Length L Ch R = 1 ,2379    ,470,470,470
BEGIN DESCRIPTION:
UNT 153 IN LACR 4.0
END DESCRIPTION:
XS GIS Cut Line= 3
      2208337.69     13192346.88      2208937.72     13191846.85
       2209237.7     13191546.87
#Sta/Elev= 30
    4223  395.78  4236.7  395.61  4244.5  393.82    4251  394.05  4273.2  391.67
  4329.1  389.14  4365.6  386.39  4372.1  386.54  4386.4   384.9  4407.2  384.41
  4421.5  382.98  4493.1  379.77  4507.5  378.44  4606.4  374.91    4635  373.05
  4741.8  369.51  4748.3  369.92  4776.9  368.55  4913.3  366.03  4976.1     365
  4997.8  362.65  5000.6  362.15  5003.8  362.65  5007.6  362.65  5018.2  364.91
  5103.1  365.12  5166.3  366.32  5329.3  369.78  5343.5  371.61  5428.3  374.71
#Mann= 5 ,-1 , 0
    4223      .1       0  4913.3     .12       0  4997.8     .07       0
  5003.8     .12       0  5166.3      .1       0
Bank Sta=4997.8,5003.8
XS Rating Curve= 0 ,0
Exp/Cntr=0.3,0.1

Type RM Length L Ch R = 1 ,1909    ,436,436,436
BEGIN DESCRIPTION:
UNT 153 IN LACR 3.0
END DESCRIPTION:
XS GIS Cut Line= 3
      2208637.72     13192746.86      2209237.72     13192196.85
      2209537.72     13191896.86
#Sta/Elev= 30
  4200.1  383.75  4221.4  382.69  4228.2  383.46  4249.7  381.35  4299.1  380.13
  4334.8  377.81  4355.8  377.58  4412.5  374.39  4447.7  373.29  4461.9  372.03
  4490.2  370.78  4511.8  370.73  4532.8  369.22  4596.3  366.87    4632  366.67
  4646.2  365.48  4738.1  362.07  4844.2  361.04  4907.4  359.68  4992.8   359.9
  4997.2  357.82  4999.9  357.32  5003.2  357.82  5010.7  360.07  5069.9  360.29
  5141.3  361.81  5240.3  362.51  5325.2  366.75  5367.6   367.7  5438.3  371.57
#Mann= 5 ,-1 , 0
  4200.1      .1       0  4907.4     .12       0  4997.2     .07       0
  5003.2     .12       0  5069.9      .1       0
Bank Sta=4997.2,5003.2
XS Rating Curve= 0 ,0
Exp/Cntr=0.3,0.1

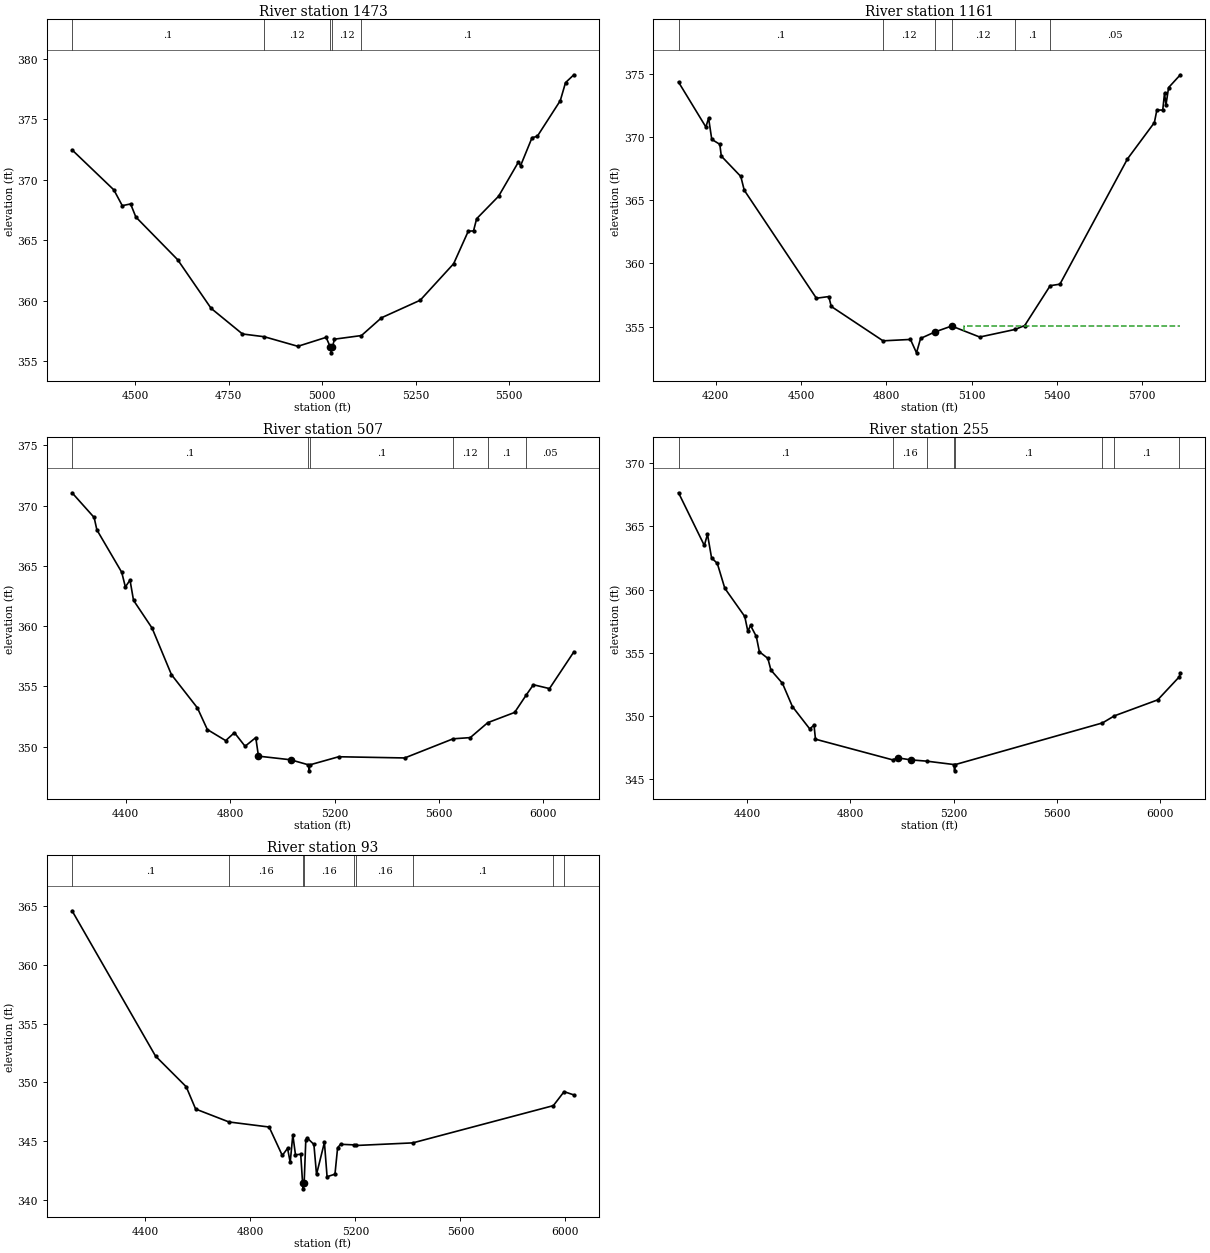
Type RM Length L Ch R = 1 ,1473    ,312,312,312
BEGIN DESCRIPTION:
UNT 153 IN LACR 2.0
END DESCRIPTION:
XS GIS Cut Line= 3
      2208937.73     13192796.85      2209537.72     13192496.86
      2209837.71     13191896.88
#Sta/Elev= 30
  4331.1  372.46  4442.9  369.15  4465.3  367.85  4487.6  367.99  4501.6  366.91
  4613.4  363.38  4702.8  359.36  4786.7  357.24  4845.2  357.01  4934.8  356.22
  5010.3  356.96  5021.3  356.18    5024  355.68  5027.3  356.18  5032.7  356.81
  5104.8  357.11  5158.4  358.58  5261.9  360.03  5351.3  363.05  5390.4  365.74
  5404.4  365.76  5412.8  366.77  5471.5  368.63  5524.6  371.46  5530.2  371.15
  5560.9  373.47  5574.9  373.58  5636.4  376.53  5650.4  378.02  5672.7  378.67
#Mann= 5 ,-1 , 0
  4331.1      .1       0  4845.2     .12       0  5021.3     .07       0
  5027.3     .12       0  5104.8      .1       0
Bank Sta=5021.3,5027.3
XS Rating Curve= 0 ,0
Exp/Cntr=0.3,0.1

Type RM Length L Ch R = 1 ,1161    ,654,654,654
BEGIN DESCRIPTION:
Mapping XS 7ec78919
END DESCRIPTION:
XS GIS Cut Line= 4
      2208875.15     13192852.38      2209343.88     13192982.59
      2209812.63     13192644.04      2209986.25     13191966.95
#Sta/Elev= 30
  4069.8  374.33  4165.9  370.78  4175.5  371.48  4186.6   369.8  4214.9  369.41
  4220.1  368.48  4288.6  366.87  4300.8  365.78  4554.3  357.24    4598  357.37
  4606.5  356.59  4788.6  353.87    4885  353.98  4906.2  352.92  4920.6  354.06
  4970.8  354.57  5029.7  355.04  5128.4  354.17  5252.7  354.77  5286.5  355.08
  5376.1  358.23  5410.3  358.35  5647.8  368.26  5742.3  371.13    5751  372.12
  5771.7  372.12  5777.9  373.44  5783.1  372.54  5792.3   373.9  5833.5  374.91
#Mann= 6 ,-1 , 0
  4069.8      .1       0  4788.6     .12       0  4970.8     .07       0
  5029.7     .12       0  5252.7      .1       0  5376.1     .05       0
#XS Ineff= 2 , 0
                          5071.8          355.06
Permanent Ineff=
       F       F
Bank Sta=4970.8,5029.7
XS Rating Curve= 0 ,0
Exp/Cntr=0.3,0.1

Type RM Length L Ch R = 1 ,507     ,252,252,252
BEGIN DESCRIPTION:
Mapping XS 8af75217
END DESCRIPTION:
XS GIS Cut Line= 4
      2208817.93     13193096.03      2209347.48     13193278.33
      2209929.08     13193152.46       2210102.7      13192405.9
#Sta/Elev= 30
  4194.8  371.07  4279.3  369.02  4289.8  367.99  4384.9  364.47  4398.9  363.25
  4416.7  363.82  4430.1  362.14  4501.3  359.83  4575.3  355.97  4674.7  353.21
  4712.8  351.41  4783.1  350.49  4816.5  351.15  4857.4  350.02  4898.3  350.74
  4908.6   349.2  5031.3   348.9    5100  348.48  5102.7  347.98    5106  348.48
  5215.8  349.15  5468.6  349.05    5654  350.64  5719.7  350.74  5786.6  351.98
  5889.6  352.83  5933.8  354.27  5961.4  355.13    6023  354.81  6116.4  357.86
#Mann= 6 ,-1 , 0
  4194.8      .1       0    5100     .07       0    5106      .1       0
    5654     .12       0  5786.6      .1       0  5933.8     .05       0
Bank Sta=4908.6,5031.3
XS Rating Curve= 0 ,0
Exp/Cntr=0.3,0.1

Type RM Length L Ch R = 1 ,255     ,162,162,162
BEGIN DESCRIPTION:
Mapping XS d21dfde2
END DESCRIPTION:
XS GIS Cut Line= 5
      2208857.27     13193175.23      2209445.79     13193468.62
      2209803.43     13193449.52      2209963.15     13193300.22
      2210134.71     13192610.52
#Sta/Elev= 30
    4134  367.67    4234  363.49  4246.2  364.38    4262  362.51  4284.3  362.07
  4313.3   360.1  4390.7  357.86  4402.7  356.68    4413  357.15  4435.4  356.28
  4447.4  355.06  4480.2  354.54  4492.1  353.61  4536.8  352.56  4575.3  350.72
  4642.4  348.95  4659.2  349.24  4664.8  348.13  4964.1  346.49  4983.8  346.65
  5033.9  346.49  5095.2  346.39  5201.2  346.12    5204  345.62  5207.2  346.12
  5777.4  349.42  5823.4  349.98  5991.6  351.25  6075.7  353.09  6079.1  353.39
#Mann= 8 ,-1 , 0
    4134      .1       0  4964.1     .16       0  5095.2      .1       0
  5201.2     .07       0  5207.2      .1       0  5777.4     .12       0
  5823.4      .1       0  6075.7     .05       0
Bank Sta=4983.8,5033.9
XS Rating Curve= 0 ,0
Exp/Cntr=0.3,0.1

Type RM Length L Ch R = 1 ,93      ,0,0,0
BEGIN DESCRIPTION:
UNT 153 IN LACR 1.0
END DESCRIPTION:
XS GIS Cut Line= 5
      2208865.74     13193256.65      2209395.22     13193612.53
      2209824.91     13193577.81      2210024.56     13193417.22
      2210150.44     13192844.27
#Sta/Elev= 30
  4120.4   364.6  4438.3  352.24  4555.2  349.63  4591.2  347.73  4718.2  346.63
  4871.2   346.2  4921.4  343.78  4941.5  344.39  4951.5  343.19  4961.5  345.53
  4971.6  343.84  4991.6  343.88  4998.7  341.44  5001.4  340.94  5004.7  341.44
  5010.9  345.06  5015.9  345.28  5041.8  344.72  5051.8  342.17  5081.9  344.89
    5092  341.97  5122.1  342.19  5132.1  344.43  5143.2  344.73  5195.9  344.68
  5203.5  344.63  5418.6  344.85  5954.1  348.02  5995.1  349.21  6032.3  348.93
#Mann= 9 ,-1 , 0
  4120.4      .1       0  4718.2     .16       0  4998.7     .07       0
  5004.7     .16       0  5195.9      .1       0  5203.5     .16       0
  5418.6      .1       0  5954.1     .12       0  5995.1      .1       0
Bank Sta=4998.7,5004.7
XS Rating Curve= 0 ,0
Exp/Cntr=0.3,0.1

Chan Stop Cuts=-1
Use User Specified Reach Order=0
Composite Channel Slope=5

--- UNT 153 IN LACR.g02 (geometry) ---

Geom Title=Dummy
Program Version=4.10

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
River Reach=UNT 153 IN LACR ,Reach-1
Reach XY= 30
      2207887.72     13191096.85      2207987.72     13191196.85
      2208137.72     13191296.85      2208237.72     13191296.85
      2208287.72     13191346.86      2208437.72     13191346.86
      2208487.72     13191396.85      2208687.72     13191396.85
      2208787.72     13191496.86      2208787.72     13191546.85
      2208837.72     13191596.85      2208837.72     13191696.85
      2208887.72     13191746.85      2208887.72     13191796.85
      2209187.72     13192096.85      2209187.72     13192146.86
      2209387.72     13192346.85      2209437.72     13192346.85
      2209487.72     13192396.85      2209487.72     13192446.85
      2209537.72     13192496.86      2209537.72     13192546.85
      2209837.72     13192846.85      2209837.72     13192996.85
      2209587.72     13193246.85      2209587.72     13193346.85
      2209687.72     13193446.86      2209687.72     13193546.85
      2209637.72     13193596.85      2209637.72     13193646.86

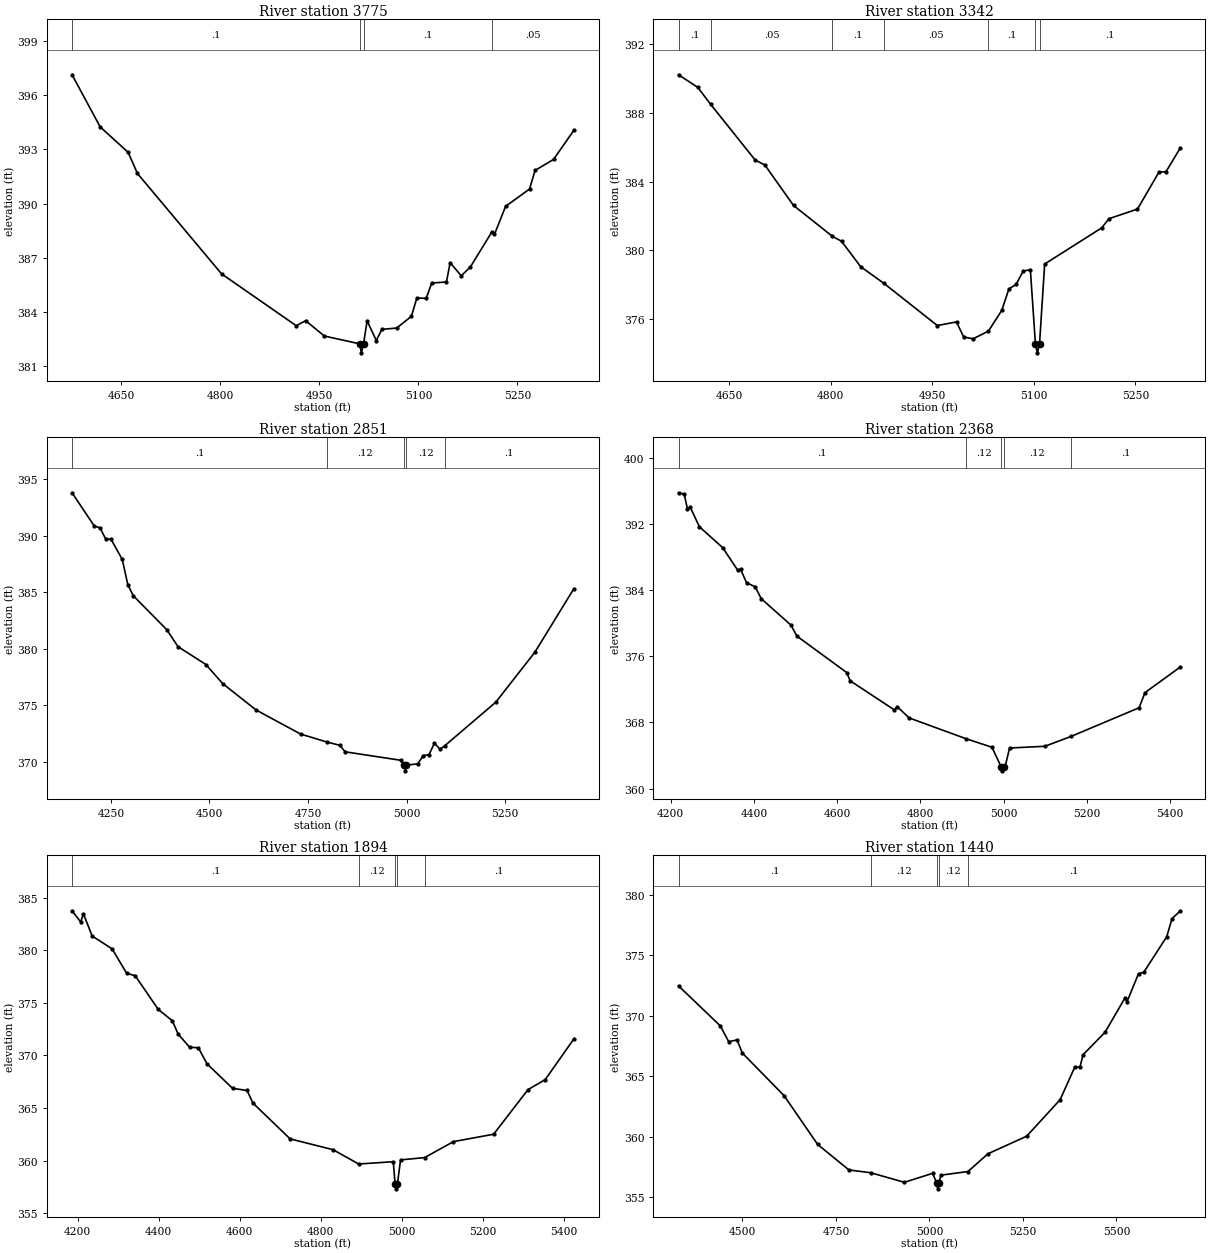
Type RM Length L Ch R = 1 ,3775    ,433,433,433
BEGIN DESCRIPTION:
UNT 153 IN LACR 7.0
END DESCRIPTION:
XS GIS Cut Line= 3
      2207637.69     13191446.88      2207937.72     13191146.86
      2208087.72     13190846.86
#Sta/Elev= 30
  4575.7  397.12  4618.2  394.24  4660.6  392.83  4674.7  391.66    4802  386.11
  4915.1  383.24  4929.3  383.52  4957.6  382.67    5011  382.24  5013.7  381.74
    5017  382.24  5022.4  383.51  5036.3  382.42  5044.7  383.04  5067.1  383.11
  5089.4  383.76  5097.8  384.78  5111.8  384.75  5120.2   385.6  5142.5  385.66
  5148.1  386.73  5164.9     386  5178.9   386.5    5211  388.41  5215.2  388.29
    5232  389.84  5268.3   390.8  5276.7  391.83  5304.7  392.44  5335.4  394.05
#Mann= 4 ,-1 , 0
  4575.7      .1       0    5011     .07       0    5017      .1       0
    5211     .05       0
Bank Sta=5011,5017
XS Rating Curve= 0 ,0
Exp/Cntr=0.3,0.1

Type RM Length L Ch R = 1 ,3342    ,491,491,491
BEGIN DESCRIPTION:
UNT 153 IN LACR 6.0
END DESCRIPTION:
XS GIS Cut Line= 3
      2207987.69     13191646.88      2208287.72     13191346.86
      2208187.73     13191046.88
#Sta/Elev= 30
  4575.7  390.23    4604   389.5  4623.1  388.51  4688.9  385.26    4703  384.98
  4745.4  382.62  4802.9  380.82  4816.2  380.54  4844.4  379.06    4879  378.08
  4957.6  375.63  4985.9  375.84  4996.5  374.96  5010.5  374.86  5032.9   375.3
  5052.7  376.51  5063.2  377.76  5073.8  378.02  5084.3   378.8  5094.9  378.88
  5102.4  374.54  5105.2  374.04  5108.4  374.54    5116  379.21  5200.3  381.32
  5210.8  381.85    5253  382.41  5284.6  384.56  5295.1  384.59  5316.2  385.97
#Mann= 7 ,-1 , 0
  4575.7      .1       0  4623.1     .05       0  4802.9      .1       0
    4879     .05       0  5032.9      .1       0  5102.4     .03       0
  5108.4      .1       0
Bank Sta=5102.4,5108.4
XS Rating Curve= 0 ,0
Exp/Cntr=0.3,0.1

Type RM Length L Ch R = 1 ,2851    ,483,483,483
BEGIN DESCRIPTION:
UNT 153 IN LACR 5.0
END DESCRIPTION:
XS GIS Cut Line= 3
      2208137.74     13192046.83      2208737.72     13191446.85
      2209037.75     13191146.83
#Sta/Elev= 30
  4151.5  393.78    4208  390.83  4222.2  390.69  4236.3  389.73  4250.5  389.66
  4278.8  387.89  4292.9  385.66    4307  384.67  4391.9  381.67  4420.2  380.18
  4490.9   378.6  4533.3  376.92  4618.2  374.58  4731.3  372.45  4797.6  371.75
  4830.3  371.46  4844.4  370.88  4985.9  370.13  4993.5   369.7  4996.2   369.2
  4999.5   369.7  5028.3  369.82  5042.4  370.55  5056.6  370.62  5070.7  371.64
  5084.9  371.11  5096.2   371.4  5226.3  375.27  5325.3  379.68  5424.3   385.3
#Mann= 5 ,-1 , 0
  4151.5      .1       0  4797.6     .12       0  4993.5     .07       0
  4999.5     .12       0  5096.2      .1       0
Bank Sta=4993.5,4999.5
XS Rating Curve= 0 ,0
Exp/Cntr=0.3,0.1

Type RM Length L Ch R = 1 ,2368    ,474,474,474
BEGIN DESCRIPTION:
UNT 153 IN LACR 4.0
END DESCRIPTION:
XS GIS Cut Line= 3
      2208337.74     13192346.84      2208937.72     13191846.85
      2209237.75     13191546.83
#Sta/Elev= 30
    4219  395.78  4232.6  395.61  4240.5  393.82    4247  394.05  4269.1  391.67
  4325.1  389.14  4361.5  386.39    4368  386.54  4382.3   384.9  4403.2  384.41
  4417.5  382.98  4489.1  379.77  4503.4  378.44  4623.2  374.03    4631  373.05
  4737.7  369.51  4744.2  369.92  4772.9  368.55  4909.3  366.04    4972     365
  4993.7  362.65  4996.5  362.15  4999.7  362.65  5003.5  362.65  5014.1  364.91
    5099  365.12  5162.2  366.32  5325.3  369.78  5339.4  371.61  5424.3  374.71
#Mann= 5 ,-1 , 0
    4219      .1       0  4909.3     .12       0  4993.7     .07       0
  4999.7     .12       0  5162.2      .1       0
Bank Sta=4993.7,4999.7
XS Rating Curve= 0 ,0
Exp/Cntr=0.3,0.1

Type RM Length L Ch R = 1 ,1894    ,454,454,454
BEGIN DESCRIPTION:
UNT 153 IN LACR 3.0
END DESCRIPTION:
XS GIS Cut Line= 3
      2208637.75     13192746.83      2209237.72     13192196.85
      2209537.75     13191896.83
#Sta/Elev= 30
  4186.1  383.75  4207.3  382.69  4214.1  383.46  4235.7  381.35    4285  380.13
  4320.8  377.81  4341.8  377.58  4398.5  374.39  4433.6  373.29  4447.8  372.03
  4476.2  370.78  4497.8  370.73  4518.7  369.22  4582.2  366.87    4618  366.67
  4632.2  365.48  4724.1  362.07  4830.1  361.04  4893.4  359.68  4978.7   359.9
  4983.1  357.82  4985.9  357.32  4989.1  357.82  4996.6  360.07  5055.9  360.29
  5127.3  361.81  5226.3  362.51  5311.1  366.75  5353.6   367.7  5424.3  371.57
#Mann= 5 ,-1 , 0
  4186.1      .1       0  4893.4     .12       0  4983.1     .07       0
  4989.1     .12       0  5055.9      .1       0
Bank Sta=4983.1,4989.1
XS Rating Curve= 0 ,0
Exp/Cntr=0.3,0.1

Type RM Length L Ch R = 1 ,1440    ,293,293,293
BEGIN DESCRIPTION:
UNT 153 IN LACR 2.0
END DESCRIPTION:
XS GIS Cut Line= 3
      2208937.74     13192796.85      2209537.72     13192496.86
      2209837.71     13191896.87
#Sta/Elev= 30
  4329.2  372.46    4441  369.15  4463.3  367.85  4485.7  367.99  4499.7  366.91
  4611.5  363.38  4700.9  359.36  4784.8  357.24  4843.3  357.01  4932.9  356.22
  5008.4  356.96  5019.4  356.18  5022.1  355.68  5025.4  356.18  5030.7  356.81
  5102.9  357.11  5156.5  358.58  5259.9  360.03  5349.4  363.05  5388.5  365.74
  5402.5  365.76  5410.9  366.77  5469.6  368.63  5522.7  371.46  5528.3  371.15
    5559  373.47    5573  373.58  5634.5  376.53  5648.5  378.02  5670.8  378.67
#Mann= 5 ,-1 , 0
  4329.2      .1       0  4843.3     .12       0  5019.4     .07       0
  5025.4     .12       0  5102.9      .1       0
Bank Sta=5019.4,5025.4
XS Rating Curve= 0 ,0
Exp/Cntr=0.3,0.1

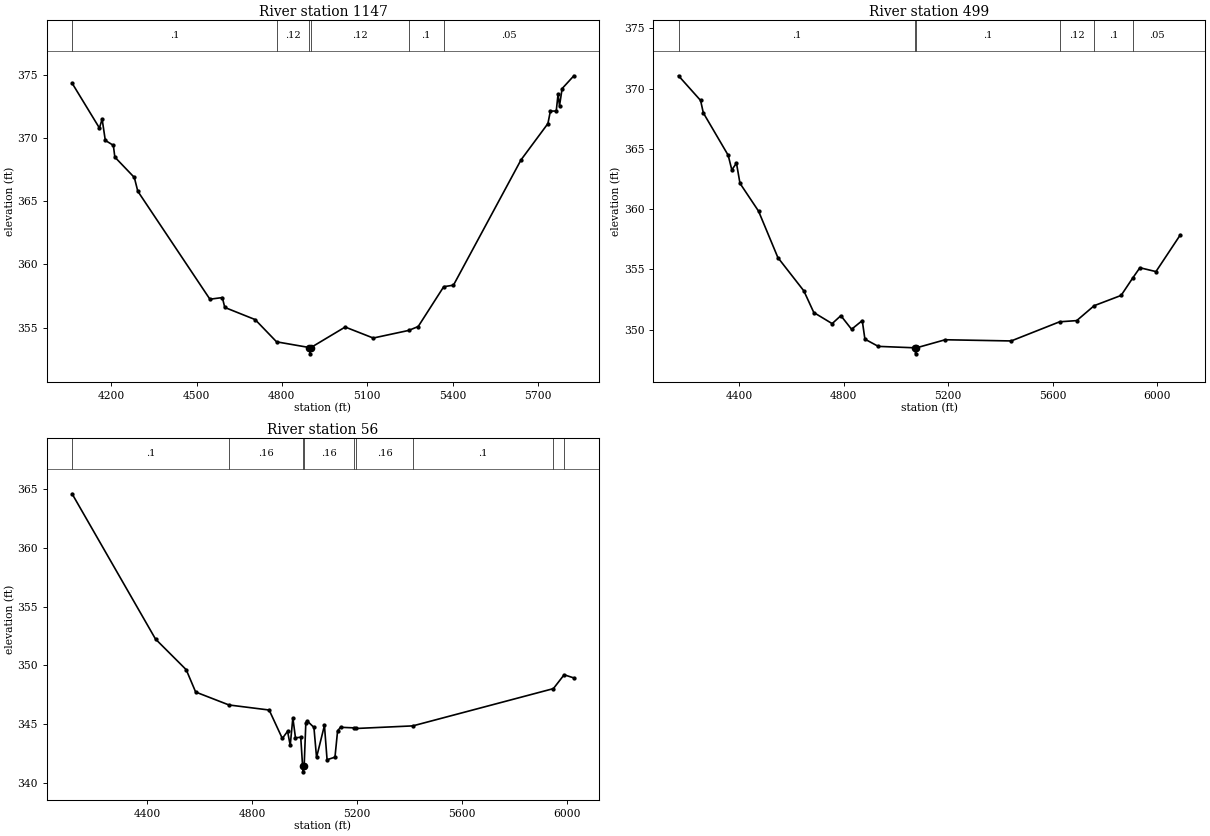
Type RM Length L Ch R = 1 ,1147    ,648,648,648
BEGIN DESCRIPTION:
Mapping XS 7ec78919
END DESCRIPTION:
XS GIS Cut Line= 4
      2208875.16     13192852.38      2209343.88     13192982.59
      2209812.63     13192644.04      2209986.25     13191966.94
#Sta/Elev= 30
  4062.6  374.33  4158.7  370.78  4168.3  371.48  4179.4   369.8  4207.7  369.41
  4212.9  368.48  4281.4  366.87  4293.6  365.78  4547.1  357.24  4590.8  357.37
  4599.3  356.59    4706  355.63  4781.4  353.87  4896.2  353.42  4898.9  352.92
  4902.2  353.42  5022.5  355.04  5121.2  354.17  5245.5  354.77  5279.2  355.08
  5368.9  358.23  5403.1  358.35  5640.6  368.26  5735.1  371.13  5743.8  372.12
  5764.4  372.12  5770.7  373.44  5775.9  372.54  5785.1   373.9  5826.3  374.91
#Mann= 6 ,-1 , 0
  4062.6      .1       0  4781.4     .12       0  4896.2     .07       0
  4902.2     .12       0  5245.5      .1       0  5368.9     .05       0
Bank Sta=4896.2,4902.2
XS Rating Curve= 0 ,0
Exp/Cntr=0.3,0.1

Type RM Length L Ch R = 1 ,499     ,443,443,443
BEGIN DESCRIPTION:
Mapping XS 8af75217
END DESCRIPTION:
XS GIS Cut Line= 4
      2208817.97     13193096.04      2209347.48     13193278.33
      2209929.08     13193152.46      2210102.68     13192405.96
#Sta/Elev= 30
  4167.4  371.07  4251.9  369.02  4262.3  367.99  4357.5  364.47  4371.5  363.25
  4389.2  363.82  4402.7  362.14  4473.8  359.83  4547.9  355.97  4647.2  353.21
  4685.4  351.41  4755.6  350.49    4789  351.15    4830  350.02  4870.9  350.74
  4881.1   349.2  4932.3   348.6  5072.5  348.48  5075.3  347.98  5078.5  348.48
  5188.4  349.15  5441.2  349.05  5626.6  350.64  5692.2  350.74  5759.1  351.98
  5862.1  352.83  5906.4  354.27    5934  355.13  5995.6  354.81  6088.9  357.86
#Mann= 6 ,-1 , 0
  4167.4      .1       0  5072.5     .07       0  5078.5      .1       0
  5626.6     .12       0  5759.1      .1       0  5906.4     .05       0
Bank Sta=5072.5,5078.5
XS Rating Curve= 0 ,0
Exp/Cntr=0.3,0.1

Type RM Length L Ch R = 1 ,56      ,0,0,0
BEGIN DESCRIPTION:
UNT 153 IN LACR 1.0
END DESCRIPTION:
XS GIS Cut Line= 5
      2208865.68     13193256.61      2209395.22     13193612.53
      2209824.91     13193577.81      2210024.56     13193417.22
      2210150.43     13192844.33
#Sta/Elev= 30
  4114.4   364.6  4432.3  352.24  4549.3  349.63  4585.3  347.73  4712.2  346.63
  4865.3   346.2  4915.5  343.78  4935.5  344.39  4945.6  343.19  4955.6  345.53
  4965.6  343.84  4985.7  343.88  4992.7  341.44  4995.5  340.94  4998.7  341.44
    5005  345.06    5010  345.28  5035.9  344.72  5045.9  342.17    5076  344.89
    5086  341.97  5116.1  342.19  5126.1  344.43  5137.3  344.73    5190  344.68
  5197.6  344.63  5412.6  344.85  5948.2  348.02  5989.2   349.2  6026.3  348.93
#Mann= 9 ,-1 , 0
  4114.4      .1       0  4712.2     .16       0  4992.7     .07       0
  4998.7     .16       0    5190      .1       0  5197.6     .16       0
  5412.6      .1       0  5948.2     .12       0  5989.2      .1       0
Bank Sta=4992.7,4998.7
XS Rating Curve= 0 ,0
Exp/Cntr=0.3,0.1