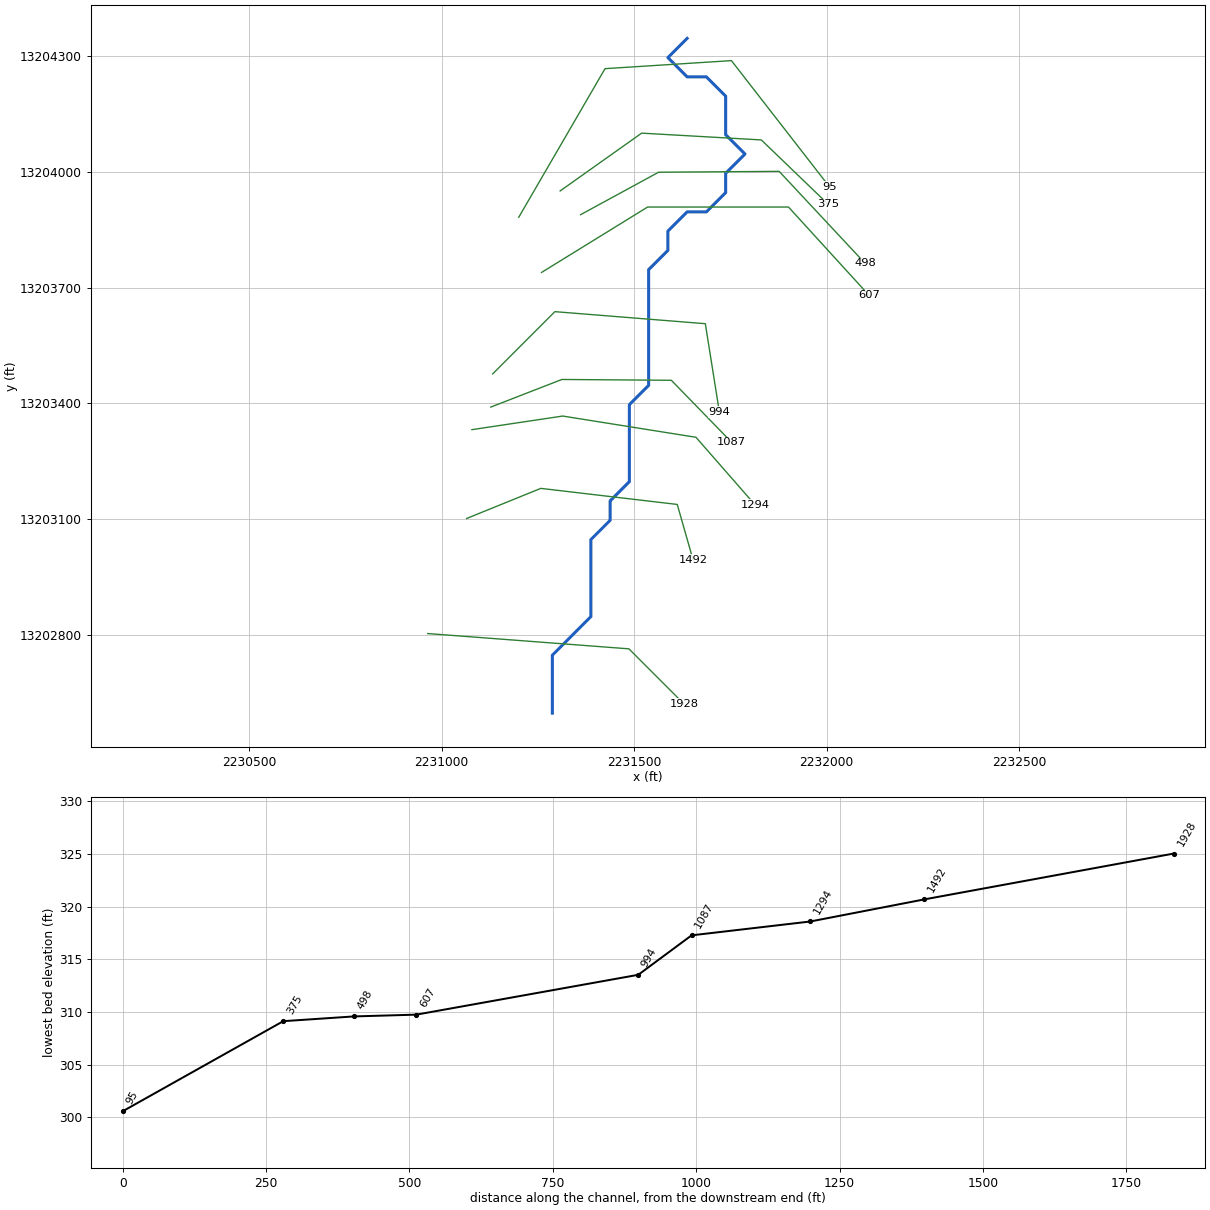
--- UNT 157 IN LACR.prj (project) ---

Proj Title=UNT 157 IN LACR Base Level Engineering
Current Plan=p01
Default Exp/Contr=0.3,0.1
English Units
Geom File=g01
Flow File=f01
Plan File=p01
Y Axis Title=Elevation
X Axis Title(PF)=Main Channel Distance
X Axis Title(XS)=Station
BEGIN DESCRIPTION:
UNT 157 IN LACR
END DESCRIPTION:
DSS Export Rating Curves= 0
DSS Export Rating Curve Sorted= 0
DSS Export Volume Flow Curves= 0
DXF OffsetX= 0
DXF OffsetY= 0
DXF ScaleX= 1
DXF ScaleY= 10

--- UNT 157 IN LACR.p01 (plan) ---

Plan Title=Multiple Run
Short Identifier=Multiple
Geom File=g01
Flow File=f01
Subcritical Flow
K Sum by GR= 0
Std Step Tol= 0.01
Critical Tol= 0.01
Num of Std Step Trials= 20
Max Error Tol= 0.3
Flow Tol Ratio= 0.001
Split Flow NTrial= 30
Split Flow Tol= 0.02
Split Flow Ratio= 0.02
Log Output Level= 0
Friction Slope Method= 1
Unsteady Friction Slope Method= 2
Unsteady Bridges Friction Slope Method= 1
Parabolic Critical Depth
Global Vel Dist=  1 , 1 , 1
Global Log Level= 0
CheckData=True
Encroach Param= -1, 0, 0, 0
BEGIN DESCRIPTION:
Multiple Run
END DESCRIPTION:

--- UNT 157 IN LACR.f01 (steady flow) ---

Flow Title=Multiple
Program Version=4.10
Number of Profiles= 7
Profile Names=10-year,25-year,50-year,1pct_min,100-year,1pct_plu,500-year
River Rch & RM=UNT 157 IN LACR,Reach-1         ,1928
      45      56      65      55      74     100      99
Boundary for River Rch & Prof#=UNT 157 IN LACR,Reach-1         , 1
Up Type= 0
Dn Type= 3
Dn Slope=0.005
Boundary for River Rch & Prof#=UNT 157 IN LACR,Reach-1         , 2
Up Type= 0
Dn Type= 3
Dn Slope=0.005
Boundary for River Rch & Prof#=UNT 157 IN LACR,Reach-1         , 3
Up Type= 0
Dn Type= 3
Dn Slope=0.005
Boundary for River Rch & Prof#=UNT 157 IN LACR,Reach-1         , 4
Up Type= 0
Dn Type= 3
Dn Slope=0.005
Boundary for River Rch & Prof#=UNT 157 IN LACR,Reach-1         , 5
Up Type= 0
Dn Type= 3
Dn Slope=0.005
Boundary for River Rch & Prof#=UNT 157 IN LACR,Reach-1         , 6
Up Type= 0
Dn Type= 3
Dn Slope=0.005
Boundary for River Rch & Prof#=UNT 157 IN LACR,Reach-1         , 7
Up Type= 0
Dn Type= 3
Dn Slope=0.005
DSS Import GetInterval= 0
DSS Import GetPeak= 0
DSS Import FillOption= 0

--- UNT 157 IN LACR.g01 (geometry) ---

Geom Title=Existing Conditions
Program Version=4.10

River Reach=UNT 157 IN LACR ,Reach-1
Reach XY= 24
      2231287.72     13202596.85      2231287.72     13202746.85
      2231337.72     13202796.86      2231387.72     13202846.85
      2231387.72     13203046.85      2231437.72     13203096.85
      2231437.72     13203146.86      2231487.72     13203196.85
      2231487.72     13203396.85      2231537.72     13203446.85
      2231537.72     13203746.85      2231587.72     13203796.86
      2231587.72     13203846.85      2231637.72     13203896.85
      2231687.72     13203896.85      2231737.72     13203946.86
      2231737.72     13203996.85      2231787.72     13204046.85
      2231737.72     13204096.85      2231737.72     13204196.85
      2231687.72     13204246.85      2231637.72     13204246.85
      2231587.72     13204296.86      2231637.72     13204346.85

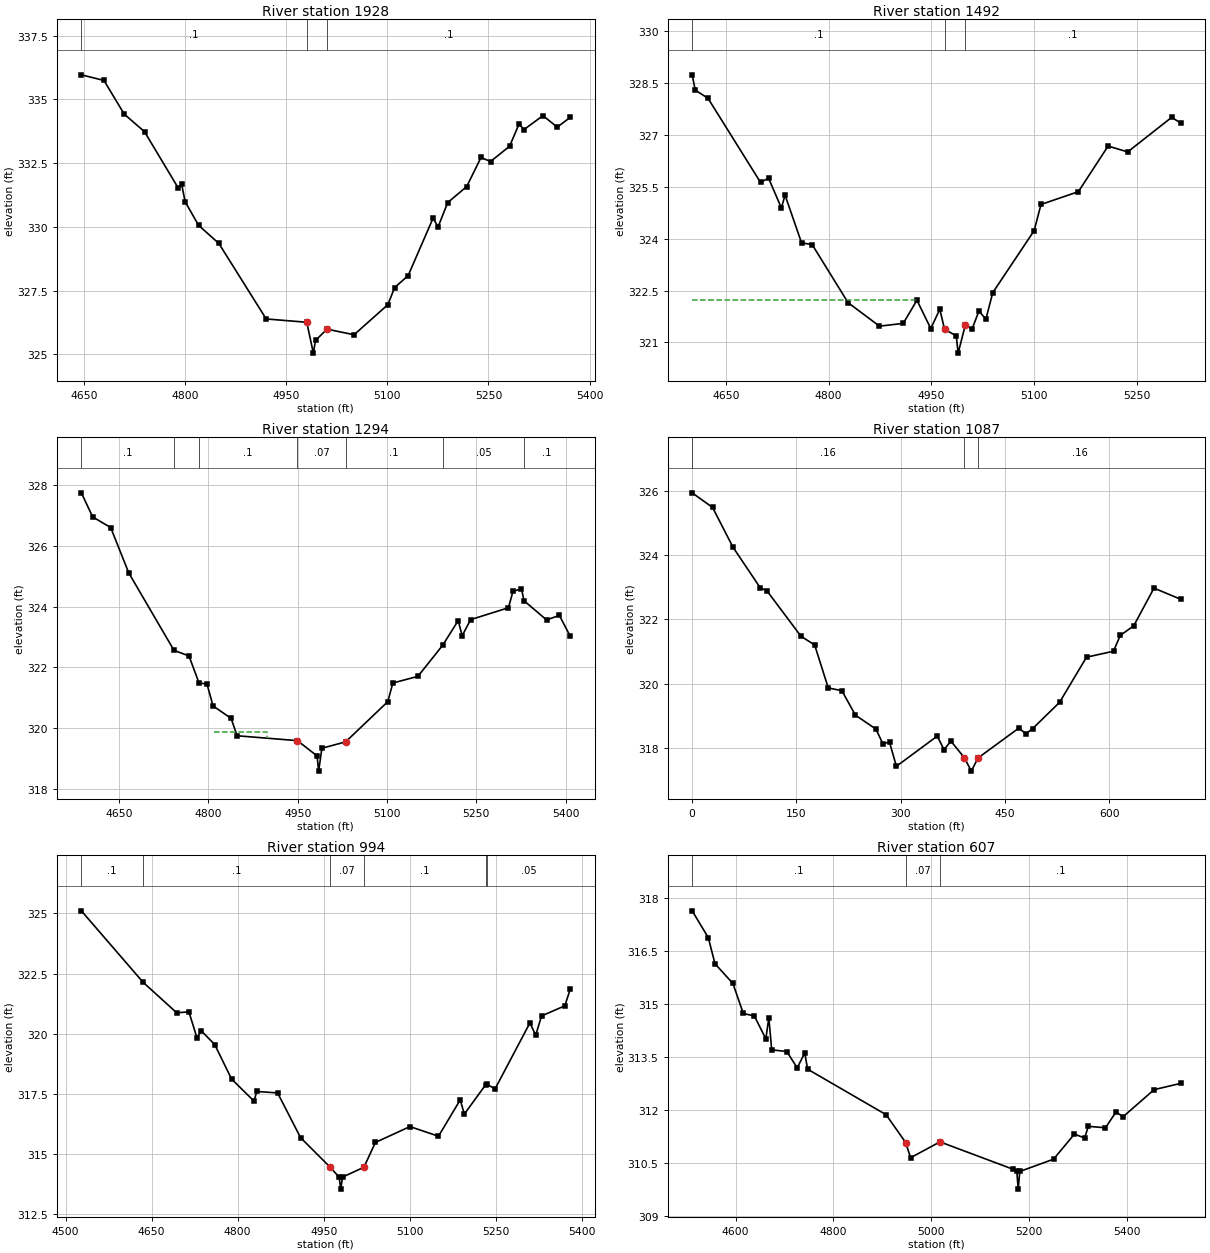
Type RM Length L Ch R = 1 ,1928    ,436,436,436
BEGIN DESCRIPTION:
UNT 157 IN LACR 3.0
END DESCRIPTION:
XS GIS Cut Line= 3
       2230964.3     13202803.12      2231486.56     13202763.46
        2231629.     13202621.02
#Sta/Elev= 30
  4646.1  335.96  4679.6  335.74  4709.7  334.42  4739.8  333.73  4789.9  331.52
  4794.9  331.67    4800  330.99    4820  330.06  4850.1  329.35  4920.3  326.39
  4980.5  326.26  4990.3  325.05  4993.5  325.55  5010.6  325.99  5050.7  325.77
  5100.8  326.95  5110.9  327.62  5130.9  328.09  5167.9  330.34  5175.4     330
  5189.5  330.95  5217.8  331.58    5239  332.72  5253.1  332.56  5281.4  333.16
  5295.6  334.04  5302.6  333.81  5330.9  334.36  5352.1  333.91  5371.3  334.29
#Mann= 3 , 0 , 0
  4646.1      .1       0  4980.5     .07       0  5010.6      .1       0
Bank Sta=4980.5,5010.6
XS Rating Curve= 0 ,0
Exp/Cntr=0.3,0.1

Type RM Length L Ch R = 1 ,1492    ,198,198,198
BEGIN DESCRIPTION:
UNT 157 IN LACR 2.0
END DESCRIPTION:
XS GIS Cut Line= 4
      2231065.15     13203101.51      2231257.84     13203179.63
      2231612.01     13203137.96      2231653.21     13202993.76
#Sta/Elev= 30
  4600.5  328.74    4605   328.3  4623.7  328.06  4700.4  325.63  4712.2  325.75
  4730.9  324.89  4736.3  325.26  4760.4  323.88  4775.9  323.83  4828.4  322.15
  4874.3  321.47    4909  321.55  4929.1  322.22  4949.3   321.4  4962.5  321.96
  4969.4  321.38  4986.5  321.19  4989.3  320.69  4999.6  321.49  5009.7  321.39
  5019.7  321.91  5029.8  321.67  5039.9  322.44  5100.3  324.23  5110.4  324.99
    5165  325.36  5208.5  326.68  5237.1  326.51  5301.4  327.51    5315  327.34
#Mann= 3 , 0 , 0
  4600.5      .1       0  4969.4     .07       0  4999.6      .1       0
#XS Ineff= 2 , 0
       0 4928.18  322.24               0
Permanent Ineff=
       T       F
Bank Sta=4969.4,4999.6
XS Rating Curve= 0 ,0
Exp/Cntr=0.3,0.1

Type RM Length L Ch R = 1 ,1294    ,207,207,207
BEGIN DESCRIPTION:
Mapping XS 1ddc8b72
END DESCRIPTION:
XS GIS Cut Line= 4
      2231078.92     13203331.95      2231314.69      13203367.2
      2231660.63     13203312.12      2231813.81     13203137.06
#Sta/Elev= 30
  4586.4  327.73  4605.4  326.94  4635.7  326.59  4666.1   325.1  4742.1  322.56
  4767.2  322.38  4784.1  321.49  4797.5  321.46  4807.6  320.74    4838  320.33
  4848.1  319.76  4949.4   319.6  4982.4   319.1  4985.1   318.6  4990.5  319.35
  5030.4  319.56  5101.3  320.88  5109.7  321.49  5151.9  321.71  5193.5  322.73
  5219.6  323.54  5226.2  323.04  5240.4  323.57    5304  323.96  5311.6   324.5
  5325.9  324.58  5330.1  324.19  5368.1  323.56  5389.5  323.71  5407.7  323.03
#Mann= 7 ,-1 , 0
  4586.4      .1       0  4742.1     .05       0  4784.1      .1       0
  4949.4     .07       0  5030.4      .1       0  5193.5     .05       0
  5330.1      .1       0
#XS Ineff= 1 ,-1
 4809.39  4898.9   319.9
Permanent Ineff=
       F
Bank Sta=4949.4,5030.4
XS Rating Curve= 0 ,0
Exp/Cntr=0.3,0.1

Type RM Length L Ch R = 1 ,1087    ,93,93,93
XS GIS Cut Line= 4
     2231127.993     13203390.47     2231312.455    13203462.084
     2231596.743    13203459.914     2231752.993    13203299.324
#Sta/Elev= 30
       0 325.93429.37814325.479258.75629 324.24597.92714322.9852107.7199322.8873
156.6834321.4756176.2689321.2089195.8543 319.873215.4605319.7849235.0667319.0236
264.4761318.5933274.2792318.1442284.0823318.1837293.8854317.4358352.7041318.3751
362.5072317.9533372.3103318.2203391.9165317.6989401.7196317.2866411.5228317.6971
470.3414318.6272480.1446318.4444489.8549318.6052528.6961319.4217567.5374 320.827
606.3787321.0124616.0889321.5027635.5096321.8028664.6405322.9729703.4818322.6232
#Mann= 3 , 0 , 0
       0     .16       0391.9165     .07       0411.5228     .16       0
#XS Ineff= 2 , 0
          353.06  318.35
Permanent Ineff=
       F       F
Bank Sta=391.9165,411.5228
XS Rating Curve= 0 ,0
Exp/Cntr=0.3,0.1

Type RM Length L Ch R = 1 ,994     ,387,387,387
BEGIN DESCRIPTION:
Mapping XS 4ff06c99
END DESCRIPTION:
XS GIS Cut Line= 4
      2231132.87     13203476.53       2231294.3     13203637.96
      2231684.92     13203606.71      2231721.38     13203377.57
#Sta/Elev= 30
  4527.5  325.11  4635.1  322.14  4693.8  320.87    4715  320.91  4729.2  319.82
  4736.2  320.13    4760  319.55  4789.3  318.12  4828.4   317.2  4833.4   317.6
  4869.6  317.54  4909.7  315.68  4961.3  314.45  4976.9  314.04  4979.7  313.54
  4982.9  314.04  5020.1  314.45  5040.1  315.48  5100.3  316.14  5150.1  315.74
    5188  317.25  5195.2  316.66  5232.4  317.88    5235  317.89  5248.8  317.71
  5309.5  320.45  5319.6  319.94  5329.8  320.74  5370.3  321.16  5379.7  321.84
#Mann= 6 ,-1 , 0
  4527.5      .1       0  4635.1      .1       0  4961.3     .07       0
  5020.1      .1       0  5232.4      .1       0    5235     .05       0
Bank Sta=4961.3,5020.1
XS Rating Curve= 0 ,0
Exp/Cntr=0.3,0.1

Type RM Length L Ch R = 1 ,607     ,109,109,109
BEGIN DESCRIPTION:
Mapping XS 10e10138
END DESCRIPTION:
XS GIS Cut Line= 4
      2231259.58     13203739.57      2231535.04     13203909.25
      2231900.81     13203909.25      2232109.35     13203680.95
#Sta/Elev= 30
  4511.4  317.65  4544.4  316.89    4558  316.15  4594.7  315.59  4615.9  314.74
  4638.4  314.67  4661.9  314.02    4668  314.62  4673.9  313.71  4704.7  313.66
    4726   313.2  4741.4  313.62  4747.3  313.16  4907.6  311.87  4947.6  311.08
  4957.6  310.65  5017.6   311.1  5167.6  310.32  5174.6  310.26  5177.4  309.76
  5180.6  310.26  5249.7  310.61  5292.2  311.32  5313.2  311.21  5320.6  311.54
  5355.7   311.5  5377.3  311.95  5391.5  311.81    5455  312.58  5509.9  312.76
#Mann= 3 , 0 , 0
  4511.4      .1       0  4947.6     .07       0  5017.6      .1       0
#XS Ineff= 1 ,-1
 5019.89 5326.52  311.06
Permanent Ineff=
       T
Bank Sta=4947.6,5017.6
XS Rating Curve= 0 ,0
Exp/Cntr=0.3,0.1

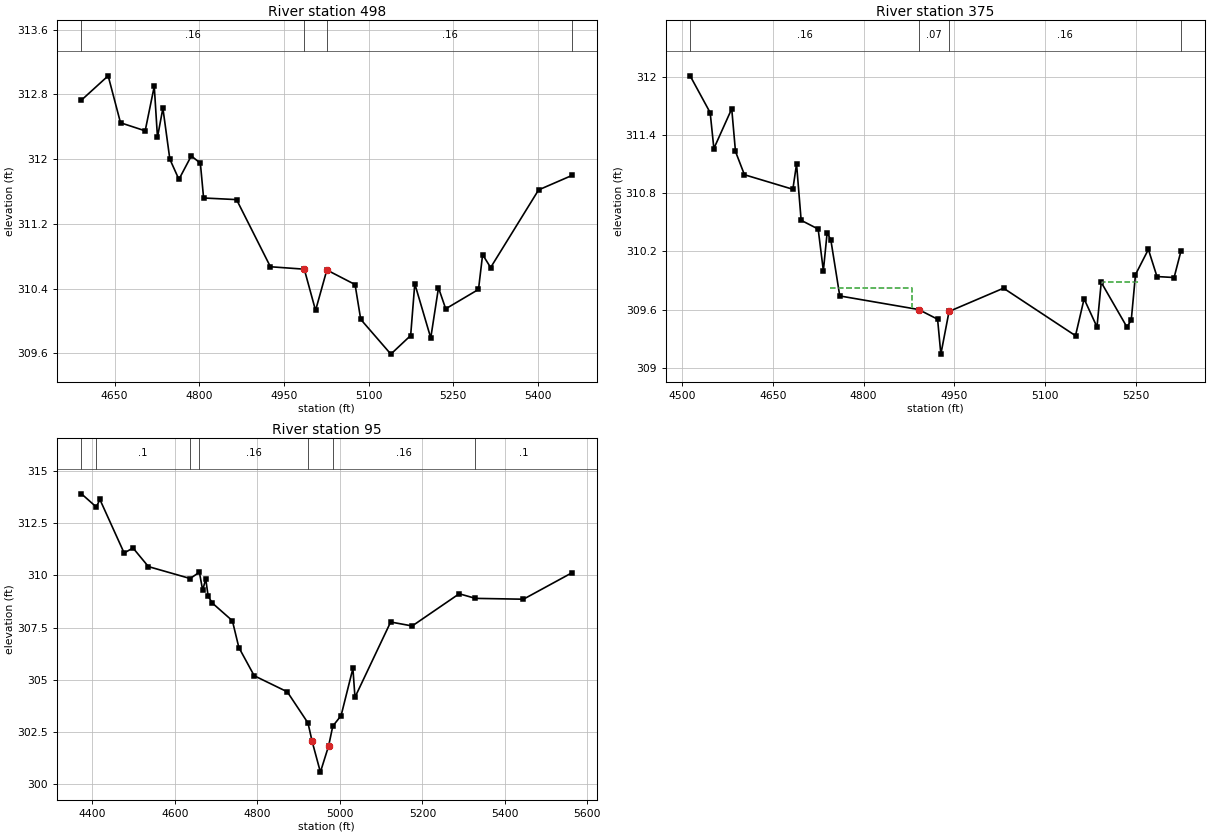
Type RM Length L Ch R = 1 ,498     ,123,123,123
BEGIN DESCRIPTION:
Mapping XS e1d932b5
END DESCRIPTION:
XS GIS Cut Line= 4
      2231360.93      13203889.4      2231563.68     13203999.59
      2231876.57      13204001.8      2232099.13     13203763.81
#Sta/Elev= 30
  4591.2  312.73  4638.5  313.03  4660.4  312.45  4704.1  312.35  4720.2   312.9
  4725.9  312.27  4735.5  312.63  4747.8     312  4763.9  311.75  4785.8  312.04
  4801.9  311.95  4807.6  311.52    4866   311.5    4926  310.67    4986  310.64
    5006  310.13    5026  310.63    5076  310.45    5086  310.02  5139.4  309.59
  5174.5  309.82  5181.8  310.46  5210.1  309.79  5223.8  310.41  5236.6  310.15
  5294.7  310.39    5302  310.82  5316.2  310.66  5401.2  311.62  5460.7   311.8
#Mann= 4 ,-1 , 0
  4591.2     .16       0    4986     .07       0    5026     .16       0
  5460.7      .1       0
#XS Ineff= 1 ,-1
 5028.18 5321.55  310.59
Permanent Ineff=
       T
Bank Sta=4986,5026
XS Rating Curve= 0 ,0
Exp/Cntr=0.3,0.1

Type RM Length L Ch R = 1 ,375     ,280,280,280
BEGIN DESCRIPTION:
Mapping XS 13005262
END DESCRIPTION:
XS GIS Cut Line= 4
      2231308.06      13203951.1      2231519.61     13204100.95
       2231830.3     13204083.32      2232003.52     13203916.68
#Sta/Elev= 30
  4513.5  312.01  4546.6  311.63  4552.7  311.26  4582.2  311.67  4588.4  311.23
  4603.2  310.99  4683.2  310.84  4689.3   311.1  4696.9  310.52    4725  310.43
  4733.6     310  4739.8  310.39  4745.9  310.32  4760.7  309.74    4891   309.6
 4922.33   309.5 4927.74  309.14 4941.27  309.58  5031.3  309.82  5150.2  309.33
  5164.4  309.71  5185.7  309.42  5192.7  309.88  5235.1  309.42  5242.3  309.49
  5249.3  309.96  5270.6  310.22  5284.8  309.94  5313.1  309.93  5324.3   310.2
#Mann= 4 ,-1 , 0
  4513.5     .16       0    4891     .07       0 4941.27     .16       0
  5324.3      .1       0
#XS Ineff= 3 ,-1
  4745.3 4879.28  309.82 5031.22 5192.82  309.81  5194.2 5254.97  309.88
Permanent Ineff=
       T       T       T
Bank Sta=4891,4941.27
XS Rating Curve= 0 ,0
Exp/Cntr=0.3,0.1

Type RM Length L Ch R = 1 ,95      ,0,0,0
BEGIN DESCRIPTION:
UNT 157 IN LACR 1.0
END DESCRIPTION:
XS GIS Cut Line= 4
      2231200.53     13203882.73      2231424.51     13204268.17
      2231752.63       13204289.      2232007.49     13203961.33
#Sta/Elev= 30
  4373.4   313.9  4409.4  313.27  4418.1  313.63  4476.9  311.07  4498.4  311.31
  4535.7  310.42  4636.9  309.85  4659.3  310.15  4667.3  309.29  4674.7  309.83
  4680.5  309.01  4690.4  308.68  4739.3  307.83    4755  306.55  4792.2   305.2
  4872.4  304.43  4922.6  302.94  4932.6  302.06  4952.7  300.59  4972.7  301.85
  4982.7  302.79  5002.8  303.29  5031.5  305.55  5036.5  304.17    5123  307.77
  5175.2  307.58  5289.2  309.12  5328.6   308.9  5444.9  308.86  5563.1  310.13
#Mann= 7 ,-1 , 0
  4373.4     .05       0  4409.4      .1       0  4636.9     .05       0
  4659.3     .16       0  4922.6     .07       0  4982.7     .16       0
  5328.6      .1       0
Bank Sta=4932.6,4972.7
XS Rating Curve= 0 ,0
Exp/Cntr=0.3,0.1

Chan Stop Cuts=-1
Use User Specified Reach Order=0
Composite Channel Slope=5