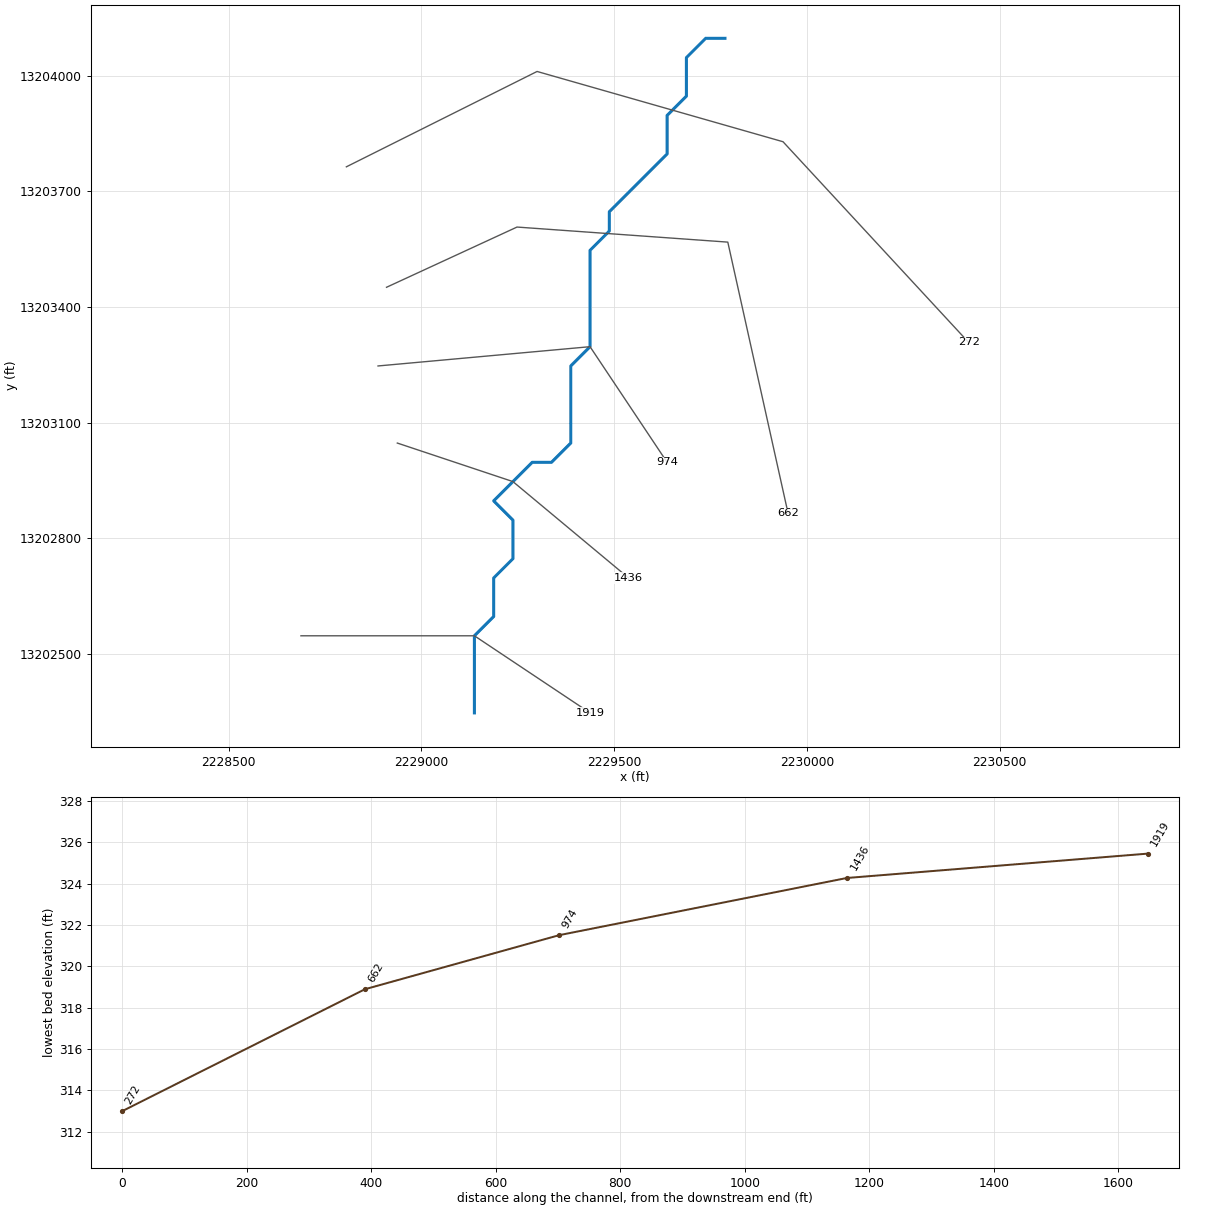
--- UNT 158 IN LACR.prj (project) ---

Proj Title=UNT 158 IN LACR Base Level Engineering
Current Plan=p01
Default Exp/Contr=0.3,0.1
English Units
Geom File=g01
Flow File=f01
Plan File=p01
Y Axis Title=Elevation
X Axis Title(PF)=Main Channel Distance
X Axis Title(XS)=Station
BEGIN DESCRIPTION:
UNT 158 IN LACR
END DESCRIPTION:
DSS Export Rating Curves= 0
DSS Export Rating Curve Sorted= 0
DSS Export Volume Flow Curves= 0
DXF OffsetX= 0
DXF OffsetY= 0
DXF ScaleX= 1
DXF ScaleY= 10

--- UNT 158 IN LACR.p01 (plan) ---

Plan Title=Multiple Run
Short Identifier=Multiple
Geom File=g01
Flow File=f01
Subcritical Flow
K Sum by GR= 0
Std Step Tol= 0.01
Critical Tol= 0.01
Num of Std Step Trials= 20
Max Error Tol= 0.3
Flow Tol Ratio= 0.001
Split Flow NTrial= 30
Split Flow Tol= 0.02
Split Flow Ratio= 0.02
Log Output Level= 0
Friction Slope Method= 1
Unsteady Friction Slope Method= 2
Unsteady Bridges Friction Slope Method= 1
Parabolic Critical Depth
Global Vel Dist=  1 , 1 , 1
Global Log Level= 0
CheckData=True
Encroach Param= -1, 0, 0, 0
BEGIN DESCRIPTION:
Multiple Run
END DESCRIPTION:

--- UNT 158 IN LACR.f01 (steady flow) ---

Flow Title=Multiple
Number of Profiles=7
Profile Names=10-year,25-year,50-year,1pct_min,100-year,1pct_plu,500-year
River Rch & RM= UNT 158 IN LACR,Reach-1,1919
     106     141     168     148     201     271     290
Boundary for River Rch & Prof#=UNT 158 IN LACR,Reach-1,1
Up Type=0
Dn Type=3
Dn Slope=0.005
Boundary for River Rch & Prof#=UNT 158 IN LACR,Reach-1,2
Up Type=0
Dn Type=3
Dn Slope=0.005
Boundary for River Rch & Prof#=UNT 158 IN LACR,Reach-1,3
Up Type=0
Dn Type=3
Dn Slope=0.005
Boundary for River Rch & Prof#=UNT 158 IN LACR,Reach-1,4
Up Type=0
Dn Type=3
Dn Slope=0.005
Boundary for River Rch & Prof#=UNT 158 IN LACR,Reach-1,5
Up Type=0
Dn Type=3
Dn Slope=0.005
Boundary for River Rch & Prof#=UNT 158 IN LACR,Reach-1,6
Up Type=0
Dn Type=3
Dn Slope=0.005
Boundary for River Rch & Prof#=UNT 158 IN LACR,Reach-1,7
Up Type=0
Dn Type=3
Dn Slope=0.005

--- UNT 158 IN LACR.g01 (geometry) ---

Geom Title=Existing Conditions
Program Version=4.10

River Reach=UNT 158 IN LACR ,Reach-1
Reach XY= 24
      2229137.72     13202346.85      2229137.72     13202546.85
      2229187.72     13202596.85      2229187.72     13202696.85
      2229237.72     13202746.85      2229237.72     13202846.85
      2229187.72     13202896.85      2229237.72     13202946.85
      2229287.72     13202996.86      2229337.72     13202996.86
      2229387.72     13203046.85      2229387.72     13203246.85
      2229437.72     13203296.86      2229437.72     13203546.85
      2229487.72     13203596.85      2229487.72     13203646.86
      2229537.72     13203696.85      2229587.72     13203746.85
      2229637.72     13203796.86      2229637.72     13203896.85
      2229687.72     13203946.86      2229687.72     13204046.85
      2229737.72     13204096.85      2229787.72     13204096.85

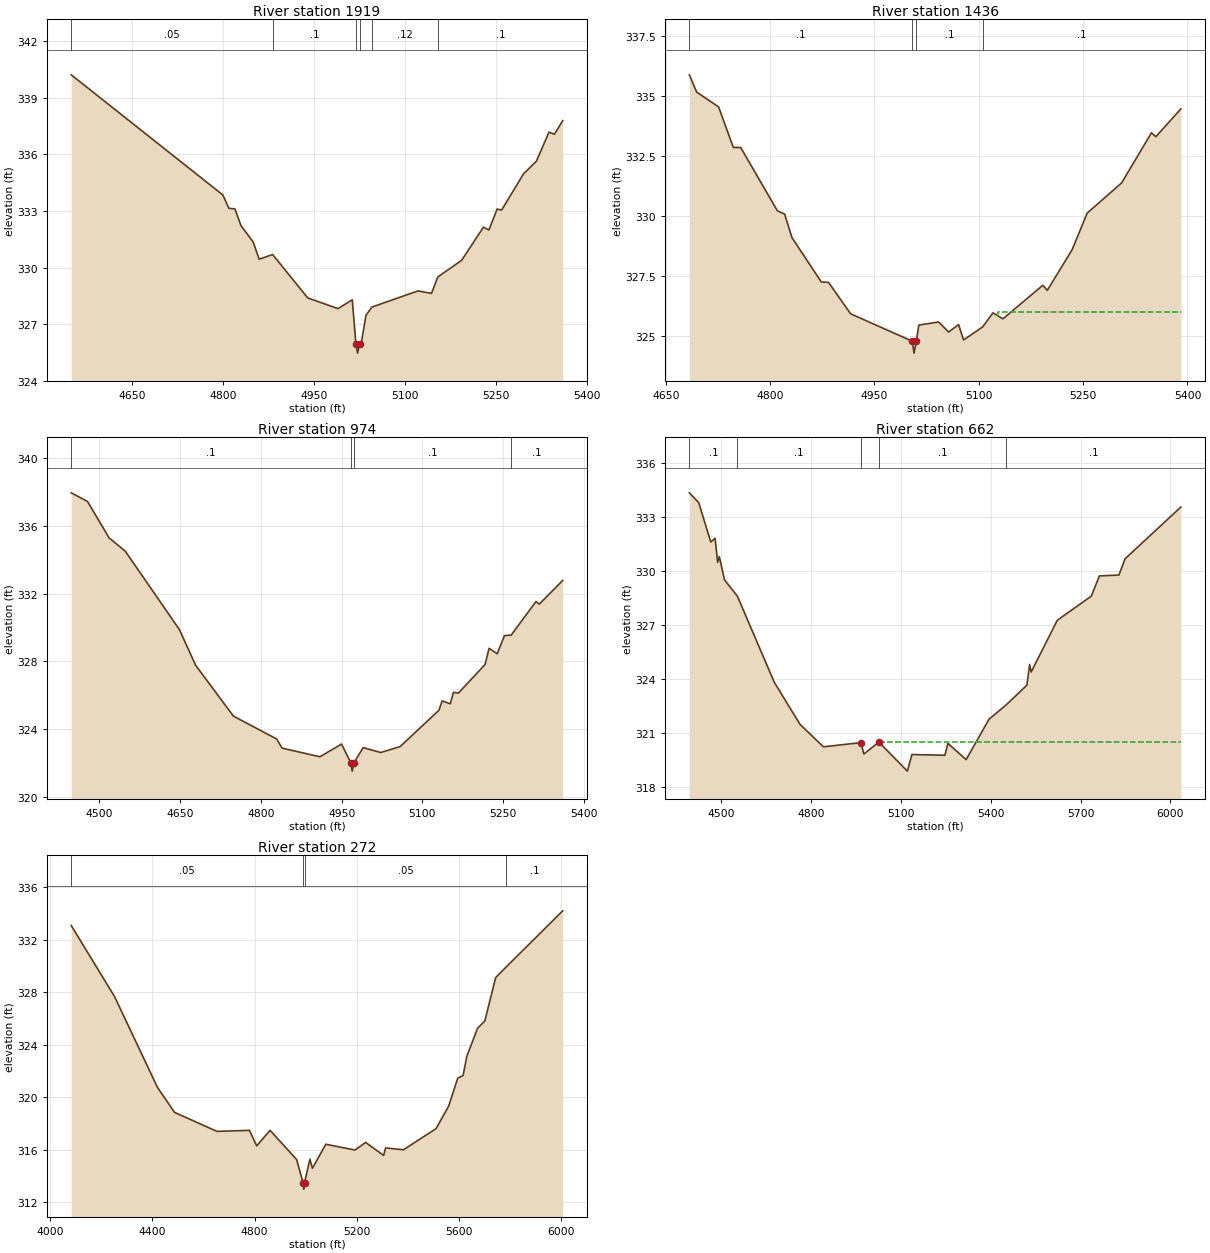
Type RM Length L Ch R = 1 ,1919    ,483,483,483
BEGIN DESCRIPTION:
UNT 158 IN LACR 4.0
END DESCRIPTION:
XS GIS Cut Line= 3
      2228687.72     13202546.85      2229137.72     13202546.85
      2229437.76     13202346.83
#Sta/Elev= 30
    4550  340.22    4800  333.85    4810  333.14    4820  333.11    4830  332.22
    4850  331.36    4860  330.44  4882.2  330.69    4940  328.39    4990  327.82
  5013.5  328.29  5019.5  325.96  5022.3  325.46  5025.5  325.96  5028.5  326.02
  5036.1  327.46  5045.8   327.9  5121.7  328.76  5144.2  328.63  5154.6   329.5
  5193.8  330.38  5229.9  332.14  5238.9  331.99  5252.4   333.1  5259.9  333.05
    5296  334.97    5317  335.63    5338  337.18    5347  337.07  5360.6  337.79
#Mann= 6 ,-1 , 0
    4550     .05       0  4882.2      .1       0  5019.5     .07       0
  5025.5      .1       0  5045.8     .12       0  5154.6      .1       0
Bank Sta=5019.5,5025.5
XS Rating Curve= 0 ,0
Exp/Cntr=0.3,0.1

Type RM Length L Ch R = 1 ,1436    ,462,462,462
BEGIN DESCRIPTION:
UNT 158 IN LACR 3.0
END DESCRIPTION:
XS GIS Cut Line= 3
      2228937.75     13203046.85      2229237.72     13202946.85
      2229537.71     13202696.86
#Sta/Elev= 30
  4683.8  335.89  4694.3  335.17  4725.9  334.55    4747  332.86  4757.6  332.86
  4810.3  330.22  4820.8  330.08  4831.3   329.1  4873.5  327.25    4884  327.23
  4915.7  325.92  5004.2  324.78  5006.9  324.28  5010.2  324.78  5013.7  325.45
  5042.3  325.58  5056.6  325.16  5070.9  325.47  5078.1  324.83  5105.4  325.37
  5120.4  325.96  5134.7  325.71    5192  327.11  5198.5   326.9  5234.3   328.6
  5255.8  330.12  5305.3  331.38  5348.2  333.47  5354.7  333.31  5390.5  334.47
#Mann= 4 ,-1 , 0
  4683.8      .1       0  5004.2     .03       0  5010.2      .1       0
  5105.4      .1       0
#XS Ineff= 2 , 0
                         5128.12             326
Permanent Ineff=
       F       F
Bank Sta=5004.2,5010.2
XS Rating Curve= 0 ,0
Exp/Cntr=0.3,0.1

Type RM Length L Ch R = 1 ,974     ,312,312,312
BEGIN DESCRIPTION:
UNT 158 IN LACR 2.0
END DESCRIPTION:
XS GIS Cut Line= 3
      2228887.69     13203246.85      2229437.72     13203296.86
      2229637.75     13202996.82
#Sta/Elev= 30
  4447.7  337.96  4477.9  337.45    4518   335.3  4548.1  334.51  4648.6  329.88
  4678.7  327.77    4749  324.76  4829.3  323.41  4839.3  322.87  4909.6  322.36
  4949.8  323.11  4966.9  322.01  4969.6  321.51  4972.9  322.01    4990   322.9
  5022.5  322.61  5058.6  322.96  5130.7  325.11  5136.7  325.66  5151.7  325.49
  5157.7  326.17  5166.8  326.12  5216.3  327.81  5223.8  328.77  5238.9  328.45
  5252.4  329.52  5264.9  329.55    5311  331.54    5317  331.38  5360.6  332.78
#Mann= 4 ,-1 , 0
  4447.7      .1       0  4966.9     .03       0  4972.9      .1       0
  5264.9      .1       0
Bank Sta=4966.9,4972.9
XS Rating Curve= 0 ,0
Exp/Cntr=0.3,0.1

Type RM Length L Ch R = 1 ,662     ,390,390,390
BEGIN DESCRIPTION:
Mapping XS e567e07c
END DESCRIPTION:
XS GIS Cut Line= 4
      2228909.72     13203450.96      2229248.24      13203607.2
      2229795.11     13203568.13      2229951.37     13202864.99
#Sta/Elev= 30
  4393.4  334.33  4424.6  333.79    4465   331.6  4479.3  331.81  4487.9  330.47
  4493.4  330.79  4510.9   329.5  4553.7   328.6    4677  323.82  4763.2  321.48
  4841.1  320.24  4966.2  320.47  4976.3  319.84  5026.4   320.5  5121.5  318.89
  5136.7  319.81  5246.9  319.77    5257  320.43  5317.7  319.53  5394.2  321.77
  5451.1  322.56  5520.7  323.66  5529.9  324.81    5535  324.39  5622.1  327.26
  5735.8   328.6  5762.9  329.72    5828  329.77  5848.5  330.67  6034.8  333.54
#Mann= 5 ,-1 , 0
  4393.4      .1       0  4553.7      .1       0  4966.2     .03       0
  5026.4      .1       0  5451.1      .1       0
#XS Ineff= 2 , 0
       0                 5026.06       0  320.51
Permanent Ineff=
       F       T
Bank Sta=4966.2,5026.4
XS Rating Curve= 0 ,0
Exp/Cntr=0.3,0.1

Type RM Length L Ch R = 1 ,272     ,0,0,0
BEGIN DESCRIPTION:
UNT 158 IN LACR 1.0
END DESCRIPTION:
XS GIS Cut Line= 4
      2228805.55     13203763.46      2229300.32     13204010.84
      2229938.34     13203828.55      2230420.11     13203307.73
#Sta/Elev= 30
  4081.7  333.07  4251.6  327.65  4419.5  320.74  4486.6  318.83    4653  317.38
  4779.9  317.46  4808.5  316.28    4861  317.46    4965  315.24  4990.1  313.48
  4992.8  312.98  4996.1  313.48    5017  315.26  5026.9  314.57  5079.4   316.4
  5193.8  315.96  5235.4  316.54  5306.2  315.55  5313.6  316.12  5383.9  315.98
  5511.5  317.59  5560.8   319.3  5596.5  321.44  5617.5  321.64  5631.7  323.08
  5674.2  325.24  5702.5  325.79  5745.1   329.1  5786.7  329.92  6007.9  334.19
#Mann= 4 ,-1 , 0
  4081.7     .05       0  4990.1     .03       0  4996.1     .05       0
  5786.7      .1       0
Bank Sta=4990.1,4996.1
XS Rating Curve= 0 ,0
Exp/Cntr=0.3,0.1

Chan Stop Cuts=-1
Use User Specified Reach Order=0
Composite Channel Slope=5