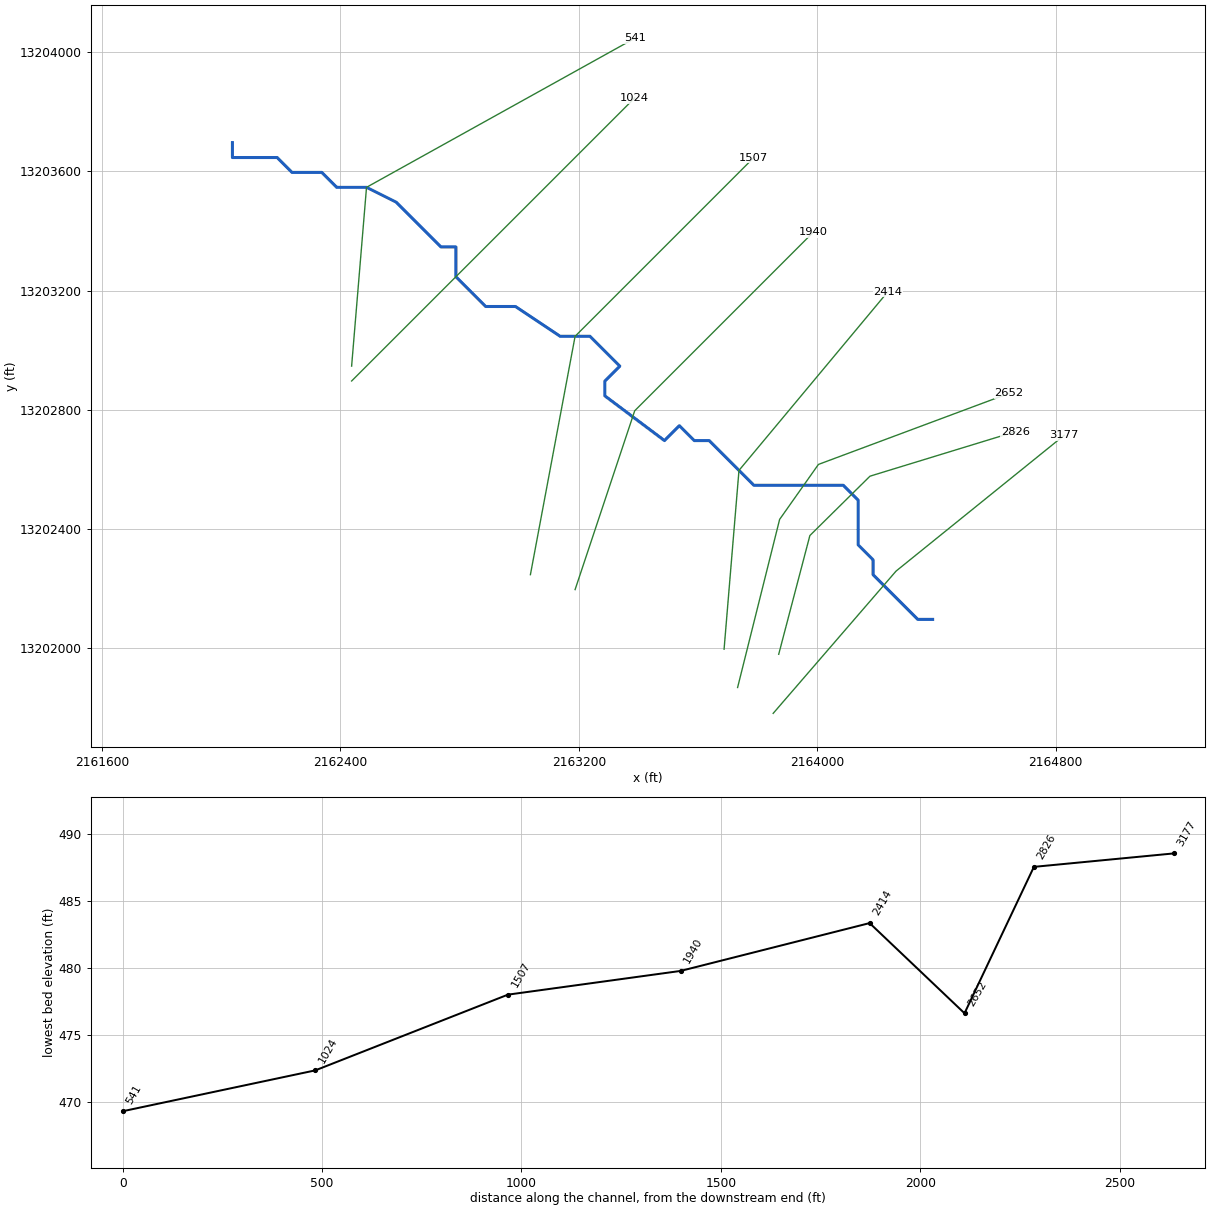
--- UNT 159 IN LACR.prj (project) ---

Proj Title=UNT 159 IN LACR Base Level Engineering
Current Plan=p01
Default Exp/Contr=0.3,0.1
English Units
Geom File=g01
Flow File=f01
Plan File=p01
Y Axis Title=Elevation
X Axis Title(PF)=Main Channel Distance
X Axis Title(XS)=Station
BEGIN DESCRIPTION:
UNT 159 IN LACR
END DESCRIPTION:
DSS Export Rating Curves= 0
DSS Export Rating Curve Sorted= 0
DSS Export Volume Flow Curves= 0
DXF OffsetX= 0
DXF OffsetY= 0
DXF ScaleX= 1
DXF ScaleY= 10

--- UNT 159 IN LACR.p01 (plan) ---

Plan Title=Multiple Run
Short Identifier=Multiple
Geom File=g01
Flow File=f01
Subcritical Flow
K Sum by GR= 0
Std Step Tol= 0.01
Critical Tol= 0.01
Num of Std Step Trials= 20
Max Error Tol= 0.3
Flow Tol Ratio= 0.001
Split Flow NTrial= 30
Split Flow Tol= 0.02
Split Flow Ratio= 0.02
Log Output Level= 0
Friction Slope Method= 1
Unsteady Friction Slope Method= 2
Unsteady Bridges Friction Slope Method= 1
Parabolic Critical Depth
Global Vel Dist=  1 , 1 , 1
Global Log Level= 0
CheckData=True
Encroach Param= -1, 0, 0, 0
BEGIN DESCRIPTION:
Multiple Run
END DESCRIPTION:

--- UNT 159 IN LACR.f01 (steady flow) ---

Flow Title=Multiple
Number of Profiles=7
Profile Names=10-year,25-year,50-year,1pct_min,100-year,1pct_plu,500-year
River Rch & RM= UNT 159 IN LACR,Reach-1,3177
     141     192     234     210     284     384     425
Boundary for River Rch & Prof#=UNT 159 IN LACR,Reach-1,1
Up Type=0
Dn Type=3
Dn Slope=0.005
Boundary for River Rch & Prof#=UNT 159 IN LACR,Reach-1,2
Up Type=0
Dn Type=3
Dn Slope=0.005
Boundary for River Rch & Prof#=UNT 159 IN LACR,Reach-1,3
Up Type=0
Dn Type=3
Dn Slope=0.005
Boundary for River Rch & Prof#=UNT 159 IN LACR,Reach-1,4
Up Type=0
Dn Type=3
Dn Slope=0.005
Boundary for River Rch & Prof#=UNT 159 IN LACR,Reach-1,5
Up Type=0
Dn Type=3
Dn Slope=0.005
Boundary for River Rch & Prof#=UNT 159 IN LACR,Reach-1,6
Up Type=0
Dn Type=3
Dn Slope=0.005
Boundary for River Rch & Prof#=UNT 159 IN LACR,Reach-1,7
Up Type=0
Dn Type=3
Dn Slope=0.005

--- UNT 159 IN LACR.g01 (geometry) ---

Geom Title=Existing Conditions
Program Version=4.10

River Reach=UNT 159 IN LACR ,Reach-1
Reach XY= 30
      2164387.72     13202096.85      2164337.72     13202096.85
      2164187.72     13202246.85      2164187.72     13202296.85
      2164137.72     13202346.85      2164137.72     13202496.86
      2164087.72     13202546.85      2163787.72     13202546.85
      2163637.72     13202696.85      2163587.72     13202696.85
      2163537.72     13202746.85      2163487.72     13202696.85
      2163287.72     13202846.85      2163287.72     13202896.85
      2163337.72     13202946.85      2163237.72     13203046.85
      2163137.72     13203046.85      2162987.72     13203146.86
      2162887.72     13203146.86      2162787.72     13203246.85
      2162787.72     13203346.85      2162737.72     13203346.85
      2162587.72     13203496.85      2162487.72     13203546.85
      2162387.72     13203546.85      2162337.72     13203596.85
      2162237.72     13203596.85      2162187.72     13203646.86
      2162037.72     13203646.86      2162037.72     13203696.85

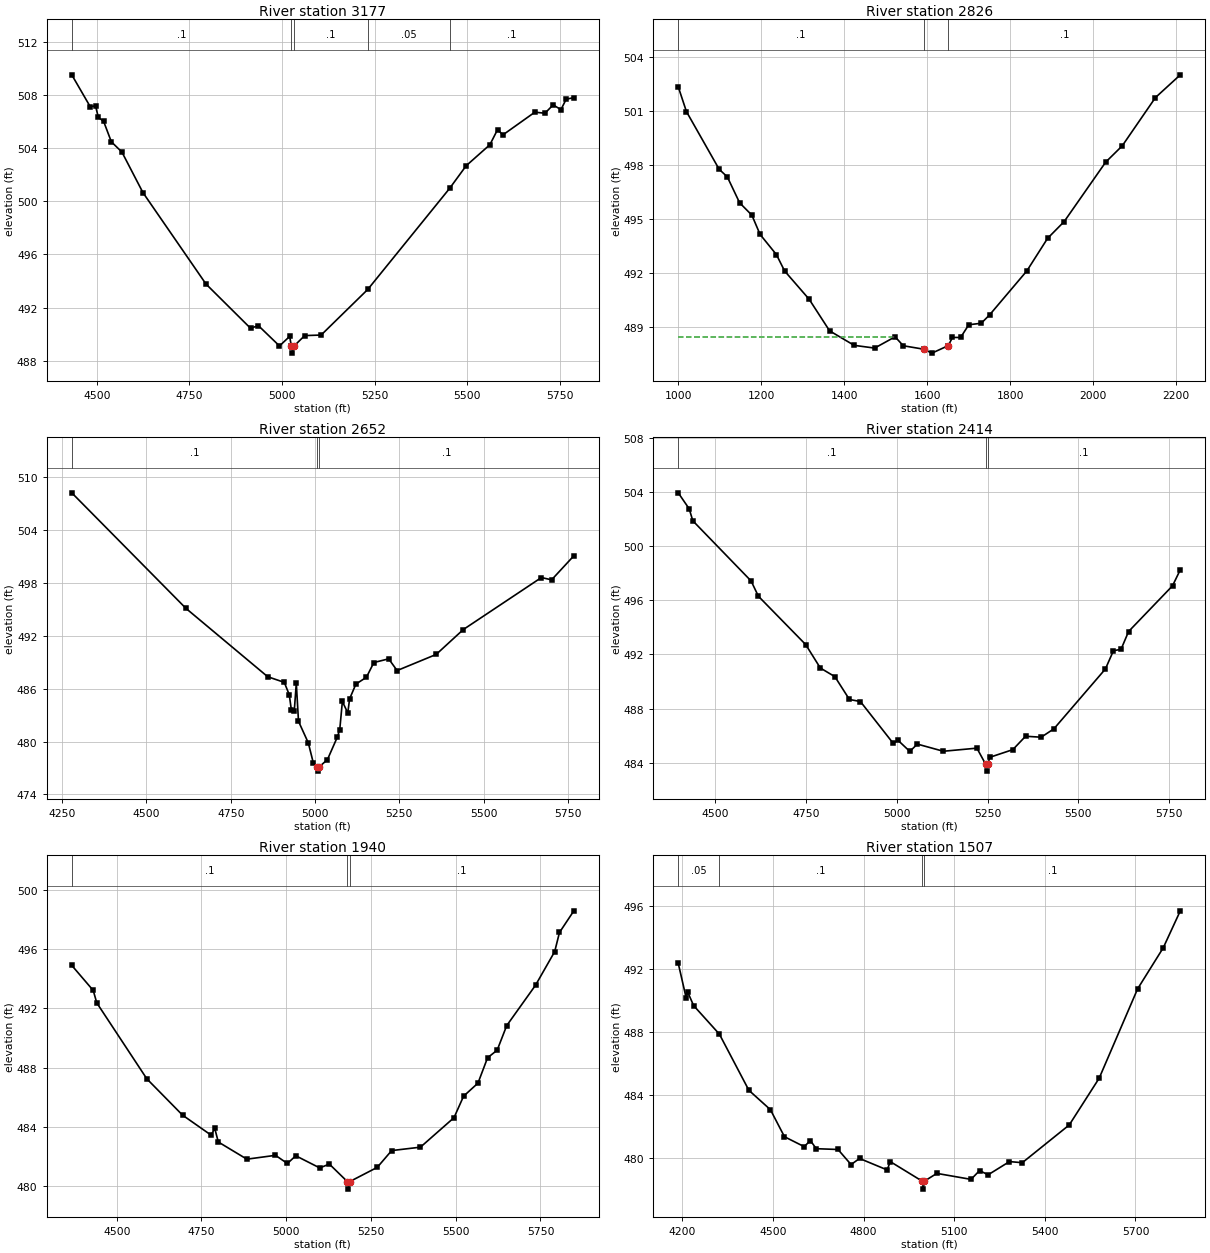
Type RM Length L Ch R = 1 ,3177    ,351,351,351
BEGIN DESCRIPTION:
UNT 159 IN LACR 6.0
END DESCRIPTION:
XS GIS Cut Line= 3
      2163852.49     13201781.38      2164264.79     13202258.78
      2164829.03     13202714.52
#Sta/Elev= 30
  4432.3  509.51  4482.2  507.11  4496.4  507.18  4504.1  506.31  4518.3  506.01
  4539.2  504.47  4567.7   503.7  4624.5  500.65  4794.8  493.77  4915.2  490.44
  4936.3  490.64  4993.3  489.11  5020.9  489.83  5025.4  489.07  5028.2  488.57
  5031.4  489.07  5061.5  489.89  5105.8  489.93  5231.7  493.36    5453  500.97
  5497.6  502.67  5561.6  504.25  5582.4  505.39  5596.8  504.99  5683.1   506.7
  5710.3  506.62  5732.6  507.25  5753.5  506.89  5767.8  507.68  5788.4  507.79
#Mann= 5 ,-1 , 0
  4432.3      .1       0  5025.4     .07       0  5031.4      .1       0
  5231.7     .05       0    5453      .1       0
Bank Sta=5025.4,5031.4
XS Rating Curve= 0 ,0
Exp/Cntr=0.3,0.1

Type RM Length L Ch R = 1 ,2826    ,174,174,174
BEGIN DESCRIPTION:
Mapping XS 21080c25
END DESCRIPTION:
XS GIS Cut Line= 4
     2163871.071    13201979.738     2163975.668    13202378.203
     2164177.391    13202577.436     2164665.511     13202726.86
#Sta/Elev= 30
    1000502.3521 1019.71500.9765 1098.56497.7726 1118.28497.3476 1147.84495.9124
 1177.41495.2227 1197.13494.1562 1236.55493.0338 1256.26492.1262  1315.4490.5561
 1364.68488.8021 1423.83487.9974 1473.14487.8458 1522.44488.4714 1542.17 487.975
 1591.48487.7834  1611.2487.5657 1650.64487.9822 1660.51488.4365 1680.23488.4342
 1699.95489.1404 1729.93489.2242 1749.91489.6837 1839.84  492.13  1889.8493.9384
 1929.76494.8685 2029.68498.1662 2069.65499.0732 2149.59501.7516 2209.54503.0147
#Mann= 3 , 0 , 0
    1000      .1       0 1591.48      .1       0 1650.64      .1       0
#XS Ineff= 2 , 0
       0 1522.92  488.47               0
Permanent Ineff=
       T       F
Bank Sta=1591.48,1650.64
XS Rating Curve= 0 ,0
Exp/Cntr=0.3,0.1

Type RM Length L Ch R = 1 ,2652    ,238,238,238
BEGIN DESCRIPTION:
Mapping XS 38d302b7
END DESCRIPTION:
XS GIS Cut Line= 4
      2163733.11     13201868.16      2163874.16      13202432.4
      2164004.37     13202616.86      2164643.69     13202855.25
#Sta/Elev= 30
  4278.3  508.24  4617.1  495.12  4859.6  487.36  4908.8  486.72  4923.6  485.32
  4929.7  483.63  4938.4  483.42  4944.5  486.63    4951   482.3  4980.2  479.84
    4995  477.57  5006.8  477.14  5009.5  476.64  5012.8  477.14  5036.8  477.94
  5066.4  480.52  5073.4  481.34  5081.2  484.55  5097.3  483.24  5102.6  484.84
  5121.3  486.52  5152.6   487.3  5174.6  488.97  5218.6  489.39  5243.6  488.06
  5359.5  489.89  5439.8  492.71  5671.7  498.62    5702  498.36    5768  501.09
#Mann= 3 ,-1 , 0
  4278.3      .1       0  5006.8     .07       0  5012.8      .1       0
Bank Sta=5006.8,5012.8
XS Rating Curve= 0 ,0
Exp/Cntr=0.3,0.1

Type RM Length L Ch R = 1 ,2414    ,474,474,474
BEGIN DESCRIPTION:
UNT 159 IN LACR 5.0
END DESCRIPTION:
XS GIS Cut Line= 3
      2163687.72     13201996.83      2163737.72     13202596.85
       2164237.7     13203196.84
#Sta/Elev= 30
  4397.9  503.96    4428  502.78  4438.1  501.89  4598.6  497.44  4618.7  496.31
  4749.1  492.73  4789.3     491  4829.4  490.36  4869.5  488.67  4899.7  488.52
    4990  485.43  5003.3  485.65  5035.8  484.83  5056.6  485.37  5128.2  484.84
  5220.6  485.07    5245  483.87  5247.7  483.37    5251  483.87  5255.8  484.39
  5319.6  484.96  5354.7  485.95  5397.7  485.88  5432.8   486.5  5574.7  490.93
  5596.8  492.28  5617.7  492.38  5638.5   493.7  5759.5  497.08    5781  498.27
#Mann= 3 ,-1 , 0
  4397.9      .1       0    5245     .07       0    5251      .1       0
Bank Sta=5245,5251
XS Rating Curve= 0 ,0
Exp/Cntr=0.3,0.1

Type RM Length L Ch R = 1 ,1940    ,433,433,433
BEGIN DESCRIPTION:
UNT 159 IN LACR 4.0
END DESCRIPTION:
XS GIS Cut Line= 3
      2163187.71     13202196.81      2163387.72     13202796.86
       2163987.7     13203396.84
#Sta/Elev= 30
  4367.5  494.89  4430.8   493.2  4441.3  492.36  4588.9  487.24  4694.3  484.79
  4778.6  483.44  4789.2   483.9  4799.7  482.98    4884  481.82  4968.4  482.08
  5003.5  481.53  5028.3  482.05    5099  481.23  5127.3  481.49  5180.8   480.3
  5183.6   479.8  5186.8   480.3  5268.7  481.27  5311.1   482.4    5396  482.63
    5495  484.62  5523.3  486.07  5565.7  486.95    5594  488.66  5622.3  489.17
  5650.5  490.83  5735.4  493.55    5792  495.82  5806.1  497.11  5848.5  498.57
#Mann= 3 ,-1 , 0
  4367.5      .1       0  5180.8     .07       0  5186.8      .1       0
Bank Sta=5180.8,5186.8
XS Rating Curve= 0 ,0
Exp/Cntr=0.3,0.1

Type RM Length L Ch R = 1 ,1507    ,483,483,483
BEGIN DESCRIPTION:
UNT 159 IN LACR 3.0
END DESCRIPTION:
XS GIS Cut Line= 3
      2163037.73      13202246.9      2163187.72     13203046.85
       2163787.7     13203646.84
#Sta/Elev= 30
  4186.1  492.39  4212.3  490.19  4217.4  490.56  4236.9   489.7  4322.4  487.88
  4420.1  484.31  4491.3  483.08  4537.9  481.36  4603.2  480.73  4623.6  481.12
  4643.1   480.6  4715.1  480.55  4758.4  479.59  4786.3  479.98  4877.9  479.25
  4888.1  479.78  4994.5  478.53  4997.2  478.03  5000.5  478.53  5042.4  479.03
  5155.6  478.65  5183.8  479.21  5212.1  478.94  5282.8  479.78  5325.3  479.71
  5480.8  482.11  5579.8  485.08  5707.1  490.76    5792  493.37  5848.5  495.72
#Mann= 4 ,-1 , 0
  4186.1     .05       0  4322.4      .1       0  4994.5     .07       0
  5000.5      .1       0
Bank Sta=4994.5,5000.5
XS Rating Curve= 0 ,0
Exp/Cntr=0.3,0.1

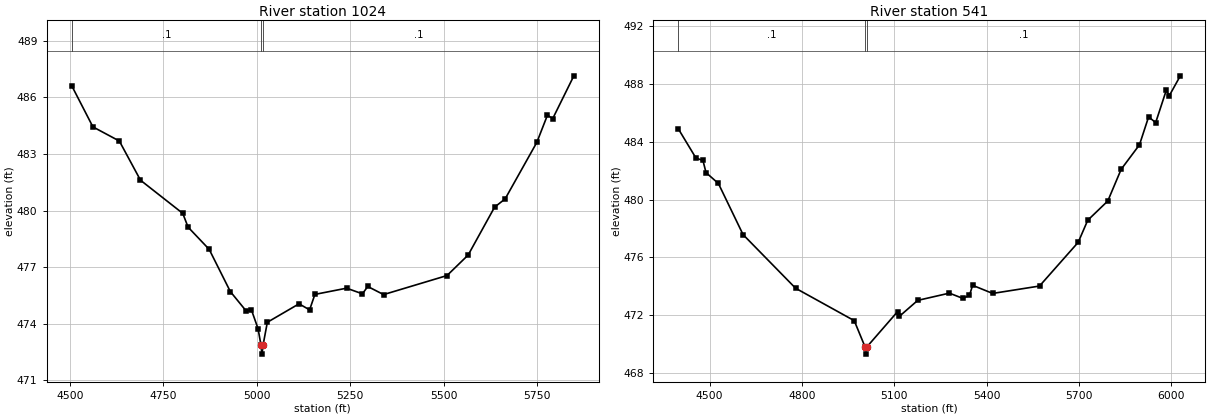
Type RM Length L Ch R = 1 ,1024    ,483,483,483
BEGIN DESCRIPTION:
UNT 159 IN LACR 2.0
END DESCRIPTION:
XS GIS Cut Line= 3
       2162437.7     13202896.84      2162787.72     13203246.85
       2163387.7     13203846.84
#Sta/Elev= 30
    4505  486.62  4561.6  484.44  4632.3  483.69  4688.9  481.61    4802  479.85
  4816.2  479.12  4872.7  477.94  4929.3   475.7  4971.7  474.67  4985.9  474.72
  5003.5  473.73  5011.1  472.88  5013.9  472.38  5017.1  472.88  5028.3  474.07
  5113.1  475.05  5141.4  474.73  5155.6  475.55  5240.4  475.88  5282.8  475.58
    5297  475.97  5339.4  475.54  5509.1  476.55  5565.7  477.64  5636.4  480.18
  5664.7  480.62  5749.5  483.62  5777.8  485.06    5792  484.88  5848.5  487.15
#Mann= 3 ,-1 , 0
    4505      .1       0  5011.1     .07       0  5017.1      .1       0
Bank Sta=5011.1,5017.1
XS Rating Curve= 0 ,0
Exp/Cntr=0.3,0.1

Type RM Length L Ch R = 1 ,541     ,0,0,0
BEGIN DESCRIPTION:
UNT 159 IN LACR 1.0
END DESCRIPTION:
XS GIS Cut Line= 3
      2162437.72     13202946.83      2162487.72     13203546.85
      2163387.75     13204046.87
#Sta/Elev= 30
  4397.9  484.89  4455.6  482.86  4478.2   482.7  4488.2  481.86  4528.4  481.11
  4608.6  477.58  4779.2  473.88  4969.9  471.64    5005  469.83  5007.8  469.33
    5011  469.83    5111  472.27  5116.7  471.94  5176.2  473.04  5279.1  473.54
  5322.6  473.18  5344.3  473.38  5354.6  474.08  5419.8  473.52    5572  474.03
  5697.8  477.05  5728.7  478.57  5793.9   479.9  5837.4  482.09  5896.9  483.78
  5926.6  485.71  5949.5  485.31  5983.8  487.53  5994.1  487.18  6029.6  488.54
#Mann= 3 ,-1 , 0
  4397.9      .1       0    5005     .07       0    5011      .1       0
Bank Sta=5005,5011
XS Rating Curve= 0 ,0
Exp/Cntr=0.3,0.1

Chan Stop Cuts=-1
Use User Specified Reach Order=0
Composite Channel Slope=5