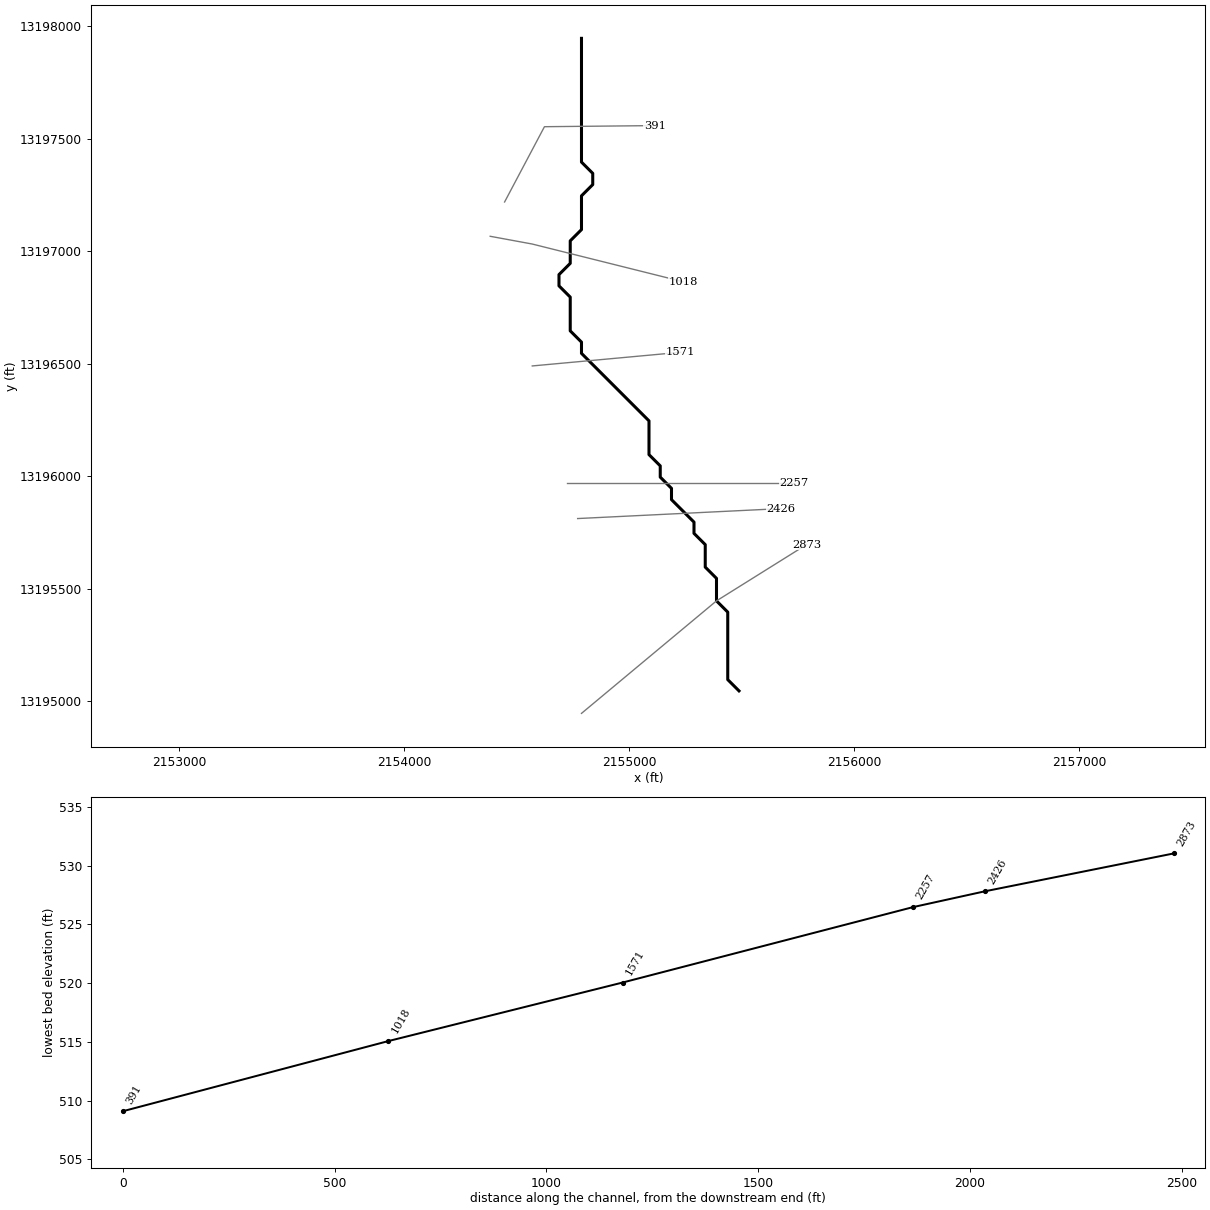
--- UNT 161 IN LACR.prj (project) ---

Proj Title=UNT 161 IN LACR Base Level Engineering
Current Plan=p01
Default Exp/Contr=0.3,0.1
English Units
Geom File=g01
Flow File=f01
Plan File=p01
BEGIN DESCRIPTION:
UNT 161 IN LACR
END DESCRIPTION:

--- UNT 161 IN LACR.p01 (plan) ---

Plan Title=Multiple Run
Short Identifier=Multiple
Geom File=g01
Flow File=f01
Subcritical Flow
K Sum by GR= 0
Std Step Tol= 0.01
Critical Tol= 0.01
Num of Std Step Trials= 20
Max Error Tol= 0.3
Flow Tol Ratio= 0.001
Split Flow NTrial= 30
Split Flow Tol= 0.02
Split Flow Ratio= 0.02
Log Output Level= 0
Friction Slope Method= 1
Unsteady Friction Slope Method= 2
Unsteady Bridges Friction Slope Method= 1
Parabolic Critical Depth
Global Vel Dist=  1 , 1 , 1
Global Log Level= 0
CheckData=True
Encroach Param= -1, 0, 0, 0
BEGIN DESCRIPTION:
Multiple Run
END DESCRIPTION:

--- UNT 161 IN LACR.f01 (steady flow) ---

Flow Title=Multiple
Number of Profiles=7
Profile Names=10-year,25-year,50-year,1pct_min,100-year,1pct_plu,500-year
River Rch & RM= UNT 161 IN LACR,Reach-1,2873
      97     130     157     140     190     257     280
Boundary for River Rch & Prof#=UNT 161 IN LACR,Reach-1,1
Up Type=0
Dn Type=3
Dn Slope=0.005
Boundary for River Rch & Prof#=UNT 161 IN LACR,Reach-1,2
Up Type=0
Dn Type=3
Dn Slope=0.005
Boundary for River Rch & Prof#=UNT 161 IN LACR,Reach-1,3
Up Type=0
Dn Type=3
Dn Slope=0.005
Boundary for River Rch & Prof#=UNT 161 IN LACR,Reach-1,4
Up Type=0
Dn Type=3
Dn Slope=0.005
Boundary for River Rch & Prof#=UNT 161 IN LACR,Reach-1,5
Up Type=0
Dn Type=3
Dn Slope=0.005
Boundary for River Rch & Prof#=UNT 161 IN LACR,Reach-1,6
Up Type=0
Dn Type=3
Dn Slope=0.005
Boundary for River Rch & Prof#=UNT 161 IN LACR,Reach-1,7
Up Type=0
Dn Type=3
Dn Slope=0.005

--- UNT 161 IN LACR.g01 (geometry) ---

Geom Title=Existing Conditions

River Reach=UNT 161 IN LACR,Reach-1
Reach XY= 30
      2155487.72     13195046.85      2155437.72     13195096.86
      2155437.72     13195396.85      2155387.72     13195446.86
      2155387.72     13195546.85      2155337.72     13195596.86
      2155337.72     13195696.85      2155287.72     13195746.86
      2155287.72     13195796.85      2155187.72     13195896.85
      2155187.72     13195946.85      2155137.72     13195996.85
      2155137.72     13196046.85      2155087.72     13196096.86
      2155087.72     13196246.86      2155037.72     13196296.85
      2154787.72     13196546.85      2154787.72     13196596.86
      2154737.72     13196646.85      2154737.72     13196796.85
      2154687.72     13196846.85      2154687.72     13196896.86
      2154737.72     13196946.85      2154737.72     13197046.85
      2154787.72     13197096.85      2154787.72     13197246.86
      2154837.72     13197296.85      2154837.72     13197346.85
      2154787.72     13197396.86      2154787.72     13197946.85

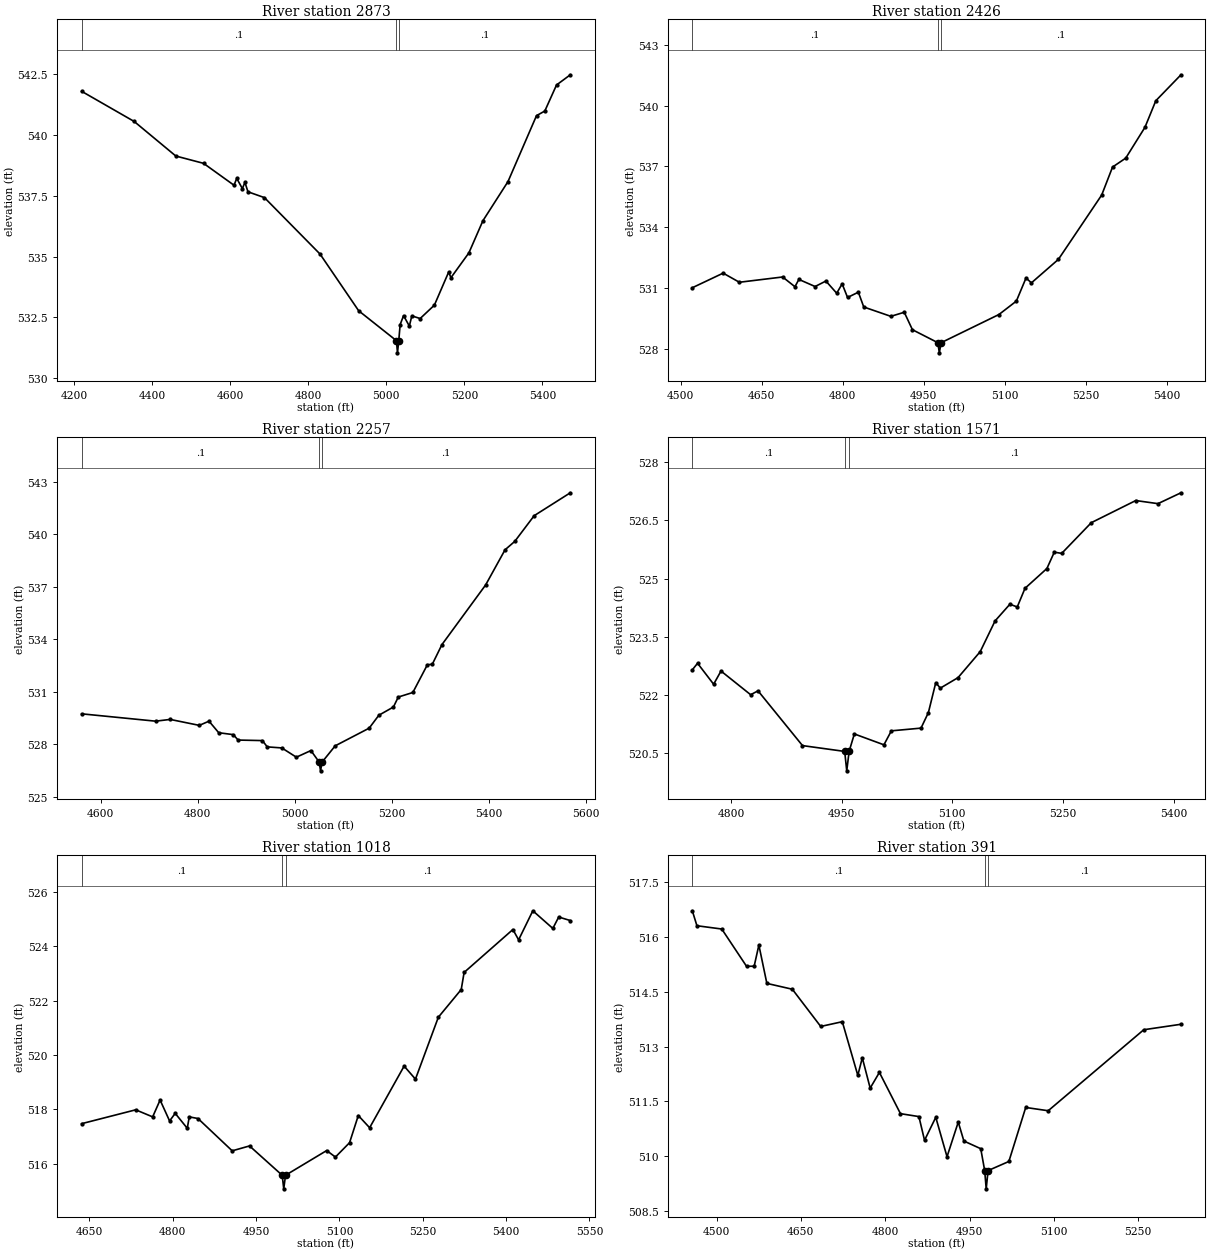
Type RM Length L Ch R = 1,2873,447,447,447
BEGIN DESCRIPTION:
UNT 161 IN LACR 2.0
END DESCRIPTION:
XS GIS Cut Line= 3
      2154787.74     13194946.87      2155387.72     13195446.86
      2155787.72     13195696.86
#Sta/Elev= 30
  4219.0  541.79  4353.7  540.55  4460.4  539.13  4531.4  538.83  4609.5  537.93
  4616.6  538.21  4631.0  537.79  4637.5  538.05  4645.3  537.66  4687.6  537.42
  4830.1  535.10  4929.1  532.77  5025.9  531.54  5028.6  531.04  5031.9  531.54
  5035.4  532.20  5044.2  532.57  5059.0  532.14  5065.4  532.56  5086.7  532.45
  5123.2  533.00  5159.8  534.36  5165.7  534.13  5211.7  535.15  5247.6  536.47
  5311.9  538.08  5385.0  540.79  5406.3  540.98  5436.3  542.05  5471.7  542.47
#Mann=3,-1,0
  4219.0     0.1       0  5025.9    0.07       0  5031.9     0.1       0
Bank Sta=5025.9,5031.9
Exp/Cntr=0.3,0.1

Type RM Length L Ch R = 1,2426,169,169,169
BEGIN DESCRIPTION:
Mapping XS 3064bf9a
END DESCRIPTION:
XS GIS Cut Line= 2
      2154770.69     13195812.69      2155674.31     13195856.88
#Sta/Elev= 30
  4521.6  531.02  4578.7  531.74  4608.7  531.29  4688.8  531.55  4711.6  531.07
  4718.9  531.43  4748.9  531.08  4768.9  531.35  4788.9  530.75  4799.0  531.21
  4809.0  530.54  4829.0  530.80  4839.0  530.07  4889.1  529.61  4914.0  529.81
  4929.1  528.95  4976.2  528.31  4978.9  527.81  4982.2  528.31  5089.3  529.70
  5121.5  530.36  5139.4  531.50  5149.4  531.26  5199.4  532.42  5279.5  535.59
  5299.6  536.97  5324.0  537.41  5359.6  538.93  5379.7  540.24  5426.3  541.52
#Mann=3,-1,0
  4521.6     0.1       0  4976.2    0.07       0  4982.2     0.1       0
Bank Sta=4976.2,4982.2
Exp/Cntr=0.3,0.1

Type RM Length L Ch R = 1,2257,686,686,686
BEGIN DESCRIPTION:
Mapping XS e02099b6
END DESCRIPTION:
XS GIS Cut Line= 2
      2154725.30     13195970.08      2155732.20     13195970.08
#Sta/Elev= 30
  4560.8  529.73  4713.2  529.31  4743.2  529.41  4803.2  529.07  4823.2  529.31
  4843.2  528.65  4873.2  528.54  4883.2  528.23  4933.2  528.20  4943.2  527.84
  4973.2  527.78  5003.2  527.25  5033.2  527.63  5050.2  526.97  5053.0  526.47
  5056.2  526.97  5083.2  527.90  5153.2  528.91  5173.2  529.65  5203.2  530.12
  5213.2  530.69  5243.2  530.95  5273.2  532.54  5283.2  532.56  5303.2  533.69
  5393.2  537.10  5433.2  539.11  5453.2  539.59  5493.2  541.06  5567.7  542.37
#Mann=3,-1,0
  4560.8     0.1       0  5050.2    0.07       0  5056.2     0.1       0
Bank Sta=5050.2,5056.2
Exp/Cntr=0.3,0.1

Type RM Length L Ch R = 1,1571,553,553,553
BEGIN DESCRIPTION:
Mapping XS 95e9e4fb
END DESCRIPTION:
XS GIS Cut Line= 2
      2154568.97     13196490.90      2155228.78     13196551.68
#Sta/Elev= 30
  4747.4  522.65  4754.5  522.82  4776.3  522.28  4786.3  522.62  4826.5  522.01
  4836.5  522.11  4896.8  520.70  4954.0  520.55  4956.8  520.05  4960.0  520.55
  4967.1  521.00  5007.2  520.72  5017.3  521.08  5057.5  521.15  5067.5  521.55
  5077.5  522.32  5083.7  522.18  5107.7  522.45  5137.8  523.12  5157.9  523.91
  5178.0  524.34  5188.0  524.27  5198.5  524.75  5228.2  525.26  5238.2  525.68
  5248.3  525.65  5288.4  526.44  5348.7  527.01  5378.8  526.93  5410.0  527.21
#Mann=3,-1,0
  4747.4     0.1       0  4954.0    0.07       0  4960.0     0.1       0
Bank Sta=4954,4960
Exp/Cntr=0.3,0.1

Type RM Length L Ch R = 1,1018,627,627,627
BEGIN DESCRIPTION:
Mapping XS 8c7c3f23
END DESCRIPTION:
XS GIS Cut Line= 3
      2154382.06     13197067.11      2154569.00     13197032.68
      2155238.02     13196865.42
#Sta/Elev= 30
  4636.0  517.47  4733.3  517.98  4763.8  517.72  4777.2  518.34  4794.3  517.57
  4804.4  517.85  4826.1  517.30  4829.7  517.72  4845.4  517.66  4907.0  516.47
  4938.2  516.65  4997.0  515.57  4999.8  515.07  5003.0  515.57  5077.1  516.48
  5092.8  516.24  5118.3  516.77  5134.0  517.77  5154.4  517.32  5216.5  519.59
  5236.9  519.11  5278.1  521.39  5319.3  522.41  5324.5  523.04  5412.3  524.62
  5422.6  524.24  5448.2  525.31  5484.2  524.66  5494.8  525.08  5515.7  524.95
#Mann=3,-1,0
  4636.0     0.1       0  4997.0    0.07       0  5003.0     0.1       0
Bank Sta=4997,5003
Exp/Cntr=0.3,0.1

Type RM Length L Ch R = 1,391,0,0,0
BEGIN DESCRIPTION:
UNT 161 IN LACR 1.0
END DESCRIPTION:
XS GIS Cut Line= 3
      2154446.03     13197219.62      2154623.11     13197554.13
      2155113.90     13197559.03
#Sta/Elev= 30
  4456.9  516.72  4465.1  516.31  4509.3  516.22  4553.3  515.20  4566.9  515.20
  4575.3  515.78  4589.5  514.73  4634.8  514.57  4685.3  513.55  4723.7  513.68
  4751.3  512.21  4759.3  512.69  4773.3  511.86  4789.7  512.29  4827.2  511.16
  4860.0  511.08  4870.0  510.43  4890.0  511.06  4910.0  509.98  4930.0  510.93
  4940.0  510.41  4970.0  510.20  4977.0  509.60  4979.7  509.10  4983.0  509.60
  5020.0  509.85  5050.0  511.33  5090.0  511.24  5260.0  513.46  5326.2  513.61
#Mann=3,-1,0
  4456.9     0.1       0  4977.0    0.07       0  4983.0     0.1       0
Bank Sta=4977,4983
Exp/Cntr=0.3,0.1

Chan Stop Cuts=-1