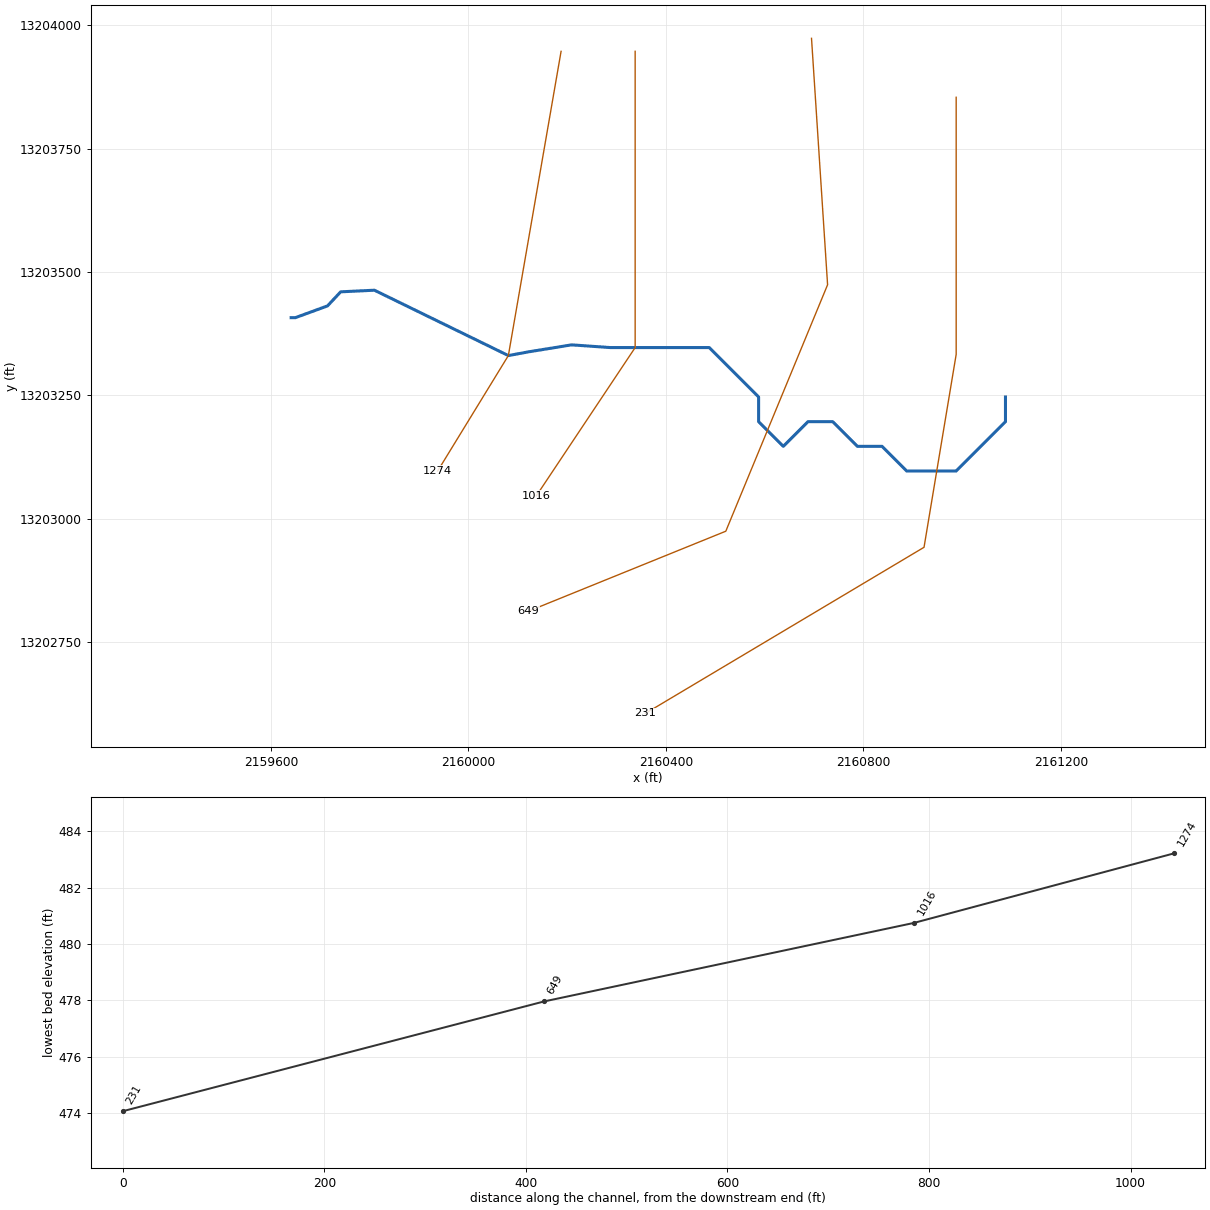
--- UNT 162 IN LACR.prj (project) ---

Proj Title=UNT 162 IN LACR Base Level Engineering
Current Plan=p01
Default Exp/Contr=0.3,0.1
English Units
Geom File=g01
Flow File=f01
Plan File=p01
BEGIN DESCRIPTION:
UNT 162 IN LACR
END DESCRIPTION:

--- UNT 162 IN LACR.p01 (plan) ---

Plan Title=Multiple Run
Short Identifier=Multiple
Geom File=g01
Flow File=f01
Subcritical Flow
K Sum by GR= 0
Std Step Tol= 0.01
Critical Tol= 0.01
Num of Std Step Trials= 20
Max Error Tol= 0.3
Flow Tol Ratio= 0.001
Split Flow NTrial= 30
Split Flow Tol= 0.02
Split Flow Ratio= 0.02
Log Output Level= 0
Friction Slope Method= 1
Unsteady Friction Slope Method= 2
Unsteady Bridges Friction Slope Method= 1
Parabolic Critical Depth
Global Vel Dist=  1 , 1 , 1
Global Log Level= 0
CheckData=True
Encroach Param= -1, 0, 0, 0
BEGIN DESCRIPTION:
Multiple Run
END DESCRIPTION:

--- UNT 162 IN LACR.f01 (steady flow) ---

Flow Title=Multiple
Number of Profiles=7
Profile Names=10-year,25-year,50-year,1pct_min,100-year,1pct_plu,500-year
River Rch & RM= UNT 162 IN LACR,Reach-1,1274
      45      57      67      58      78     105     107
Boundary for River Rch & Prof#=UNT 162 IN LACR,Reach-1,1
Up Type=0
Dn Type=3
Dn Slope=0.005
Boundary for River Rch & Prof#=UNT 162 IN LACR,Reach-1,2
Up Type=0
Dn Type=3
Dn Slope=0.005
Boundary for River Rch & Prof#=UNT 162 IN LACR,Reach-1,3
Up Type=0
Dn Type=3
Dn Slope=0.005
Boundary for River Rch & Prof#=UNT 162 IN LACR,Reach-1,4
Up Type=0
Dn Type=3
Dn Slope=0.005
Boundary for River Rch & Prof#=UNT 162 IN LACR,Reach-1,5
Up Type=0
Dn Type=3
Dn Slope=0.005
Boundary for River Rch & Prof#=UNT 162 IN LACR,Reach-1,6
Up Type=0
Dn Type=3
Dn Slope=0.005
Boundary for River Rch & Prof#=UNT 162 IN LACR,Reach-1,7
Up Type=0
Dn Type=3
Dn Slope=0.005

--- UNT 162 IN LACR.g01 (geometry) ---

Geom Title=Existing Conditions

River Reach=UNT 162 IN LACR,Reach-1
Reach XY= 27
      2159640.94     13203407.42      2159649.62     13203407.42
      2159714.73     13203431.29      2159741.31     13203459.77
      2159809.67     13203463.03      2160080.94     13203330.65
      2160122.17     13203338.25      2160208.97     13203352.35
      2160287.72     13203346.85      2160337.72     13203346.85
      2160387.72     13203346.85      2160437.72     13203346.85
      2160487.72     13203346.85      2160537.72     13203296.86
      2160587.72     13203246.85      2160587.72     13203196.85
      2160637.72     13203146.86      2160687.72     13203196.85
      2160737.72     13203196.85      2160787.72     13203146.86
      2160837.72     13203146.86      2160887.72     13203096.85
      2160937.72     13203096.85      2160987.72     13203096.85
      2161037.72     13203146.86      2161087.72     13203196.85
      2161087.72     13203246.85

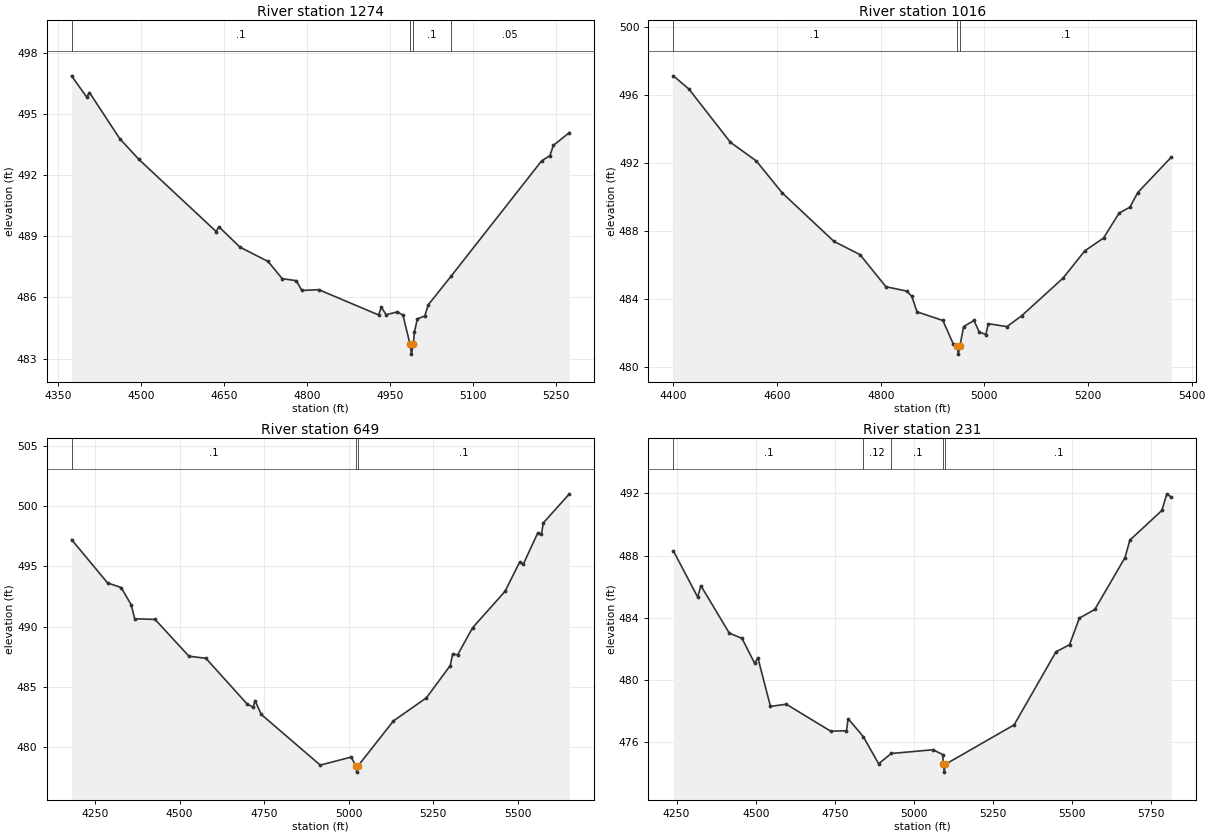
Type RM Length L Ch R = 1,1274,258,258,258
BEGIN DESCRIPTION:
UNT 162 IN LACR 3.0
END DESCRIPTION:
XS GIS Cut Line= 3
      2160187.72     13203946.87      2160080.94     13203330.65
      2159937.71     13203096.83
#Sta/Elev= 30
  4374.6  496.86  4401.9  495.82  4407.0  496.04  4461.7  493.78  4496.4  492.76
  4635.8  489.23  4640.9  489.46  4679.1  488.46  4729.8  487.76  4755.2  486.92
  4780.6  486.82  4790.7  486.34  4821.2  486.38  4929.4  485.14  4934.4  485.52
  4943.0  485.15  4963.3  485.29  4973.4  485.13  4986.1  483.72  4988.8  483.22
  4992.1  483.72  4994.2  484.30  4999.4  484.95  5013.0  485.09  5018.9  485.63
  5060.4  487.04  5223.9  492.69  5239.0  492.95  5245.2  493.45  5274.2  494.08
#Mann=4,-1,0
  4374.6     0.1       0  4986.1    0.07       0  4992.1     0.1       0
  5060.4    0.05       0
Bank Sta=4986.1,4992.1
Exp/Cntr=0.3,0.1

Type RM Length L Ch R = 1,1016,367,367,367
BEGIN DESCRIPTION:
UNT 162 IN LACR 2.0
END DESCRIPTION:
XS GIS Cut Line= 3
      2160337.72     13203946.85      2160337.72     13203346.85
      2160137.70     13203046.82
#Sta/Elev= 30
  4400.0  497.13  4430.0  496.35  4510.0  493.22  4560.0  492.12  4610.0  490.24
  4710.0  487.38  4760.0  486.61  4810.0  484.72  4850.0  484.46  4860.0  484.16
  4870.0  483.24  4920.0  482.73  4940.0  481.35  4947.0  481.25  4949.8  480.75
  4953.0  481.25  4960.0  482.37  4980.0  482.73  4990.0  482.06  5003.0  481.90
  5007.5  482.54  5043.6  482.37  5072.1  483.01  5151.7  485.22  5193.8  486.83
  5229.9  487.58  5259.9  489.05  5280.9  489.40  5296.0  490.26  5360.6  492.34
#Mann=3,-1,0
  4400.0     0.1       0  4947.0    0.07       0  4953.0     0.1       0
Bank Sta=4947,4953
Exp/Cntr=0.3,0.1

Type RM Length L Ch R = 1,649,418,418,418
BEGIN DESCRIPTION:
Mapping XS e55549cf
END DESCRIPTION:
XS GIS Cut Line= 4
      2160694.91     13203973.15      2160727.46     13203474.06
      2160521.30     13202974.93      2160121.30     13202812.77
#Sta/Elev= 30
  4180.6  497.22  4287.1  493.63  4327.2  493.25  4357.3  491.80  4367.3  490.66
  4427.4  490.61  4527.6  487.56  4577.7  487.39  4699.4  483.61  4717.5  483.33
  4722.9  483.89  4741.4  482.74  4915.8  478.54  5007.6  479.21  5021.0  478.46
  5023.7  477.96  5027.0  478.46  5132.1  482.20  5229.5  484.11  5300.2  486.79
  5307.2  487.76  5321.8  487.67  5366.2  489.92  5462.0  492.93  5505.2  495.35
  5516.0  495.18  5559.2  497.79  5569.8  497.68  5575.2  498.60  5652.4  501.01
#Mann=3,-1,0
  4180.6     0.1       0  5021.0    0.07       0  5027.0     0.1       0
Bank Sta=5021,5027
Exp/Cntr=0.3,0.1

Type RM Length L Ch R = 1,231,0,0,0
BEGIN DESCRIPTION:
UNT 162 IN LACR 1.0
END DESCRIPTION:
XS GIS Cut Line= 4
      2160987.88     13203853.80      2160987.88     13203333.00
      2160922.77     13202942.38      2160358.54     13202606.01
#Sta/Elev= 30
  4239.8  488.30  4316.7  485.32  4326.7  486.06  4416.7  483.00  4456.7  482.67
  4496.7  481.06  4506.7  481.43  4546.7  478.29  4596.7  478.43  4736.7  476.70
  4787.0  476.72  4792.1  477.50  4839.9  476.35  4888.5  474.60  4928.7  475.26
  5060.8  475.50  5091.1  475.19  5093.2  474.56  5096.0  474.06  5099.2  474.56
  5316.8  477.10  5449.1  481.80  5492.0  482.26  5523.1  483.97  5571.8  484.53
  5667.2  487.86  5682.7  488.99  5783.9  490.90  5799.5  491.97  5813.5  491.76
#Mann=5,-1,0
  4239.8     0.1       0  4839.9    0.12       0  4928.7     0.1       0
  5093.2    0.07       0  5099.2     0.1       0
Bank Sta=5093.2,5099.2
Exp/Cntr=0.3,0.1

Chan Stop Cuts=-1