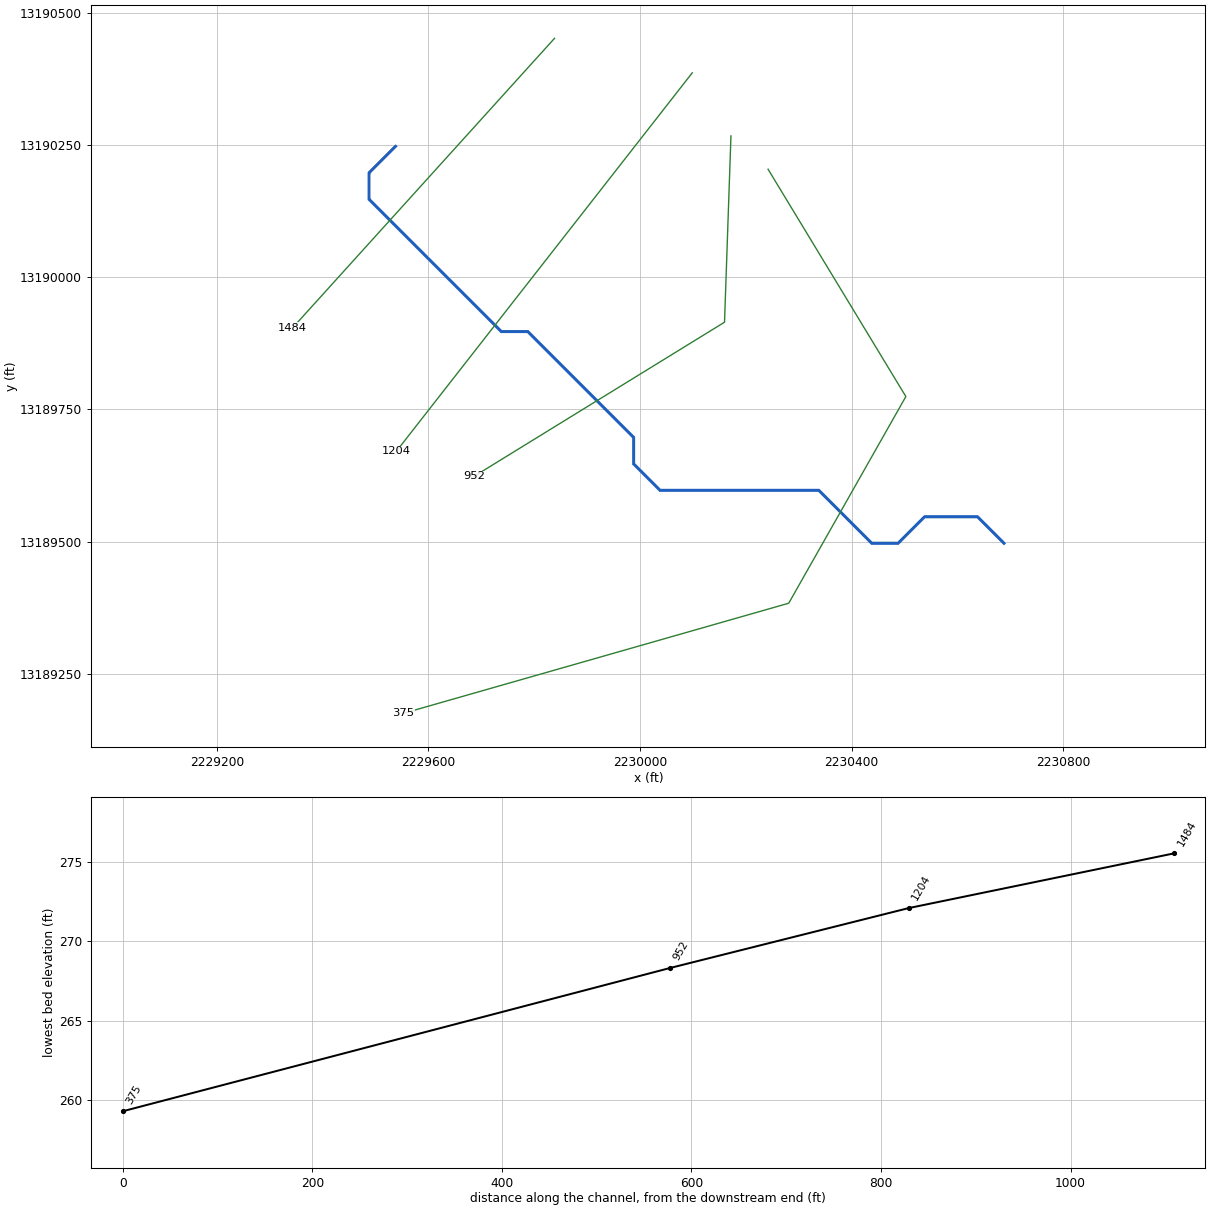
--- UNT 168 IN LACR.prj (project) ---

Proj Title=UNT 168 IN LACR Base Level Engineering
Current Plan=p01
Default Exp/Contr=0.3,0.1
English Units
Geom File=g01
Flow File=f01
Plan File=p01
Y Axis Title=Elevation
X Axis Title(PF)=Main Channel Distance
X Axis Title(XS)=Station
BEGIN DESCRIPTION:
UNT 168 IN LACR
END DESCRIPTION:
DSS Export Rating Curves= 0
DSS Export Rating Curve Sorted= 0
DSS Export Volume Flow Curves= 0
DXF OffsetX= 0
DXF OffsetY= 0
DXF ScaleX= 1
DXF ScaleY= 10

--- UNT 168 IN LACR.p01 (plan) ---

Plan Title=Multiple Run
Short Identifier=Multiple
Geom File=g01
Flow File=f01
Subcritical Flow
K Sum by GR= 0
Std Step Tol= 0.01
Critical Tol= 0.01
Num of Std Step Trials= 20
Max Error Tol= 0.3
Flow Tol Ratio= 0.001
Split Flow NTrial= 30
Split Flow Tol= 0.02
Split Flow Ratio= 0.02
Log Output Level= 0
Friction Slope Method= 1
Unsteady Friction Slope Method= 2
Unsteady Bridges Friction Slope Method= 1
Parabolic Critical Depth
Global Vel Dist=  1 , 1 , 1
Global Log Level= 0
CheckData=True
Encroach Param= -1, 0, 0, 0
BEGIN DESCRIPTION:
Multiple Run
END DESCRIPTION:

--- UNT 168 IN LACR.f01 (steady flow) ---

Flow Title=Multiple
Number of Profiles=7
Profile Names=10-year,25-year,50-year,1pct_min,100-year,1pct_plu,500-year
River Rch & RM= UNT 168 IN LACR,Reach-1,1484
     121     161     194     173     234     316     343
Boundary for River Rch & Prof#=UNT 168 IN LACR,Reach-1,1
Up Type=0
Dn Type=3
Dn Slope=0.005
Boundary for River Rch & Prof#=UNT 168 IN LACR,Reach-1,2
Up Type=0
Dn Type=3
Dn Slope=0.005
Boundary for River Rch & Prof#=UNT 168 IN LACR,Reach-1,3
Up Type=0
Dn Type=3
Dn Slope=0.005
Boundary for River Rch & Prof#=UNT 168 IN LACR,Reach-1,4
Up Type=0
Dn Type=3
Dn Slope=0.005
Boundary for River Rch & Prof#=UNT 168 IN LACR,Reach-1,5
Up Type=0
Dn Type=3
Dn Slope=0.005
Boundary for River Rch & Prof#=UNT 168 IN LACR,Reach-1,6
Up Type=0
Dn Type=3
Dn Slope=0.005
Boundary for River Rch & Prof#=UNT 168 IN LACR,Reach-1,7
Up Type=0
Dn Type=3
Dn Slope=0.005

--- UNT 168 IN LACR.g01 (geometry) ---

Geom Title=Existing Conditions
Program Version=4.10

River Reach=UNT 168 IN LACR ,Reach-1
Reach XY= 28
      2229537.72     13190246.85      2229487.72     13190196.86
      2229487.72     13190146.85      2229537.72     13190096.85
      2229587.72     13190046.85      2229637.72     13189996.85
      2229687.72     13189946.85      2229737.72     13189896.85
      2229787.72     13189896.85      2229837.72     13189846.86
      2229887.72     13189796.85      2229937.72     13189746.85
      2229987.72     13189696.86      2229987.72     13189646.85
      2230037.72     13189596.85      2230087.72     13189596.85
      2230137.72     13189596.85      2230187.72     13189596.85
      2230237.72     13189596.85      2230287.72     13189596.85
      2230337.72     13189596.85      2230387.72     13189546.86
      2230437.72     13189496.85      2230487.72     13189496.85
      2230537.72     13189546.86      2230587.72     13189546.86
      2230637.72     13189546.86      2230687.72     13189496.85

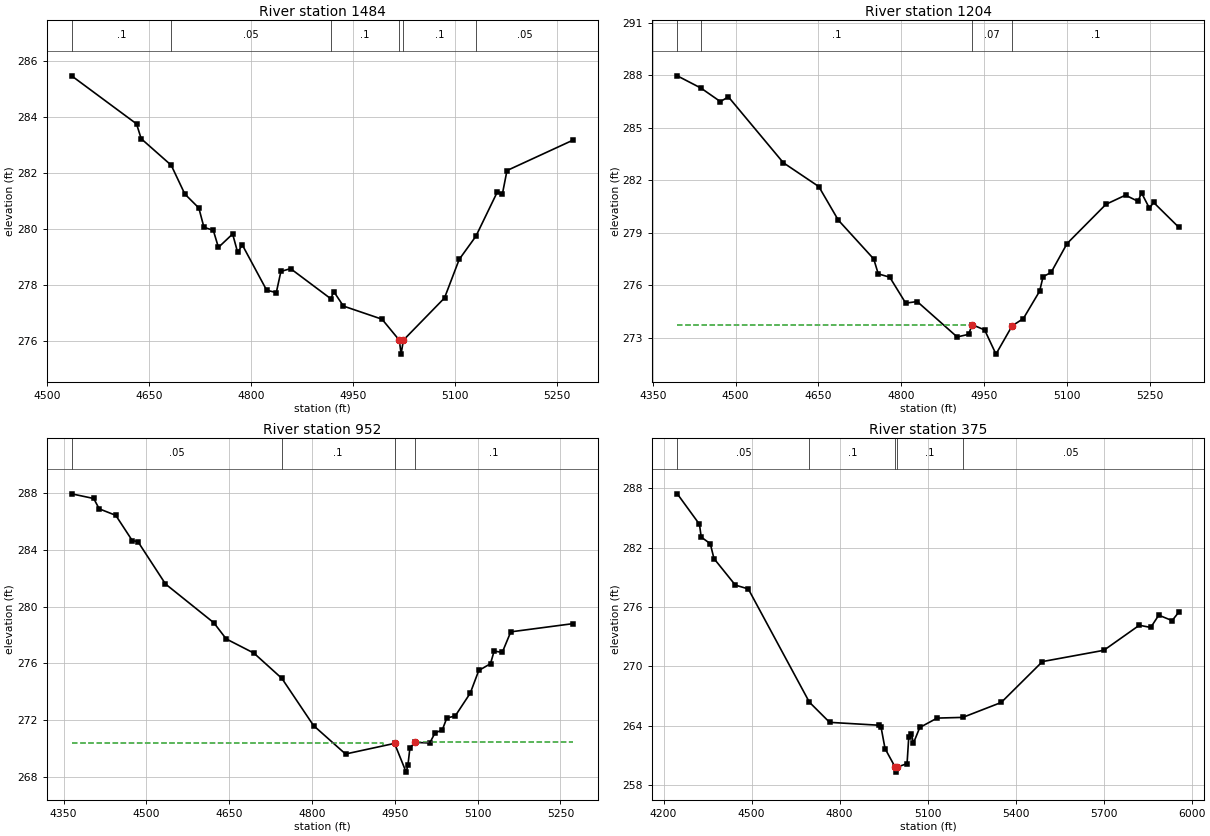
Type RM Length L Ch R = 1 ,1484    ,280,280,280
BEGIN DESCRIPTION:
UNT 168 IN LACR 2.0
END DESCRIPTION:
XS GIS Cut Line= 2
      2229838.22     13190451.17      2229343.42     13189904.29
#Sta/Elev= 30
  4536.4  285.48  4631.9  283.76  4638.7  283.23  4682.9  282.28  4702.9  281.25
  4723.5  280.75    4731  280.06  4744.8  279.95  4752.3  279.34  4773.2  279.82
  4780.6  279.16  4787.4  279.43  4823.2  277.81  4837.4  277.72  4844.2  278.48
  4858.4  278.58  4917.7   277.5  4921.9  277.76  4936.1  277.24  4992.9  276.77
  5018.3  276.02    5021  275.52  5024.3  276.02  5084.8  277.53  5106.4  278.91
    5131  279.74  5162.6  281.33    5170  281.26  5176.7  282.09  5273.9  283.18
#Mann= 6 ,-1 , 0
  4536.4      .1       0  4682.9     .05       0  4917.7      .1       0
  5018.3     .07       0  5024.3      .1       0    5131     .05       0
Bank Sta=5018.3,5024.3
XS Rating Curve= 0 ,0
Exp/Cntr=0.3,0.1

Type RM Length L Ch R = 1 ,1204    ,252,252,252
BEGIN DESCRIPTION:
Mapping XS f14da9e3
END DESCRIPTION:
XS GIS Cut Line= 2
      2230098.62     13190386.05      2229539.49     13189670.88
#Sta/Elev= 30
  4394.4  287.96  4437.3  287.26  4472.4  286.49  4486.9  286.76  4586.4     283
  4650.6  281.64  4685.8  279.73    4750  277.51  4758.2  276.66    4779  276.47
  4807.9  274.99  4828.7  275.08    4901  273.06  4921.8  273.21  4928.2  273.76
  4950.8  273.46  4971.3  272.08  5000.5  273.69  5020.9  274.11  5050.3  275.67
  5056.6   276.5  5071.1  276.74    5100  278.39  5170.5  280.63  5205.8  281.15
  5228.4   280.8  5234.8  281.28  5249.2   280.4  5256.5  280.74  5302.2  279.32
#Mann= 4 ,-1 , 0
  4394.4     .05       0  4437.3      .1       0  4928.2     .07       0
  5000.5      .1       0
#XS Ineff= 2 , 0
       0 4928.05  273.77               0
Permanent Ineff=
       T       F
Bank Sta=4928.2,5000.5
XS Rating Curve= 0 ,0
Exp/Cntr=0.3,0.1

Type RM Length L Ch R = 1 ,952     ,577,577,577
BEGIN DESCRIPTION:
Mapping XS ad6d6512
END DESCRIPTION:
XS GIS Cut Line= 3
      2230171.69     13190266.83      2230159.54     13189914.61
      2229685.87     13189623.12
#Sta/Elev= 30
  4364.4  287.97  4404.4  287.64  4414.4  286.91  4444.4  286.45  4474.4  284.66
  4484.4   284.6  4534.5   281.6  4622.1  278.86  4644.5  277.72  4694.6  276.72
  4745.4  274.93  4802.7   271.6  4860.7  269.59  4949.5  270.34  4970.5  268.31
  4973.8  268.81  4977.3     270  4986.2  270.41  5013.3  270.37  5022.9  271.08
    5036  271.29  5044.2  272.13  5059.5  272.28  5086.7  273.89  5102.1  275.49
  5123.4  275.97  5129.9  276.86  5144.7  276.77  5160.1  278.22    5273   278.8
#Mann= 4 ,-1 , 0
  4364.4     .05       0  4745.4      .1       0  4949.5     .03       0
  4986.2      .1       0
#XS Ineff= 2 , 0
       0 4928.18  270.37 4986.26       0  270.43
Permanent Ineff=
       T       T
Bank Sta=4949.5,4986.2
XS Rating Curve= 0 ,0
Exp/Cntr=0.3,0.1

Type RM Length L Ch R = 1 ,375     ,0,0,0
BEGIN DESCRIPTION:
UNT 168 IN LACR 1.0
END DESCRIPTION:
XS GIS Cut Line= 4
      2230241.85     13190203.78      2230502.28     13189774.08
      2230280.92     13189383.46      2229552.21     13189175.25
#Sta/Elev= 30
  4246.8  287.43  4322.4  284.35  4328.3  283.06  4359.3  282.39  4371.8  280.89
  4444.6  278.21  4488.8  277.82    4697  266.38    4766  264.34  4933.3  264.05
  4941.5  263.83  4954.9  261.69  4989.5  259.81  4992.2  259.31  4995.5  259.81
    5030  260.17  5035.7  262.81  5044.9   263.2  5051.6  262.23  5073.3  263.82
  5132.4  264.77  5219.8  264.84    5351  266.35  5491.4  270.48  5700.8  271.62
  5821.6  274.15  5860.6  273.93    5888  275.17  5933.4  274.62  5956.1  275.47
#Mann= 5 ,-1 , 0
  4246.8     .05       0    4697      .1       0  4989.5     .07       0
  4995.5      .1       0  5219.8     .05       0
Bank Sta=4989.5,4995.5
XS Rating Curve= 0 ,0
Exp/Cntr=0.3,0.1

Chan Stop Cuts=-1
Use User Specified Reach Order=0
Composite Channel Slope=5