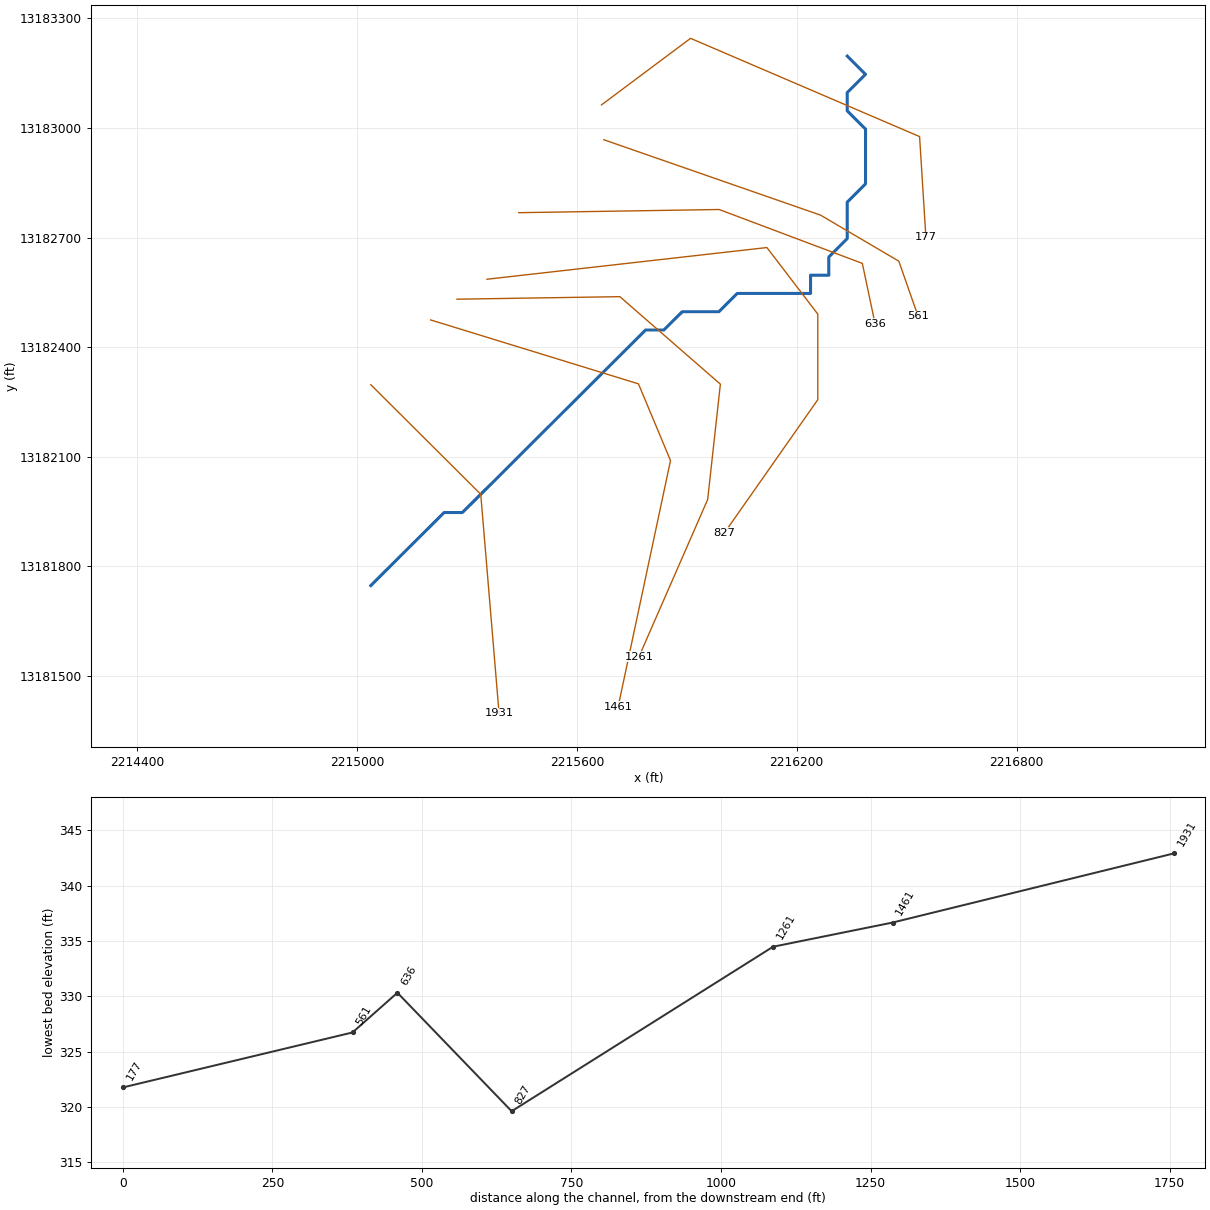
--- UNT 171 IN LACR.prj (project) ---

Proj Title=UNT 171 IN LACR Base Level Engineering
Current Plan=p01
Default Exp/Contr=0.3,0.1
English Units
Geom File=g01
Flow File=f01
Plan File=p01
Y Axis Title=Elevation
X Axis Title(PF)=Main Channel Distance
X Axis Title(XS)=Station
BEGIN DESCRIPTION:
UNT 171 IN LACR
END DESCRIPTION:
DSS Export Rating Curves= 0
DSS Export Rating Curve Sorted= 0
DSS Export Volume Flow Curves= 0
DXF OffsetX= 0
DXF OffsetY= 0
DXF ScaleX= 1
DXF ScaleY= 10

--- UNT 171 IN LACR.p01 (plan) ---

Plan Title=Multiple Run
Short Identifier=Multiple
Geom File=g01
Flow File=f01
Subcritical Flow
K Sum by GR= 0
Std Step Tol= 0.01
Critical Tol= 0.01
Num of Std Step Trials= 20
Max Error Tol= 0.3
Flow Tol Ratio= 0.001
Split Flow NTrial= 30
Split Flow Tol= 0.02
Split Flow Ratio= 0.02
Log Output Level= 0
Friction Slope Method= 1
Unsteady Friction Slope Method= 2
Unsteady Bridges Friction Slope Method= 1
Parabolic Critical Depth
Global Vel Dist=  1 , 1 , 1
Global Log Level= 0
CheckData=True
Encroach Param= -1, 0, 0, 0
BEGIN DESCRIPTION:
Multiple Run
END DESCRIPTION:

--- UNT 171 IN LACR.f01 (steady flow) ---

Flow Title=Multiple
Program Version=4.10
Number of Profiles= 7
Profile Names=10-year,25-year,50-year,1pct_min,100-year,1pct_plu,500-year
River Rch & RM=UNT 171 IN LACR,Reach-1         ,1931
     112     150     180     160     216     292     315
River Rch & RM=UNT 171 IN LACR,Reach-1         ,177
     112     150     180     160     216     292     315
Boundary for River Rch & Prof#=UNT 171 IN LACR,Reach-1         , 1
Up Type= 0
Dn Type= 3
Dn Slope=0.005
Boundary for River Rch & Prof#=UNT 171 IN LACR,Reach-1         , 2
Up Type= 0
Dn Type= 3
Dn Slope=0.005
Boundary for River Rch & Prof#=UNT 171 IN LACR,Reach-1         , 3
Up Type= 0
Dn Type= 3
Dn Slope=0.005
Boundary for River Rch & Prof#=UNT 171 IN LACR,Reach-1         , 4
Up Type= 0
Dn Type= 3
Dn Slope=0.005
Boundary for River Rch & Prof#=UNT 171 IN LACR,Reach-1         , 5
Up Type= 0
Dn Type= 3
Dn Slope=0.005
Boundary for River Rch & Prof#=UNT 171 IN LACR,Reach-1         , 6
Up Type= 0
Dn Type= 3
Dn Slope=0.005
Boundary for River Rch & Prof#=UNT 171 IN LACR,Reach-1         , 7
Up Type= 0
Dn Type= 3
Dn Slope=0.005
DSS Import GetInterval= 0
DSS Import GetPeak= 0
DSS Import FillOption= 0

--- UNT 171 IN LACR.g01 (geometry) ---

Geom Title=Existing Conditions
Program Version=4.10

River Reach=UNT 171 IN LACR ,Reach-1
Reach XY= 30
      2215037.72     13181746.85      2215087.72     13181796.86
      2215137.72     13181846.85      2215237.72     13181946.85
      2215287.72     13181946.85      2215337.72     13181996.86
      2215387.72     13182046.85      2215437.72     13182096.85
      2215487.72     13182146.86      2215537.72     13182196.85
      2215587.72     13182246.85      2215637.72     13182296.86
      2215687.72     13182346.85      2215787.72     13182446.85
      2215837.72     13182446.85      2215887.72     13182496.85
      2215987.72     13182496.85      2216037.72     13182546.85
      2216237.72     13182546.85      2216237.72     13182596.85
      2216287.72     13182596.85      2216287.72     13182646.86
      2216337.72     13182696.85      2216337.72     13182796.86
      2216387.72     13182846.85      2216387.72     13182996.85
      2216337.72     13183046.85      2216337.72     13183096.85
      2216387.72     13183146.86      2216337.72     13183196.85

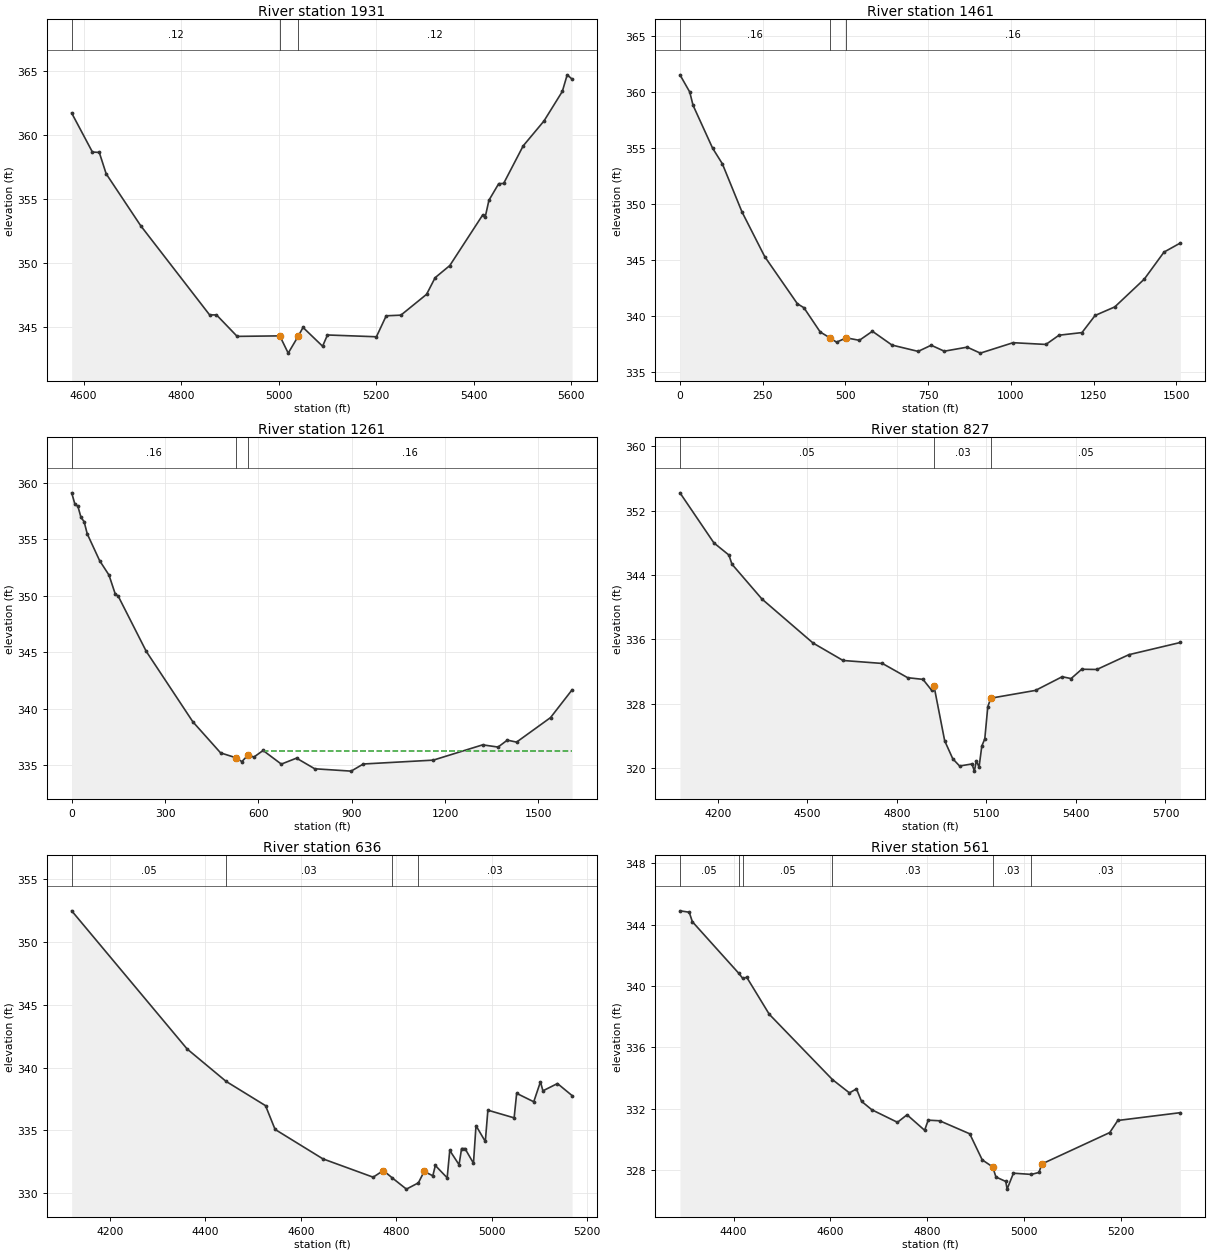
Type RM Length L Ch R = 1 ,1931    ,470,470,470
BEGIN DESCRIPTION:
UNT 171 IN LACR 2.0
END DESCRIPTION:
XS GIS Cut Line= 3
      2215037.69     13182296.88      2215337.72     13181996.86
      2215387.72     13181396.83
#Sta/Elev= 30
  4575.7   361.7  4618.2  358.65  4632.3  358.62  4646.4  356.95  4717.2  352.89
  4858.6  345.91  4872.7  345.91  4915.1  344.23  5002.5  344.27  5019.8  342.92
  5040.1  344.23  5050.2  344.93  5090.3  343.46  5100.3  344.34  5200.7   344.2
  5220.8  345.84  5250.9  345.89  5303.6  347.52  5321.1  348.82  5351.2  349.77
  5418.9  353.74    5424  353.59  5431.5  354.88  5451.6  356.18  5461.6  356.19
  5501.7  359.13  5544.4  361.08    5582  363.39    5592  364.69  5602.1  364.35
#Mann= 3 , 0 , 0
  4575.7     .12       0  5002.5     .07       0  5040.1     .12       0
Bank Sta=5002.5,5040.1
XS Rating Curve= 0 ,0
Exp/Cntr=0.3,0.1

Type RM Length L Ch R = 1 ,1461    ,200,200,200
BEGIN DESCRIPTION:
Mapping XS cb55b4fe
END DESCRIPTION:
XS GIS Cut Line= 4
      2215201.03     13182474.25      2215768.06     13182299.25
      2215855.56     13182089.25     2215712.684    13181415.412
#Sta/Elev= 30
       0 361.50429.57472359.968639.43296358.792998.58239354.9641128.1571353.5642
187.3065349.2825256.3142345.2771354.8966 341.079374.6131340.7253423.9043338.5593
 453.479338.0323473.1955337.6524502.7702338.0366542.2032337.8175581.6361338.6248
640.8536337.3932719.8284336.8296759.3159337.3781798.8033336.8472868.1144337.2074
907.7685336.67421006.904337.60511106.039337.44941145.693338.27361215.087338.5075
1254.741340.03531314.222340.79851403.444343.28061462.925345.68731512.492346.5017
#Mann= 3 , 0 , 0
       0     .16       0 453.479     .07       0502.7702     .16       0
#XS Ineff= 2 , 0
       0                  581.52       0   338.6
Permanent Ineff=
       F       T
Bank Sta=453.479,502.7702
XS Rating Curve= 0 ,0
Exp/Cntr=0.3,0.1

Type RM Length L Ch R = 1 ,1261    ,437,437,437
BEGIN DESCRIPTION:
Mapping XS e881e3b3
END DESCRIPTION:
XS GIS Cut Line= 5
     2215272.904    13182531.062     2215717.349    13182538.007
     2215991.654    13182298.423     2215956.932    13181982.451
     2215769.432    13181551.895
#Sta/Elev= 30
       0359.1051    9.99358.1364   19.97357.9081   29.96356.9266   39.95356.5576
   49.93355.4799   89.88353.1029  119.84351.8326  139.82350.1737   149.8349.9527
  239.68345.0825  389.49338.8502  478.68336.1007  527.48 335.674     547335.3288
  566.51   335.9  586.03335.7361  615.31336.3135  673.86335.1076  722.66 335.636
  781.21 334.695  898.35334.4867   937.4335.1175 1162.25335.4587 1320.95336.8107
 1370.55336.6157  1400.3337.2286 1430.06337.0537 1539.17339.2208  1608.6341.6811
#Mann= 3 , 0 , 0
       0     .16       0  527.48     .07       0  566.51     .16       0
#XS Ineff= 2 , 0
       0                   615.6       0  336.31
Permanent Ineff=
       F       T
Bank Sta=527.48,566.51
XS Rating Curve= 0 ,0
Exp/Cntr=0.3,0.1

Type RM Length L Ch R = 1 ,827     ,191,191,191
BEGIN DESCRIPTION:
Mapping XS 342875b9
END DESCRIPTION:
XS GIS Cut Line= 5
      2215354.69     13182585.71      2216118.59     13182672.52
      2216257.48     13182490.23      2216257.48     13182255.85
      2216002.95     13181891.53
#Sta/Elev= 30
  4073.2  354.23    4187     348  4237.3  346.49  4247.3  345.36    4348  341.02
  4519.1  335.55  4619.7  333.38  4751.6  333.01  4836.1  331.24  4887.5  331.03
  4916.6  329.67  4924.6  330.17  4960.2  323.39  4987.4  321.15  5010.1  320.26
  5051.7  320.51  5059.7  319.62  5066.2  320.91  5075.4  320.12  5084.6  322.74
  5094.6  323.63  5104.6  327.62  5114.6  328.69  5264.6  329.66    5354  331.36
  5383.7  331.13  5419.4  332.29    5470  332.26  5577.3   334.1    5750  335.62
#Mann= 3 ,-1 , 0
  4073.2     .05       0  4924.6     .03       0  5114.6     .05       0
Bank Sta=4924.6,5114.6
XS Rating Curve= 0 ,0
Exp/Cntr=0.3,0.1

Type RM Length L Ch R = 1 ,636     ,75,75,75
BEGIN DESCRIPTION:
Mapping XS e04b034e
END DESCRIPTION:
XS GIS Cut Line= 4
      2215441.53       13182768.      2215988.39     13182776.68
      2216379.01     13182629.12      2216413.73     13182464.22
#Sta/Elev= 30
  4120.1  352.47    4362  341.48  4443.7   338.9  4526.3  336.97  4546.3  335.08
  4646.4  332.74  4751.8  331.28  4773.2  331.81  4791.6  331.23  4821.5  330.33
  4846.6  330.83  4858.7  331.74  4876.8  331.39  4882.1  332.21  4906.9  331.23
  4912.3  333.41  4931.8  332.27  4937.1  333.56  4944.2  333.56    4962  332.39
  4967.3  335.38  4986.8  334.12  4992.2  336.61  5047.2     336  5052.5  337.95
  5088.3  337.28  5102.4  338.87  5107.5  338.15    5138  338.73  5168.7  337.77
#Mann= 4 ,-1 , 0
  4120.1     .05       0  4443.7     .03       0  4791.6     .03       0
  4846.6     .03       0
Bank Sta=4773.2,4858.7
XS Rating Curve= 0 ,0
Exp/Cntr=0.3,0.1

Type RM Length L Ch R = 1 ,561     ,384,384,384
BEGIN DESCRIPTION:
Mapping XS d76034bf
END DESCRIPTION:
XS GIS Cut Line= 4
      2215673.54     13182967.75      2216265.06     13182761.25
      2216478.56     13182635.25      2216531.05     13182484.77
#Sta/Elev= 30
  4289.1   344.9  4308.2  344.81  4314.7  344.19  4410.1  340.84  4418.6   340.5
  4427.1  340.56  4473.6  338.15    4604  333.89  4639.2  333.02  4653.7  333.28
  4664.2  332.47  4685.4  331.92  4738.4   331.1  4758.2  331.59  4794.5  330.58
  4801.9  331.24  4825.6   331.2  4887.7  330.35  4913.5  328.65  4935.1  328.19
  4941.9  327.53  4962.2  327.24  4964.9  326.74    4978  327.78  5015.1   327.7
  5030.8  327.83  5036.6  328.38  5176.9  330.43  5193.6  331.22  5322.9  331.73
#Mann= 6 ,-1 , 0
  4289.1     .05       0  4410.1      .1       0  4418.6     .05       0
    4604     .03       0  4935.1     .03       0  5015.1     .03       0
Bank Sta=4935.1,5036.6
XS Rating Curve= 0 ,0
Exp/Cntr=0.3,0.1

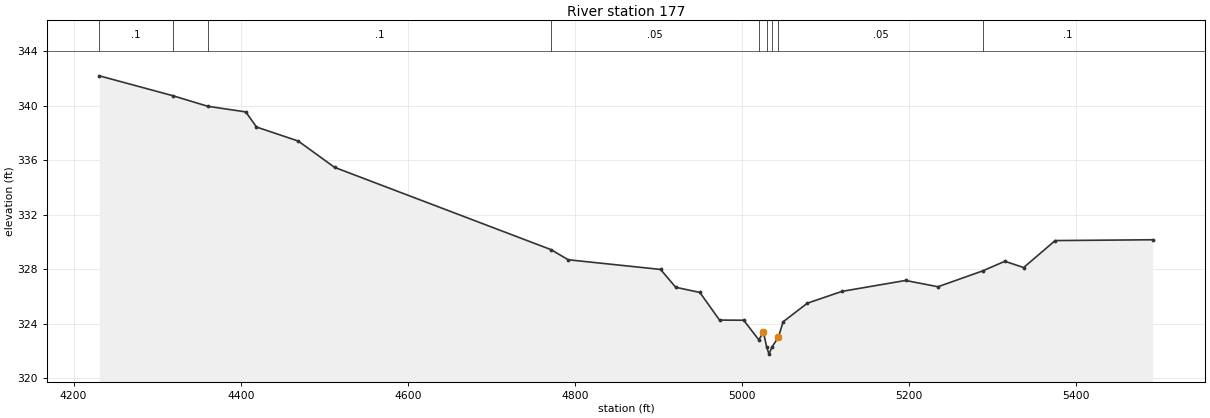
Type RM Length L Ch R = 1 ,177     ,0,0,0
BEGIN DESCRIPTION:
UNT 171 IN LACR 1.0
END DESCRIPTION:
XS GIS Cut Line= 4
      2215667.22     13183063.15      2215910.26     13183245.43
      2216535.26     13182976.34      2216552.52     13182700.25
#Sta/Elev= 30
  4230.8  342.21  4318.8  340.75  4360.7  339.97  4406.1  339.56  4418.9  338.45
  4468.9  337.42  4512.3  335.49  4771.2  329.45  4792.1   328.7  4902.6  327.99
  4920.7  326.68  4949.6   326.3  4973.2  324.27  5002.1  324.26  5020.2  322.82
  5025.7  323.39  5029.7  322.27  5032.4  321.77  5035.7  322.27  5043.6  323.01
  5049.2  324.14  5078.2  325.51  5119.8  326.38  5195.8  327.18  5234.6  326.72
    5288  327.88  5314.7  328.59  5337.2  328.13  5374.9  330.11  5491.7  330.17
#Mann= 9 ,-1 , 0
  4230.8      .1       0  4318.8     .05       0  4360.7      .1       0
  4771.2     .05       0  5020.2      .1       0  5029.7     .07       0
  5035.7      .1       0  5043.6     .05       0    5288      .1       0
Bank Sta=5025.7,5043.6
XS Rating Curve= 0 ,0
Exp/Cntr=0.3,0.1

Chan Stop Cuts=-1
Use User Specified Reach Order=0
Composite Channel Slope=5