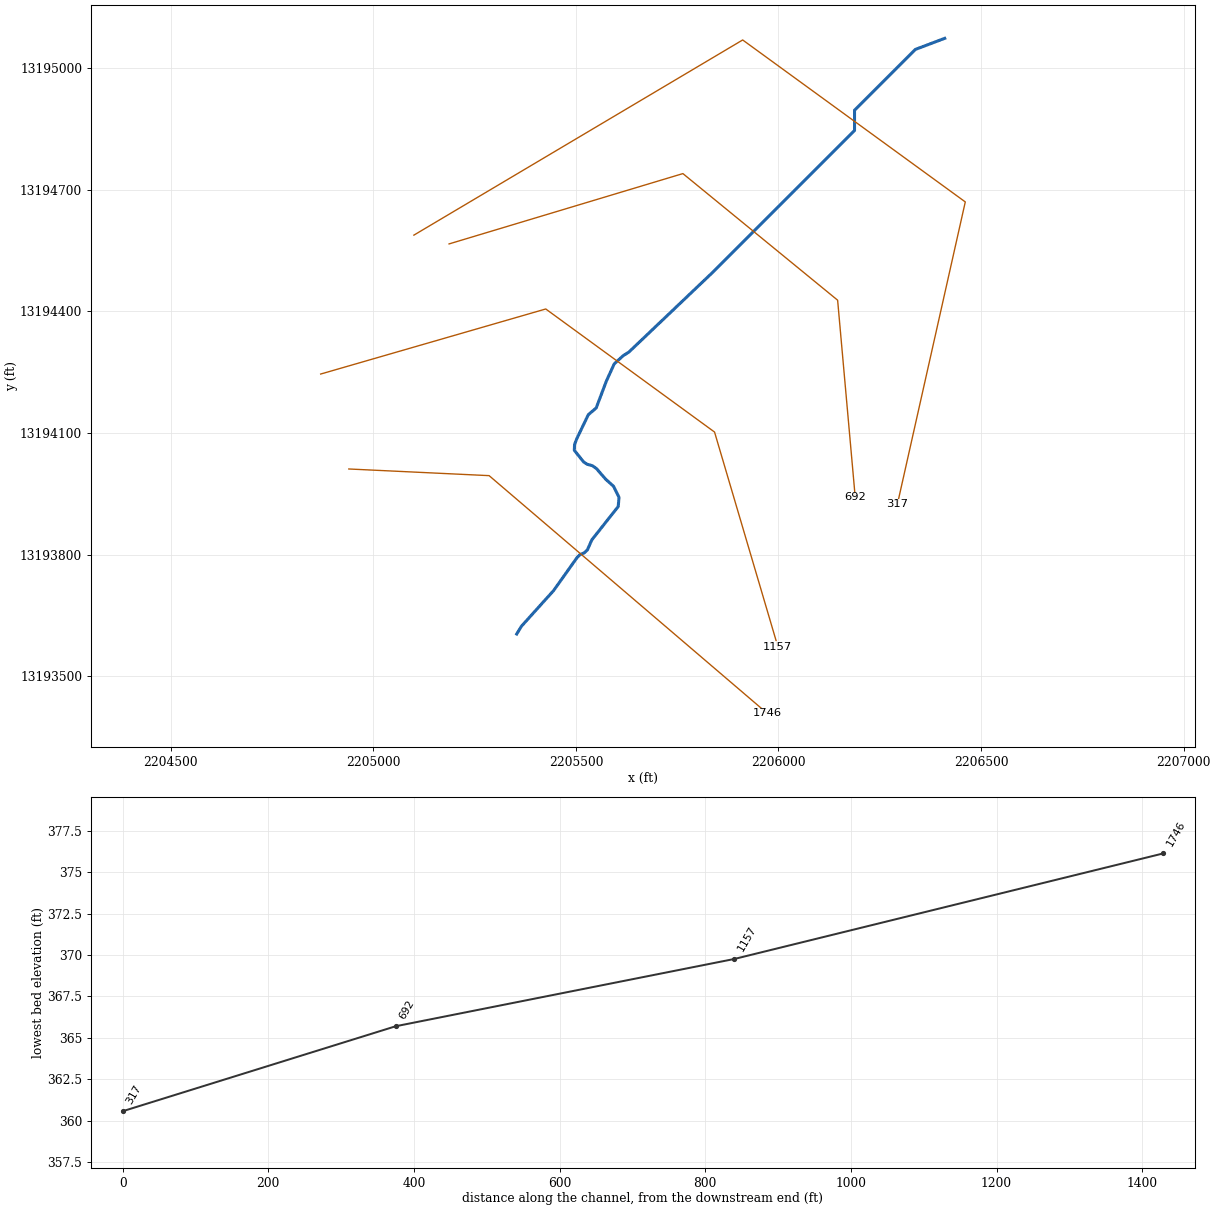
--- UNT 174 IN LACR.prj (project) ---

Proj Title=UNT 174 IN LACR Base Level Engineering
Current Plan=p01
Default Exp/Contr=0.3,0.1
English Units
Geom File=g01
Flow File=f01
Plan File=p01
BEGIN DESCRIPTION:
UNT 174 IN LACR
END DESCRIPTION:

--- UNT 174 IN LACR.p01 (plan) ---

Plan Title=Multiple Run
Short Identifier=Multiple
Geom File=g01
Flow File=f01
Subcritical Flow
K Sum by GR= 0
Std Step Tol= 0.01
Critical Tol= 0.01
Num of Std Step Trials= 20
Max Error Tol= 0.3
Flow Tol Ratio= 0.001
Split Flow NTrial= 30
Split Flow Tol= 0.02
Split Flow Ratio= 0.02
Log Output Level= 0
Friction Slope Method= 1
Unsteady Friction Slope Method= 2
Unsteady Bridges Friction Slope Method= 1
Parabolic Critical Depth
Global Vel Dist=  1 , 1 , 1
Global Log Level= 0
CheckData=True
Encroach Param= -1, 0, 0, 0
BEGIN DESCRIPTION:
Multiple Run
END DESCRIPTION:

--- UNT 174 IN LACR.f01 (steady flow) ---

Flow Title=Multiple
Number of Profiles=7
Profile Names=10-year,25-year,50-year,1pct_min,100-year,1pct_plu,500-year
River Rch & RM= UNT 174 IN LACR,Reach-1,1746
     100     134     160     142     192     260     281
Boundary for River Rch & Prof#=UNT 174 IN LACR,Reach-1,1
Up Type=0
Dn Type=3
Dn Slope=0.005
Boundary for River Rch & Prof#=UNT 174 IN LACR,Reach-1,2
Up Type=0
Dn Type=3
Dn Slope=0.005
Boundary for River Rch & Prof#=UNT 174 IN LACR,Reach-1,3
Up Type=0
Dn Type=3
Dn Slope=0.005
Boundary for River Rch & Prof#=UNT 174 IN LACR,Reach-1,4
Up Type=0
Dn Type=3
Dn Slope=0.005
Boundary for River Rch & Prof#=UNT 174 IN LACR,Reach-1,5
Up Type=0
Dn Type=3
Dn Slope=0.005
Boundary for River Rch & Prof#=UNT 174 IN LACR,Reach-1,6
Up Type=0
Dn Type=3
Dn Slope=0.005
Boundary for River Rch & Prof#=UNT 174 IN LACR,Reach-1,7
Up Type=0
Dn Type=3
Dn Slope=0.005

--- UNT 174 IN LACR.g01 (geometry) ---

Geom Title=Existing Conditions

River Reach=UNT 174 IN LACR,Reach-1
Reach XY= 30
      2205353.76     13193603.87      2205365.18     13193622.72
      2205444.66     13193710.84      2205502.76     13193792.51
      2205509.84     13193799.75      2205520.53     13193804.23
      2205528.06     13193811.22      2205539.46     13193836.58
      2205604.40     13193918.57      2205606.27     13193941.16
      2205592.92     13193968.48      2205573.62     13193985.74
      2205550.52     13194012.36      2205540.57     13194019.30
      2205527.46     13194022.97      2205518.85     13194028.60
      2205495.95     13194057.33      2205496.64     13194071.57
      2205501.85     13194085.46      2205530.54     13194145.18
      2205550.03     13194161.92      2205574.95     13194227.77
      2205594.40     13194270.48      2205616.62     13194290.97
      2205630.44     13194299.55      2205837.72     13194496.85
      2206187.72     13194846.85      2206187.72     13194896.85
      2206337.72     13195046.85      2206410.29     13195074.28

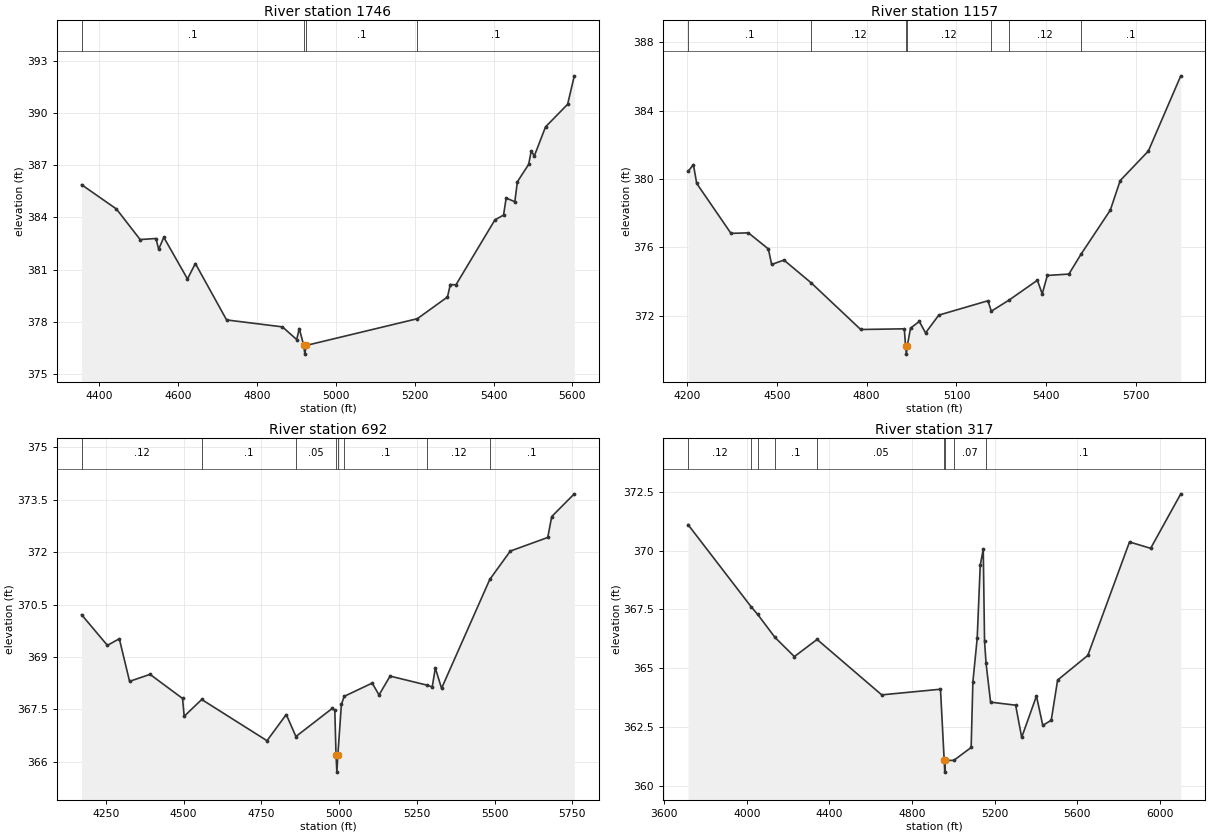
Type RM Length L Ch R = 1,1746,589,589,589
BEGIN DESCRIPTION:
UNT 174 IN LACR 1.0
END DESCRIPTION:
XS GIS Cut Line= 3
      2204939.33     13194011.23      2205285.66     13193994.80
      2205972.34     13193407.95
#Sta/Elev= 30
  4354.9  385.89  4443.4  384.49  4503.5  382.73  4543.5  382.79  4550.6  382.17
  4563.5  382.86  4623.6  380.46  4643.6  381.35  4722.8  378.10  4864.4  377.70
  4900.7  376.97  4907.2  377.60  4918.5  376.63  4921.3  376.13  4924.5  376.63
  5206.6  378.17  5283.1  379.42  5290.4  380.14  5304.6  380.12  5403.4  383.86
  5425.4  384.14  5432.0  385.12  5454.0  384.91  5460.5  386.06  5489.1  387.06
  5495.7  387.84  5503.4  387.54  5531.9  389.22  5587.9  390.52  5604.9  392.16
#Mann=4,-1,0
  4354.9     0.1       0  4918.5    0.07       0  4924.5     0.1       0
  5206.6     0.1       0
Bank Sta=4918.5,4924.5
Exp/Cntr=0.3,0.1

Type RM Length L Ch R = 1,1157,465,465,465
BEGIN DESCRIPTION:
Mapping XS b72dd7dc
END DESCRIPTION:
XS GIS Cut Line= 4
      2204869.89     13194245.59      2205425.48     13194406.20
      2205842.15     13194102.38      2205998.40     13193572.86
#Sta/Elev= 30
  4203.2  380.44  4221.2  380.84  4232.2  379.74  4346.7  376.82  4404.9  376.85
  4471.6  375.91  4482.5  375.00  4523.6  375.26  4615.1  373.92  4780.1  371.20
  4925.7  371.24  4929.8  370.26  4932.6  369.76  4935.8  370.26  4946.5  371.28
  4975.9  371.67  4996.7  371.00  5040.8  372.04  5205.1  372.88  5216.4  372.27
  5276.5  372.93  5370.3  374.08  5386.4  373.28  5403.6  374.36  5475.5  374.44
  5516.0  375.60  5613.9  378.18  5647.0  379.91  5740.9  381.63  5849.3  386.03
#Mann=7,-1,0
  4203.2     0.1       0  4615.1    0.12       0  4929.8    0.07       0
  4935.8    0.12       0  5216.4     0.1       0  5276.5    0.12       0
  5516.0     0.1       0
Bank Sta=4929.8,4935.8
Exp/Cntr=0.3,0.1

Type RM Length L Ch R = 1,692,375,375,375
BEGIN DESCRIPTION:
Mapping XS 8bc48025
END DESCRIPTION:
XS GIS Cut Line= 4
      2205186.80     13194566.80      2205764.02     13194740.40
      2206145.97     13194427.90      2206189.37     13193941.79
#Sta/Elev= 30
  4171.8  370.21  4254.9  369.33  4293.2  369.52  4326.2  368.30  4392.0  368.50
  4496.5  367.81  4501.8  367.30  4558.2  367.78  4768.0  366.60  4830.0  367.35
  4861.0  366.72  4978.6  367.53  4986.1  367.47  4989.9  366.20  4992.7  365.70
  4995.9  366.20  5007.3  367.64  5016.2  367.87  5106.3  368.25  5128.2  367.91
  5163.8  368.45  5283.1  368.19  5299.2  368.14  5309.3  368.68  5329.3  368.10
  5484.4  371.22  5550.2  372.03  5670.7  372.42  5683.5  373.02  5756.1  373.67
#Mann=8,-1,0
  4171.8    0.12       0  4558.2     0.1       0  4861.0    0.05       0
  4989.9   0.035       0  4995.9    0.05       0  5016.2     0.1       0
  5283.1    0.12       0  5484.4     0.1       0
Bank Sta=4989.9,4995.9
Exp/Cntr=0.3,0.1

Type RM Length L Ch R = 1,317,0,0,0
BEGIN DESCRIPTION:
UNT 174 IN LACR 2.0
END DESCRIPTION:
XS GIS Cut Line= 4
      2205099.98     13194588.50      2205911.59     13195070.26
      2206461.10     13194670.47      2206293.54     13193924.43
#Sta/Elev= 30
  3714.7  371.11  4021.6  367.60  4052.0  367.29  4135.8  366.31  4230.1  365.49
  4340.2  366.22  4653.4  363.86  4938.2  364.10  4956.2  361.07  4959.0  360.57
  4962.2  361.07  5002.7  361.07  5086.8  361.62  5095.2  364.41  5116.1  366.27
  5130.8  369.37  5145.5  370.07  5151.7  366.15  5159.1  365.20  5181.0  363.55
  5302.4  363.42  5331.7  362.05  5403.3  363.81  5434.0  362.56  5475.0  362.78
  5505.8  364.49  5652.2  365.54  5854.2  370.37  5956.7  370.10  6102.7  372.42
#Mann=9,-1,0
  3714.7    0.12       0  4021.6     0.1       0  4052.0    0.12       0
  4135.8     0.1       0  4340.2    0.05       0  4956.2   0.035       0
  4962.2    0.05       0  5002.7    0.07       0  5159.1     0.1       0
Bank Sta=4956.2,4962.2
Exp/Cntr=0.3,0.1

Chan Stop Cuts=-1