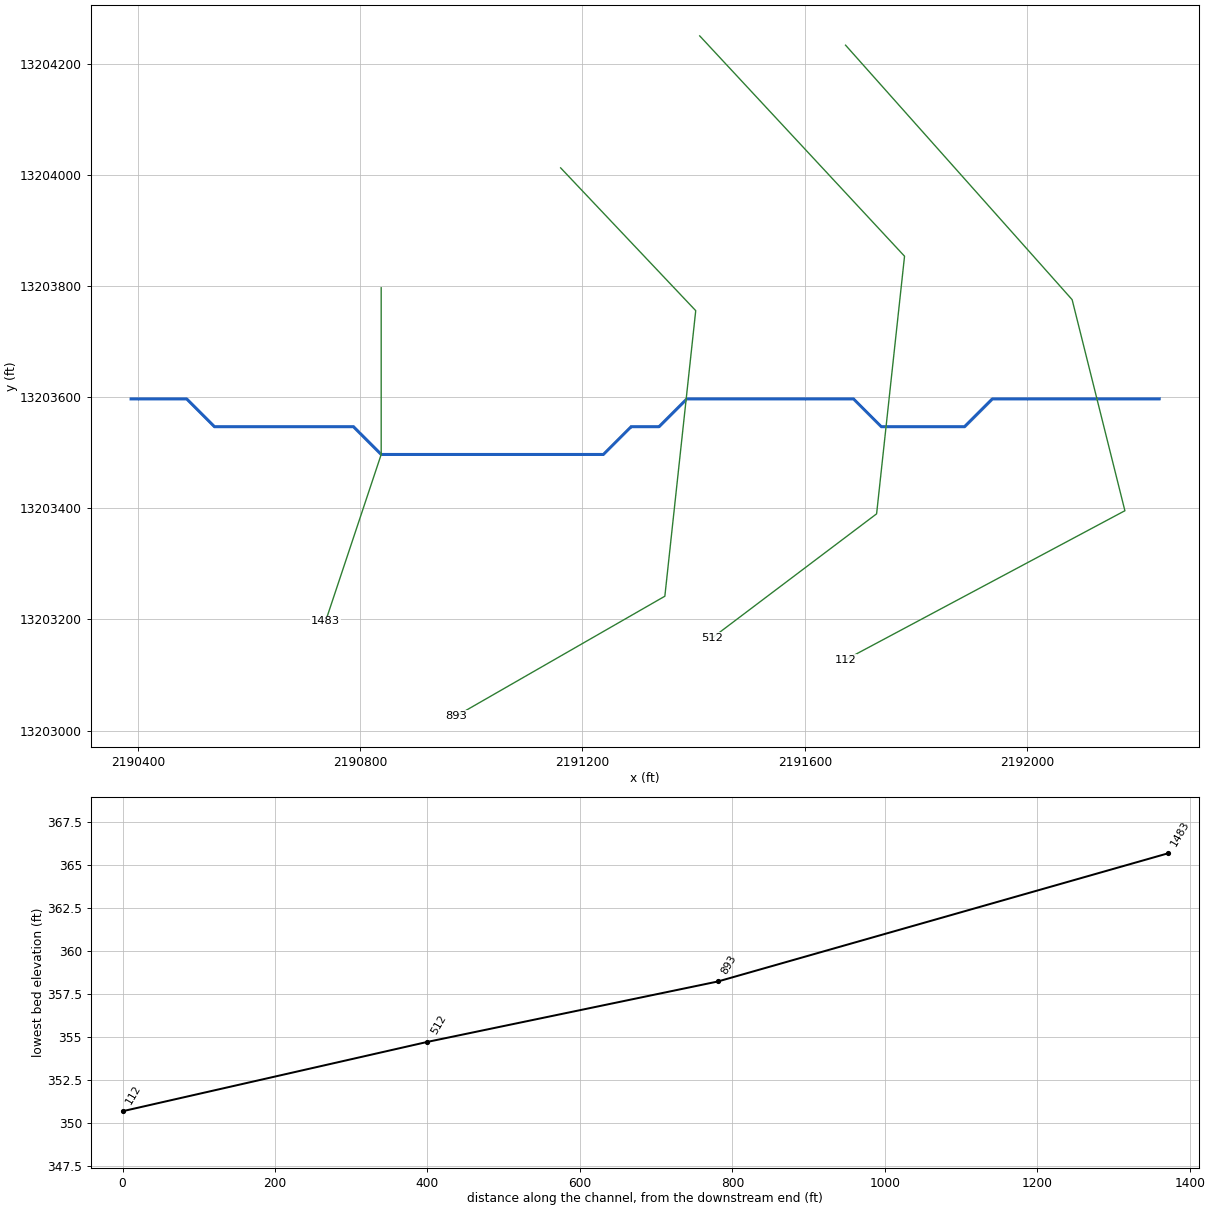
--- UNT 177 IN LACR.prj (project) ---

Proj Title=UNT 177 IN LACR Base Level Engineering
Current Plan=p01
Default Exp/Contr=0.3,0.1
English Units
Geom File=g01
Flow File=f01
Plan File=p01
BEGIN DESCRIPTION:
UNT 177 IN LACR
END DESCRIPTION:

--- UNT 177 IN LACR.p01 (plan) ---

Plan Title=Multiple Run
Short Identifier=Multiple
Geom File=g01
Flow File=f01
Subcritical Flow
K Sum by GR= 0
Std Step Tol= 0.01
Critical Tol= 0.01
Num of Std Step Trials= 20
Max Error Tol= 0.3
Flow Tol Ratio= 0.001
Split Flow NTrial= 30
Split Flow Tol= 0.02
Split Flow Ratio= 0.02
Log Output Level= 0
Friction Slope Method= 1
Unsteady Friction Slope Method= 2
Unsteady Bridges Friction Slope Method= 1
Parabolic Critical Depth
Global Vel Dist=  1 , 1 , 1
Global Log Level= 0
CheckData=True
Encroach Param= -1, 0, 0, 0
BEGIN DESCRIPTION:
Multiple Run
END DESCRIPTION:

--- UNT 177 IN LACR.f01 (steady flow) ---

Flow Title=Multiple
Number of Profiles=7
Profile Names=10-year,25-year,50-year,1pct_min,100-year,1pct_plu,500-year
River Rch & RM= UNT 177 IN LACR,Reach-1,1483
     117     158     191     171     231     312     342
Boundary for River Rch & Prof#=UNT 177 IN LACR,Reach-1,1
Up Type=0
Dn Type=3
Dn Slope=0.005
Boundary for River Rch & Prof#=UNT 177 IN LACR,Reach-1,2
Up Type=0
Dn Type=3
Dn Slope=0.005
Boundary for River Rch & Prof#=UNT 177 IN LACR,Reach-1,3
Up Type=0
Dn Type=3
Dn Slope=0.005
Boundary for River Rch & Prof#=UNT 177 IN LACR,Reach-1,4
Up Type=0
Dn Type=3
Dn Slope=0.005
Boundary for River Rch & Prof#=UNT 177 IN LACR,Reach-1,5
Up Type=0
Dn Type=3
Dn Slope=0.005
Boundary for River Rch & Prof#=UNT 177 IN LACR,Reach-1,6
Up Type=0
Dn Type=3
Dn Slope=0.005
Boundary for River Rch & Prof#=UNT 177 IN LACR,Reach-1,7
Up Type=0
Dn Type=3
Dn Slope=0.005

--- UNT 177 IN LACR.g01 (geometry) ---

Geom Title=Existing Conditions

River Reach=UNT 177 IN LACR,Reach-1
Reach XY= 14
      2190387.72     13203596.85      2190487.72     13203596.85
      2190537.72     13203546.85      2190787.72     13203546.85
      2190837.72     13203496.85      2191237.72     13203496.85
      2191287.72     13203546.85      2191337.72     13203546.85
      2191387.72     13203596.85      2191687.72     13203596.85
      2191737.72     13203546.85      2191887.72     13203546.85
      2191937.72     13203596.85      2192237.72     13203596.85

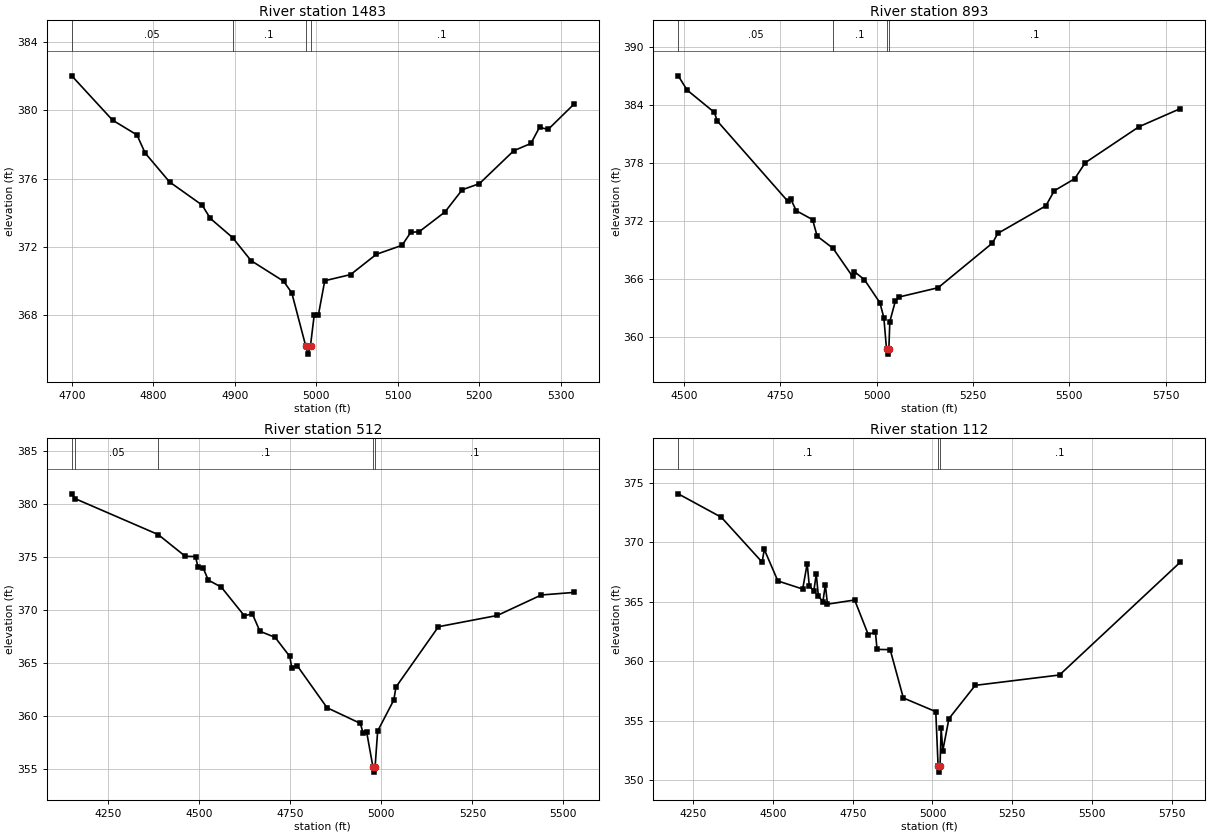
Type RM Length L Ch R = 1,1483,590,590,590
BEGIN DESCRIPTION:
UNT 177 IN LACR 2.0
END DESCRIPTION:
XS GIS Cut Line= 3
      2190837.72     13203796.85      2190837.72     13203496.85
      2190737.73     13203196.88
#Sta/Elev= 30
  4700.0  382.03  4750.0  379.43  4780.0  378.56  4790.0  377.50  4820.0  375.80
  4860.0  374.44  4870.0  373.66  4897.4  372.53  4920.0  371.18  4960.0  369.97
  4970.0  369.29  4987.0  366.19  4989.8  365.69  4993.0  366.19  4997.5  367.97
  5002.6  367.97  5010.5  370.00  5042.2  370.36  5073.8  371.55  5105.4  372.08
  5116.0  372.84  5126.5  372.88  5158.1  374.04  5179.2  375.34  5200.3  375.70
  5242.4  377.63  5263.5  378.06  5274.1  379.01  5284.6  378.88  5316.2  380.36
#Mann=4,-1,0
  4700.0    0.05       0  4897.4     0.1       0  4987.0    0.07       0
  4993.0     0.1       0
Bank Sta=4987,4993
Exp/Cntr=0.3,0.1

Type RM Length L Ch R = 1,893,381,381,381
BEGIN DESCRIPTION:
Mapping XS fc92ca34
END DESCRIPTION:
XS GIS Cut Line= 4
      2191160.69     13204012.61      2191403.77     13203755.65
      2191348.21     13203241.76      2190973.21     13203026.48
#Sta/Elev= 30
  4485.3  386.99  4508.3  385.52  4579.1  383.21  4586.4  382.33  4770.1  374.01
  4777.4  374.25  4791.5  373.05  4834.0  372.13  4845.8  370.42  4887.0  369.17
  4937.6  366.26  4942.6  366.75  4968.6  365.92  5008.8  363.53  5018.9  361.99
  5025.9  358.73  5028.7  358.23  5031.9  358.73  5034.4  361.59  5049.0  363.75
  5059.1  364.14  5159.7  365.09  5300.5  369.70  5314.8  370.71  5439.5  373.56
  5461.1  375.11  5514.3  376.36  5541.6  378.01  5681.1  381.73  5788.3  383.60
#Mann=4,-1,0
  4485.3    0.05       0  4887.0     0.1       0  5025.9    0.07       0
  5031.9     0.1       0
Bank Sta=5025.9,5031.9
Exp/Cntr=0.3,0.1

Type RM Length L Ch R = 1,512,400,400,400
BEGIN DESCRIPTION:
Mapping XS 05a022b7
END DESCRIPTION:
XS GIS Cut Line= 4
      2191410.93     13204250.18      2191779.56     13203853.63
      2191729.29     13203390.03      2191433.27     13203166.63
#Sta/Elev= 30
  4150.0  380.93  4159.6  380.47  4387.4  377.09  4461.4  375.05  4489.8  375.02
  4496.6  374.01  4510.7  373.95  4524.9  372.80  4560.6  372.14  4624.1  369.43
  4645.6  369.64  4666.6  367.98  4708.3  367.41  4748.5  365.61  4754.2  364.54
  4768.7  364.75  4850.9  360.78  4942.5  359.30  4949.7  358.40  4959.8  358.47
  4976.9  355.21  4979.6  354.71  4982.9  355.21  4989.9  358.58  5034.2  361.50
  5040.2  362.73  5156.8  368.41  5318.5  369.47  5439.3  371.40  5528.6  371.64
#Mann=5,-1,0
  4150.0     0.1       0  4159.6    0.05       0  4387.4     0.1       0
  4976.9    0.07       0  4982.9     0.1       0
Bank Sta=4976.9,4982.9
Exp/Cntr=0.3,0.1

Type RM Length L Ch R = 1,112,0,0,0
BEGIN DESCRIPTION:
UNT 177 IN LACR 1.0
END DESCRIPTION:
XS GIS Cut Line= 4
      2191673.42     13204233.46      2192081.17     13203775.43
      2192176.12     13203395.62      2191673.47     13203127.54
#Sta/Elev= 30
  4202.7  374.05  4337.9  372.08  4465.8  368.31  4472.5  369.38  4515.1  366.73
  4592.9  366.05  4607.1  368.18  4613.8  366.29  4628.0  365.92  4635.5  367.30
  4642.2  365.45  4656.4  365.00  4664.0  366.41  4670.7  364.78  4755.9  365.13
  4798.6  362.22  4821.0  362.45  4826.1  360.98  4867.3  360.96  4908.6  356.90
  5010.3  355.75  5017.6  351.17  5020.4  350.67  5023.6  351.17  5027.1  354.35
  5032.3  352.47  5051.5  355.16  5134.0  357.96  5398.3  358.83  5777.1  368.31
#Mann=3,-1,0
  4202.7     0.1       0  5017.6    0.07       0  5023.6     0.1       0
Bank Sta=5017.6,5023.6
Exp/Cntr=0.3,0.1

Chan Stop Cuts=-1