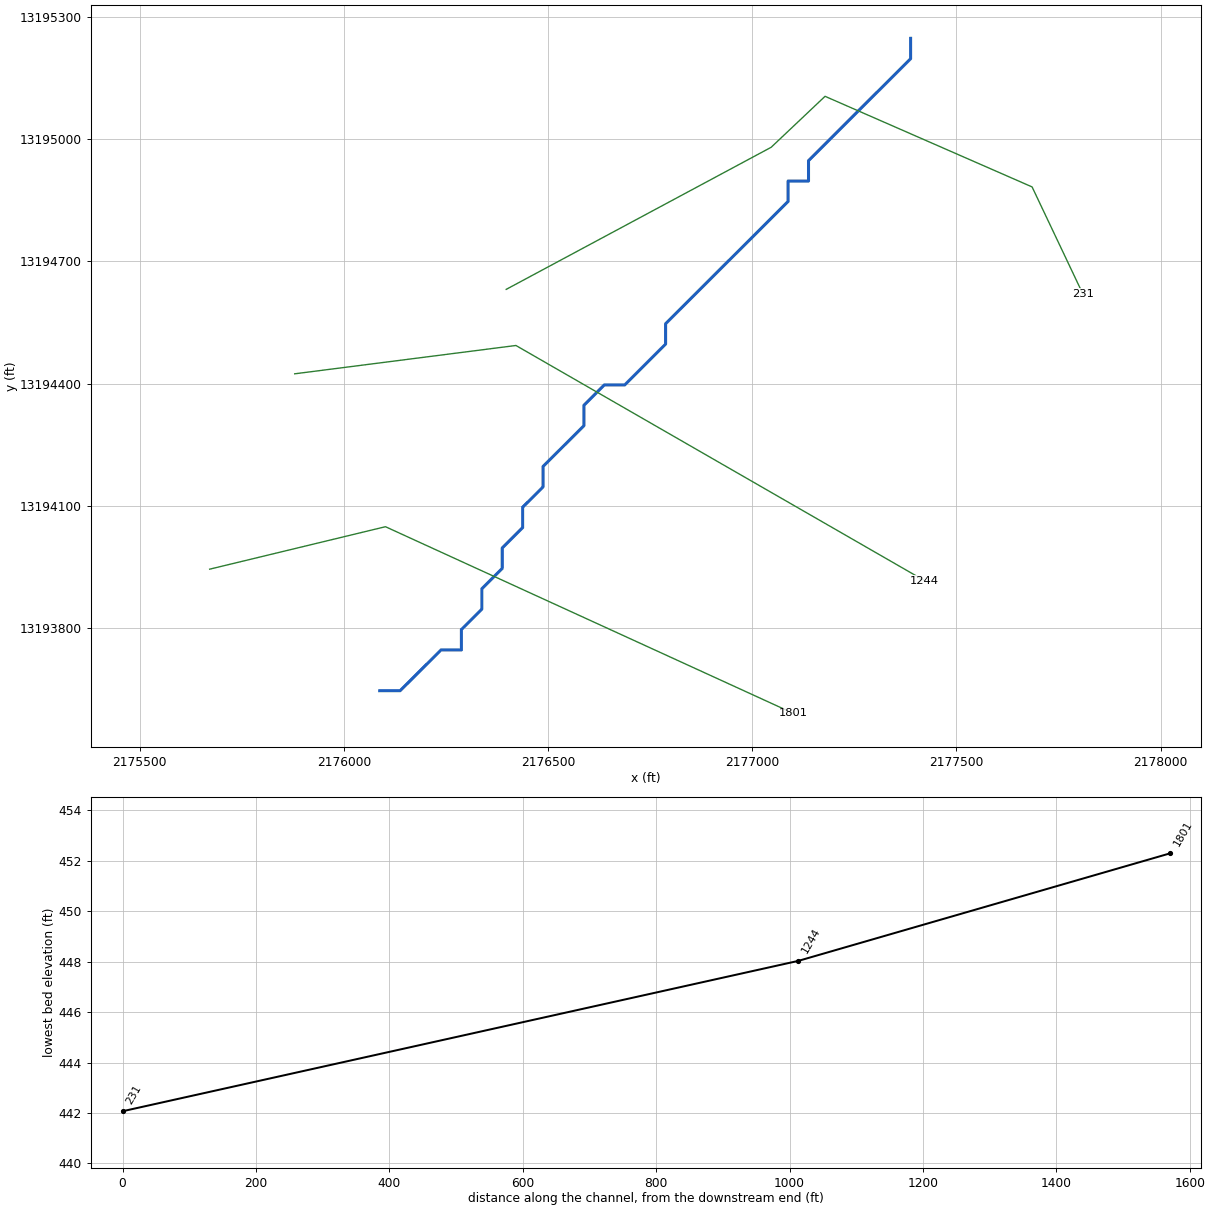
--- UNT 178 IN LACR.prj (project) ---

Proj Title=UNT 178 IN LACR Base Level Engineering
Current Plan=p01
Default Exp/Contr=0.3,0.1
English Units
Geom File=g01
Flow File=f01
Plan File=p01
BEGIN DESCRIPTION:
UNT 178 IN LACR
END DESCRIPTION:

--- UNT 178 IN LACR.p01 (plan) ---

Plan Title=Multiple Run
Short Identifier=Multiple
Geom File=g01
Flow File=f01
Subcritical Flow
K Sum by GR= 0
Std Step Tol= 0.01
Critical Tol= 0.01
Num of Std Step Trials= 20
Max Error Tol= 0.3
Flow Tol Ratio= 0.001
Split Flow NTrial= 30
Split Flow Tol= 0.02
Split Flow Ratio= 0.02
Log Output Level= 0
Friction Slope Method= 1
Unsteady Friction Slope Method= 2
Unsteady Bridges Friction Slope Method= 1
Parabolic Critical Depth
Global Vel Dist=  1 , 1 , 1
Global Log Level= 0
CheckData=True
Encroach Param= -1, 0, 0, 0
BEGIN DESCRIPTION:
Multiple Run
END DESCRIPTION:

--- UNT 178 IN LACR.f01 (steady flow) ---

Flow Title=Multiple
Number of Profiles=7
Profile Names=10-year,25-year,50-year,1pct_min,100-year,1pct_plu,500-year
River Rch & RM= UNT 178 IN LACR,Reach-1,1801
     123     166     201     180     243     329     360
Boundary for River Rch & Prof#=UNT 178 IN LACR,Reach-1,1
Up Type=0
Dn Type=3
Dn Slope=0.005
Boundary for River Rch & Prof#=UNT 178 IN LACR,Reach-1,2
Up Type=0
Dn Type=3
Dn Slope=0.005
Boundary for River Rch & Prof#=UNT 178 IN LACR,Reach-1,3
Up Type=0
Dn Type=3
Dn Slope=0.005
Boundary for River Rch & Prof#=UNT 178 IN LACR,Reach-1,4
Up Type=0
Dn Type=3
Dn Slope=0.005
Boundary for River Rch & Prof#=UNT 178 IN LACR,Reach-1,5
Up Type=0
Dn Type=3
Dn Slope=0.005
Boundary for River Rch & Prof#=UNT 178 IN LACR,Reach-1,6
Up Type=0
Dn Type=3
Dn Slope=0.005
Boundary for River Rch & Prof#=UNT 178 IN LACR,Reach-1,7
Up Type=0
Dn Type=3
Dn Slope=0.005

--- UNT 178 IN LACR.g01 (geometry) ---

Geom Title=Existing Conditions

River Reach=UNT 178 IN LACR,Reach-1
Reach XY= 30
      2176087.72     13193646.86      2176137.72     13193646.86
      2176237.72     13193746.85      2176287.72     13193746.85
      2176287.72     13193796.86      2176337.72     13193846.85
      2176337.72     13193896.85      2176387.72     13193946.86
      2176387.72     13193996.85      2176437.72     13194046.85
      2176437.72     13194096.85      2176487.72     13194146.85
      2176487.72     13194196.85      2176587.72     13194296.86
      2176587.72     13194346.85      2176637.72     13194396.85
      2176687.72     13194396.85      2176737.72     13194446.86
      2176787.72     13194496.85      2176787.72     13194546.85
      2176837.72     13194596.86      2176887.72     13194646.85
      2177087.72     13194846.85      2177087.72     13194896.85
      2177137.72     13194896.85      2177137.72     13194946.86
      2177187.72     13194996.85      2177287.72     13195096.86
      2177387.72     13195196.85      2177387.72     13195246.85

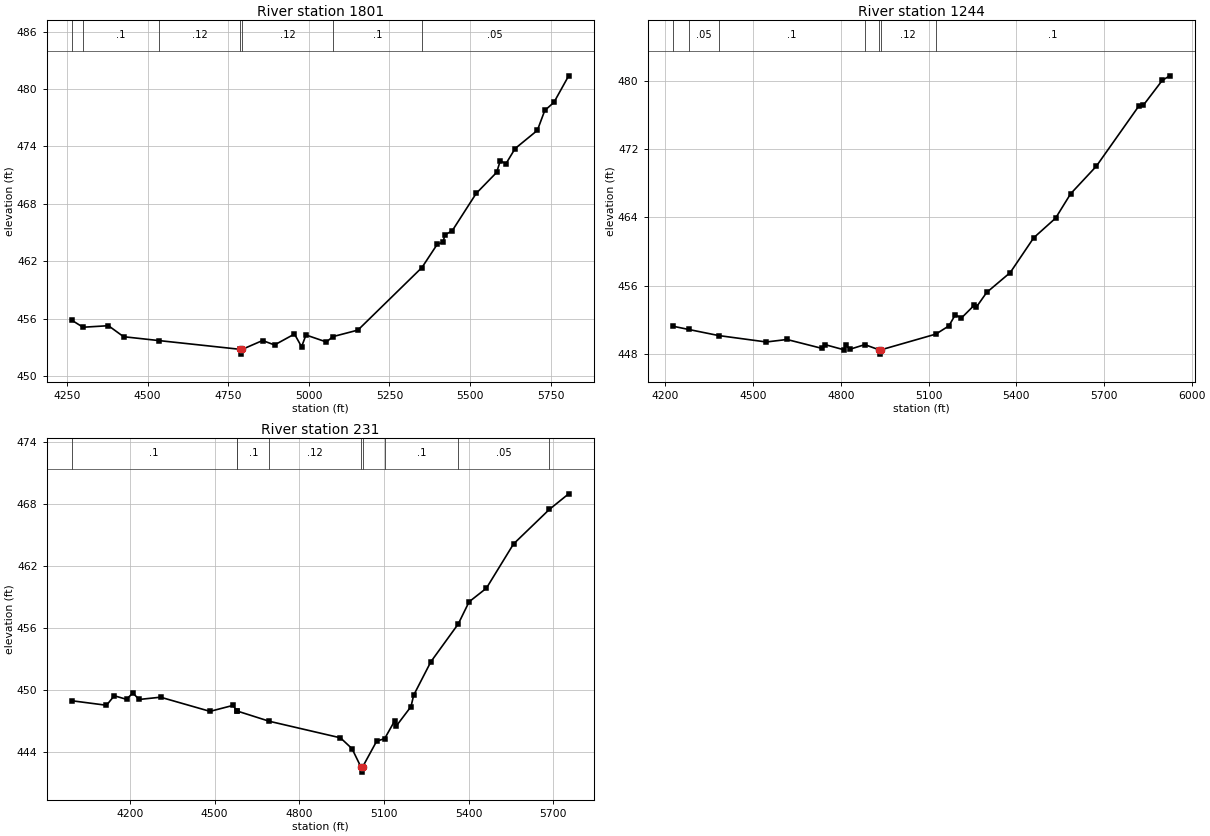
Type RM Length L Ch R = 1,1801,557,557,557
BEGIN DESCRIPTION:
UNT 178 IN LACR 2.0
END DESCRIPTION:
XS GIS Cut Line= 3
      2175671.33     13193944.95      2176101.84     13194049.10
      2177100.69     13193591.30
#Sta/Elev= 30
  4264.3  455.85  4299.9  455.10  4378.8  455.26  4425.8  454.11  4534.1  453.71
  4787.7  452.79  4790.5  452.29  4793.7  452.79  4856.7  453.71  4893.9  453.25
  4955.7  454.39  4977.7  453.06  4991.4  454.29  5054.7  453.56  5074.9  454.12
  5152.4  454.80  5351.0  461.34  5398.9  463.79  5416.4  463.97  5421.9  464.74
  5444.9  465.18  5519.4  469.09  5582.7  471.28  5593.9  472.50  5611.4  472.18
  5639.9  473.77  5708.9  475.67  5731.9  477.75  5760.4  478.60  5806.0  481.37
#Mann=7,-1,0
  4264.3    0.05       0  4299.9     0.1       0  4534.1    0.12       0
  4787.7    0.07       0  4793.7    0.12       0  5074.9     0.1       0
  5351.0    0.05       0
Bank Sta=4787.7,4793.7
Exp/Cntr=0.3,0.1

Type RM Length L Ch R = 1,1244,1013,1013,1013
BEGIN DESCRIPTION:
Mapping XS 489cadf2
END DESCRIPTION:
XS GIS Cut Line= 3
      2175879.59     13194424.10      2176421.28     13194493.55
      2177421.24     13193917.18
#Sta/Elev= 30
  4224.6  451.30  4280.0  450.91  4382.1  450.20  4545.3  449.45  4615.9  449.74
  4736.9  448.69  4747.0  449.13  4810.6  448.54  4816.4  449.07  4832.1  448.61
  4882.2  449.14  4931.1  448.53  4933.9  448.03  4937.1  448.53  5125.1  450.37
  5169.7  451.33  5191.3  452.61  5212.8  452.26  5255.9  453.73  5262.9  453.49
  5299.0  455.24  5379.5  457.56  5459.9  461.63  5534.6  463.92  5586.1  466.77
  5674.0  469.99  5819.1  477.01  5834.9  477.12  5899.5  480.02  5924.9  480.55
#Mann=7,-1,0
  4224.6     0.1       0  4280.0    0.05       0  4382.1     0.1       0
  4882.2    0.12       0  4931.1    0.07       0  4937.1    0.12       0
  5125.1     0.1       0
Bank Sta=4931.1,4937.1
Exp/Cntr=0.3,0.1

Type RM Length L Ch R = 1,231,0,0,0
BEGIN DESCRIPTION:
UNT 178 IN LACR 1.0
END DESCRIPTION:
XS GIS Cut Line= 5
      2176397.45     13194631.16      2177046.28     13194979.66
      2177178.23     13195104.66      2177685.17     13194882.44
      2177809.37     13194620.24
#Sta/Elev= 30
  3992.7  448.98  4116.6  448.54  4144.2  449.46  4188.0  449.11  4209.9  449.74
  4231.9  449.10  4308.2  449.32  4483.5  447.95  4565.5  448.53  4578.9  447.97
  4580.0  447.98  4693.8  446.99  4945.7  445.39  4986.8  444.34  5018.3  442.57
  5021.1  442.07  5024.3  442.57  5074.2  445.07  5102.4  445.31  5138.2  447.04
  5143.6  446.53  5195.8  448.41  5205.2  449.51  5266.0  452.74  5363.3  456.41
  5401.7  458.55  5463.1  459.87  5559.2  464.15  5686.1  467.49  5754.6  469.00
#Mann=9,-1,0
  3992.7     0.1       0  4578.9    0.12       0  4580.0     0.1       0
  4693.8    0.12       0  5018.3    0.07       0  5024.3    0.12       0
  5102.4     0.1       0  5363.3    0.05       0  5686.1     0.1       0
Bank Sta=5018.3,5024.3
Exp/Cntr=0.3,0.1

Chan Stop Cuts=-1