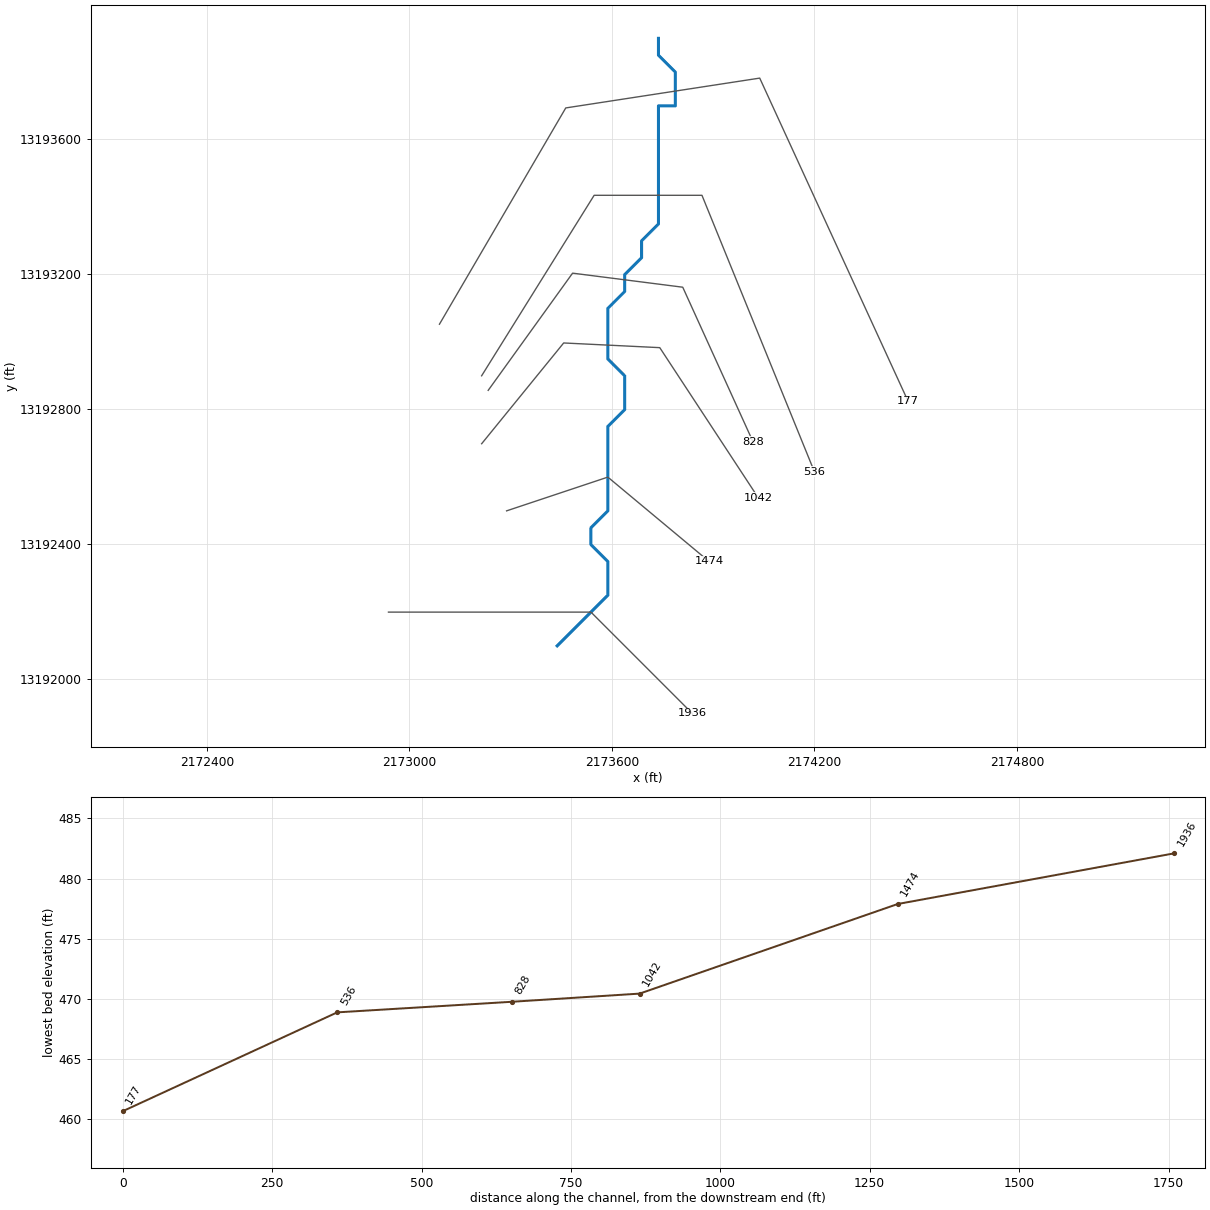
--- UNT 179 IN LACR.prj (project) ---

Proj Title=UNT 179 IN LACR Base Level Engineering
Current Plan=p01
Default Exp/Contr=0.3,0.1
English Units
Geom File=g01
Flow File=f01
Plan File=p01
Y Axis Title=Elevation
X Axis Title(PF)=Main Channel Distance
X Axis Title(XS)=Station
BEGIN DESCRIPTION:
UNT 179 IN LACR
END DESCRIPTION:
DSS Export Rating Curves= 0
DSS Export Rating Curve Sorted= 0
DSS Export Volume Flow Curves= 0
DXF OffsetX= 0
DXF OffsetY= 0
DXF ScaleX= 1
DXF ScaleY= 10

--- UNT 179 IN LACR.p01 (plan) ---

Plan Title=Multiple Run
Short Identifier=Multiple
Geom File=g01
Flow File=f01
Subcritical Flow
K Sum by GR= 0
Std Step Tol= 0.01
Critical Tol= 0.01
Num of Std Step Trials= 20
Max Error Tol= 0.3
Flow Tol Ratio= 0.001
Split Flow NTrial= 30
Split Flow Tol= 0.02
Split Flow Ratio= 0.02
Log Output Level= 0
Friction Slope Method= 1
Unsteady Friction Slope Method= 2
Unsteady Bridges Friction Slope Method= 1
Parabolic Critical Depth
Global Vel Dist=  1 , 1 , 1
Global Log Level= 0
CheckData=True
Encroach Param= -1, 0, 0, 0
BEGIN DESCRIPTION:
Multiple Run
END DESCRIPTION:

--- UNT 179 IN LACR.f01 (steady flow) ---

Flow Title=Multiple
Program Version=4.10
Number of Profiles= 7
Profile Names=10-year,25-year,50-year,1pct_min,100-year,1pct_plu,500-year
River Rch & RM=UNT 179 IN LACR,Reach-1         ,1936
     102     137     165     147     199     269     292
Boundary for River Rch & Prof#=UNT 179 IN LACR,Reach-1         , 1
Up Type= 0
Dn Type= 3
Dn Slope=0.015
Boundary for River Rch & Prof#=UNT 179 IN LACR,Reach-1         , 2
Up Type= 0
Dn Type= 3
Dn Slope=0.015
Boundary for River Rch & Prof#=UNT 179 IN LACR,Reach-1         , 3
Up Type= 0
Dn Type= 3
Dn Slope=0.015
Boundary for River Rch & Prof#=UNT 179 IN LACR,Reach-1         , 4
Up Type= 0
Dn Type= 3
Dn Slope=0.015
Boundary for River Rch & Prof#=UNT 179 IN LACR,Reach-1         , 5
Up Type= 0
Dn Type= 3
Dn Slope=0.015
Boundary for River Rch & Prof#=UNT 179 IN LACR,Reach-1         , 6
Up Type= 0
Dn Type= 3
Dn Slope=0.015
Boundary for River Rch & Prof#=UNT 179 IN LACR,Reach-1         , 7
Up Type= 0
Dn Type= 3
Dn Slope=0.015
DSS Import GetInterval= 0
DSS Import GetPeak= 0
DSS Import FillOption= 0

--- UNT 179 IN LACR.g01 (geometry) ---

Geom Title=Existing Conditions
Program Version=4.10

River Reach=UNT 179 IN LACR ,Reach-1
Reach XY= 23
      2173437.72     13192096.85      2173487.72     13192146.86
      2173537.72     13192196.85      2173587.72     13192246.85
      2173587.72     13192346.85      2173537.72     13192396.85
      2173537.72     13192446.85      2173587.72     13192496.86
      2173587.72     13192746.85      2173637.72     13192796.86
      2173637.72     13192896.85      2173587.72     13192946.85
      2173587.72     13193096.85      2173637.72     13193146.86
      2173637.72     13193196.85      2173687.72     13193246.85
      2173687.72     13193296.86      2173737.72     13193346.85
      2173737.72     13193696.85      2173787.72     13193696.85
      2173787.72     13193796.86      2173737.72     13193846.85
      2173737.72     13193896.85

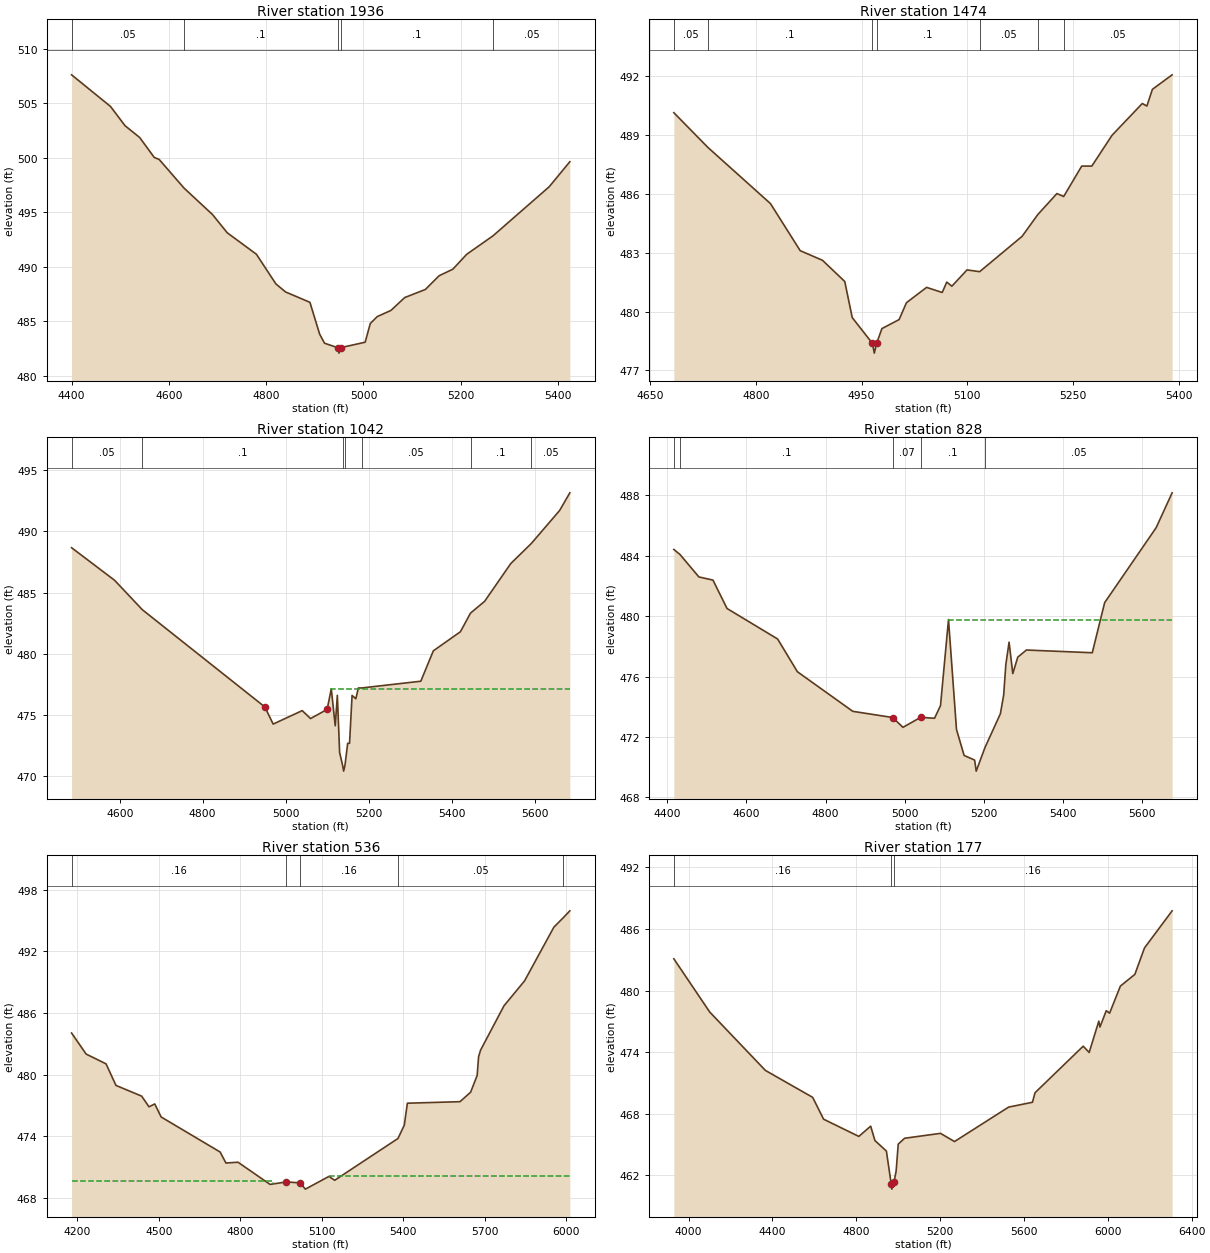
Type RM Length L Ch R = 1 ,1936    ,462,462,462
BEGIN DESCRIPTION:
UNT 179 IN LACR 3.0
END DESCRIPTION:
XS GIS Cut Line= 3
      2172937.72     13192196.85      2173537.72     13192196.85
      2173837.75     13191896.83
#Sta/Elev= 30
    4400  507.62    4480  504.72    4510  502.95    4540  501.87    4570  500.04
    4580  499.86  4631.2  497.23    4690  494.79    4720  493.13    4780  491.16
    4820  488.44    4840   487.7    4890  486.75    4910  483.83    4920     483
    4947  482.59  4949.8  482.09    4953  482.59  5003.5  483.09  5014.1  484.81
  5028.3  485.44  5056.6  486.01  5084.9  487.19  5127.3  487.93  5155.6  489.19
  5183.8  489.79  5212.1  491.15  5266.6  492.86  5381.8  497.35  5424.3  499.65
#Mann= 5 ,-1 , 0
    4400     .05       0  4631.2      .1       0    4947     .07       0
    4953      .1       0  5266.6     .05       0
Bank Sta=4947,4953
XS Rating Curve= 0 ,0
Exp/Cntr=0.3,0.1

Type RM Length L Ch R = 1 ,1474    ,432,432,432
BEGIN DESCRIPTION:
UNT 179 IN LACR 2.0
END DESCRIPTION:
XS GIS Cut Line= 3
      2173287.75     13192496.86      2173587.72     13192596.85
      2173887.71     13192346.86
#Sta/Elev= 30
  4683.8  490.13  4732.1  488.36  4820.8   485.5    4863   483.1  4894.6  482.61
  4926.2  481.53  4936.8  479.69  4965.4  478.38  4968.1  477.88  4971.4  478.38
  4978.9  479.13  5003.3  479.59  5013.7  480.45  5042.3  481.23  5064.4  480.97
  5070.9   481.5  5078.1  481.29  5099.6  482.12  5117.5  482.03  5177.7  483.83
  5200.2  484.95  5227.1  486.01  5236.7  485.86  5262.3  487.41  5276.6  487.41
  5305.3  488.98  5348.2   490.6  5354.7  490.47  5362.5  491.32  5390.5  492.06
#Mann= 7 ,-1 , 0
  4683.8     .05       0  4732.1      .1       0  4965.4     .07       0
  4971.4      .1       0  5117.5     .05       0  5200.2      .1       0
  5236.7     .05       0
Bank Sta=4965.4,4971.4
XS Rating Curve= 0 ,0
Exp/Cntr=0.3,0.1

Type RM Length L Ch R = 1 ,1042    ,214,214,214
BEGIN DESCRIPTION:
Mapping XS bb949ab0
END DESCRIPTION:
XS GIS Cut Line= 4
      2173213.84      13192695.7      2173456.87     13192994.29
       2173741.6      13192980.4      2174033.01     13192536.34
#Sta/Elev= 30
    4484  488.66  4587.7     486  4654.5   483.6  4949.9  475.66    4970  474.26
    5040  475.36  5060.1  474.71  5100.1  475.46  5110.1  477.14  5119.6  474.12
  5124.7  476.61  5130.2  471.94  5137.2  470.92  5139.9  470.42  5143.2  470.92
  5149.6  472.69  5154.1  472.69  5160.2   476.6  5169.3  476.33  5175.3  477.21
  5183.5  477.21  5325.9  477.76  5356.1  480.24  5421.4   481.8  5445.7  483.32
  5479.7  484.28  5542.9  487.37  5592.2     489  5660.6   491.7  5685.2  493.14
#Mann= 7 ,-1 , 0
    4484     .05       0  4654.5      .1       0  5137.2     .07       0
  5143.2      .1       0  5183.5     .05       0  5445.7      .1       0
  5592.2     .05       0
#XS Ineff= 2 , 0
                         5110.34          477.13
Permanent Ineff=
       F       F
Bank Sta=4949.9,5100.1
XS Rating Curve= 0 ,0
Exp/Cntr=0.3,0.1

Type RM Length L Ch R = 1 ,828     ,292,292,292
BEGIN DESCRIPTION:
Mapping XS 5225b0bf
END DESCRIPTION:
XS GIS Cut Line= 4
      2173233.25     13192853.88      2173483.28     13193201.14
      2173809.67     13193159.48      2174017.83     13192701.51
#Sta/Elev= 30
  4416.4  484.42  4431.8  484.09  4479.7   482.6  4515.3  482.39  4550.9  480.51
  4678.8  478.49  4728.9  476.32  4868.9   473.7  4969.8  473.29  4995.8  472.64
  5040.3   473.3  5075.6  473.24  5090.7  474.08  5110.9  479.78  5131.1   472.5
  5150.4  470.78    5177  470.47    5181  469.74  5203.1   471.3  5242.1  473.54
  5250.4  474.77  5255.9   476.8  5264.1  478.28  5273.5   476.2  5286.1  477.29
    5308  477.76  5474.5  477.58  5505.8   480.9    5636  485.86  5676.4  488.17
#Mann= 5 ,-1 , 0
  4416.4     .05       0  4431.8      .1       0  4969.8     .07       0
  5040.3      .1       0  5203.1     .05       0
#XS Ineff= 2 , 0
                         5111.14          479.74
Permanent Ineff=
       F       F
Bank Sta=4969.8,5040.3
XS Rating Curve= 0 ,0
Exp/Cntr=0.3,0.1

Type RM Length L Ch R = 1 ,536     ,359,359,359
BEGIN DESCRIPTION:
Mapping XS cde4866b
END DESCRIPTION:
XS GIS Cut Line= 4
      2173213.81     13192897.05      2173547.15     13193431.79
       2173866.6     13193431.79      2174199.92     13192612.36
#Sta/Elev= 30
  4179.3  484.05    4233     482  4306.2  481.05  4342.8  478.95  4437.2  477.91
  4464.3  476.87  4485.5  477.15    4509  475.88  4726.2  472.47  4747.5   471.4
  4791.8  471.48    4910  469.32    4970  469.56    5020  469.47    5040  468.86
  5126.9   470.1  5147.8  469.72  5380.9  473.79  5404.1  475.09  5415.4  477.22
  5609.2  477.37  5648.2  478.29  5672.3  479.92  5677.6  481.74  5684.8  482.38
  5771.1   486.7  5846.7  489.12  5954.7  494.35    5989  495.26  6013.5  495.94
#Mann= 5 ,-1 , 0
  4179.3     .16       0    4970     .07       0    5020     .16       0
  5380.9     .05       0    5989      .1       0
#XS Ineff= 2 , 0
         4919.93  469.65 5127.06           470.1
Permanent Ineff=
       F       F
Bank Sta=4970,5020
XS Rating Curve= 0 ,0
Exp/Cntr=0.3,0.1

Type RM Length L Ch R = 1 ,177     ,0,0,0
BEGIN DESCRIPTION:
UNT 179 IN LACR 1.0
END DESCRIPTION:
XS GIS Cut Line= 4
      2173088.81     13193049.82      2173463.05     13193690.66
      2174037.72     13193779.01      2174477.44     13192821.26
#Sta/Elev= 30
  3929.4  483.09  4100.6   477.9    4366  472.21  4591.7  469.58  4643.9  467.45
  4811.9  465.77  4868.5  466.77  4888.7  465.37  4943.5  464.34  4966.6  461.13
  4969.4  460.63  4979.8  461.33  4989.9  462.38    5000  465.02  5030.4  465.59
  5201.6  466.07  5268.4  465.27  5526.7  468.63  5640.4   469.1  5652.7  470.03
  5882.5  474.57    5911  473.96    5957  477.01  5962.5  476.44  5992.5  478.03
  6008.5  477.79  6059.9  480.43  6128.9  481.57  6174.9  484.15  6306.8  487.77
#Mann= 3 , 0 , 0
  3929.4     .16       0  4966.6     .07       0  4979.8     .16       0
Bank Sta=4966.6,4979.8
XS Rating Curve= 0 ,0
Exp/Cntr=0.3,0.1

Chan Stop Cuts=-1
Use User Specified Reach Order=0
Composite Channel Slope=5