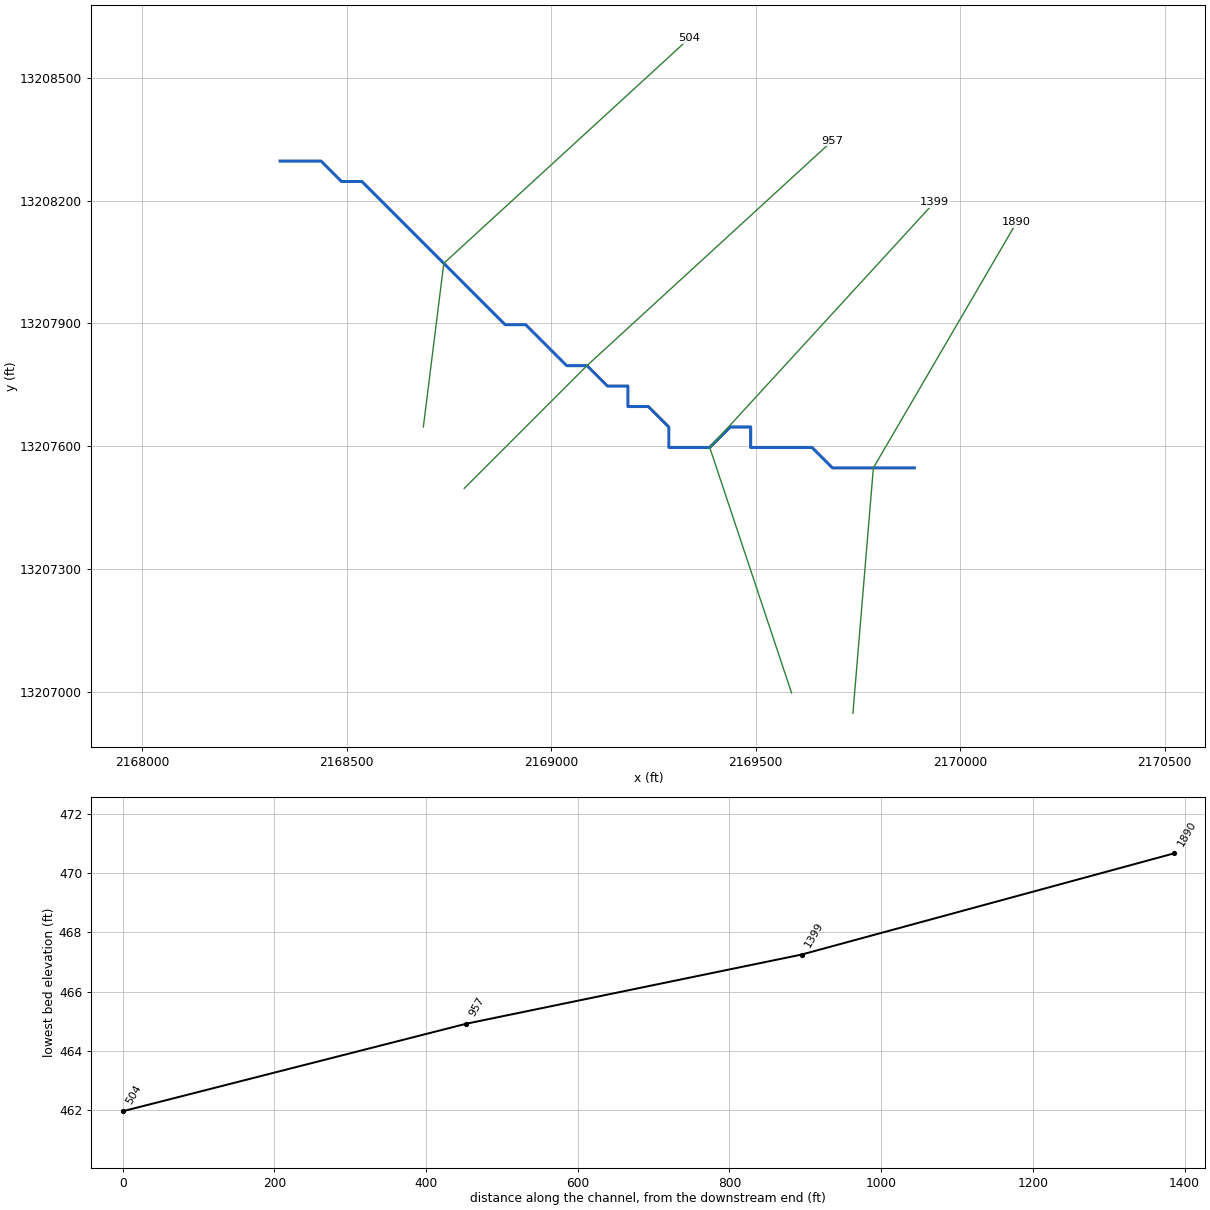
--- UNT 182 IN LACR.prj (project) ---

Proj Title=UNT 182 IN LACR Base Level Engineering
Current Plan=p01
Default Exp/Contr=0.3,0.1
English Units
Geom File=g01
Flow File=f01
Plan File=p01
Y Axis Title=Elevation
X Axis Title(PF)=Main Channel Distance
X Axis Title(XS)=Station
BEGIN DESCRIPTION:
UNT 182 IN LACR
END DESCRIPTION:
DSS Export Rating Curves= 0
DSS Export Rating Curve Sorted= 0
DSS Export Volume Flow Curves= 0
DXF OffsetX= 0
DXF OffsetY= 0
DXF ScaleX= 1
DXF ScaleY= 10

--- UNT 182 IN LACR.p01 (plan) ---

Plan Title=Multiple Run
Short Identifier=Multiple
Geom File=g01
Flow File=f01
Subcritical Flow
K Sum by GR= 0
Std Step Tol= 0.01
Critical Tol= 0.01
Num of Std Step Trials= 20
Max Error Tol= 0.3
Flow Tol Ratio= 0.001
Split Flow NTrial= 30
Split Flow Tol= 0.02
Split Flow Ratio= 0.02
Log Output Level= 0
Friction Slope Method= 1
Unsteady Friction Slope Method= 2
Unsteady Bridges Friction Slope Method= 1
Parabolic Critical Depth
Global Vel Dist=  1 , 1 , 1
Global Log Level= 0
CheckData=True
Encroach Param= -1, 0, 0, 0
BEGIN DESCRIPTION:
Multiple Run
END DESCRIPTION:

--- UNT 182 IN LACR.f01 (steady flow) ---

Flow Title=Multiple
Program Version=4.10
Number of Profiles= 7
Profile Names=10-year,25-year,50-year,1pct_min,100-year,1pct_plu,500-year
River Rch & RM=UNT 182 IN LACR,Reach-1         ,1890
     121     165     200     179     243     328     363
Boundary for River Rch & Prof#=UNT 182 IN LACR,Reach-1         , 1
Up Type= 0
Dn Type= 3
Dn Slope=0.007
Boundary for River Rch & Prof#=UNT 182 IN LACR,Reach-1         , 2
Up Type= 0
Dn Type= 3
Dn Slope=0.007
Boundary for River Rch & Prof#=UNT 182 IN LACR,Reach-1         , 3
Up Type= 0
Dn Type= 3
Dn Slope=0.007
Boundary for River Rch & Prof#=UNT 182 IN LACR,Reach-1         , 4
Up Type= 0
Dn Type= 3
Dn Slope=0.007
Boundary for River Rch & Prof#=UNT 182 IN LACR,Reach-1         , 5
Up Type= 0
Dn Type= 3
Dn Slope=0.007
Boundary for River Rch & Prof#=UNT 182 IN LACR,Reach-1         , 6
Up Type= 0
Dn Type= 3
Dn Slope=0.007
Boundary for River Rch & Prof#=UNT 182 IN LACR,Reach-1         , 7
Up Type= 0
Dn Type= 3
Dn Slope=0.007
DSS Import GetInterval= 0
DSS Import GetPeak= 0
DSS Import FillOption= 0

--- UNT 182 IN LACR.g01 (geometry) ---

Geom Title=Existing Conditions
Program Version=4.10

River Reach=UNT 182 IN LACR ,Reach-1
Reach XY= 27
      2169887.72     13207546.85      2169687.72     13207546.85
      2169637.72     13207596.85      2169487.72     13207596.85
      2169487.72     13207646.85      2169437.72     13207646.85
      2169387.72     13207596.85      2169287.72     13207596.85
      2169287.72     13207646.85      2169237.72     13207696.85
      2169187.72     13207696.85      2169187.72     13207746.86
      2169137.72     13207746.86      2169087.72     13207796.85
      2169037.72     13207796.85      2168987.72     13207846.85
      2168937.72     13207896.86      2168887.72     13207896.86
      2168837.72     13207946.85      2168787.72     13207996.85
      2168737.72     13208046.86      2168687.72     13208096.85
      2168587.72     13208196.85      2168537.72     13208246.86
      2168487.72     13208246.86      2168437.72     13208296.85
      2168337.72     13208296.85

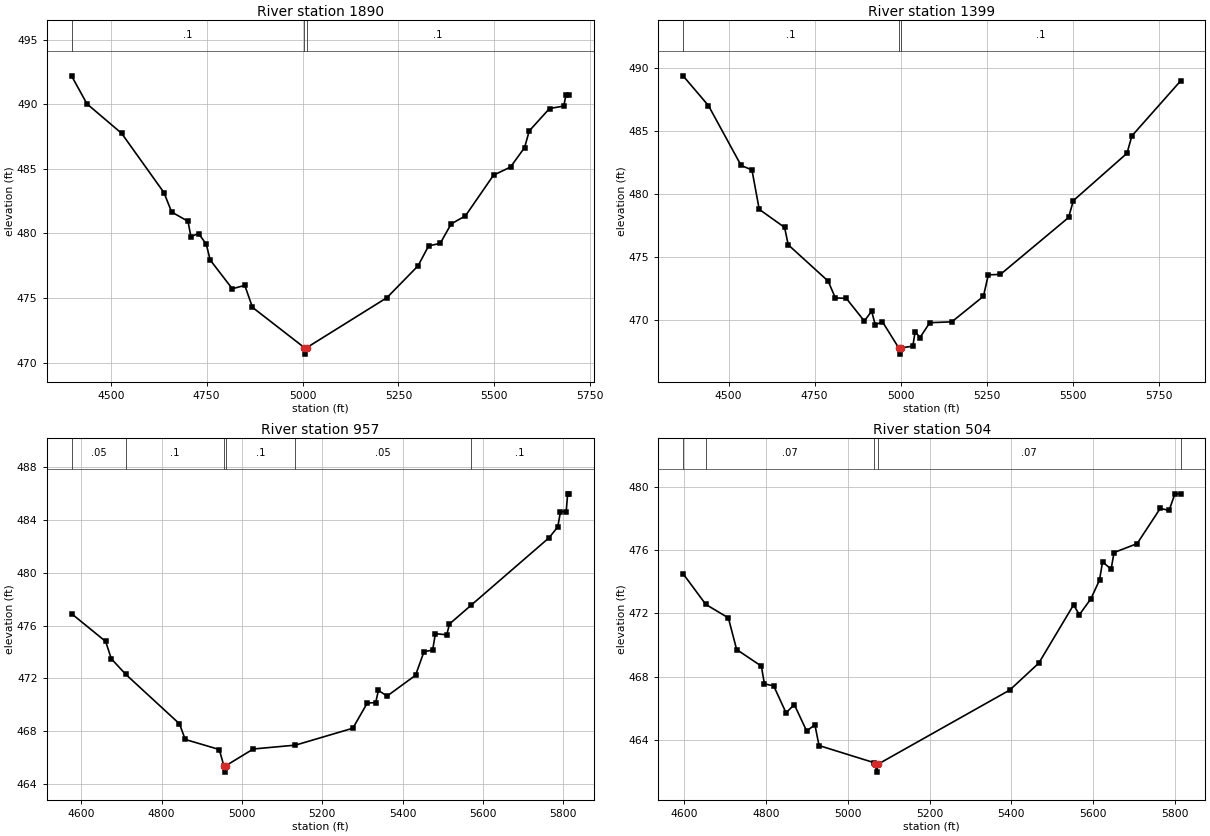
Type RM Length L Ch R = 1 ,1890    ,491,491,491
BEGIN DESCRIPTION:
UNT 182 IN LACR 4.0
END DESCRIPTION:
XS GIS Cut Line= 3
      2169737.72     13206946.83      2169787.72     13207546.85
      2170137.71     13208146.84
#Sta/Elev= 30
  4397.9   492.2  4438.1  490.03  4528.4  487.75  4638.8  483.16  4658.8  481.66
  4701.5  480.94    4709  479.76  4729.1  479.99  4749.1  479.17  4759.2  477.95
  4816.9  475.72  4849.5  475.98  4869.5  474.28  5004.9  471.16  5007.6  470.66
  5010.9  471.16    5220  475.03    5301  477.49  5328.7  479.04  5358.9  479.23
  5387.4  480.74  5424.6  481.36  5497.8  484.51  5542.1  485.14  5578.9  486.65
  5590.8  487.93  5643.8  489.67    5681  489.86  5686.8  490.75  5694.6  490.75
#Mann= 3 ,-1 , 0
  4397.9      .1       0  5004.9     .07       0  5010.9      .1       0
Bank Sta=5004.9,5010.9
XS Rating Curve= 0 ,0
Exp/Cntr=0.3,0.1

Type RM Length L Ch R = 1 ,1399    ,442,442,442
BEGIN DESCRIPTION:
UNT 182 IN LACR 3.0
END DESCRIPTION:
XS GIS Cut Line= 3
      2169587.73     13206996.81      2169387.72     13207596.85
      2169937.69     13208196.82
#Sta/Elev= 30
  4367.5  489.39  4441.3  487.02  4536.2  482.26  4567.8   481.9  4588.9  478.77
  4662.7  477.33  4673.2  475.95  4789.2  473.06  4810.3  471.72  4841.9  471.69
  4894.6  469.88  4915.7  470.67  4926.2  469.59  4947.3  469.82  4994.4  467.75
  4997.1  467.25  5000.4  467.75  5035.5  467.88  5042.2  469.03  5056.4  468.57
  5084.8  469.75  5148.9  469.82  5240.8  471.85    5255  473.56  5290.1  473.59
  5488.4  478.12  5502.2  479.46  5658.2  483.23  5672.4  484.61  5813.9  488.98
#Mann= 3 ,-1 , 0
  4367.5      .1       0  4994.4     .07       0  5000.4      .1       0
Bank Sta=4994.4,5000.4
XS Rating Curve= 0 ,0
Exp/Cntr=0.3,0.1

Type RM Length L Ch R = 1 ,957     ,453,453,453
BEGIN DESCRIPTION:
UNT 182 IN LACR 2.0
END DESCRIPTION:
XS GIS Cut Line= 3
       2168787.7     13207496.83      2169087.72     13207796.85
      2169687.69     13208346.83
#Sta/Elev= 30
  4575.7   476.9  4660.6   474.8  4674.7  473.49  4710.4  472.32  4844.4  468.57
  4858.6  467.39  4943.4  466.63  4954.6  465.42  4957.3  464.92  4960.6  465.42
  5028.1  466.67  5132.9  466.96  5275.9  468.24  5311.7  470.14  5332.7  470.18
  5339.5   471.1    5361  470.67  5431.9  472.24  5452.9  474.02  5474.5  474.15
  5481.3  475.39  5509.6   475.3  5516.4  476.12  5569.9  477.53  5764.3  482.64
  5785.9  483.46  5792.7  484.61  5806.9  484.61  5810.5  485.96  5813.9  485.96
#Mann= 6 ,-1 , 0
  4575.7     .05       0  4710.4      .1       0  4954.6     .07       0
  4960.6      .1       0  5132.9     .05       0  5569.9      .1       0
Bank Sta=4954.6,4960.6
XS Rating Curve= 0 ,0
Exp/Cntr=0.3,0.1

Type RM Length L Ch R = 1 ,504     ,0,0,0
BEGIN DESCRIPTION:
UNT 182 IN LACR 1.0
END DESCRIPTION:
XS GIS Cut Line= 3
      2168687.72     13207646.87      2168737.72     13208046.86
      2169337.69     13208596.83
#Sta/Elev= 30
  4596.9  474.51  4652.5  472.57  4707.7  471.72  4727.9  469.72  4788.4  468.67
  4795.9  467.55  4818.6  467.42  4848.8  465.72    4869  466.24  4899.2  464.57
  4919.4  464.96  4929.5  463.65  5063.8  462.57  5067.6  462.47  5070.4  461.97
  5073.6  462.47  5396.2  467.16  5467.1  468.86  5552.2  472.54  5566.4  471.92
  5594.7  472.93  5615.7  474.11  5623.1  475.26  5644.1   474.8  5651.2  475.85
  5707.6  476.41  5764.3  478.64  5785.9  478.51  5800.1  479.56  5813.9  479.56
#Mann= 5 ,-1 , 0
  4596.9     .05       0  4652.5     .07       0  5063.8    .035       0
  5073.6     .07       0  5813.9     .08       0
Bank Sta=5067.6,5073.6
XS Rating Curve= 0 ,0
Exp/Cntr=0.3,0.1

Chan Stop Cuts=-1
Use User Specified Reach Order=0
Composite Channel Slope=5