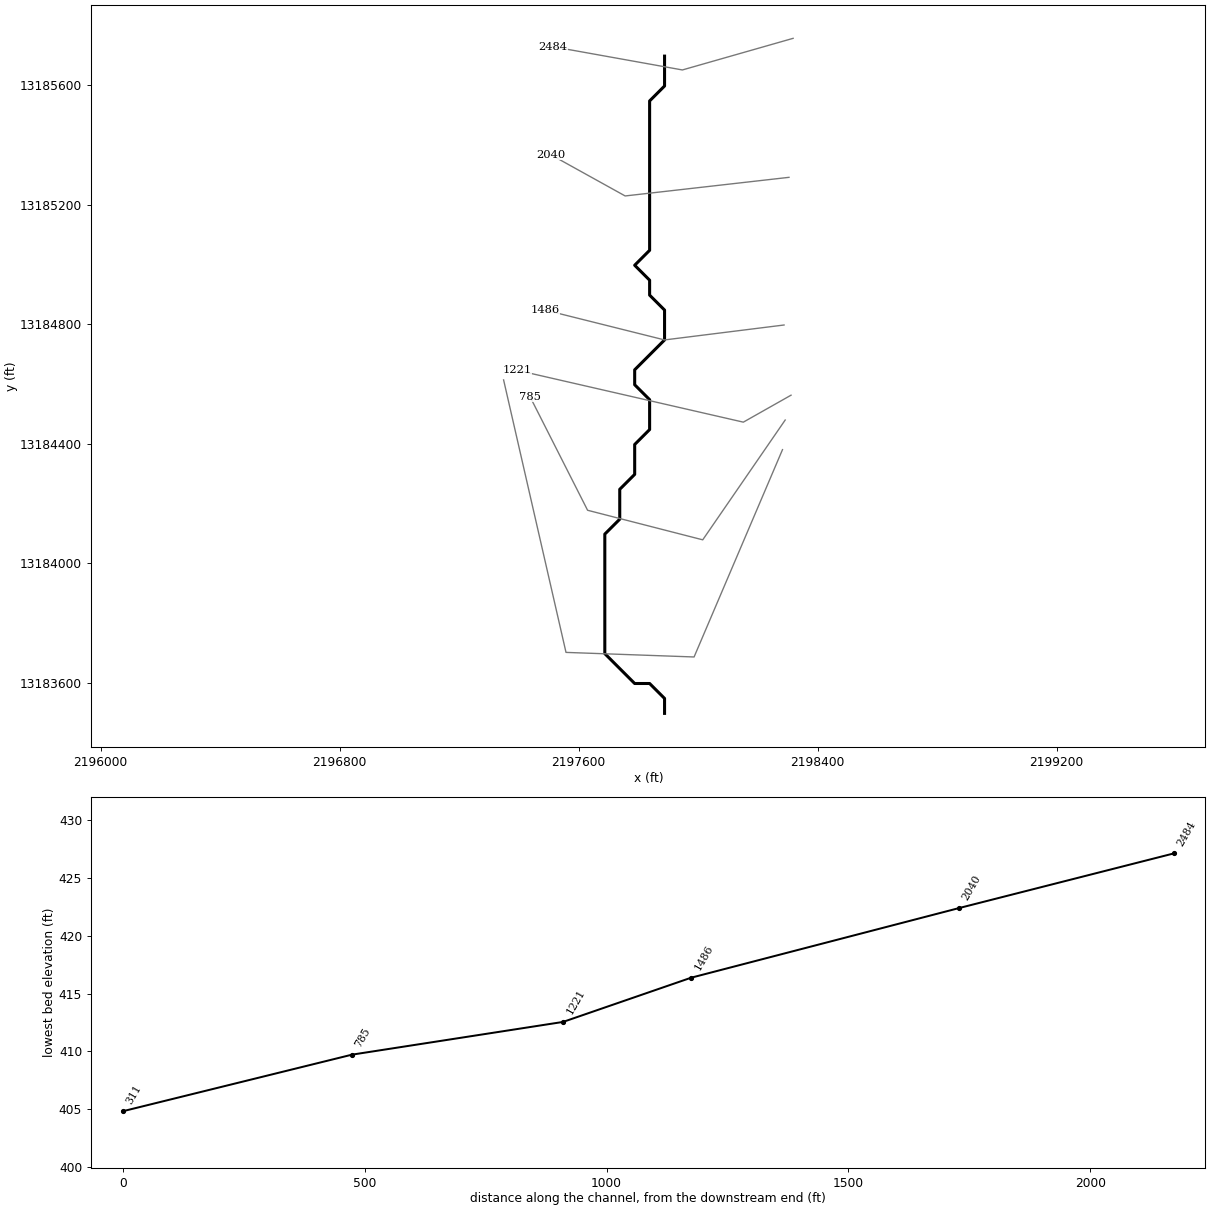
--- UNT 187 IN LACR.prj (project) ---

Proj Title=UNT 187 IN LACR Base Level Engineering
Current Plan=p01
Default Exp/Contr=0.3,0.1
English Units
Geom File=g01
Flow File=f01
Plan File=p01
BEGIN DESCRIPTION:
UNT 187 IN LACR
END DESCRIPTION:

--- UNT 187 IN LACR.p01 (plan) ---

Plan Title=Multiple Run
Short Identifier=Multiple
Geom File=g01
Flow File=f01
Subcritical Flow
K Sum by GR= 0
Std Step Tol= 0.01
Critical Tol= 0.01
Num of Std Step Trials= 20
Max Error Tol= 0.3
Flow Tol Ratio= 0.001
Split Flow NTrial= 30
Split Flow Tol= 0.02
Split Flow Ratio= 0.02
Log Output Level= 0
Friction Slope Method= 1
Unsteady Friction Slope Method= 2
Unsteady Bridges Friction Slope Method= 1
Parabolic Critical Depth
Global Vel Dist=  1 , 1 , 1
Global Log Level= 0
CheckData=True
Encroach Param= -1, 0, 0, 0
BEGIN DESCRIPTION:
Multiple Run
END DESCRIPTION:

--- UNT 187 IN LACR.f01 (steady flow) ---

Flow Title=Multiple
Number of Profiles=7
Profile Names=10-year,25-year,50-year,1pct_min,100-year,1pct_plu,500-year
River Rch & RM= UNT 187 IN LACR,Reach-1,2484
     146     199     243     219     296     401     445
Boundary for River Rch & Prof#=UNT 187 IN LACR,Reach-1,1
Up Type=0
Dn Type=3
Dn Slope=0.005
Boundary for River Rch & Prof#=UNT 187 IN LACR,Reach-1,2
Up Type=0
Dn Type=3
Dn Slope=0.005
Boundary for River Rch & Prof#=UNT 187 IN LACR,Reach-1,3
Up Type=0
Dn Type=3
Dn Slope=0.005
Boundary for River Rch & Prof#=UNT 187 IN LACR,Reach-1,4
Up Type=0
Dn Type=3
Dn Slope=0.005
Boundary for River Rch & Prof#=UNT 187 IN LACR,Reach-1,5
Up Type=0
Dn Type=3
Dn Slope=0.005
Boundary for River Rch & Prof#=UNT 187 IN LACR,Reach-1,6
Up Type=0
Dn Type=3
Dn Slope=0.005
Boundary for River Rch & Prof#=UNT 187 IN LACR,Reach-1,7
Up Type=0
Dn Type=3
Dn Slope=0.005

--- UNT 187 IN LACR.g01 (geometry) ---

Geom Title=Existing Conditions

River Reach=UNT 187 IN LACR,Reach-1
Reach XY= 23
      2197887.72     13185696.85      2197887.72     13185596.86
      2197837.72     13185546.85      2197837.72     13185046.85
      2197787.72     13184996.85      2197837.72     13184946.86
      2197837.72     13184896.85      2197887.72     13184846.85
      2197887.72     13184746.85      2197787.72     13184646.85
      2197787.72     13184596.86      2197837.72     13184546.85
      2197837.72     13184446.86      2197787.72     13184396.85
      2197787.72     13184296.86      2197737.72     13184246.85
      2197737.72     13184146.85      2197687.72     13184096.86
      2197687.72     13183696.85      2197787.72     13183596.85
      2197837.72     13183596.85      2197887.72     13183546.85
      2197887.72     13183496.85

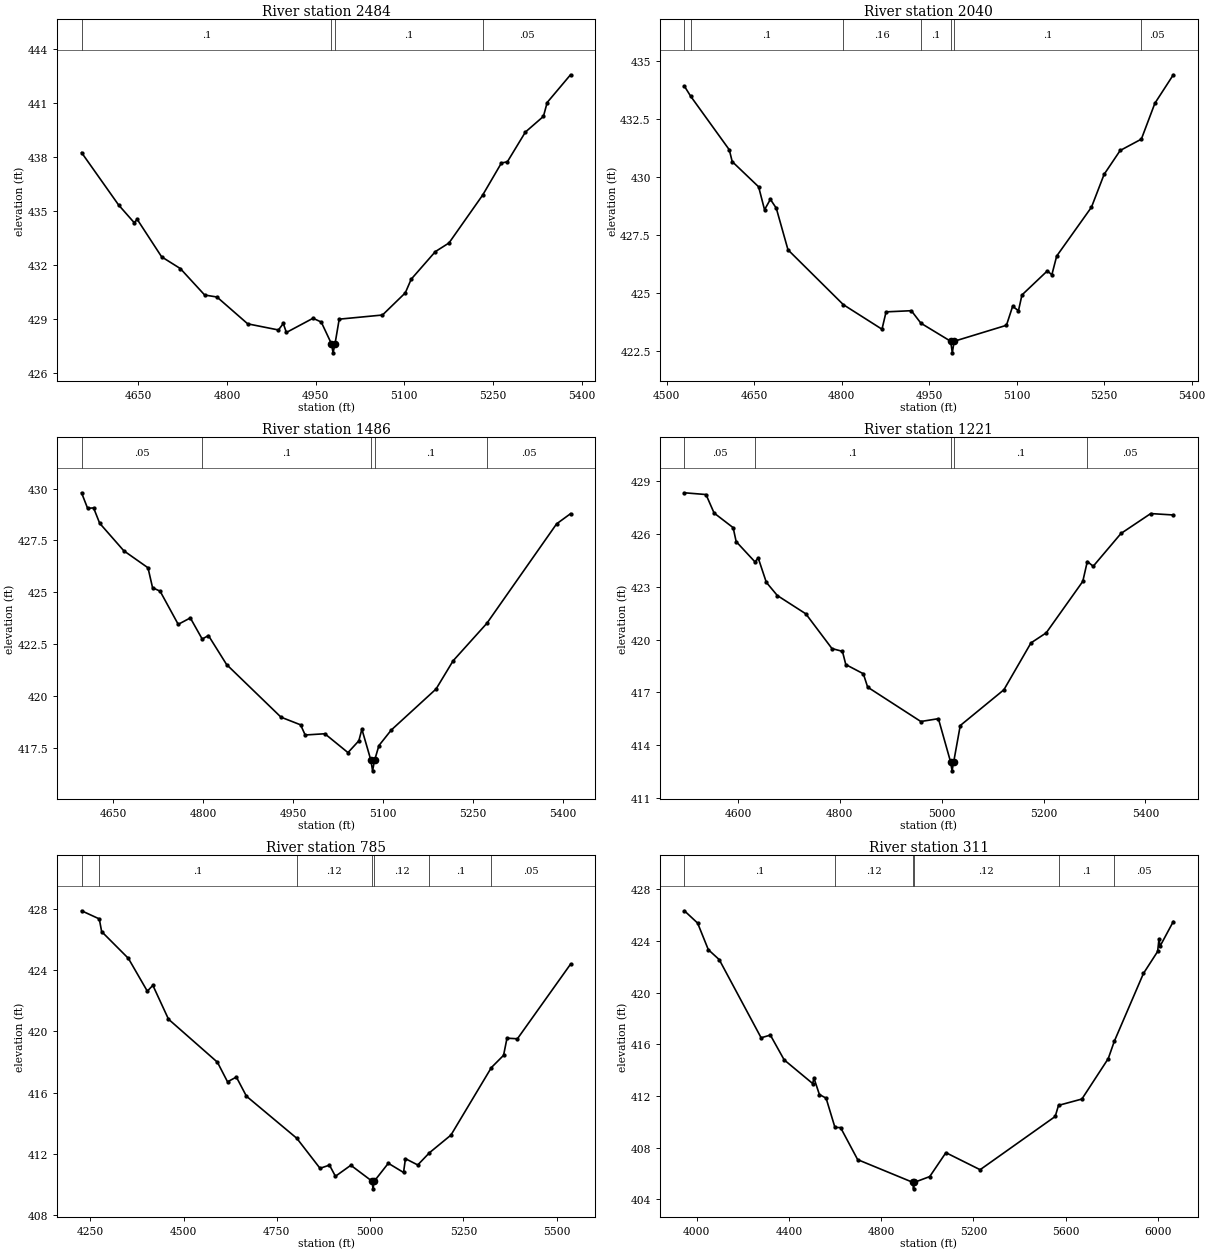
Type RM Length L Ch R = 1,2484,444,444,444
BEGIN DESCRIPTION:
UNT 187 IN LACR 4.0
END DESCRIPTION:
XS GIS Cut Line= 3
      2198318.05     13185756.38      2197947.38     13185650.55
      2197512.62     13185728.60
#Sta/Elev= 30
  4553.9  438.26  4616.6  435.35  4642.9  434.37  4648.1  434.55  4689.4  432.47
  4721.0  431.82  4762.2  430.35  4783.0  430.24  4835.0  428.75  4887.0  428.41
  4895.2  428.77  4900.4  428.27  4945.5  429.06  4959.4  428.85  4976.7  427.64
  4979.4  427.14  4982.7  427.64  4989.8  429.01  5063.0  429.24  5101.6  430.47
  5111.6  431.23  5152.4  432.76  5175.5  433.24  5232.5  435.90  5264.2  437.68
  5274.3  437.75  5304.8  439.40  5335.3  440.27  5341.6  441.04  5381.1  442.58
#Mann=4,-1,0
  4553.9     0.1       0  4976.7    0.07       0  4982.7     0.1       0
  5232.5    0.05       0
Bank Sta=4976.7,4982.7
Exp/Cntr=0.3,0.1

Type RM Length L Ch R = 1,2040,554,554,554
BEGIN DESCRIPTION:
UNT 187 IN LACR 3.0
END DESCRIPTION:
XS GIS Cut Line= 3
      2198304.22     13185291.12      2197755.78     13185228.80
      2197505.62     13185367.49
#Sta/Elev= 30
  4530.5  433.93  4541.4  433.49  4607.5  431.18  4612.5  430.67  4657.8  429.58
  4667.9  428.59  4677.9  429.04  4688.0  428.66  4708.1  426.86  4803.0  424.49
  4869.2  423.43  4876.2  424.18  4919.5  424.23  4935.9  423.69  4986.9  422.91
  4989.7  422.41  4992.9  422.91  5082.5  423.60  5093.1  424.42  5103.1  424.23
  5109.1  424.91  5152.6  425.95  5160.3  425.78  5168.6  426.59  5228.2  428.70
  5249.9  430.12  5277.4  431.15  5313.7  431.64  5336.9  433.19  5368.5  434.42
#Mann=7,-1,0
  4530.5    0.05       0  4541.4     0.1       0  4803.0    0.16       0
  4935.9     0.1       0  4986.9    0.07       0  4992.9     0.1       0
  5313.7    0.05       0
Bank Sta=4986.9,4992.9
Exp/Cntr=0.3,0.1

Type RM Length L Ch R = 1,1486,265,265,265
BEGIN DESCRIPTION:
UNT 187 IN LACR 2.0
END DESCRIPTION:
XS GIS Cut Line= 3
      2198287.71     13184796.85      2197887.72     13184746.85
      2197487.73     13184846.85
#Sta/Elev= 30
  4596.9  429.80  4607.0  429.05  4617.0  429.07  4627.1  428.33  4667.4  427.00
  4707.7  426.18  4715.3  425.22  4727.9  425.05  4758.1  423.45  4778.3  423.76
  4798.1  422.74  4808.5  422.91  4838.8  421.51  4929.5  418.97  4962.2  418.60
  4969.8  418.11  5002.6  418.17  5041.2  417.26  5059.3  417.83  5064.4  418.39
  5079.5  416.88  5082.2  416.38  5085.5  416.88  5092.8  417.60  5113.4  418.35
  5188.1  420.33  5216.5  421.69  5272.8  423.50  5389.1  428.30  5412.3  428.79
#Mann=5,-1,0
  4596.9    0.05       0  4798.1     0.1       0  5079.5    0.07       0
  5085.5     0.1       0  5272.8    0.05       0
Bank Sta=5079.5,5085.5
Exp/Cntr=0.3,0.1

Type RM Length L Ch R = 1,1221,436,436,436
BEGIN DESCRIPTION:
Mapping XS c6140dc1
END DESCRIPTION:
XS GIS Cut Line= 3
      2198311.13     13184561.94      2198151.42     13184471.67
      2197394.43     13184645.29
#Sta/Elev= 30
  4494.7  428.33  4537.2  428.23  4553.1  427.18  4590.5  426.35  4596.4  425.56
  4633.3  424.41  4639.7  424.63  4655.6  423.25  4677.2  422.50  4733.2  421.46
  4784.5  419.49  4805.1  419.33  4811.7  418.58  4846.1  418.06  4854.6  417.30
  4959.0  415.35  4993.5  415.51  5017.5  413.05  5020.3  412.55  5023.5  413.05
  5036.4  415.12  5122.1  417.15  5175.3  419.81  5205.2  420.38  5277.0  423.30
  5285.9  424.43  5297.5  424.16  5352.0  426.02  5410.4  427.15  5454.8  427.07
#Mann=5,-1,0
  4494.7    0.05       0  4633.3     0.1       0  5017.5    0.07       0
  5023.5     0.1       0  5285.9    0.05       0
Bank Sta=5017.5,5023.5
Exp/Cntr=0.3,0.1

Type RM Length L Ch R = 1,785,474,474,474
BEGIN DESCRIPTION:
Mapping XS 0ad13a5d
END DESCRIPTION:
XS GIS Cut Line= 4
      2198291.51     13184478.77      2198015.49     13184077.76
      2197630.08     13184176.72      2197437.36     13184556.93
#Sta/Elev= 30
  4226.4  427.88  4273.9  427.35  4280.3  426.52  4352.0  424.77  4402.7  422.63
  4417.6  423.01  4459.5  420.80  4590.7  417.99  4617.8  416.71  4641.5  417.02
  4668.5  415.77  4803.6  413.02  4865.8  411.06  4891.1  411.27  4907.1  410.54
  4948.4  411.26  5005.2  410.22  5007.9  409.72  5011.2  410.22  5048.9  411.39
  5089.7  410.79  5094.8  411.69  5127.8  411.28  5159.3  412.08  5216.8  413.23
  5325.2  417.64  5357.9  418.44  5367.1  419.56  5395.0  419.52  5537.4  424.39
#Mann=7,-1,0
  4226.4    0.05       0  4273.9     0.1       0  4803.6    0.12       0
  5005.2    0.07       0  5011.2    0.12       0  5159.3     0.1       0
  5325.2    0.05       0
Bank Sta=5005.2,5011.2
Exp/Cntr=0.3,0.1

Type RM Length L Ch R = 1,311,0,0,0
BEGIN DESCRIPTION:
UNT 187 IN LACR 1.0
END DESCRIPTION:
XS GIS Cut Line= 4
      2198282.49     13184379.64      2197986.52     13183685.64
      2197557.84     13183700.95      2197348.91     13184613.11
#Sta/Elev= 30
  3947.1  426.34  4004.5  425.39  4050.9  423.33  4098.2  422.56  4279.8  416.51
  4319.8  416.72  4379.7  414.80  4503.2  412.97  4508.7  413.39  4532.3  412.12
  4561.3  411.84  4599.8  409.57  4624.2  409.56  4698.2  407.08  4937.5  405.32
  4940.3  404.82  4943.5  405.32  5010.6  405.77  5080.6  407.62  5228.9  406.30
  5554.3  410.42  5568.7  411.28  5670.0  411.77  5784.3  414.90  5810.5  416.24
  5936.8  421.49  5998.3  423.19  6004.0  424.14  6009.1  423.61  6066.3  425.51
#Mann=6,-1,0
  3947.1     0.1       0  4599.8    0.12       0  4937.5    0.07       0
  4943.5    0.12       0  5568.7     0.1       0  5810.5    0.05       0
Bank Sta=4937.5,4943.5
Exp/Cntr=0.3,0.1

Chan Stop Cuts=-1