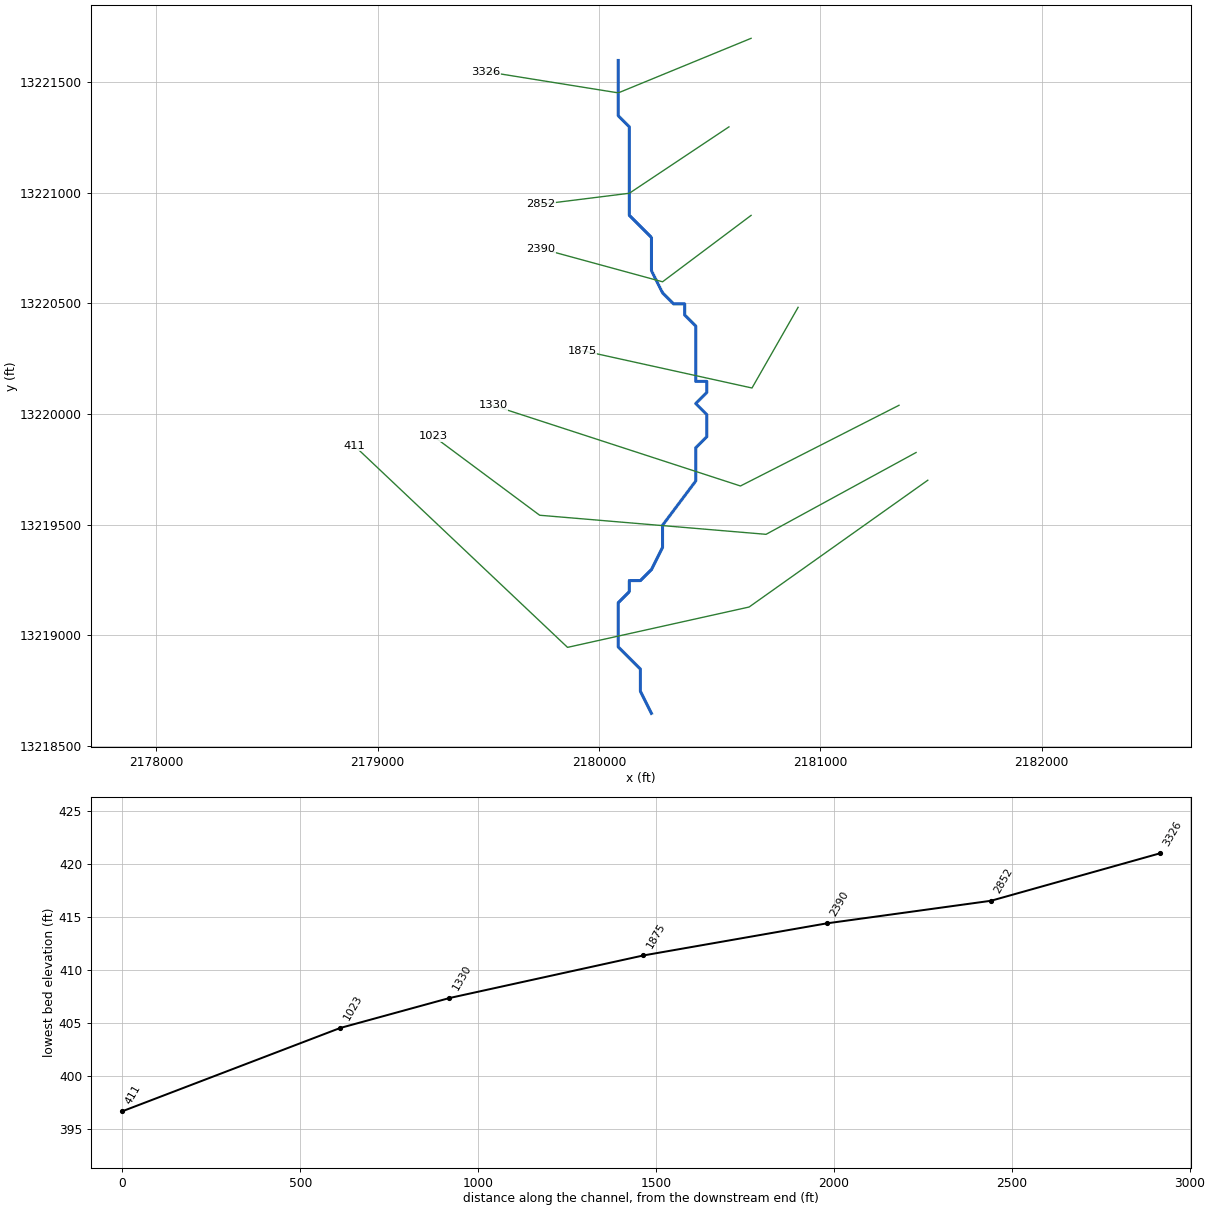
--- UNT 189 IN LACR.prj (project) ---

Proj Title=UNT 189 IN LACR Base Level Engineering
Current Plan=p01
Default Exp/Contr=0.3,0.1
English Units
Geom File=g01
Flow File=f01
Plan File=p01
Y Axis Title=Elevation
X Axis Title(PF)=Main Channel Distance
X Axis Title(XS)=Station
BEGIN DESCRIPTION:
UNT 189 IN LACR
END DESCRIPTION:
DSS Export Rating Curves= 0
DSS Export Rating Curve Sorted= 0
DSS Export Volume Flow Curves= 0
DXF OffsetX= 0
DXF OffsetY= 0
DXF ScaleX= 1
DXF ScaleY= 10

--- UNT 189 IN LACR.p01 (plan) ---

Plan Title=Multiple Run
Short Identifier=Multiple
Geom File=g01
Flow File=f01
Subcritical Flow
K Sum by GR= 0
Std Step Tol= 0.01
Critical Tol= 0.01
Num of Std Step Trials= 20
Max Error Tol= 0.3
Flow Tol Ratio= 0.001
Split Flow NTrial= 30
Split Flow Tol= 0.02
Split Flow Ratio= 0.02
Log Output Level= 0
Friction Slope Method= 1
Unsteady Friction Slope Method= 2
Unsteady Bridges Friction Slope Method= 1
Parabolic Critical Depth
Global Vel Dist=  1 , 1 , 1
Global Log Level= 0
CheckData=True
Encroach Param= -1, 0, 0, 0
BEGIN DESCRIPTION:
Multiple Run
END DESCRIPTION:

--- UNT 189 IN LACR.f01 (steady flow) ---

Flow Title=Multiple
Number of Profiles=7
Profile Names=10-year,25-year,50-year,1pct_min,100-year,1pct_plu,500-year
River Rch & RM= UNT 189 IN LACR,Reach-1,3326
      73      95     112      98     133     180     189
Boundary for River Rch & Prof#=UNT 189 IN LACR,Reach-1,1
Up Type=0
Dn Type=3
Dn Slope=0.005
Boundary for River Rch & Prof#=UNT 189 IN LACR,Reach-1,2
Up Type=0
Dn Type=3
Dn Slope=0.005
Boundary for River Rch & Prof#=UNT 189 IN LACR,Reach-1,3
Up Type=0
Dn Type=3
Dn Slope=0.005
Boundary for River Rch & Prof#=UNT 189 IN LACR,Reach-1,4
Up Type=0
Dn Type=3
Dn Slope=0.005
Boundary for River Rch & Prof#=UNT 189 IN LACR,Reach-1,5
Up Type=0
Dn Type=3
Dn Slope=0.005
Boundary for River Rch & Prof#=UNT 189 IN LACR,Reach-1,6
Up Type=0
Dn Type=3
Dn Slope=0.005
Boundary for River Rch & Prof#=UNT 189 IN LACR,Reach-1,7
Up Type=0
Dn Type=3
Dn Slope=0.005

--- UNT 189 IN LACR.g01 (geometry) ---

Geom Title=Existing Conditions
Program Version=4.10

River Reach=UNT 189 IN LACR ,Reach-1
Reach XY= 30
      2180087.72     13221596.85      2180087.72     13221346.86
      2180137.72     13221296.85      2180137.72     13220896.85
      2180237.72     13220796.85      2180237.72     13220646.85
      2180287.72     13220546.86      2180337.72     13220496.85
      2180387.72     13220496.85      2180387.72     13220446.85
      2180437.72     13220396.85      2180437.72     13220146.85
      2180487.72     13220146.85      2180487.72     13220096.85
      2180437.72     13220046.86      2180487.72     13219996.85
      2180487.72     13219896.85      2180437.72     13219846.85
      2180437.72     13219696.86      2180287.72     13219496.85
      2180287.72     13219396.86      2180237.72     13219296.85
      2180187.72     13219246.85      2180137.72     13219246.85
      2180137.72     13219196.85      2180087.72     13219146.85
      2180087.72     13218946.85      2180187.72     13218846.85
      2180187.72     13218746.86      2180237.72     13218646.85

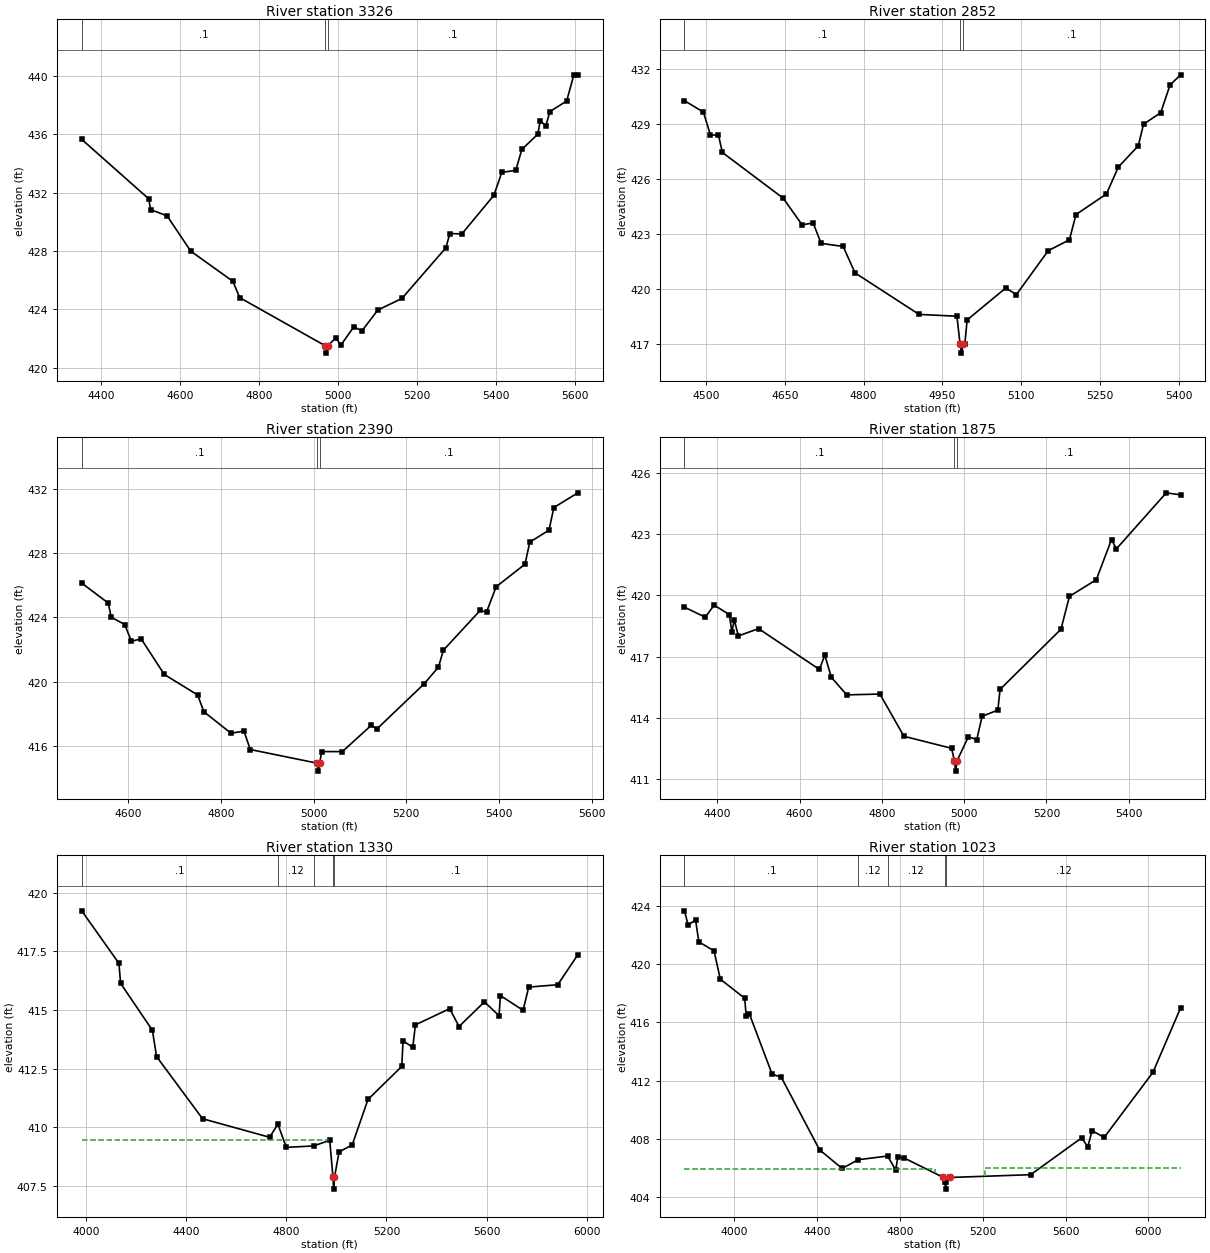
Type RM Length L Ch R = 1 ,3326    ,474,474,474
BEGIN DESCRIPTION:
UNT 189 IN LACR 6.0
END DESCRIPTION:
XS GIS Cut Line= 3
      2180687.68     13221696.84      2180087.72      13221450.4
      2179487.72     13221546.85
#Sta/Elev= 30
  4351.4  435.66  4520.7  431.59  4526.1  430.84  4567.6  430.41  4627.4  427.99
  4734.1  425.92  4751.4   424.8  4968.4  421.49  4971.2  420.99  4974.4  421.49
  4995.4  422.05  5007.1  421.52  5040.5   422.8  5060.8  422.51  5101.3  423.95
  5162.1  424.74  5273.5  428.22  5283.6   429.2    5314  429.17    5395  431.82
  5415.3   433.4  5450.4  433.53  5465.9  434.97  5506.4  436.02  5512.3  436.94
  5526.7  436.58  5536.8  437.57  5579.3  438.29  5597.6  440.09  5607.7  440.09
#Mann= 3 ,-1 , 0
  4351.4      .1       0  4968.4     .07       0  4974.4      .1       0
Bank Sta=4968.4,4974.4
XS Rating Curve= 0 ,0
Exp/Cntr=0.3,0.1

Type RM Length L Ch R = 1 ,2852    ,462,462,462
BEGIN DESCRIPTION:
UNT 189 IN LACR 5.0
END DESCRIPTION:
XS GIS Cut Line= 3
      2180587.69     13221296.84      2180137.72     13220996.85
      2179737.73     13220946.86
#Sta/Elev= 30
  4459.2  430.28  4495.2  429.66  4508.7  428.41  4523.8  428.41  4531.3  427.46
    4647  424.97    4683  423.52    4704  423.62  4719.1  422.51  4761.1  422.34
  4783.7   420.9  4905.4  418.64  4977.5  418.54  4983.5  417.03  4986.2  416.53
  4989.5  417.03  4992.5  417.03    4997  418.34  5070.5  420.08  5090.7  419.72
  5151.2  422.11  5191.5   422.7  5204.1  424.08    5262   425.2  5284.7  426.67
  5322.5  427.82  5332.6     429  5365.3  429.63    5383  431.14  5403.1  431.69
#Mann= 3 ,-1 , 0
  4459.2      .1       0  4983.5     .07       0  4989.5      .1       0
Bank Sta=4983.5,4989.5
XS Rating Curve= 0 ,0
Exp/Cntr=0.3,0.1

Type RM Length L Ch R = 1 ,2390    ,515,515,515
BEGIN DESCRIPTION:
UNT 189 IN LACR 4.0
END DESCRIPTION:
XS GIS Cut Line= 3
      2180687.72     13220896.85      2180287.72     13220596.85
      2179737.71     13220746.86
#Sta/Elev= 30
    4500  426.15  4557.3   424.9  4563.5  424.02  4592.7  423.56  4607.3  422.51
  4628.1  422.67  4678.1  420.44    4750  419.16  4763.5  418.11  4821.9  416.77
    4850   416.9  4863.5  415.75  5007.4   414.9  5010.1   414.4  5013.4   414.9
  5017.3  415.62  5062.2  415.62  5124.4  417.26  5136.5  417.03  5238.4  419.85
  5269.5   420.9  5279.9  421.95  5359.3  424.44  5373.1  424.34  5393.9  425.92
  5456.1  427.33  5466.4  428.71  5507.9  429.46  5518.3  430.87  5570.1  431.79
#Mann= 3 ,-1 , 0
    4500      .1       0  5007.4     .07       0  5013.4      .1       0
Bank Sta=5007.4,5013.4
XS Rating Curve= 0 ,0
Exp/Cntr=0.3,0.1

Type RM Length L Ch R = 1 ,1875    ,545,545,545
BEGIN DESCRIPTION:
UNT 189 IN LACR 3.0
END DESCRIPTION:
XS GIS Cut Line= 3
      2180900.17     13220481.52      2180691.85     13220116.96
      2179923.65     13220286.23
#Sta/Elev= 30
  4319.9  419.42  4370.4  418.93    4392  419.52  4428.9  419.06  4435.2  418.21
  4440.9   418.8    4451  418.01    4500  418.37  4647.8  416.37  4661.2  417.06
  4677.1  415.98  4714.5  415.12  4795.2  415.16  4853.5  413.09  4969.3   412.5
  4976.5  411.88  4979.3  411.38  4982.5  411.88  5010.2  413.06  5030.7  412.93
  5043.7  414.07  5081.9  414.37  5087.4  415.39  5235.5  418.34    5256  419.95
  5321.4  420.77  5358.4  422.74  5370.2  422.28  5491.5  425.03  5526.4  424.93
#Mann= 3 ,-1 , 0
  4319.9      .1       0  4976.5     .07       0  4982.5      .1       0
Bank Sta=4976.5,4982.5
XS Rating Curve= 0 ,0
Exp/Cntr=0.3,0.1

Type RM Length L Ch R = 1 ,1330    ,307,307,307
BEGIN DESCRIPTION:
UNT 189 IN LACR 2.0
END DESCRIPTION:
XS GIS Cut Line= 3
      2181355.92     13220038.84      2180639.76     13219674.26
      2179521.37     13220038.39
#Sta/Elev= 30
  3983.9  419.23  4132.5  416.99    4139  416.14  4265.9  414.14  4282.5  413.02
  4466.1  410.37  4733.7  409.58  4766.7  410.14  4800.2  409.15    4909  409.21
  4973.6  409.45  4986.5  407.87  4989.2  407.37  4992.5  407.87  5010.8  408.96
  5063.1  409.25  5126.2  411.19    5261   412.6  5266.2  413.68    5305  413.42
  5315.5  414.37  5452.2  415.06  5489.7   414.3  5590.7  415.35  5649.3  414.76
  5654.6  415.62  5745.1  414.99  5767.7  415.98  5883.4  416.08  5963.7  417.36
#Mann= 5 ,-1 , 0
  3983.9      .1       0  4766.7     .12       0    4909      .1       0
  4986.5     .07       0  4992.5      .1       0
#XS Ineff= 2 , 0
       0 4971.59  409.47               0
Permanent Ineff=
       T       F
Bank Sta=4986.5,4992.5
XS Rating Curve= 0 ,0
Exp/Cntr=0.3,0.1

Type RM Length L Ch R = 1 ,1023    ,612,612,612
BEGIN DESCRIPTION:
Mapping XS 9407a099
END DESCRIPTION:
XS GIS Cut Line= 4
       2181433.1     13219825.49      2180755.38     13219455.82
      2179732.59     13219542.08       2179252.4     13219899.15
#Sta/Elev= 30
  3758.7  423.65  3776.2  422.67  3812.1  423.03  3828.2  421.52  3901.5   420.9
  3931.7  418.96  4049.6  417.65    4057   416.4  4072.4  416.57  4182.3  412.43
  4225.9  412.24    4411  407.25  4520.2  405.97  4598.7  406.57  4739.9  406.82
  4779.2  405.87  4789.3  406.73  4819.4  406.69    5010  405.35  5017.1  405.05
  5019.8  404.55  5023.1  405.05  5040.1  405.35    5431  405.54  5677.8  408.07
    5707  407.45  5727.9  408.56  5786.3   408.1    6022  412.57  6155.5  416.99
#Mann= 5 ,-1 , 0
  3758.7      .1       0  4598.7     .12       0  4739.9     .12       0
  5017.1     .07       0  5023.1     .12       0
#XS Ineff= 2 , 0
       0 4969.32  405.94 5210.72       0  405.97
Permanent Ineff=
       T       T
Bank Sta=5010,5040.1
XS Rating Curve= 0 ,0
Exp/Cntr=0.3,0.1

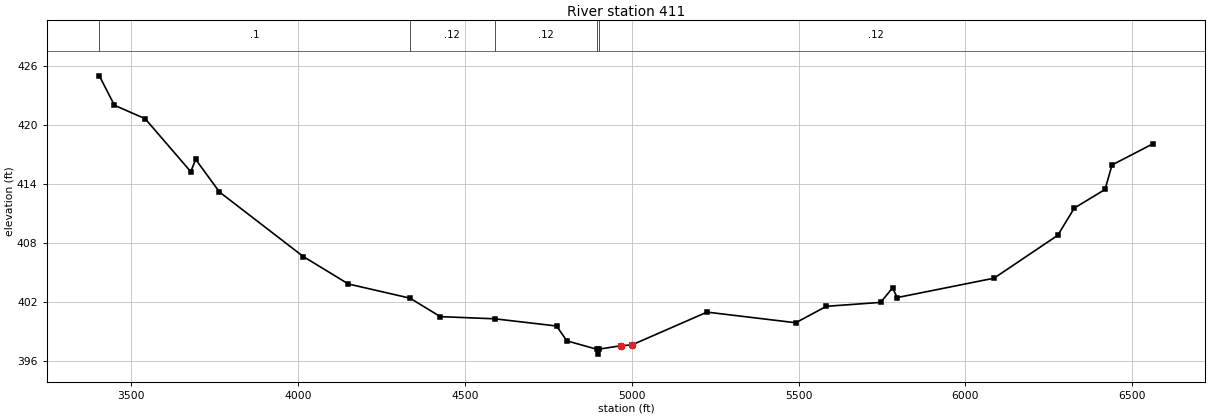
Type RM Length L Ch R = 1 ,411     ,0,0,0
BEGIN DESCRIPTION:
UNT 189 IN LACR 1.0
END DESCRIPTION:
XS GIS Cut Line= 4
      2181486.16     13219700.33      2180678.83     13219127.38
      2179858.51     13218945.09        2178895.     13219856.52
#Sta/Elev= 30
  3404.5     425  3449.6  422.01  3541.8  420.64  3678.4  415.26  3693.2   416.5
  3764.5  413.19  4015.7  406.63  4150.8  403.84  4335.3   402.4  4426.3  400.52
  4589.4   400.3  4774.6  399.57  4805.4  398.06  4894.6  397.21  4897.3  396.71
  4900.6  397.21  4968.6  397.57    5000  397.64  5225.4  400.98  5491.3   399.9
  5583.1  401.57  5745.7  401.97  5781.3  403.44  5795.5  402.46  6085.5  404.43
  6276.5  408.79  6325.9  411.55  6418.1  413.45  6439.1  415.94  6561.1  418.08
#Mann= 5 ,-1 , 0
  3404.5      .1       0  4335.3     .12       0  4589.4     .12       0
  4894.6     .07       0  4900.6     .12       0
Bank Sta=4968.6,5000
XS Rating Curve= 0 ,0
Exp/Cntr=0.3,0.1

Chan Stop Cuts=-1
Use User Specified Reach Order=0
Composite Channel Slope=5