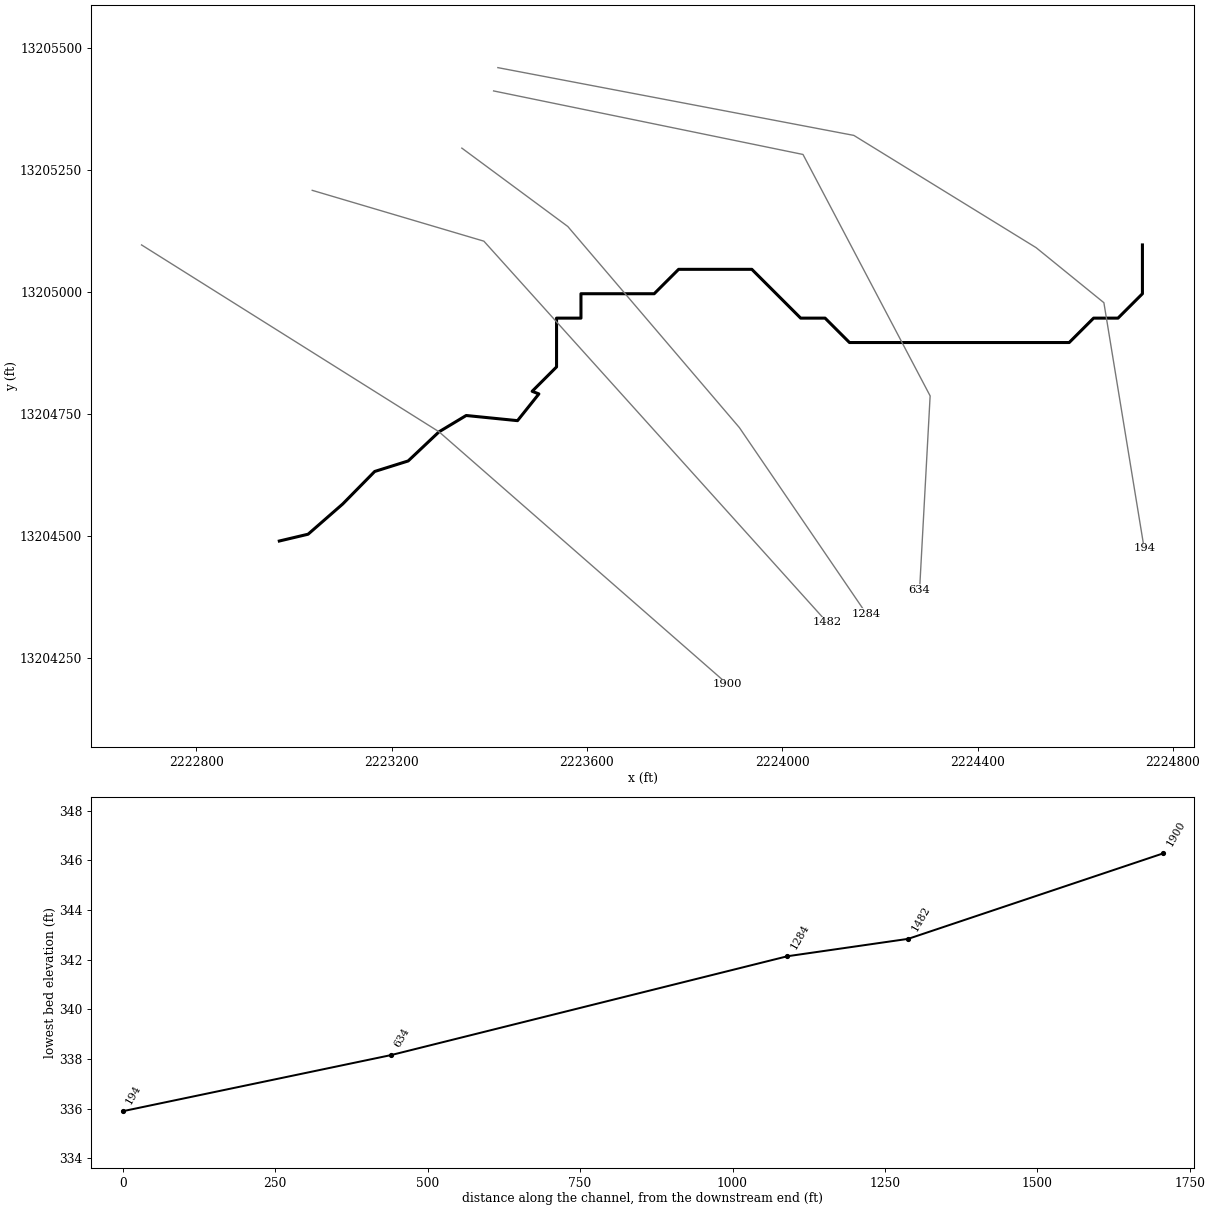
--- UNT 193 IN LACR.prj (project) ---

Proj Title=UNT 193 IN LACR Base Level Engineering
Current Plan=p01
Default Exp/Contr=0.3,0.1
English Units
Geom File=g01
Flow File=f01
Plan File=p01
BEGIN DESCRIPTION:
UNT 193 IN LACR
END DESCRIPTION:

--- UNT 193 IN LACR.p01 (plan) ---

Plan Title=Multiple Run
Short Identifier=Multiple
Geom File=g01
Flow File=f01
Subcritical Flow
K Sum by GR= 0
Std Step Tol= 0.01
Critical Tol= 0.01
Num of Std Step Trials= 20
Max Error Tol= 0.3
Flow Tol Ratio= 0.001
Split Flow NTrial= 30
Split Flow Tol= 0.02
Split Flow Ratio= 0.02
Log Output Level= 0
Friction Slope Method= 1
Unsteady Friction Slope Method= 2
Unsteady Bridges Friction Slope Method= 1
Parabolic Critical Depth
Global Vel Dist=  1 , 1 , 1
Global Log Level= 0
CheckData=True
Encroach Param= -1, 0, 0, 0
BEGIN DESCRIPTION:
Multiple Run
END DESCRIPTION:

--- UNT 193 IN LACR.f01 (steady flow) ---

Flow Title=Multiple
Number of Profiles=7
Profile Names=10-year,25-year,50-year,1pct_min,100-year,1pct_plu,500-year
River Rch & RM= UNT 193 IN LACR,Reach-1,1900
     135     182     221     198     267     361     396
Boundary for River Rch & Prof#=UNT 193 IN LACR,Reach-1,1
Up Type=0
Dn Type=3
Dn Slope=0.005
Boundary for River Rch & Prof#=UNT 193 IN LACR,Reach-1,2
Up Type=0
Dn Type=3
Dn Slope=0.005
Boundary for River Rch & Prof#=UNT 193 IN LACR,Reach-1,3
Up Type=0
Dn Type=3
Dn Slope=0.005
Boundary for River Rch & Prof#=UNT 193 IN LACR,Reach-1,4
Up Type=0
Dn Type=3
Dn Slope=0.005
Boundary for River Rch & Prof#=UNT 193 IN LACR,Reach-1,5
Up Type=0
Dn Type=3
Dn Slope=0.005
Boundary for River Rch & Prof#=UNT 193 IN LACR,Reach-1,6
Up Type=0
Dn Type=3
Dn Slope=0.005
Boundary for River Rch & Prof#=UNT 193 IN LACR,Reach-1,7
Up Type=0
Dn Type=3
Dn Slope=0.005

--- UNT 193 IN LACR.g01 (geometry) ---

Geom Title=Existing Conditions

River Reach=UNT 193 IN LACR,Reach-1
Reach XY= 26
      2222969.86     13204490.04      2223028.83     13204504.01
      2223099.63     13204565.84      2223165.25     13204632.58
      2223233.84     13204654.16      2223297.03     13204713.88
      2223352.61     13204747.30      2223457.77     13204736.74
      2223501.52     13204791.54      2223487.72     13204796.86
      2223537.72     13204846.85      2223537.72     13204946.86
      2223587.72     13204946.86      2223587.72     13204996.85
      2223737.72     13204996.85      2223787.72     13205046.85
      2223937.72     13205046.85      2223987.72     13204996.85
      2224037.72     13204946.86      2224087.72     13204946.86
      2224137.72     13204896.85      2224587.72     13204896.85
      2224637.72     13204946.86      2224687.72     13204946.86
      2224737.72     13204996.85      2224737.72     13205096.86

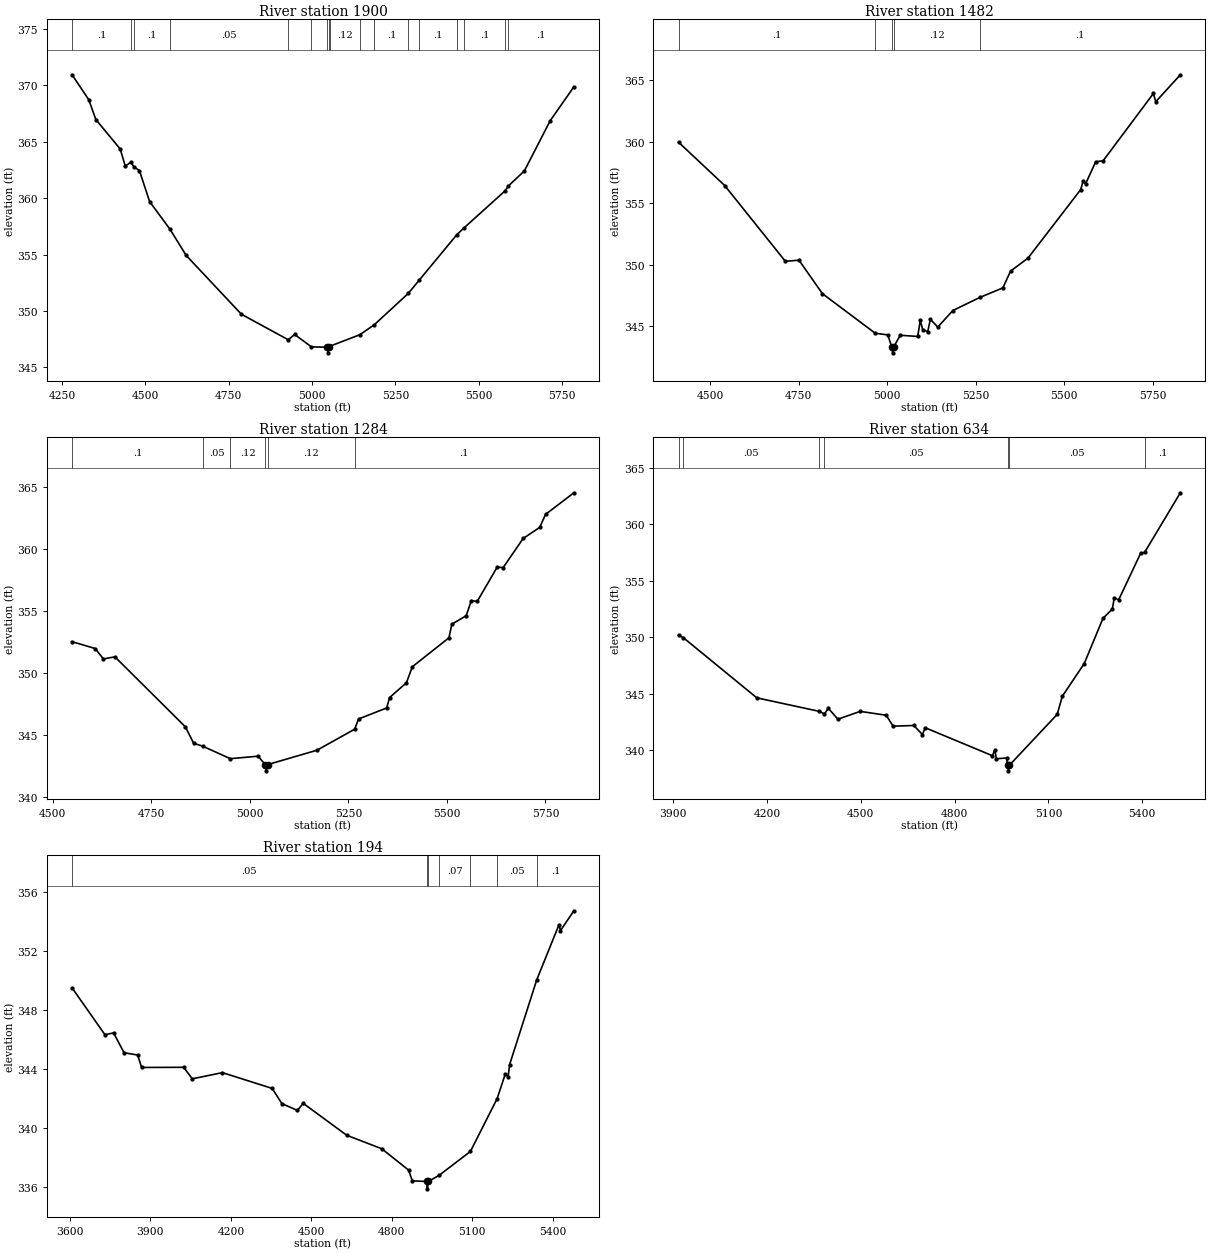
Type RM Length L Ch R = 1,1900,418,418,418
BEGIN DESCRIPTION:
UNT 193 IN LACR 2.0
END DESCRIPTION:
XS GIS Cut Line= 3
      2222687.70     13205096.87      2223297.03     13204713.88
      2223887.72     13204196.86
#Sta/Elev= 30
  4280.3  370.94  4330.4  368.73  4351.6  366.97  4424.6  364.36  4439.9  362.84
  4456.1  363.18  4466.6  362.76  4482.3  362.44  4512.9  359.69  4574.2  357.23
  4622.5  354.92  4788.2  349.70  4928.6  347.44  4947.6  347.91  4998.1  346.81
  5045.0  346.78  5047.8  346.28  5051.0  346.78  5053.0  346.86  5143.5  347.89
  5186.9  348.78  5288.5  351.55  5320.8  352.71  5433.6  356.74  5454.8  357.34
  5578.6  360.64  5588.7  361.08  5636.5  362.41  5714.3  366.88  5785.0  369.87
#Mann=17,-1,0
  4280.3     0.1       0  4456.1    0.05       0  4466.6     0.1       0
  4574.2    0.05       0  4928.6    0.12       0  4998.1    0.08       0
  5045.0    0.07       0  5051.0    0.08       0  5053.0    0.12       0
  5143.5    0.08       0  5186.9     0.1       0  5288.5    0.08       0
  5320.8     0.1       0  5433.6    0.08       0  5454.8     0.1       0
  5578.6    0.08       0  5588.7     0.1       0
Bank Sta=5045,5051
Exp/Cntr=0.3,0.1

Type RM Length L Ch R = 1,1482,198,198,198
BEGIN DESCRIPTION:
Mapping XS ea0ae72d
END DESCRIPTION:
XS GIS Cut Line= 3
      2223037.29     13205208.76      2223388.86     13205104.59
      2224091.96     13204323.38
#Sta/Elev= 30
  4410.8  359.96  4541.2  356.44  4712.6  350.28  4751.1  350.37  4817.3  347.65
  4966.7  344.43  5001.9  344.30  5013.1  343.34  5015.9  342.84  5019.1  343.34
  5037.1  344.27  5086.4  344.17  5093.9  345.47  5100.6  344.73  5114.8  344.55
  5122.3  345.57  5143.2  344.93  5185.8  346.28  5262.0  347.34  5327.1  348.12
  5348.8  349.48  5398.1  350.54  5546.8  356.10  5554.3  356.81  5561.0  356.59
  5589.4  358.37  5610.4  358.45  5752.4  363.92  5759.1  363.25  5828.5  365.44
#Mann=5,-1,0
  4410.8     0.1       0  4966.7    0.12       0  5013.1    0.07       0
  5019.1    0.12       0  5262.0     0.1       0
Bank Sta=5013.1,5019.1
Exp/Cntr=0.3,0.1

Type RM Length L Ch R = 1,1284,650,650,650
BEGIN DESCRIPTION:
Mapping XS dd7e1a3a
END DESCRIPTION:
XS GIS Cut Line= 4
      2223343.73     13205295.28      2223560.71     13205134.71
      2223912.28     13204722.38      2224172.20     13204341.16
#Sta/Elev= 30
  4548.9  352.54  4607.5  351.99  4628.5  351.15  4657.6  351.32  4836.5  345.68
  4857.4  344.36  4880.0  344.13  4950.3  343.12  5021.0  343.32  5038.9  342.64
  5041.6  342.14  5044.9  342.64  5170.3  343.80  5265.8  345.49  5276.0  346.32
  5347.1  347.20  5354.5  348.04  5397.3  349.23  5412.2  350.52  5505.0  352.85
  5512.6  353.95  5548.9  354.63  5561.9  355.85  5576.8  355.78  5627.7  358.55
  5642.6  358.50  5693.4  360.85  5735.4  361.74  5750.3  362.79  5822.1  364.53
#Mann=6,-1,0
  4548.9     0.1       0  4880.0    0.05       0  4950.3    0.12       0
  5038.9    0.07       0  5044.9    0.12       0  5265.8     0.1       0
Bank Sta=5038.9,5044.9
Exp/Cntr=0.3,0.1

Type RM Length L Ch R = 1,634,440,440,440
BEGIN DESCRIPTION:
Mapping XS 292219ea
END DESCRIPTION:
XS GIS Cut Line= 4
      2223408.77     13205412.49      2224042.48     13205282.28
      2224302.90     13204787.49      2224281.30     13204390.06
#Sta/Elev= 30
  3917.5  350.16  3932.1  349.98  4167.8  344.63  4368.0  343.43  4384.1  343.20
  4396.2  343.71  4426.9  342.74  4498.3  343.43  4581.3  343.09  4603.4  342.12
  4669.5  342.18  4697.2  341.38  4706.2  341.98  4920.9  339.50  4928.3  340.00
  4933.9  339.23  4966.1  339.30  4969.3  338.66  4972.1  338.16  4975.3  338.66
  5128.1  343.17  5144.3  344.77  5214.4  347.67  5274.4  351.68  5304.5  352.51
  5310.3  353.50  5324.5  353.32  5394.6  357.44  5407.3  357.52  5521.6  362.81
#Mann=7,-1,0
  3917.5     0.1       0  3932.1    0.05       0  4368.0    0.12       0
  4384.1    0.05       0  4969.3    0.03       0  4975.3    0.05       0
  5407.3     0.1       0
Bank Sta=4969.3,4975.3
Exp/Cntr=0.3,0.1

Type RM Length L Ch R = 1,194,0,0,0
BEGIN DESCRIPTION:
UNT 193 IN LACR 1.0
END DESCRIPTION:
XS GIS Cut Line= 5
      2223417.50     13205460.23      2224146.65     13205321.34
      2224519.92     13205091.31      2224658.80     13204978.46
      2224741.28     13204474.94
#Sta/Elev= 30
  3608.3  349.51  3730.7  346.34  3763.1  346.46  3801.9  345.12  3852.8  344.96
  3867.5  344.12  4024.0  344.13  4056.4  343.35  4168.4  343.77  4354.1  342.70
  4390.3  341.67  4448.3  341.21  4469.6  341.69  4631.7  339.53  4762.9  338.61
  4862.2  337.17  4876.4  336.44  4929.6  336.40  4932.4  335.90  4935.6  336.40
  4975.8  336.81  5092.6  338.43  5192.3  342.01  5222.9  343.69  5233.1  343.49
  5238.9  344.32  5340.2  350.07  5422.9  353.79  5428.0  353.38  5478.2  354.73
#Mann=7,-1,0
  3608.3    0.05       0  4929.6    0.07       0  4935.6    0.05       0
  4975.8    0.07       0  5092.6    0.08       0  5192.3    0.05       0
  5340.2     0.1       0
Bank Sta=4929.6,4935.6
Exp/Cntr=0.3,0.1

Chan Stop Cuts=-1