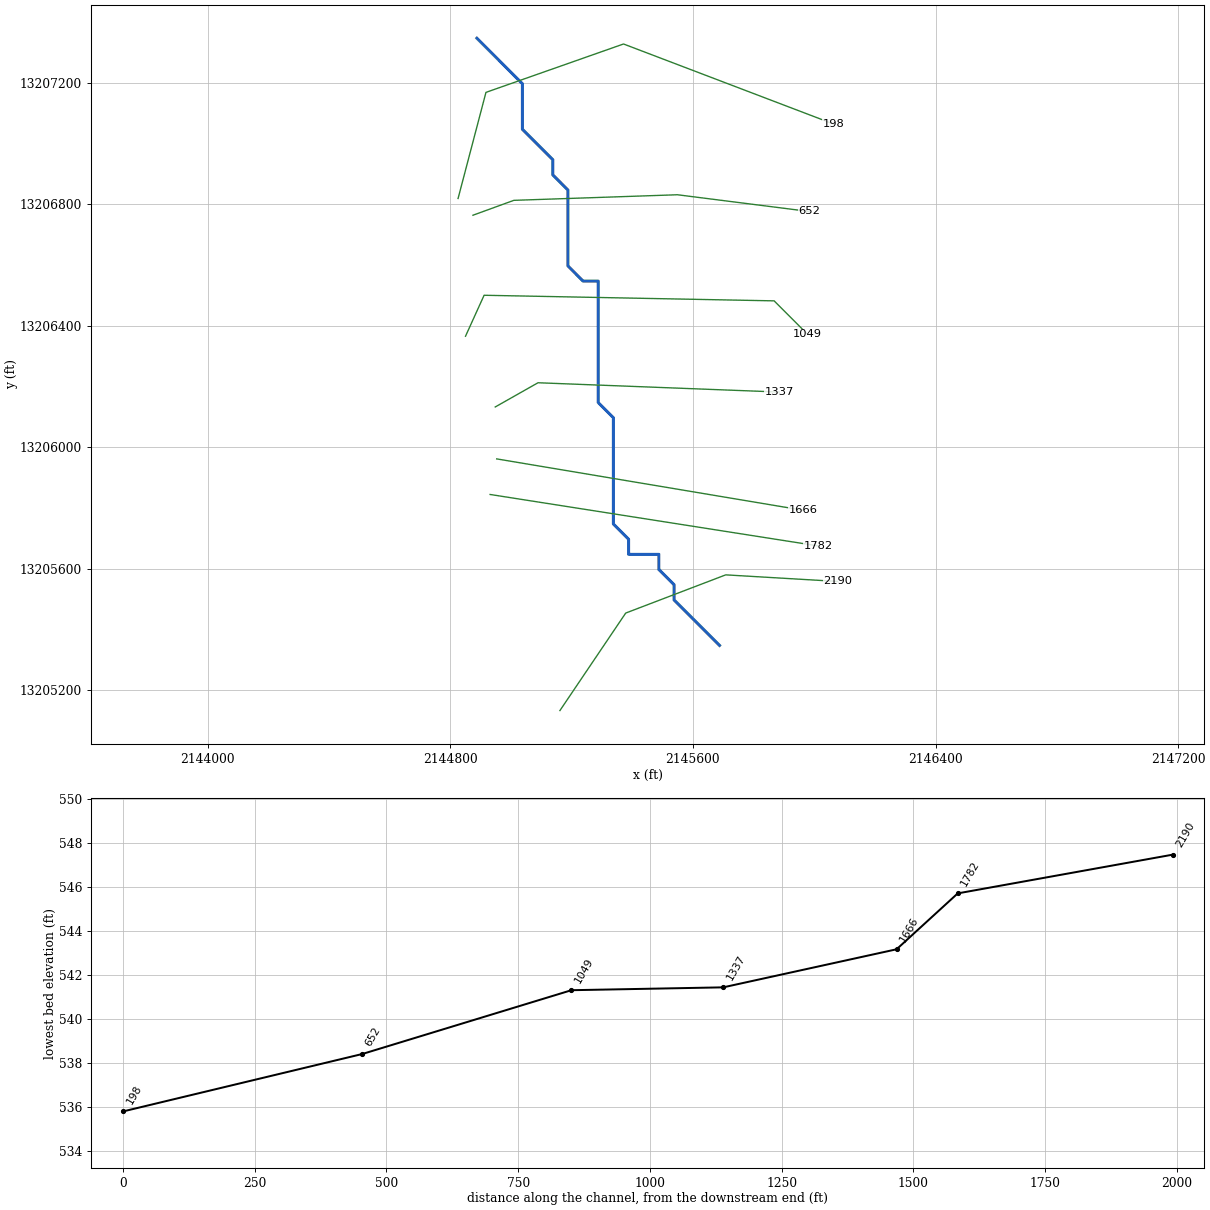
--- UNT 202 IN LACR.prj (project) ---

Proj Title=UNT 202 IN LACR Base Level Engineering
Current Plan=p01
Default Exp/Contr=0.3,0.1
English Units
Geom File=g01
Flow File=f01
Plan File=p01
Y Axis Title=Elevation
X Axis Title(PF)=Main Channel Distance
X Axis Title(XS)=Station
BEGIN DESCRIPTION:
UNT 202 IN LACR
END DESCRIPTION:
DSS Export Rating Curves= 0
DSS Export Rating Curve Sorted= 0
DSS Export Volume Flow Curves= 0
DXF OffsetX= 0
DXF OffsetY= 0
DXF ScaleX= 1
DXF ScaleY= 10

--- UNT 202 IN LACR.p01 (plan) ---

Plan Title=Multiple Run
Short Identifier=Multiple
Geom File=g01
Flow File=f01
Subcritical Flow
K Sum by GR= 0
Std Step Tol= 0.01
Critical Tol= 0.01
Num of Std Step Trials= 20
Max Error Tol= 0.3
Flow Tol Ratio= 0.001
Split Flow NTrial= 30
Split Flow Tol= 0.02
Split Flow Ratio= 0.02
Log Output Level= 0
Friction Slope Method= 1
Unsteady Friction Slope Method= 2
Unsteady Bridges Friction Slope Method= 1
Parabolic Critical Depth
Global Vel Dist=  1 , 1 , 1
Global Log Level= 0
CheckData=True
Encroach Param= -1, 0, 0, 0
BEGIN DESCRIPTION:
Multiple Run
END DESCRIPTION:

--- UNT 202 IN LACR.f01 (steady flow) ---

Flow Title=Multiple
Program Version=4.10
Number of Profiles= 7
Profile Names=10-year,25-year,50-year,1pct_min,100-year,1pct_plu,500-year
River Rch & RM=UNT 202 IN LACR,Reach-1         ,2190
     159     221     271     246     333     450     508
Boundary for River Rch & Prof#=UNT 202 IN LACR,Reach-1         , 1
Up Type= 0
Dn Type= 3
Dn Slope=0.003
Boundary for River Rch & Prof#=UNT 202 IN LACR,Reach-1         , 2
Up Type= 0
Dn Type= 3
Dn Slope=0.003
Boundary for River Rch & Prof#=UNT 202 IN LACR,Reach-1         , 3
Up Type= 0
Dn Type= 3
Dn Slope=0.003
Boundary for River Rch & Prof#=UNT 202 IN LACR,Reach-1         , 4
Up Type= 0
Dn Type= 3
Dn Slope=0.003
Boundary for River Rch & Prof#=UNT 202 IN LACR,Reach-1         , 5
Up Type= 0
Dn Type= 3
Dn Slope=0.003
Boundary for River Rch & Prof#=UNT 202 IN LACR,Reach-1         , 6
Up Type= 0
Dn Type= 3
Dn Slope=0.003
Boundary for River Rch & Prof#=UNT 202 IN LACR,Reach-1         , 7
Up Type= 0
Dn Type= 3
Dn Slope=0.003
DSS Import GetInterval= 0
DSS Import GetPeak= 0
DSS Import FillOption= 0

--- UNT 202 IN LACR.g01 (geometry) ---

Geom Title=Existing Conditions
Program Version=4.10

River Reach=UNT 202 IN LACR ,Reach-1
Reach XY= 23
      2145687.72     13205346.85      2145637.72     13205396.85
      2145587.72     13205446.86      2145537.72     13205496.85
      2145537.72     13205546.85      2145487.72     13205596.86
      2145487.72     13205646.85      2145387.72     13205646.85
      2145387.72     13205696.85      2145337.72     13205746.86
      2145337.72     13206096.86      2145287.72     13206146.85
      2145287.72     13206546.85      2145237.72     13206546.85
      2145187.72     13206596.86      2145187.72     13206846.85
      2145137.72     13206896.86      2145137.72     13206946.85
      2145037.72     13207046.85      2145037.72     13207196.85
      2144987.72     13207246.86      2144937.72     13207296.85
      2144887.72     13207346.85

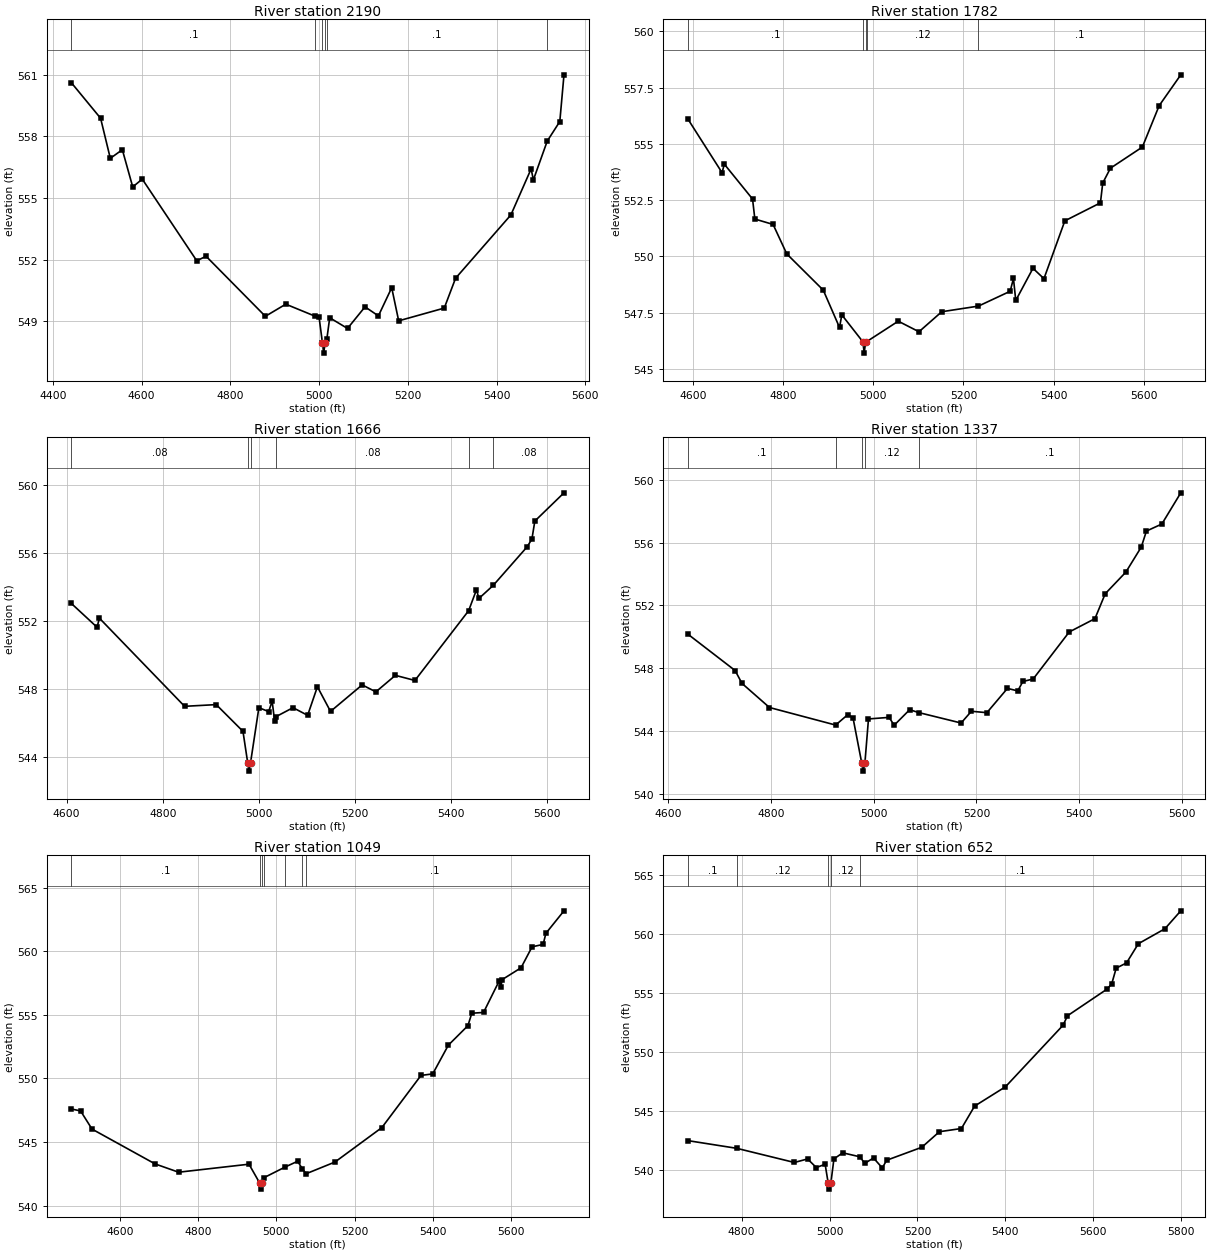
Type RM Length L Ch R = 1 ,2190    ,408,408,408
BEGIN DESCRIPTION:
UNT 202 IN LACR 3.0
END DESCRIPTION:
XS GIS Cut Line= 4
      2145161.33      13205132.2      2145378.33     13205453.36
       2145708.2     13205579.23      2146077.09     13205557.53
#Sta/Elev= 30
  4441.8  560.61  4507.8  558.88  4529.7  556.93  4556.8  557.35  4580.2  555.54
  4601.7  555.92  4724.5  551.95  4745.5  552.17  4879.1  549.25  4925.1  549.84
  4991.8  549.25    5000  549.23  5007.7  547.96  5010.5  547.46  5013.7  547.96
  5017.8  548.17  5024.1  549.18  5064.2  548.66  5103.7  549.71  5133.8  549.27
  5163.8  550.64  5179.5  549.03  5282.2  549.65  5307.7   551.1  5432.4  554.18
    5478  556.42    5483  555.88  5514.3  557.77  5542.6  558.72    5552  560.99
#Mann= 6 ,-1 , 0
  4441.8      .1       0  4991.8     .12       0  5007.7     .07       0
  5013.7     .12       0  5017.8      .1       0  5514.3     .12       0
Bank Sta=5007.7,5013.7
XS Rating Curve= 0 ,0
Exp/Cntr=0.3,0.1

Type RM Length L Ch R = 1 ,1782    ,116,116,116
BEGIN DESCRIPTION:
Mapping XS cd34babe
END DESCRIPTION:
XS GIS Cut Line= 2
      2144931.28     13205843.99        2146012.     13205674.72
#Sta/Elev= 30
  4588.6  556.09    4664  553.72    4669   554.1  4731.7  552.55  4736.8  551.66
  4777.3  551.42  4807.7  550.11  4888.7   548.5  4924.8  546.84  4929.9   547.4
  4976.8   546.2  4979.5   545.7  4982.8   546.2    4985  546.21  5055.2  547.12
  5101.2  546.65  5151.8  547.54  5233.2  547.79  5303.7  548.45    5311  549.02
  5316.1  548.04  5354.3  549.47  5378.7  549.01  5425.1  551.58  5504.1  552.38
  5509.2  553.26  5526.3  553.92  5597.2  554.86  5634.5   556.7  5682.5  558.07
#Mann= 5 ,-1 , 0
  4588.6      .1       0  4976.8     .07       0  4982.8      .1       0
    4985     .12       0  5233.2      .1       0
Bank Sta=4976.8,4982.8
XS Rating Curve= 0 ,0
Exp/Cntr=0.3,0.1

Type RM Length L Ch R = 1 ,1666    ,329,329,329
BEGIN DESCRIPTION:
UNT 202 IN LACR 2.0
END DESCRIPTION:
XS GIS Cut Line= 2
      2144952.97     13205961.18      2145963.51     13205792.03
#Sta/Elev= 30
  4609.9  553.02  4663.4  551.62  4668.4  552.15  4845.5  546.97  4911.3  547.07
  4966.9   545.5  4976.7  543.66  4979.5  543.16  4982.7  543.66    5000  546.89
  5020.3  546.66  5027.6  547.27  5032.7  546.11  5036.1  546.37    5071  546.89
  5101.4  546.44  5121.7  548.12    5149  546.67  5214.8  548.23  5243.3  547.82
  5283.9  548.79  5324.5  548.49  5436.2  552.59  5452.5  553.82  5457.6  553.31
  5487.4  554.08  5557.7  556.34  5567.8   556.8  5573.9  557.86  5634.5  559.52
#Mann= 6 ,-1 , 0
  4609.9     .08       0  4976.7     .07       0  4982.7     .08       0
  5036.1     .08       0  5436.2      .1       0  5487.4     .08       0
Bank Sta=4976.7,4982.7
XS Rating Curve= 0 ,0
Exp/Cntr=0.3,0.1

Type RM Length L Ch R = 1 ,1337    ,288,288,288
BEGIN DESCRIPTION:
Mapping XS c122412d
END DESCRIPTION:
XS GIS Cut Line= 3
      2144948.13     13206132.26      2145089.16     13206211.97
      2145884.48     13206181.38
#Sta/Elev= 30
  4639.3  550.16  4730.7  547.85    4744  547.03  4797.5  545.49  4926.1  544.37
    4950  545.04    4960  544.82    4977  541.93  4979.7  541.43    4983  541.93
    4990  544.76    5030  544.86    5040  544.36  5070.1  545.35  5087.3  545.17
  5170.1   544.5  5190.1  545.25  5220.2  545.16  5260.2  546.71  5280.2  546.55
  5290.2  547.15  5310.2  547.31  5380.3  550.31  5430.3  551.16  5450.3  552.75
  5490.4  554.13  5520.4  555.73  5530.4  556.75  5560.4   557.2  5597.2  559.19
#Mann= 5 ,-1 , 0
  4639.3      .1       0  4926.1     .12       0    4977     .07       0
    4983     .12       0  5087.3      .1       0
Bank Sta=4977,4983
XS Rating Curve= 0 ,0
Exp/Cntr=0.3,0.1

Type RM Length L Ch R = 1 ,1049    ,397,397,397
BEGIN DESCRIPTION:
Mapping XS 15a3d22c
END DESCRIPTION:
XS GIS Cut Line= 4
      2144850.05     13206365.24      2144911.36     13206500.13
      2145867.79     13206481.73       2145977.9     13206371.62
#Sta/Elev= 30
  4475.4   547.6  4499.1  547.45  4528.4  546.02  4689.9  543.28    4750  542.63
    4930  543.26    4957   541.8  4959.7   541.3    4963   541.8  4967.7  542.19
  5022.6  543.04  5054.4  543.49  5066.5   542.9  5076.2  542.51    5150  543.43
    5270  546.14  5370.1  550.24  5400.1  550.36  5440.1  552.62  5490.1  554.15
  5500.1  555.13  5530.1  555.19  5569.5  557.63  5574.5  557.23  5577.6  557.77
    5626   558.7  5654.3  560.35  5682.6  560.54  5689.6  561.41  5735.9  563.18
#Mann= 7 ,-1 , 0
  4475.4      .1       0    4957     .07       0    4963      .1       0
  4967.7     .12       0  5022.6      .1       0  5066.5     .12       0
  5076.2      .1       0
Bank Sta=4957,4963
XS Rating Curve= 0 ,0
Exp/Cntr=0.3,0.1

Type RM Length L Ch R = 1 ,652     ,454,454,454
BEGIN DESCRIPTION:
Mapping XS 8a06e256
END DESCRIPTION:
XS GIS Cut Line= 4
      2144874.57     13206763.75      2145009.45      13206812.8
      2145548.98      13206831.2      2145983.53     13206776.11
#Sta/Elev= 30
  4678.1  542.51  4788.9  541.86    4920  540.66    4950  540.96    4970  540.23
    4990  540.51    4997   538.9  4999.7   538.4    5003   538.9    5010  540.96
    5030  541.48  5069.3  541.14    5080  540.58  5100.1  541.04  5120.1   540.2
  5130.1  540.85  5210.1  541.95  5250.1  543.27  5300.2  543.54  5330.2  545.44
  5400.5  547.08  5531.6   552.3  5541.6   553.1  5632.4  555.38  5642.4  555.82
  5652.5  557.14    5676  557.58  5702.9  559.21  5763.4  560.48  5799.5     562
#Mann= 5 ,-1 , 0
  4678.1      .1       0  4788.9     .12       0    4997     .07       0
    5003     .12       0  5069.3      .1       0
Bank Sta=4997,5003
XS Rating Curve= 0 ,0
Exp/Cntr=0.3,0.1

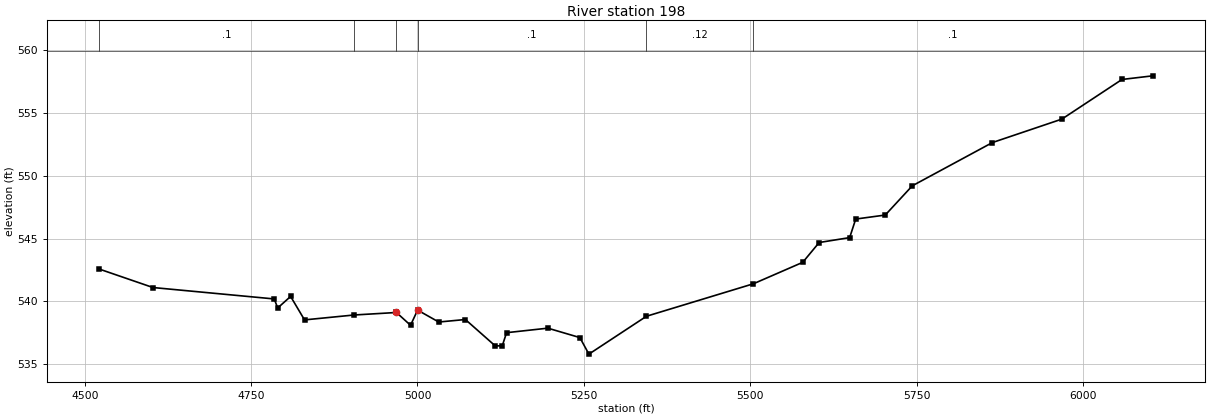
Type RM Length L Ch R = 1 ,198     ,0,0,0
BEGIN DESCRIPTION:
UNT 202 IN LACR 1.0
END DESCRIPTION:
XS GIS Cut Line= 4
      2144825.52     13206818.92      2144917.49      13207168.4
      2145371.18      13207327.8       2146063.3     13207064.43
#Sta/Elev= 30
    4522  542.57  4602.6   541.1  4784.8  540.19    4790  539.47  4809.4  540.39
  4830.3  538.52  4904.7  538.91  4968.4  539.11  4989.6  538.09  5000.2   539.3
    5032  538.35    5072  538.55  5116.8  536.45  5127.4  536.45  5133.9   537.5
  5195.9  537.86    5244  537.11  5257.6  535.79  5344.1  538.81  5504.8   541.4
  5578.9  543.11  5603.6  544.69  5649.4  545.08  5658.5  546.56  5702.9  546.88
  5743.5  549.21  5863.9  552.66  5968.3  554.53  6058.6  557.69  6104.8  557.98
#Mann= 6 ,-1 , 0
    4522      .1       0  4904.7     .12       0  4968.4     .07       0
  5000.2      .1       0  5344.1     .12       0  5504.8      .1       0
Bank Sta=4968.4,5000.2
XS Rating Curve= 0 ,0
Exp/Cntr=0.3,0.1

Chan Stop Cuts=-1
Use User Specified Reach Order=0
Composite Channel Slope=5