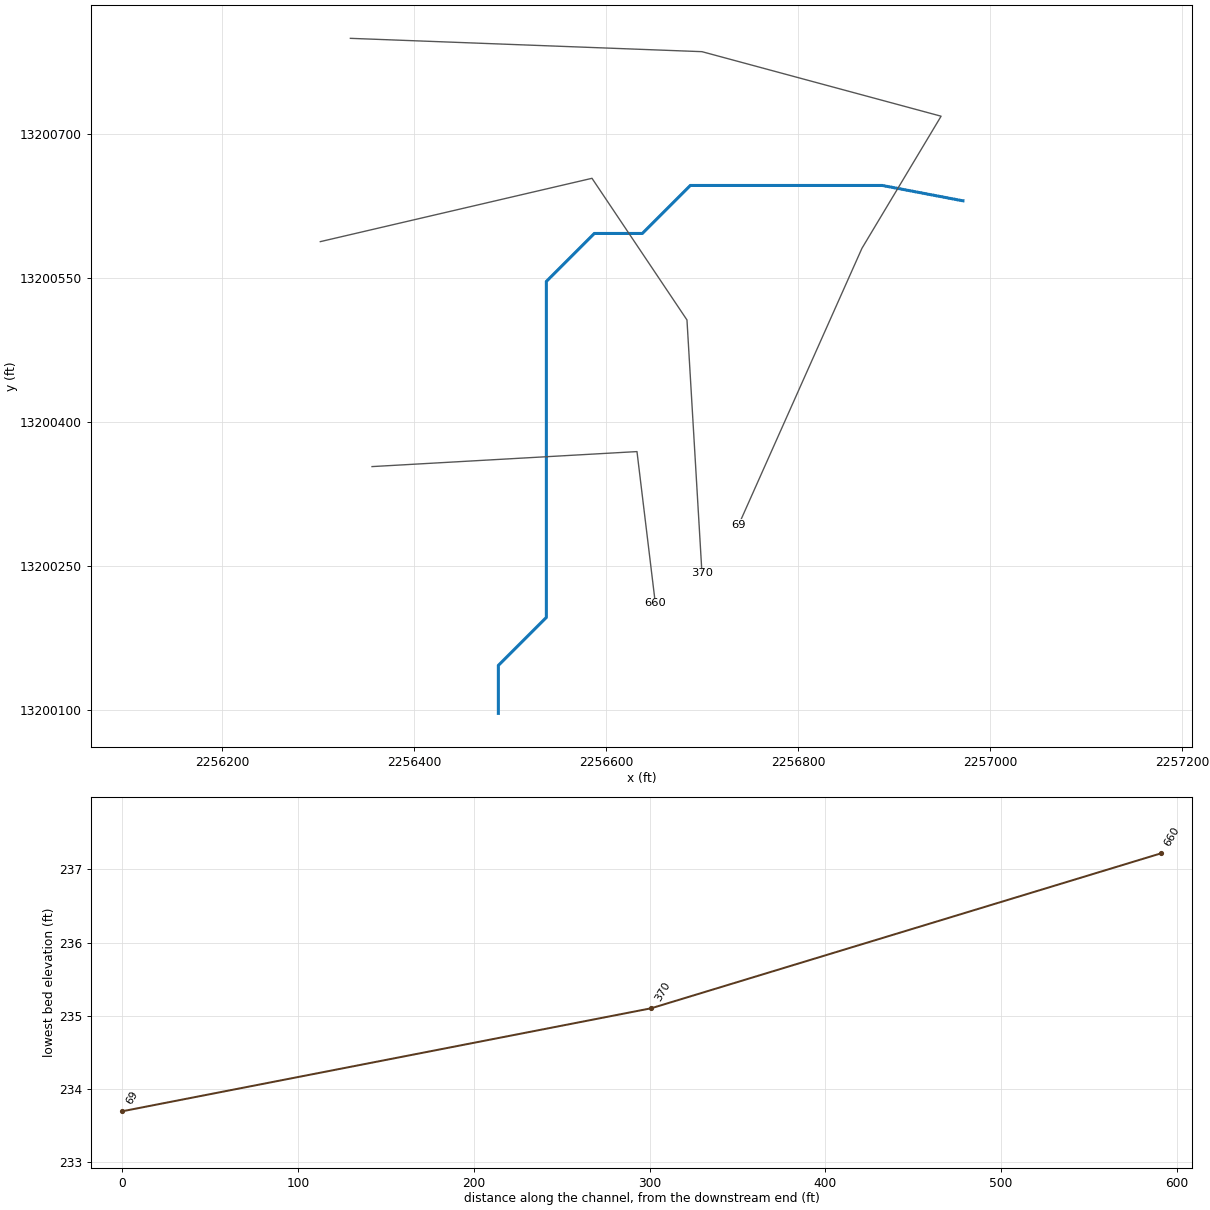
--- UNT 203 IN LACR.prj (project) ---

Proj Title=UNT 203 IN LACR Base Level Engineering
Current Plan=p01
Default Exp/Contr=0.3,0.1
English Units
Geom File=g01
Flow File=f01
Plan File=p01
Y Axis Title=Elevation
X Axis Title(PF)=Main Channel Distance
X Axis Title(XS)=Station
BEGIN DESCRIPTION:
UNT 203 IN LACR
END DESCRIPTION:
DSS Export Rating Curves= 0
DSS Export Rating Curve Sorted= 0
DSS Export Volume Flow Curves= 0
DXF OffsetX= 0
DXF OffsetY= 0
DXF ScaleX= 1
DXF ScaleY= 10

--- UNT 203 IN LACR.p01 (plan) ---

Plan Title=Multiple Run
Short Identifier=Multiple
Geom File=g01
Flow File=f01
Subcritical Flow
K Sum by GR= 0
Std Step Tol= 0.01
Critical Tol= 0.01
Num of Std Step Trials= 20
Max Error Tol= 0.3
Flow Tol Ratio= 0.001
Split Flow NTrial= 30
Split Flow Tol= 0.02
Split Flow Ratio= 0.02
Log Output Level= 0
Friction Slope Method= 1
Unsteady Friction Slope Method= 2
Unsteady Bridges Friction Slope Method= 1
Parabolic Critical Depth
Global Vel Dist=  1 , 1 , 1
Global Log Level= 0
CheckData=True
Encroach Param= -1, 0, 0, 0
BEGIN DESCRIPTION:
Multiple Run
END DESCRIPTION:

--- UNT 203 IN LACR.f01 (steady flow) ---

Flow Title=Multiple
Number of Profiles=7
Profile Names=10-year,25-year,50-year,1pct_min,100-year,1pct_plu,500-year
River Rch & RM= UNT 203 IN LACR,Reach-1,660
     167     226     274     245     331     447     490
Boundary for River Rch & Prof#=UNT 203 IN LACR,Reach-1,1
Up Type=0
Dn Type=3
Dn Slope=0.005
Boundary for River Rch & Prof#=UNT 203 IN LACR,Reach-1,2
Up Type=0
Dn Type=3
Dn Slope=0.005
Boundary for River Rch & Prof#=UNT 203 IN LACR,Reach-1,3
Up Type=0
Dn Type=3
Dn Slope=0.005
Boundary for River Rch & Prof#=UNT 203 IN LACR,Reach-1,4
Up Type=0
Dn Type=3
Dn Slope=0.005
Boundary for River Rch & Prof#=UNT 203 IN LACR,Reach-1,5
Up Type=0
Dn Type=3
Dn Slope=0.005
Boundary for River Rch & Prof#=UNT 203 IN LACR,Reach-1,6
Up Type=0
Dn Type=3
Dn Slope=0.005
Boundary for River Rch & Prof#=UNT 203 IN LACR,Reach-1,7
Up Type=0
Dn Type=3
Dn Slope=0.005

--- UNT 203 IN LACR.g01 (geometry) ---

Geom Title=Existing Conditions
Program Version=4.10

River Reach=UNT 203 IN LACR ,Reach-1
Reach XY= 18
      2256487.72     13200096.85      2256487.72     13200146.85
      2256537.72     13200196.86      2256537.72     13200246.85
      2256537.72     13200296.85      2256537.72     13200346.86
      2256537.72     13200396.85      2256537.72     13200446.85
      2256537.72     13200496.85      2256537.72     13200546.85
      2256587.72     13200596.85      2256637.72     13200596.85
      2256687.72     13200646.85      2256737.72     13200646.85
      2256787.72     13200646.85      2256837.72     13200646.85
      2256887.72     13200646.85      2256971.73     13200630.86

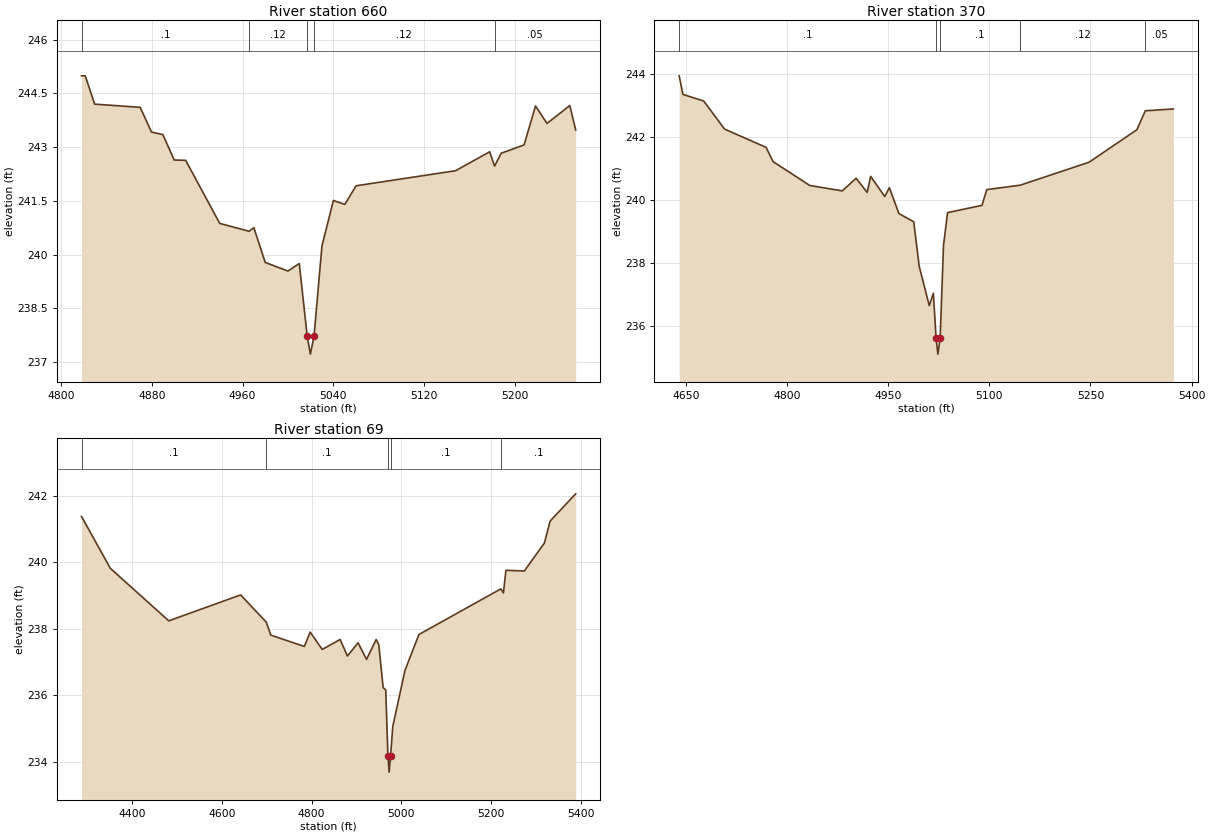
Type RM Length L Ch R = 1 ,660     ,290,290,290
BEGIN DESCRIPTION:
UNT 203 IN LACR 2.0
END DESCRIPTION:
XS GIS Cut Line= 3
      2256356.11     13200353.96      2256632.13     13200369.59
      2256651.22      13200211.7
#Sta/Elev= 30
  4818.1  244.99  4821.4  244.99  4829.7   244.2  4869.8  244.11  4879.8  243.42
  4889.8  243.35  4899.8  242.64  4909.9  242.63  4939.9  240.87  4965.8  240.65
    4970  240.75    4980  239.78    5000  239.54    5010  239.75    5017  237.72
  5019.8  237.22    5023  237.72    5030  240.24  5040.1  241.51  5050.1   241.4
  5060.1  241.92  5147.7  242.34  5177.8  242.87  5182.1  242.47    5188  242.83
  5208.1  243.06  5218.2  244.15  5228.3  243.66  5248.4  244.16  5253.6  243.48
#Mann= 5 ,-1 , 0
  4818.1      .1       0  4965.8     .12       0    5017     .07       0
    5023     .12       0  5182.1     .05       0
Bank Sta=5017,5023
XS Rating Curve= 0 ,0
Exp/Cntr=0.3,0.1

Type RM Length L Ch R = 1 ,370     ,301,301,301
BEGIN DESCRIPTION:
Mapping XS 4c0ad85c
END DESCRIPTION:
XS GIS Cut Line= 4
      2256302.22     13200588.33      2256585.26     13200654.31
      2256684.21     13200506.74      2256699.84      13200242.8
#Sta/Elev= 30
  4640.2  243.93  4645.8  243.34  4676.6  243.13  4707.5  242.24  4769.1  241.66
  4779.3  241.21  4833.9  240.45    4882  240.28  4902.5  240.68    4919  240.23
  4924.1  240.74    4945   240.1  4951.8  240.38    4966  239.56    4988   239.3
    4996  237.89    5011  236.64  5017.1  237.03  5021.1   235.6  5023.8   235.1
  5027.1   235.6  5032.1  238.55  5038.1  239.59  5089.1  239.82  5096.3  240.32
  5145.7  240.46    5248  241.19  5318.8  242.22  5331.3  242.82  5372.9  242.88
#Mann= 5 ,-1 , 0
  4640.2      .1       0  5021.1     .07       0  5027.1      .1       0
  5145.7     .12       0  5331.3     .05       0
Bank Sta=5021.1,5027.1
XS Rating Curve= 0 ,0
Exp/Cntr=0.3,0.1

Type RM Length L Ch R = 1 ,69      ,0,0,0
BEGIN DESCRIPTION:
UNT 203 IN LACR 1.0
END DESCRIPTION:
XS GIS Cut Line= 5
      2256333.55     13200800.14      2256699.84     13200786.25
      2256948.97     13200719.01      2256866.51     13200581.39
      2256738.02     13200293.16
#Sta/Elev= 30
  4287.7  241.38  4351.9  239.82    4482  238.24  4642.1  239.02  4699.2   238.2
  4709.3  237.81  4783.9  237.47  4797.1   237.9  4823.8  237.38  4863.7  237.68
  4879.9  237.18  4903.6  237.58  4922.5  237.08  4943.9  237.68  4949.8  237.52
  4959.5  236.23  4965.3  236.16  4970.1  234.19  4972.8  233.69  4976.1  234.19
  4980.9  235.06  5008.1  236.75  5039.2  237.83  5221.5   239.2  5227.4  239.08
  5232.9  239.76  5273.9  239.74  5318.6  240.58  5331.3  241.24  5388.3  242.06
#Mann= 5 ,-1 , 0
  4287.7      .1       0  4699.2      .1       0  4970.1    .035       0
  4976.1      .1       0  5221.5      .1       0
Bank Sta=4970.1,4976.1
XS Rating Curve= 0 ,0
Exp/Cntr=0.3,0.1

Chan Stop Cuts=-1
Use User Specified Reach Order=0
Composite Channel Slope=5