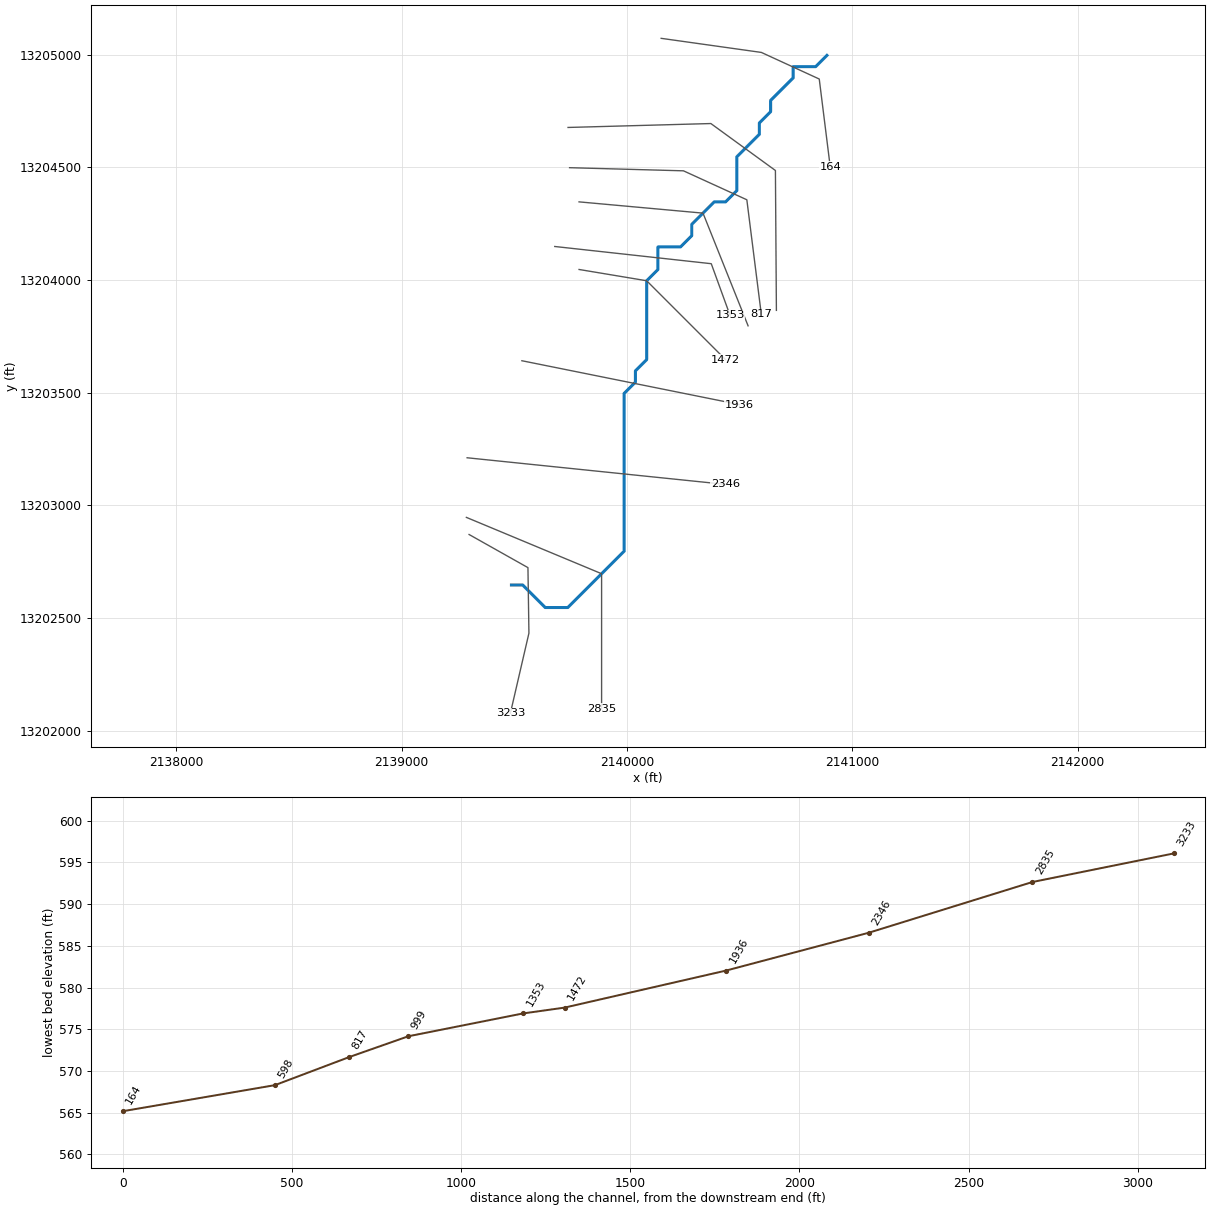
--- UNT 204 IN LACR.prj (project) ---

Proj Title=UNT 204 IN LACR Base Level Engineering
Current Plan=p01
Default Exp/Contr=0.3,0.1
English Units
Geom File=g01
Flow File=f01
Plan File=p01
Y Axis Title=Elevation
X Axis Title(PF)=Main Channel Distance
X Axis Title(XS)=Station
BEGIN DESCRIPTION:
UNT 204 IN LACR
END DESCRIPTION:
DSS Export Rating Curves= 0
DSS Export Rating Curve Sorted= 0
DSS Export Volume Flow Curves= 0
DXF OffsetX= 0
DXF OffsetY= 0
DXF ScaleX= 1
DXF ScaleY= 10

--- UNT 204 IN LACR.p01 (plan) ---

Plan Title=Multiple Run
Short Identifier=Multiple
Geom File=g01
Flow File=f01
Subcritical Flow
K Sum by GR= 0
Std Step Tol= 0.01
Critical Tol= 0.01
Num of Std Step Trials= 20
Max Error Tol= 0.3
Flow Tol Ratio= 0.001
Split Flow NTrial= 30
Split Flow Tol= 0.02
Split Flow Ratio= 0.02
Log Output Level= 0
Friction Slope Method= 1
Unsteady Friction Slope Method= 2
Unsteady Bridges Friction Slope Method= 1
Parabolic Critical Depth
Global Vel Dist=  1 , 1 , 1
Global Log Level= 0
CheckData=True
Encroach Param= -1, 0, 0, 0
BEGIN DESCRIPTION:
Multiple Run
END DESCRIPTION:

--- UNT 204 IN LACR.f01 (steady flow) ---

Flow Title=Multiple
Program Version=4.10
Number of Profiles= 7
Profile Names=10-year,25-year,50-year,1pct_min,100-year,1pct_plu,500-year
River Rch & RM=UNT 204 IN LACR,Reach-1         ,3233
     139     191     235     212     287     389     437
Boundary for River Rch & Prof#=UNT 204 IN LACR,Reach-1         , 1
Up Type= 0
Dn Type= 3
Dn Slope=0.005
Boundary for River Rch & Prof#=UNT 204 IN LACR,Reach-1         , 2
Up Type= 0
Dn Type= 3
Dn Slope=0.005
Boundary for River Rch & Prof#=UNT 204 IN LACR,Reach-1         , 3
Up Type= 0
Dn Type= 3
Dn Slope=0.005
Boundary for River Rch & Prof#=UNT 204 IN LACR,Reach-1         , 4
Up Type= 0
Dn Type= 3
Dn Slope=0.005
Boundary for River Rch & Prof#=UNT 204 IN LACR,Reach-1         , 5
Up Type= 0
Dn Type= 3
Dn Slope=0.005
Boundary for River Rch & Prof#=UNT 204 IN LACR,Reach-1         , 6
Up Type= 0
Dn Type= 3
Dn Slope=0.005
Boundary for River Rch & Prof#=UNT 204 IN LACR,Reach-1         , 7
Up Type= 0
Dn Type= 3
Dn Slope=0.005
DSS Import GetInterval= 0
DSS Import GetPeak= 0
DSS Import FillOption= 0

--- UNT 204 IN LACR.g01 (geometry) ---

Geom Title=Existing Conditions
Program Version=4.10

River Reach=UNT 204 IN LACR ,Reach-1
Reach XY= 30
      2139487.72     13202646.86      2139537.72     13202646.86
      2139637.72     13202546.85      2139737.72     13202546.85
      2139837.72     13202646.86      2139937.72     13202746.85
      2139987.72     13202796.86      2139987.72     13203496.85
      2140037.72     13203546.85      2140037.72     13203596.85
      2140087.72     13203646.86      2140087.72     13203996.85
      2140137.72     13204046.85      2140137.72     13204146.86
      2140237.72     13204146.86      2140287.72     13204196.85
      2140287.72     13204246.85      2140337.72     13204296.86
      2140387.72     13204346.85      2140437.72     13204346.85
      2140487.72     13204396.85      2140487.72     13204546.85
      2140587.72     13204646.85      2140587.72     13204696.85
      2140637.72     13204746.85      2140637.72     13204796.86
      2140737.72     13204896.85      2140737.72     13204946.86
      2140837.72     13204946.86      2140887.72     13204996.85

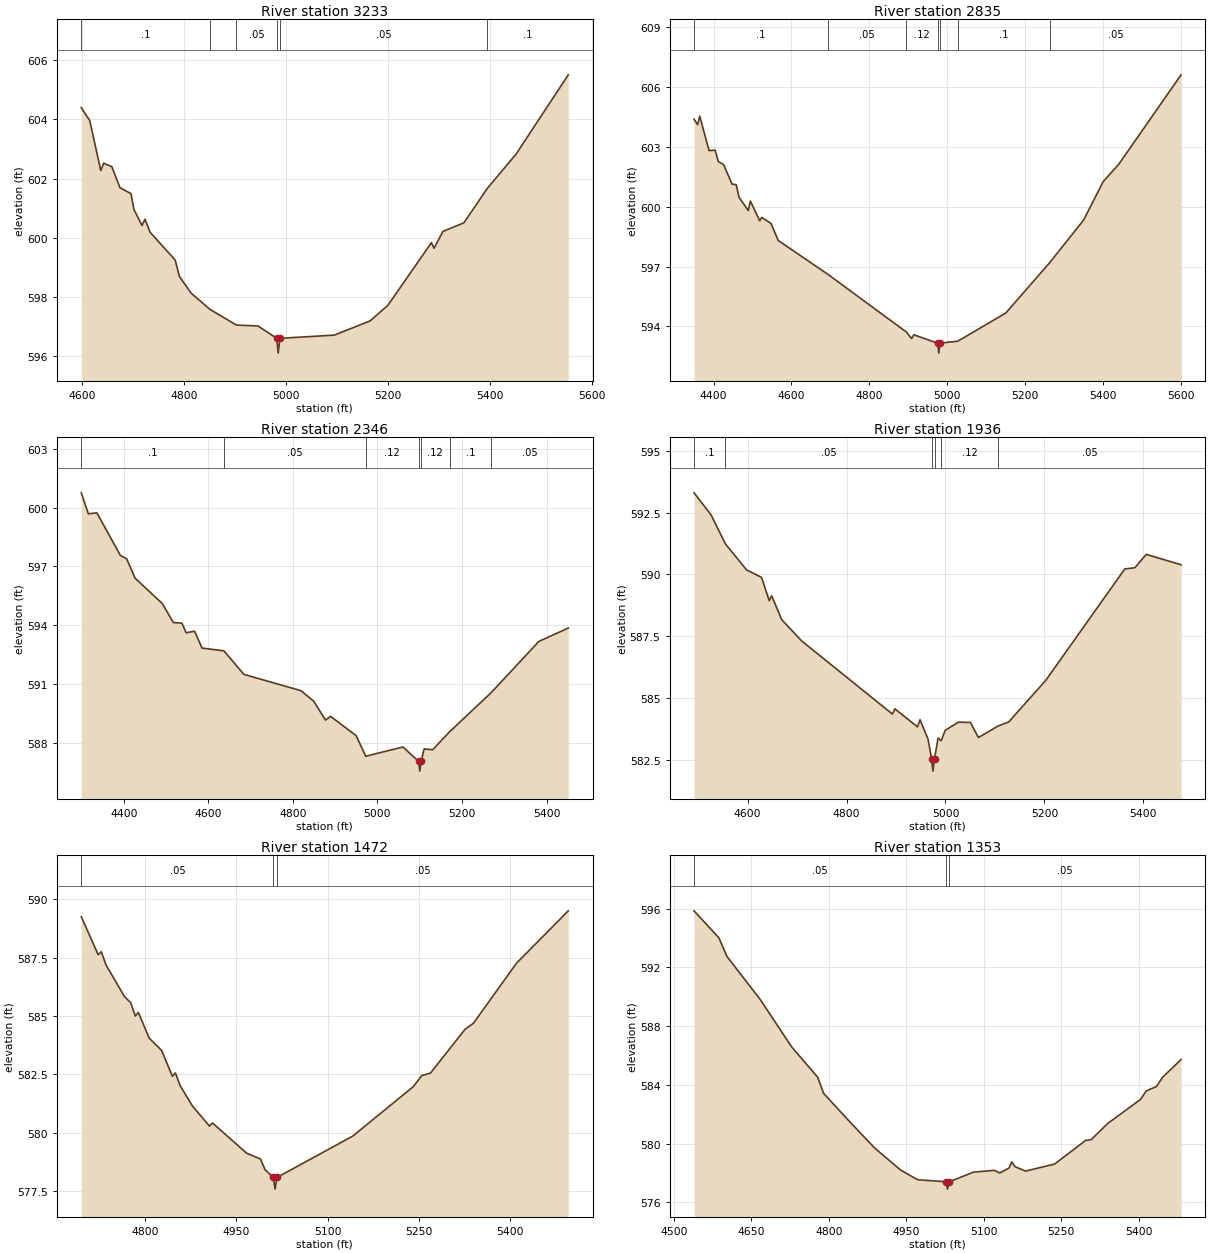
Type RM Length L Ch R = 1 ,3233    ,418,418,418
BEGIN DESCRIPTION:
UNT 204 IN LACR 7.0
END DESCRIPTION:
XS GIS Cut Line= 4
       2139299.7     13202870.88      2139560.92     13202723.91
      2139565.26     13202433.11      2139482.79     13202077.19
#Sta/Elev= 30
  4598.5   604.4  4615.2  603.96  4636.8  602.27  4642.6  602.52  4658.5   602.4
  4674.4  601.69  4696.1  601.49  4701.9  600.95  4717.8  600.41  4723.5  600.62
  4733.7  600.18  4782.8  599.24  4791.3  598.68  4814.2  598.12  4851.2  597.57
  4903.1  597.04  4945.3  597.01  4982.3  596.59    4985  596.09  4988.3  596.59
  5095.3   596.7  5165.3  597.18  5200.4  597.71  5285.8  599.83  5290.9  599.64
  5308.4  600.21  5349.4   600.5  5395.3  601.66  5452.1  602.83  5554.4  605.51
#Mann= 6 ,-1 , 0
  4598.5      .1       0  4851.2     .12       0  4903.1     .05       0
  4982.3     .03       0  4988.3     .05       0  5395.3      .1       0
Bank Sta=4982.3,4988.3
XS Rating Curve= 0 ,0
Exp/Cntr=0.3,0.1

Type RM Length L Ch R = 1 ,2835    ,484,484,484
BEGIN DESCRIPTION:
UNT 204 IN LACR 6.0
END DESCRIPTION:
XS GIS Cut Line= 3
      2139287.72     13202946.85      2139887.72     13202696.85
      2139887.72     13202096.85
#Sta/Elev= 30
    4350  604.39  4359.2  604.12  4364.6  604.55  4388.5  602.82  4404.2  602.84
  4412.3  602.27  4425.8  602.12  4447.5  601.14  4458.3  601.11  4465.4  600.48
  4489.2  599.81  4494.6  600.29  4518.5   599.3  4523.9  599.47  4547.7  599.16
  4566.1  598.31  4693.8  596.61  4894.9  593.72  4908.5  593.39  4913.9  593.58
  4975.3  593.16  4978.1  592.66  4981.3  593.16  5027.1  593.26    5150  594.67
  5262.9   597.2    5350  599.34    5400  601.26    5440  602.13    5600  606.62
#Mann= 7 ,-1 , 0
    4350      .1       0  4693.8     .05       0  4894.9     .12       0
  4975.3     .07       0  4981.3     .12       0  5027.1      .1       0
  5262.9     .05       0
Bank Sta=4975.3,4981.3
XS Rating Curve= 0 ,0
Exp/Cntr=0.3,0.1

Type RM Length L Ch R = 1 ,2346    ,421,421,421
BEGIN DESCRIPTION:
UNT 204 IN LACR 5.0
END DESCRIPTION:
XS GIS Cut Line= 2
      2139291.01     13203211.37      2140436.84     13203093.31
#Sta/Elev= 30
  4299.6  600.75  4316.4  599.68  4336.5  599.73  4392.1  597.56  4406.9  597.39
    4427   596.4  4491.2  595.11  4517.5  594.14  4537.6  594.11  4547.6  593.62
  4567.7   593.7  4585.2  592.84    4637   592.7  4684.2   591.5    4819  590.67
  4849.2  590.14  4877.3  589.17  4889.4  589.36  4949.7  588.38  4972.5  587.33
  5060.3   587.8  5097.5  587.07  5100.3  586.57  5103.5  587.07  5110.6   587.7
  5130.7  587.66  5170.6  588.57  5269.6  590.58    5382  593.18  5451.5  593.86
#Mann= 7 ,-1 , 0
  4299.6      .1       0    4637     .05       0  4972.5     .12       0
  5097.5     .07       0  5103.5     .12       0  5170.6      .1       0
  5269.6     .05       0
Bank Sta=5097.5,5103.5
XS Rating Curve= 0 ,0
Exp/Cntr=0.3,0.1

Type RM Length L Ch R = 1 ,1936    ,478,478,478
BEGIN DESCRIPTION:
UNT 204 IN LACR 4.0
END DESCRIPTION:
XS GIS Cut Line= 2
      2139534.02     13203641.93      2140499.33     13203447.48
#Sta/Elev= 30
  4491.6   593.3    4526  592.41  4554.8  591.24  4597.9  590.18    4628  589.88
  4643.6  588.94  4648.7  589.13  4668.8  588.17  4709.6   587.3  4892.6  584.35
  4897.7  584.56  4943.4  583.83  4948.5  584.12  4964.6  583.34  4971.8  582.54
  4974.6  582.04  4977.8  582.54    4985  583.38  4991.3  583.27  4999.4  583.69
  5025.8  584.02  5050.2  584.01  5066.6   583.4  5106.8  583.87  5127.8  584.03
  5202.7  585.71  5362.5  590.22  5382.9  590.27  5405.9  590.81  5476.3  590.39
#Mann= 6 ,-1 , 0
  4491.6      .1       0  4554.8     .05       0  4971.8     .07       0
  4977.8     .05       0  4991.3     .12       0  5106.8     .05       0
Bank Sta=4971.8,4977.8
XS Rating Curve= 0 ,0
Exp/Cntr=0.3,0.1

Type RM Length L Ch R = 1 ,1472    ,123,123,123
BEGIN DESCRIPTION:
UNT 204 IN LACR 3.0
END DESCRIPTION:
XS GIS Cut Line= 3
      2139787.76     13204046.85      2140087.72     13203996.85
      2140437.74     13203646.84
#Sta/Elev= 30
  4695.9  589.25  4723.7  587.62  4728.8  587.75  4736.4  587.19  4766.8  585.83
    4777  585.57  4784.6     585  4789.6  585.15  4807.4  584.05  4827.7  583.53
  4845.4  582.42  4850.5  582.56  4858.1  582.02  4878.3  581.15  4906.2  580.29
  4911.3  580.42  4967.1  579.13  4989.9  578.88  4997.5  578.42  5011.1  578.09
  5013.9  577.59  5017.1  578.09  5141.4  579.86  5240.4  581.97  5254.6  582.45
  5268.7  582.55  5325.3  584.42  5339.4  584.69  5410.1  587.26    5495   589.5
#Mann= 3 ,-1 , 0
  4695.9     .05       0  5011.1     .03       0  5017.1     .05       0
Bank Sta=5011.1,5017.1
XS Rating Curve= 0 ,0
Exp/Cntr=0.3,0.1

Type RM Length L Ch R = 1 ,1353    ,339,339,339
BEGIN DESCRIPTION:
Mapping XS d1687b12
END DESCRIPTION:
XS GIS Cut Line= 3
      2139679.88     13204148.87      2140374.34     13204072.48
      2140457.67     13203843.31
#Sta/Elev= 30
  4539.4  595.86  4587.5  594.02  4603.1  592.75    4668  589.79  4728.4  586.58
  4778.7  584.52  4790.1  583.42    4839  581.55  4889.3  579.68  4939.6  578.18
  4972.1  577.53  5027.2  577.39  5029.9  576.89  5033.2  577.39  5080.5  578.05
  5120.7  578.17  5130.8  577.99  5149.1  578.33  5154.1  578.74    5161  578.41
  5181.1  578.12  5237.2   578.6  5297.2  580.21  5307.9  580.26  5339.8  581.36
  5403.6  583.01  5414.3  583.58  5434.2  583.88  5446.2  584.52  5481.9  585.72
#Mann= 3 ,-1 , 0
  4539.4     .05       0  5027.2     .03       0  5033.2     .05       0
Bank Sta=5027.2,5033.2
XS Rating Curve= 0 ,0
Exp/Cntr=0.3,0.1

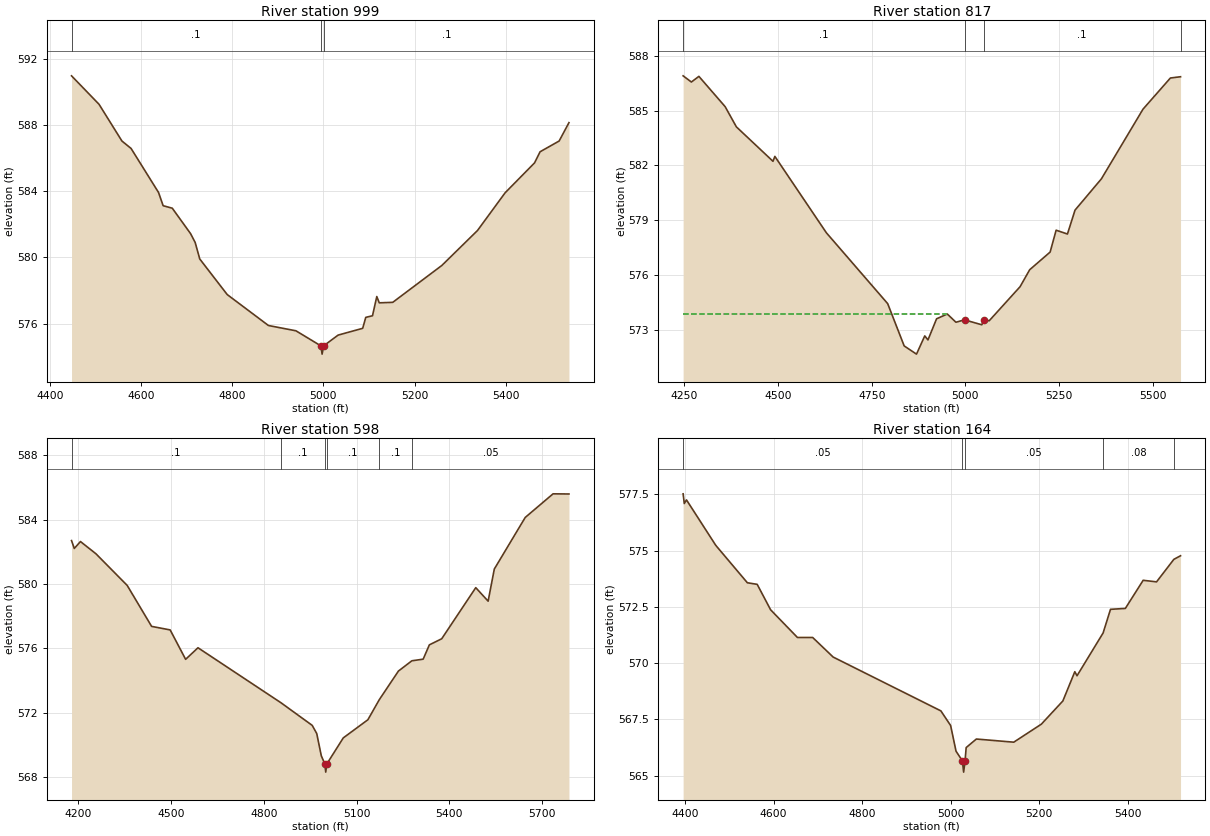
Type RM Length L Ch R = 1 ,999     ,175,175,175
BEGIN DESCRIPTION:
UNT 204 IN LACR 2.0
END DESCRIPTION:
XS GIS Cut Line= 3
      2139787.69     13204346.86      2140337.72     13204296.86
      2140537.71     13203796.87
#Sta/Elev= 30
  4447.7  590.97    4508  589.25  4558.2  587.03  4578.3  586.58  4638.5  583.92
  4648.6  583.12  4668.6  582.97  4708.8  581.43  4718.8   580.9  4728.9   579.9
  4789.1  577.75  4879.5  575.88  4939.8  575.56  4994.5  574.65  4997.2  574.15
  5000.5  574.65  5032.3   575.3  5086.2  575.71  5092.9  576.37  5107.7  576.47
  5117.1  577.63  5122.5  577.25  5152.1  577.28  5259.8  579.51  5337.9  581.62
  5398.5   583.9  5463.1  585.71  5475.2  586.38    5517  587.03  5538.5  588.14
#Mann= 3 , 0 , 0
  4447.7      .1       0  4994.5     .07       0  5000.5      .1       0
Bank Sta=4994.5,5000.5
XS Rating Curve= 0 ,0
Exp/Cntr=0.3,0.1

Type RM Length L Ch R = 1 ,817     ,219,219,219
BEGIN DESCRIPTION:
Mapping XS bdc9d9be
END DESCRIPTION:
XS GIS Cut Line= 4
      2139745.69     13204498.52      2140250.94     13204484.63
      2140532.19     13204356.15      2140596.43     13203847.44
#Sta/Elev= 30
  4246.7  586.92  4268.7  586.58  4288.8  586.89  4358.8  585.23  4388.8  584.12
  4486.5  582.23  4491.5   582.5  4628.9  578.31  4792.6  574.42  4836.6   572.1
  4869.5  571.65  4891.5  572.65  4900.1  572.43  4923.1  573.59  4951.7  573.85
  4974.7   573.4  4997.7  573.53  5043.8  573.26  5049.3  573.54  5063.5  573.48
  5145.9  575.35  5171.5  576.28  5226.1  577.25  5242.1  578.45  5272.3  578.24
  5292.5  579.55    5363  581.27  5473.9  585.09    5547   586.8  5574.1  586.87
#Mann= 4 ,-1 , 0
  4246.7      .1       0  4997.7     .03       0  5049.3      .1       0
  5574.1     .05       0
#XS Ineff= 2 , 0
       0 4950.87  573.87               0
Permanent Ineff=
       T       F
Bank Sta=4997.7,5049.3
XS Rating Curve= 0 ,0
Exp/Cntr=0.3,0.1

Type RM Length L Ch R = 1 ,598     ,450,450,450
BEGIN DESCRIPTION:
Mapping XS 5ef01b26
END DESCRIPTION:
XS GIS Cut Line= 4
      2139738.85     13204677.03      2140372.55      13204694.4
      2140659.01     13204486.06      2140663.35     13203865.41
#Sta/Elev= 30
    4178   582.7  4186.9  582.21  4206.9  582.64  4256.9  581.88    4358  579.91
    4437  577.36    4497  577.14    4547  575.31    4587  576.03  4855.2  572.61
  4956.4   571.2  4971.1  570.69  4985.8  569.31  4997.4  568.79  5000.2  568.29
  5003.4  568.79  5056.9  570.42  5136.5  571.55  5173.4   572.8  5235.3  574.58
  5278.8  575.22  5315.3  575.32  5335.3  576.21  5375.3  576.59  5485.4  579.77
  5525.4  578.93  5545.4  580.93  5645.4  584.14  5735.4  585.61  5786.8   585.6
#Mann= 6 ,-1 , 0
    4178      .1       0  4855.2      .1       0  4997.4     .03       0
  5003.4      .1       0  5173.4      .1       0  5278.8     .05       0
Bank Sta=4997.4,5003.4
XS Rating Curve= 0 ,0
Exp/Cntr=0.3,0.1

Type RM Length L Ch R = 1 ,164     ,0,0,0
BEGIN DESCRIPTION:
UNT 204 IN LACR 1.0
END DESCRIPTION:
XS GIS Cut Line= 4
      2140152.08     13205072.49      2140596.56     13205009.98
      2140853.51     13204891.93      2140902.11     13204503.07
#Sta/Elev= 30
  4395.8  577.52  4398.4  577.09  4403.4  577.25  4469.6  575.23  4540.9  573.57
  4563.1   573.5  4593.4  572.37    4654  571.14  4688.4  571.14  4734.7  570.27
    4978  567.88    5000  567.23  5012.2  566.09  5026.6  565.66  5029.4  565.16
  5032.6  565.66  5035.1  566.25  5058.1  566.63  5142.6  566.49  5204.9  567.29
  5253.5  568.32  5280.5  569.62  5285.5  569.44  5344.4  571.34  5361.1  572.39
  5394.6  572.43  5434.9  573.68  5465.1  573.61  5504.2  574.61  5519.3  574.77
#Mann= 5 ,-1 , 0
  4395.8     .05       0  5026.6     .03       0  5032.6     .05       0
  5344.4     .08       0  5504.2      .1       0
Bank Sta=5026.6,5032.6
XS Rating Curve= 0 ,0
Exp/Cntr=0.3,0.1
Stream Node=UNT 204 IN LACR ,Reach-1         , 0 , 0 ,Upstream end
Stream Node=UNT 204 IN LACR ,Reach-1         , 0 , 1 ,Downstream end

Chan Stop Cuts=-1
Use User Specified Reach Order=0
Composite Channel Slope=5