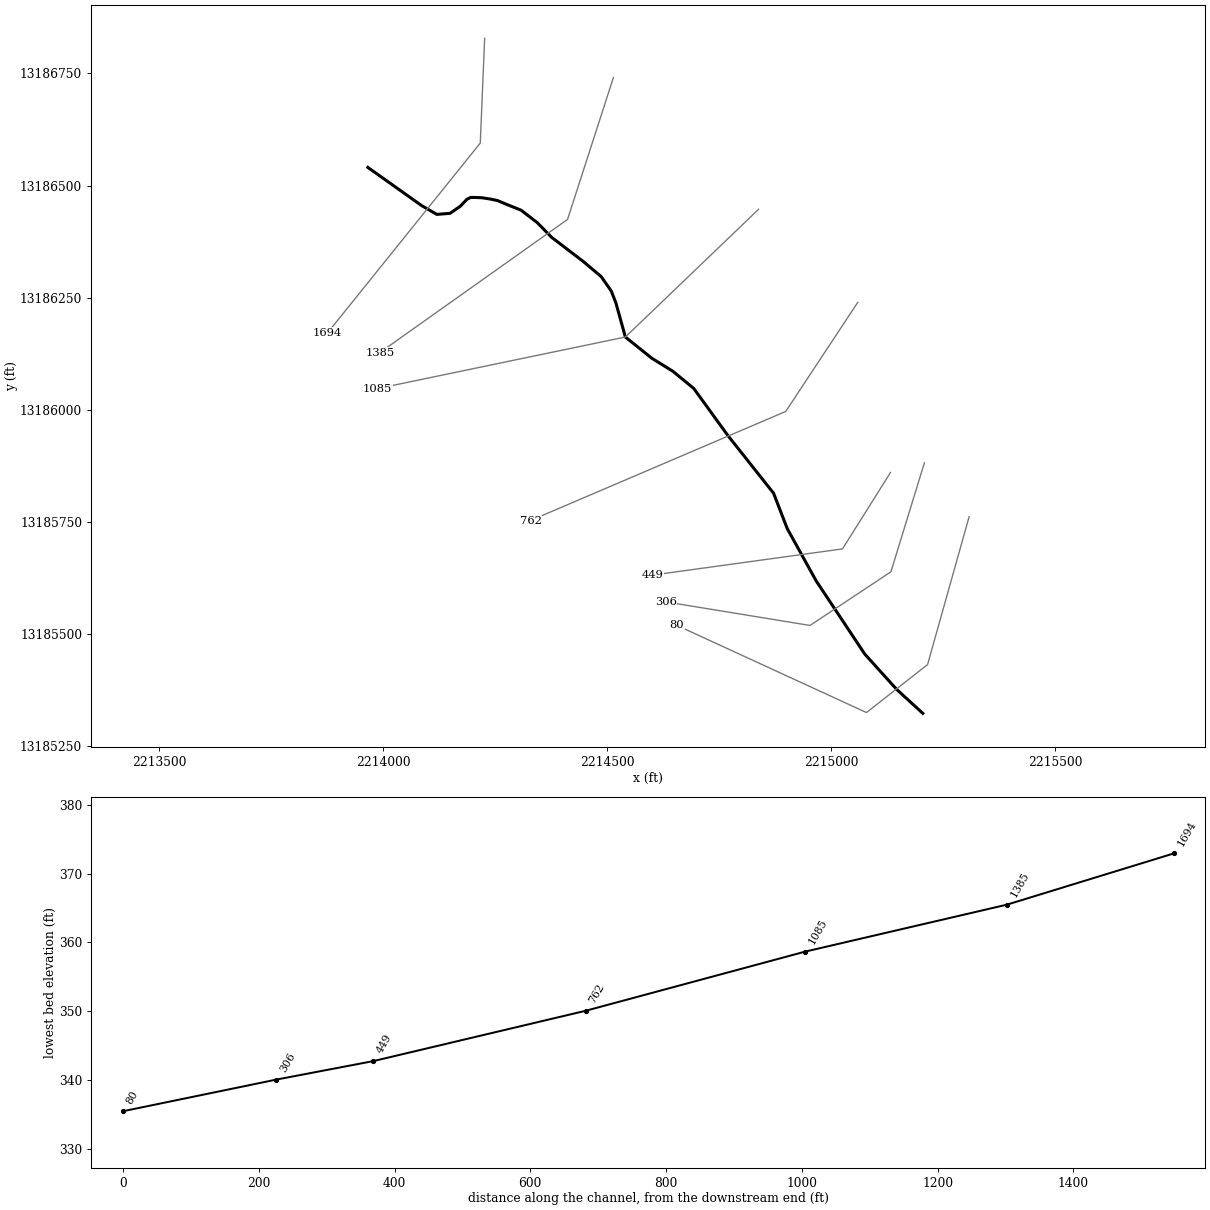
--- UNT 210 IN LACR.prj (project) ---

Proj Title=UNT 210 IN LACR Base Level Engineering
Current Plan=p01
Default Exp/Contr=0.3,0.1
English Units
Geom File=g01
Geom File=g02
Flow File=f01
Plan File=p01
Y Axis Title=Elevation
X Axis Title(PF)=Main Channel Distance
X Axis Title(XS)=Station
BEGIN DESCRIPTION:
UNT 210 IN LACR
END DESCRIPTION:
DSS Export Rating Curves= 0
DSS Export Rating Curve Sorted= 0
DSS Export Volume Flow Curves= 0
DXF OffsetX= 0
DXF OffsetY= 0
DXF ScaleX= 1
DXF ScaleY= 10

--- UNT 210 IN LACR.p01 (plan) ---

Plan Title=Multiple Run
Short Identifier=Multiple
Geom File=g01
Flow File=f01
Subcritical Flow
K Sum by GR= 0
Std Step Tol= 0.01
Critical Tol= 0.01
Num of Std Step Trials= 20
Max Error Tol= 0.3
Flow Tol Ratio= 0.001
Split Flow NTrial= 30
Split Flow Tol= 0.02
Split Flow Ratio= 0.02
Log Output Level= 0
Friction Slope Method= 1
Unsteady Friction Slope Method= 2
Unsteady Bridges Friction Slope Method= 1
Parabolic Critical Depth
Global Vel Dist=  1 , 1 , 1
Global Log Level= 0
CheckData=True
Encroach Param= -1, 0, 0, 0
BEGIN DESCRIPTION:
Multiple Run
END DESCRIPTION:

--- UNT 210 IN LACR.f01 (steady flow) ---

Flow Title=Multiple
Program Version=4.10
Number of Profiles= 7
Profile Names=10-year,25-year,50-year,1pct_min,100-year,1pct_plu,500-year
River Rch & RM=UNT 210 IN LACR,Reach-1         ,1694
      42      53      61      53      71      96      97
Boundary for River Rch & Prof#=UNT 210 IN LACR,Reach-1         , 1
Up Type= 0
Dn Type= 3
Dn Slope=0.005
Boundary for River Rch & Prof#=UNT 210 IN LACR,Reach-1         , 2
Up Type= 0
Dn Type= 3
Dn Slope=0.005
Boundary for River Rch & Prof#=UNT 210 IN LACR,Reach-1         , 3
Up Type= 0
Dn Type= 3
Dn Slope=0.005
Boundary for River Rch & Prof#=UNT 210 IN LACR,Reach-1         , 4
Up Type= 0
Dn Type= 3
Dn Slope=0.005
Boundary for River Rch & Prof#=UNT 210 IN LACR,Reach-1         , 5
Up Type= 0
Dn Type= 3
Dn Slope=0.005
Boundary for River Rch & Prof#=UNT 210 IN LACR,Reach-1         , 6
Up Type= 0
Dn Type= 3
Dn Slope=0.005
Boundary for River Rch & Prof#=UNT 210 IN LACR,Reach-1         , 7
Up Type= 0
Dn Type= 3
Dn Slope=0.005
DSS Import GetInterval= 0
DSS Import GetPeak= 0
DSS Import FillOption= 0

--- UNT 210 IN LACR.g01 (geometry) ---

Geom Title=Existing Conditions
Program Version=4.10

River Reach=UNT 210 IN LACR ,Reach-1
Reach XY= 30
      2213965.88     13186540.32      2214085.67     13186455.25
      2214119.72     13186435.48      2214149.42     13186437.98
      2214172.34     13186453.95      2214186.92     13186469.23
      2214195.25     13186473.39      2214203.59     13186473.39
      2214220.25      13186472.7      2214238.31     13186469.92
      2214254.98     13186466.45      2214275.67     13186457.76
      2214307.75     13186444.92      2214343.87     13186417.14
      2214375.81      13186384.5      2214446.64     13186330.34
      2214486.23       13186297.      2214509.14     13186264.37
      2214519.56     13186237.28      2214540.53     13186161.85
      2214599.43     13186114.55       2214646.6     13186085.39
      2214693.12     13186047.06      2214769.11     13185942.24
      2214871.32     13185813.17      2214901.78     13185734.23
      2214966.32     13185617.61       2215074.8     13185454.23
      2215146.33     13185375.06      2215204.39     13185321.89

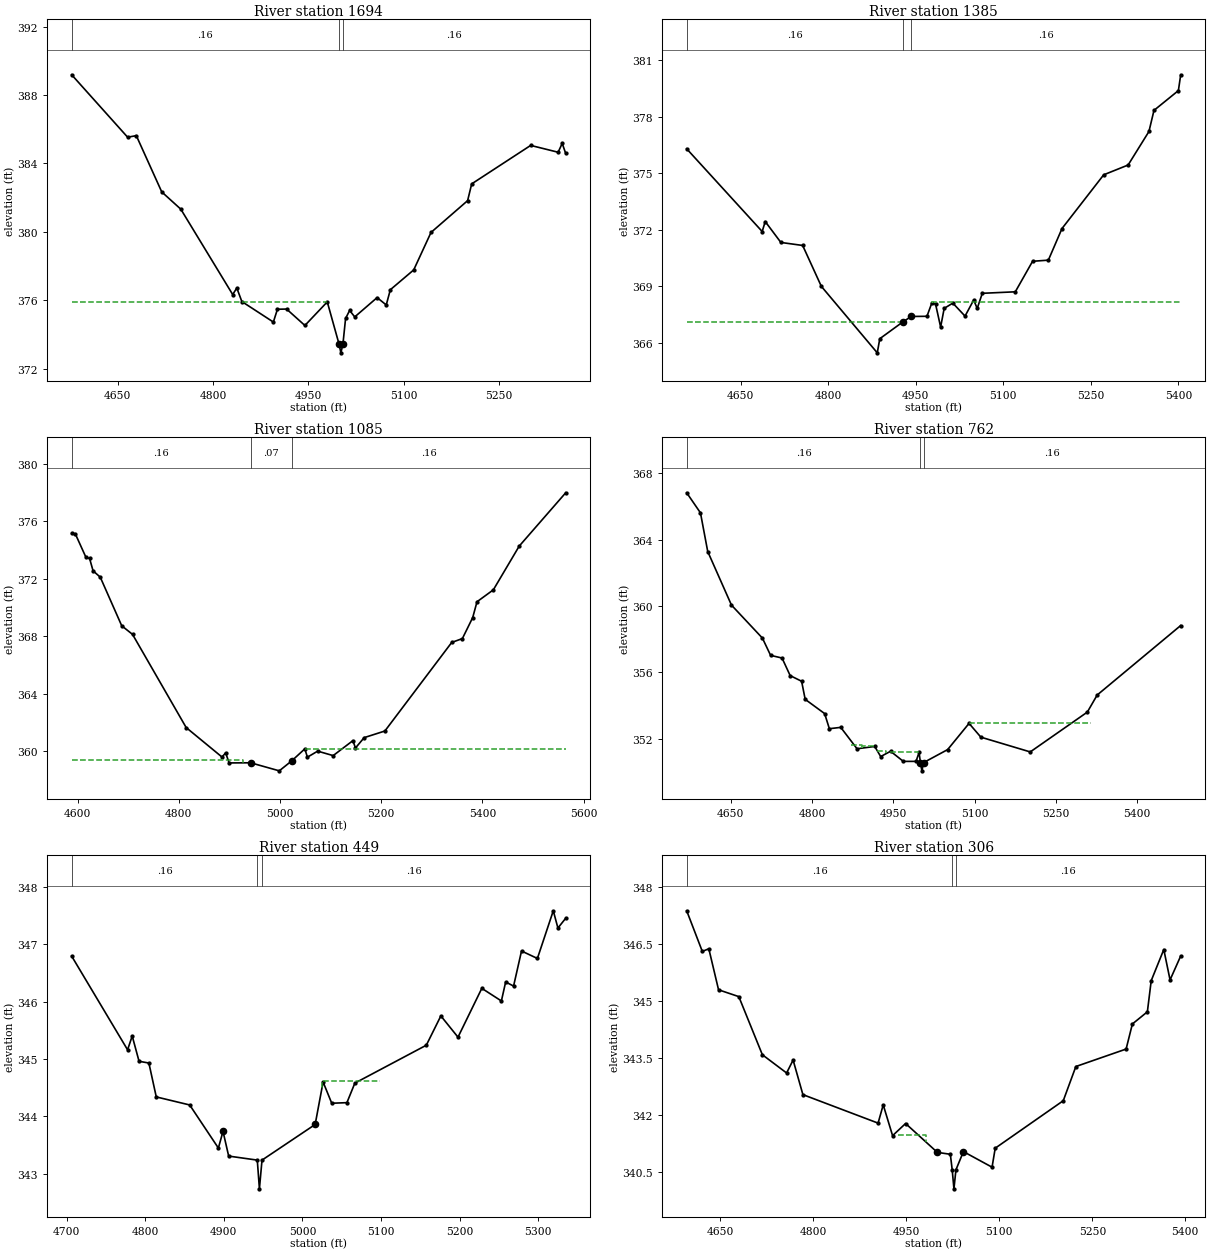
Type RM Length L Ch R = 1 ,1694    ,246,246,246
BEGIN DESCRIPTION:
UNT 210 IN LACR 3.0
END DESCRIPTION:
XS GIS Cut Line= 3
      2214226.44     13186828.46       2214216.7     13186594.74
      2213876.13     13186171.46
#Sta/Elev= 30
  4577.5  389.18  4665.5  385.53  4679.2  385.62  4719.2  382.33  4749.2  381.32
  4830.8  376.33  4837.3  376.71  4845.2  375.92  4894.8  374.72  4901.2  375.47
  4915.6  375.48  4944.4  374.52  4979.6   375.9  4998.2  373.42    5001  372.92
  5004.2  373.42  5008.4  374.93  5014.8   375.4  5022.8  375.02    5058  376.15
  5072.4  375.72  5078.8  376.61  5115.6  377.77  5142.8  379.96  5200.4  381.82
  5206.8   382.8  5299.6  385.05  5342.8  384.65  5349.2  385.17  5354.7  384.58
#Mann= 3 ,-1 , 0
  4577.5     .16       0  4998.2     .07       0  5004.2     .16       0
#XS Ineff= 2 , 0
       0 4979.57  375.92               0
Permanent Ineff=
       T       F
Bank Sta=4998.2,5004.2
XS Rating Curve= 0 ,0
Exp/Cntr=0.3,0.1

Type RM Length L Ch R = 1 ,1385    ,297,297,297
BEGIN DESCRIPTION:
Mapping XS 3e3a3d23
END DESCRIPTION:
XS GIS Cut Line= 3
      2214513.76     13186740.85      2214411.49      13186424.3
       2213992.7     13186127.25
#Sta/Elev= 30
  4557.7   376.3    4687  371.91  4692.2  372.44    4719  371.33  4756.3  371.17
  4788.3     369  4884.1  365.47  4888.4  366.22  4927.4   367.1  4942.2   367.4
  4969.2  367.41  4977.8  368.14    4984  368.05  4992.6  366.84  4998.7  367.83
  5013.5  368.11  5034.4  367.42  5049.2  368.27  5055.3  367.83    5064  368.63
  5120.5  368.71  5150.1  370.33  5177.1  370.39  5200.5  372.07  5271.9  374.92
  5313.7  375.44  5349.4  377.22    5358  378.34  5399.8  379.39  5403.8  380.23
#Mann= 3 , 0 , 0
  4557.7     .16       0  4927.4     .07       0  4942.2     .16       0
#XS Ineff= 2 , 0
       0 4927.09   367.1 4977.57       0  368.16
Permanent Ineff=
       T       T
Bank Sta=4927.4,4942.2
XS Rating Curve= 0 ,0
Exp/Cntr=0.3,0.1

Type RM Length L Ch R = 1 ,1085    ,323,323,323
BEGIN DESCRIPTION:
UNT 210 IN LACR 2.0
END DESCRIPTION:
XS GIS Cut Line= 3
      2214837.74     13186446.88      2214540.53     13186161.85
      2213987.76     13186046.86
#Sta/Elev= 30
  4588.2  375.16  4595.3  375.14  4616.4   373.5  4623.6  373.42  4630.5  372.56
  4644.7  372.12  4687.1  368.74  4708.5  368.14  4814.5  361.66  4885.3  359.61
  4892.5   359.9  4899.4   359.2  4941.9  359.21  4998.5  358.65  5023.3  359.35
    5049  360.18  5054.1   359.6  5074.4  360.02    5105  359.71    5144  360.75
  5149.1  360.24  5166.3  360.96  5207.2  361.42  5339.3  367.58  5360.4  367.85
  5380.8  369.31  5389.3  370.41  5421.6  371.24  5472.7  374.28  5564.6  377.99
#Mann= 3 , 0 , 0
  4588.2     .16       0  4941.9     .07       0  5023.3     .16       0
#XS Ineff= 2 , 0
       0 4927.69  359.38 5048.75       0  360.19
Permanent Ineff=
       T       T
Bank Sta=4941.9,5023.3
XS Rating Curve= 0 ,0
Exp/Cntr=0.3,0.1

Type RM Length L Ch R = 1 ,762     ,313,313,313
BEGIN DESCRIPTION:
Mapping XS 474a6f4b
END DESCRIPTION:
XS GIS Cut Line= 3
      2215059.18     13186239.27      2214898.46     13185995.76
      2214328.67     13185752.26
#Sta/Elev= 30
  4568.7  366.82  4594.1  365.61  4607.5  363.28  4651.3  360.05  4708.4  358.06
  4723.5  357.02  4744.6  356.86  4759.6   355.8  4780.7  355.46  4787.3  354.37
  4823.2  353.51  4831.9   352.6  4852.9  352.68    4883  351.39  4915.6  351.53
  4926.6  350.92  4944.8  351.24  4968.4  350.63  4991.8  350.63  4997.4  351.17
  4999.9  350.56  5002.6  350.06  5005.9  350.56  5050.1  351.34  5089.6  352.92
  5111.4  352.09  5202.5   351.2  5307.8   353.6    5326  354.63  5480.1  358.82
#Mann= 3 ,-1 , 0
  4568.7     .16       0  4999.9     .07       0  5005.9     .16       0
#XS Ineff= 5 ,-1
 4871.31 4892.02  351.63 4892.02 4915.51  351.54 4918.91 4937.14  351.27
 4943.94 4997.41  351.17 5091.16 5314.92  352.94
Permanent Ineff=
       T       T       T       T       T
Bank Sta=4999.9,5005.9
XS Rating Curve= 0 ,0
Exp/Cntr=0.3,0.1

Type RM Length L Ch R = 1 ,449     ,143,143,143
BEGIN DESCRIPTION:
Mapping XS 93cbabd8
END DESCRIPTION:
XS GIS Cut Line= 3
      2215132.23     13185859.44      2215025.07     13185688.97
      2214602.04     13185630.62
#Sta/Elev= 30
  4706.5  346.79  4777.6  345.16  4783.5   345.4  4792.2  344.96  4804.7  344.93
  4814.1  344.34  4856.6   344.2  4893.1  343.45    4899  343.74  4906.2  343.31
  4942.6  343.24  4945.3  342.74  4948.6  343.24  5016.2  343.86  5026.3   344.6
  5037.3  344.23  5056.6  344.24  5066.7  344.58  5157.6  345.24  5176.1  345.75
  5197.9  345.38  5228.2  346.23  5253.1  346.01  5258.5  346.34  5268.6  346.27
  5278.7  346.88  5298.9  346.75  5319.1  347.58    5325  347.28  5334.9  347.45
#Mann= 3 ,-1 , 0
  4706.5     .16       0  4942.6     .07       0  4948.6     .16       0
#XS Ineff= 2 ,-1
  4706.5 4855.66   344.2 5024.86 5098.34  344.62
Permanent Ineff=
       T       T
Bank Sta=4899,5016.2
XS Rating Curve= 0 ,0
Exp/Cntr=0.3,0.1

Type RM Length L Ch R = 1 ,306     ,226,226,226
BEGIN DESCRIPTION:
Mapping XS 4034b8a2
END DESCRIPTION:
XS GIS Cut Line= 4
      2215207.83     13185880.96      2215133.17     13185637.89
      2214952.61      13185518.1      2214630.75     13185570.73
#Sta/Elev= 30
  4595.5  347.37  4620.7   346.3  4631.2  346.37  4646.9  345.29  4679.6  345.11
  4717.6  343.58  4756.7   343.1  4767.2  343.44    4783  342.53  4904.3  341.78
  4912.6  342.26  4927.7  341.45  4948.7  341.77  4999.9  341.01  5020.9  340.96
  5023.9  340.55  5026.7  340.05  5029.9  340.55    5042  341.03  5088.2  340.62
  5093.3  341.12  5203.1  342.37  5223.4  343.27  5304.5  343.73  5314.6  344.39
  5338.8  344.71    5345  345.53  5365.3  346.35  5375.4  345.55  5392.6  346.18
#Mann= 3 ,-1 , 0
  4595.5     .16       0  5023.9     .07       0  5029.9     .16       0
#XS Ineff= 2 ,-1
 4935.91 4981.49  341.47 5042.05 5113.64  341.01
Permanent Ineff=
       T       T
Bank Sta=4999.9,5042
XS Rating Curve= 0 ,0
Exp/Cntr=0.3,0.1

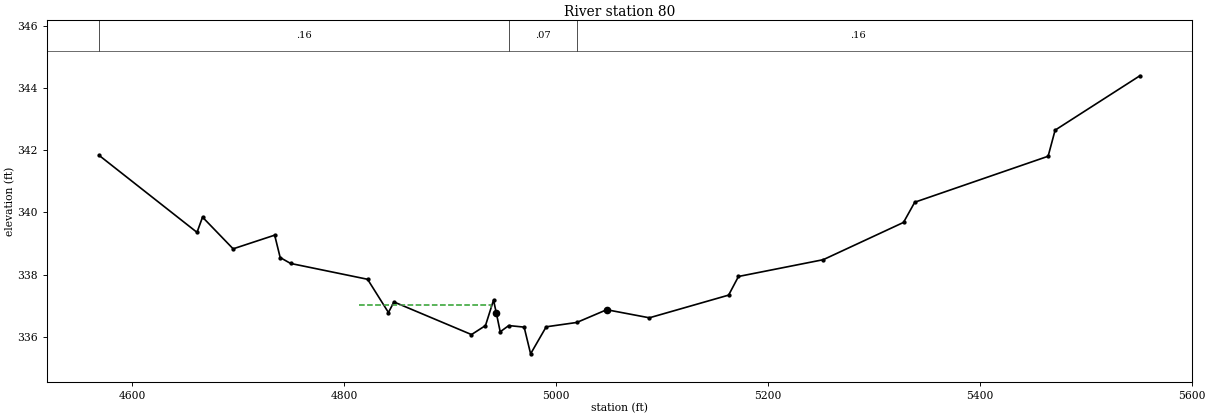
Type RM Length L Ch R = 1 ,80      ,0,0,0
BEGIN DESCRIPTION:
UNT 210 IN LACR 1.0
END DESCRIPTION:
XS GIS Cut Line= 4
      2215307.76     13185760.91      2215214.99     13185430.87
      2215078.64     13185323.74        2214655.     13185518.51
#Sta/Elev= 30
  4568.6  341.84  4661.1  339.36  4666.3  339.85  4695.2  338.83  4734.4  339.27
  4739.6  338.55  4749.4  338.36  4822.1  337.85  4841.8  336.78    4847  337.12
  4920.2  336.07  4933.4  336.36    4941  337.18 4943.65  336.76  4947.3  336.16
  4955.4  336.36  4969.9  336.31    4976  335.45  4990.7  336.32  5019.6  336.46
  5047.8  336.87  5088.1  336.61  5162.9  337.34  5172.2  337.94  5252.2  338.48
    5328  339.68  5338.6  340.33  5464.5  341.81  5471.1  342.65  5551.1   344.4
#Mann= 3 ,-1 , 0
  4568.6     .16       0  4955.4     .07       0  5019.6     .16       0
#XS Ineff= 1 ,-1
 4814.36 4938.67  337.02
Permanent Ineff=
       T
Bank Sta=4943.65,5047.8
XS Rating Curve= 0 ,0
Exp/Cntr=0.3,0.1

Chan Stop Cuts=-1
Use User Specified Reach Order=0
Composite Channel Slope=5

--- UNT 210 IN LACR.g02 (geometry) ---

Geom Title=Dummy
Program Version=4.10

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
River Reach=UNT 210 IN LACR ,Reach-1
Reach XY= 10
      2213965.88     13186540.32      2214139.49       13186424.
      2214248.86     13186410.11      2214372.13     13186326.78
      2214540.53     13186161.85      2214728.49     13185999.57
      2214871.32     13185813.17      2214966.32     13185617.61
      2215112.09     13185412.95      2215237.72     13185296.85

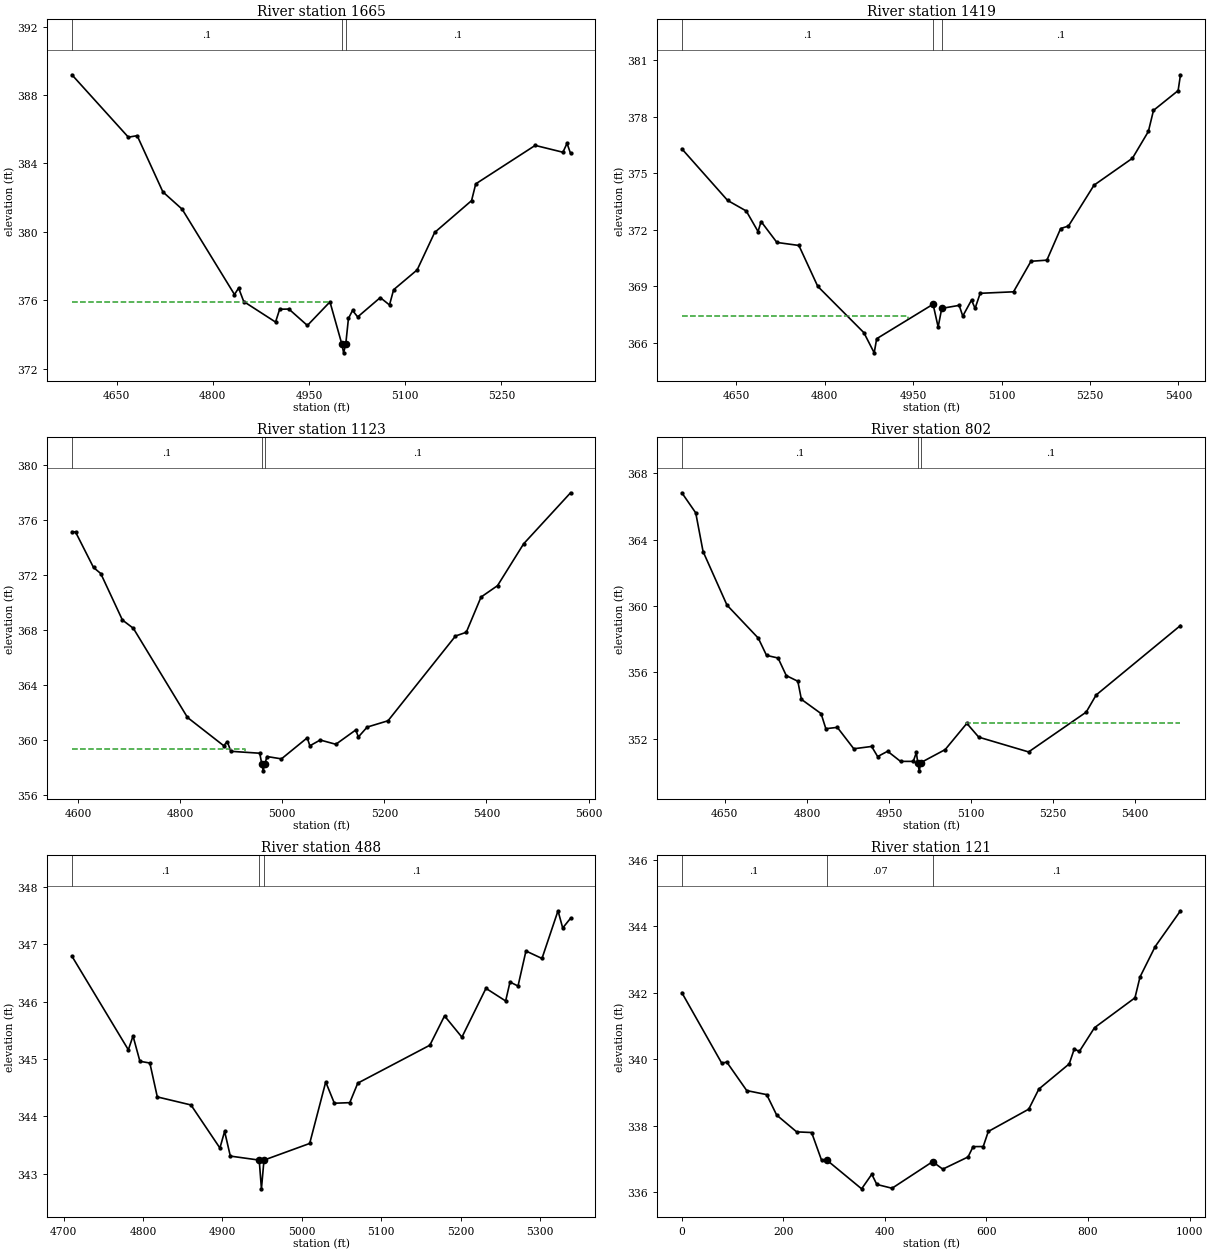
Type RM Length L Ch R = 1 ,1665    ,246,246,246
BEGIN DESCRIPTION:
UNT 210 IN LACR 3.0
END DESCRIPTION:
XS GIS Cut Line= 3
      2214226.44     13186828.51       2214216.7     13186594.74
      2213876.16      13186171.5
#Sta/Elev= 30
  4580.5  389.18  4668.5  385.53  4682.2  385.62  4722.3  382.33  4752.3  381.32
  4833.9  376.33  4840.3  376.71  4848.3  375.92  4897.9  374.72  4904.3  375.47
  4918.7  375.48  4947.5  374.52  4982.7   375.9  5001.3  373.42    5004  372.92
  5007.3  373.42  5011.5  374.93  5017.9   375.4  5025.9  375.02  5061.1  376.15
  5075.5  375.72  5081.9  376.61  5118.6  377.77  5145.9  379.96  5203.4  381.82
  5209.9   382.8  5302.6  385.05  5345.8  384.65  5352.2  385.17  5357.7  384.58
#Mann= 3 ,-1 , 0
  4580.5      .1       0  5001.3     .07       0  5007.3      .1       0
#XS Ineff= 2 , 0
         4982.95  375.87
Permanent Ineff=
       F       F
Bank Sta=5001.3,5007.3
XS Rating Curve= 0 ,0
Exp/Cntr=0.3,0.1

Type RM Length L Ch R = 1 ,1419    ,296,296,296
BEGIN DESCRIPTION:
Mapping XS 3e3a3d23
END DESCRIPTION:
XS GIS Cut Line= 3
      2214513.75     13186740.84      2214411.49      13186424.3
      2213992.69     13186127.25
#Sta/Elev= 30
  4557.5   376.3  4635.2  373.56  4666.8     373  4686.8  371.91    4692  372.44
  4718.8  371.33  4756.1  371.17  4788.1     369  4866.4  366.54  4883.9  365.47
  4888.1  366.22  4983.8  368.05  4992.4  366.84  4998.5  367.83  5028.1  367.99
  5034.2  367.42    5049  368.27  5055.1  367.83  5063.7  368.63  5120.3  368.71
  5149.9  370.33  5176.9  370.39  5200.3  372.07  5213.5   372.2  5256.9  374.37
  5322.1   375.8  5349.1  377.22  5357.8  378.34  5399.6  379.39  5403.6  380.23
#Mann= 3 , 0 , 0
  4557.5      .1       0  4983.8     .07       0  4998.5      .1       0
#XS Ineff= 2 , 0
         4941.91  367.41
Permanent Ineff=
       F       F
Bank Sta=4983.8,4998.5
XS Rating Curve= 0 ,0
Exp/Cntr=0.3,0.1

Type RM Length L Ch R = 1 ,1123    ,321,321,321
BEGIN DESCRIPTION:
UNT 210 IN LACR 2.0
END DESCRIPTION:
XS GIS Cut Line= 3
      2214837.74     13186446.88      2214540.53     13186161.85
      2213987.76     13186046.86
#Sta/Elev= 30
  4588.2  375.16  4595.3  375.14  4630.5  372.56  4644.7  372.12  4687.1  368.74
  4708.5  368.14  4814.5  361.66  4885.3  359.61  4892.5   359.9  4899.4   359.2
    4956  359.06    4960  358.28  4962.7  357.78    4966  358.28  4970.2  358.82
  4998.5  358.65    5049  360.18  5054.1   359.6  5074.4  360.02    5105  359.71
    5144  360.75  5149.1  360.24  5166.3  360.96  5207.2  361.42  5339.3  367.58
  5360.4  367.85  5389.3  370.41  5421.6  371.24  5472.7  374.28  5564.6  377.99
#Mann= 3 ,-1 , 0
  4588.2      .1       0    4960     .07       0    4966      .1       0
#XS Ineff= 2 , 0
         4927.75  359.38
Permanent Ineff=
       F       F
Bank Sta=4960,4966
XS Rating Curve= 0 ,0
Exp/Cntr=0.3,0.1

Type RM Length L Ch R = 1 ,802     ,314,314,314
BEGIN DESCRIPTION:
Mapping XS 474a6f4b
END DESCRIPTION:
XS GIS Cut Line= 3
      2215059.17     13186239.26      2214898.46     13185995.76
      2214328.66     13185752.26
#Sta/Elev= 30
  4571.4  366.82  4596.8  365.61  4610.2  363.28  4653.9  360.05  4711.1  358.06
  4726.2  357.02  4747.3  356.86  4762.3   355.8  4783.4  355.46  4789.9  354.37
  4825.9  353.51  4834.6   352.6  4855.6  352.68  4885.7  351.39  4918.3  351.53
  4929.3  350.92  4947.5  351.24  4971.1  350.63  4994.4  350.63  5000.1  351.17
  5002.5  350.56  5005.3  350.06  5008.5  350.56  5052.7  351.34  5092.3  352.92
  5114.1  352.09  5205.2   351.2  5310.5   353.6  5328.6  354.63  5482.8  358.82
#Mann= 3 ,-1 , 0
  4571.4      .1       0  5002.5     .07       0  5008.5      .1       0
#XS Ineff= 2 , 0
                         5091.36          352.93
Permanent Ineff=
       F       F
Bank Sta=5002.5,5008.5
XS Rating Curve= 0 ,0
Exp/Cntr=0.3,0.1

Type RM Length L Ch R = 1 ,488     ,367,367,367
BEGIN DESCRIPTION:
Mapping XS 93cbabd8
END DESCRIPTION:
XS GIS Cut Line= 3
      2215132.21     13185859.41      2215025.07     13185688.97
      2214602.09     13185630.63
#Sta/Elev= 30
  4710.3  346.79  4781.4  345.16  4787.3   345.4    4796  344.96  4808.5  344.93
  4817.9  344.34  4860.3   344.2  4896.8  343.45  4902.7  343.74  4909.9  343.31
  4946.3  343.24  4949.1  342.74  4952.3  343.24  5009.9  343.53  5030.1   344.6
    5041  344.23  5060.4  344.24  5070.5  344.58  5161.3  345.24  5179.8  345.75
  5201.7  345.38    5232  346.23  5256.8  346.01  5262.3  346.34  5272.4  346.27
  5282.4  346.88  5302.6  346.75  5322.8  347.58  5328.7  347.28  5338.6  347.45
#Mann= 3 ,-1 , 0
  4710.3      .1       0  4946.3     .07       0  4952.3      .1       0
Bank Sta=4946.3,4952.3
XS Rating Curve= 0 ,0
Exp/Cntr=0.3,0.1

Type RM Length L Ch R = 1 ,121     ,0,0,0
BEGIN DESCRIPTION:
UNT 210 IN LACR 1.0
END DESCRIPTION:
XS GIS Cut Line= 2
 2218164.662758613189363.54268472217575.3384917213188577.8218145
#Sta/Elev= 30
       0342.007478.66209339.884988.49486 339.921127.8259339.0629 167.157338.9412
186.8225338.3261226.1535337.8218255.6518337.8022275.3173336.9652285.1501336.9788
354.1348336.1092374.1111336.5477384.0993 336.241414.0638336.1269 493.969336.9256
513.9453336.7009563.7573337.0678573.7197337.3786593.6444337.3804603.6068337.8333
683.3059338.5046703.2307 339.109763.0051339.8654772.9674340.3142782.9298 340.238
 812.817340.9529892.5161341.8512902.4785342.4791932.3657343.3931982.1776 344.468
#Mann= 3 ,-1 , 0
       0      .1       0285.1501     .07       0 493.969      .1       0
Bank Sta=285.1501,493.969
XS Rating Curve= 0 ,0
Exp/Cntr=0.3,0.1