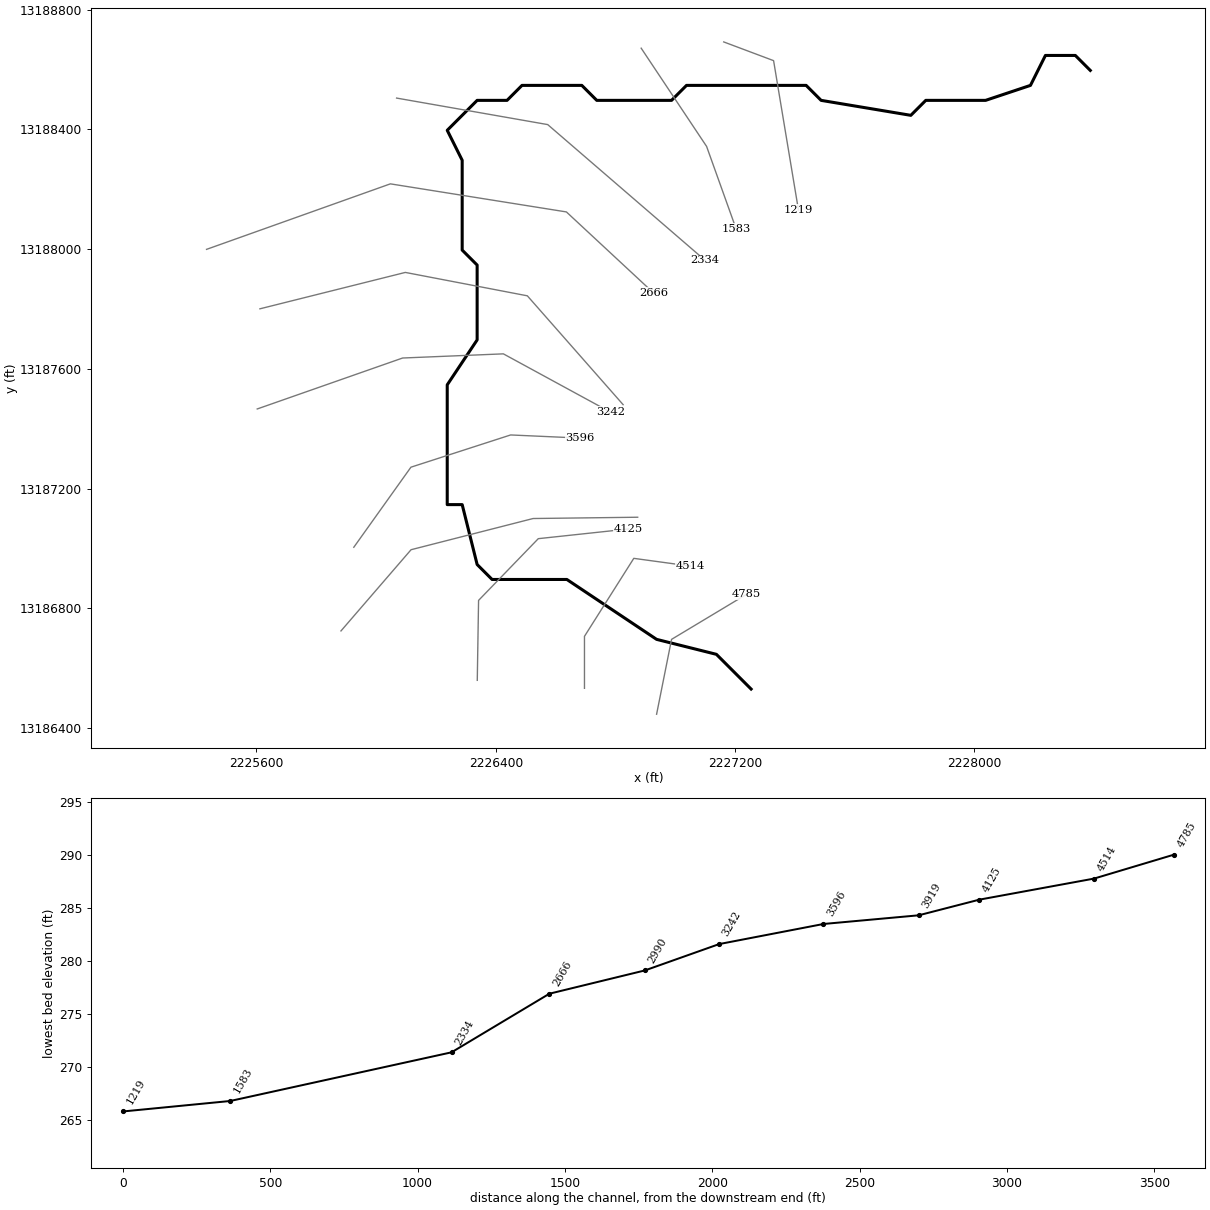
--- WILLIE TANK CREEK.prj (project) ---

Proj Title=WILLIE TANK CREEK Base Level Engineering
Current Plan=p01
Default Exp/Contr=0.3,0.1
English Units
Geom File=g01
Flow File=f01
Plan File=p01
Y Axis Title=Elevation
X Axis Title(PF)=Main Channel Distance
X Axis Title(XS)=Station
BEGIN DESCRIPTION:
WILLIE TANK CREEK
END DESCRIPTION:
DSS Export Rating Curves= 0
DSS Export Rating Curve Sorted= 0
DSS Export Volume Flow Curves= 0
DXF OffsetX= 0
DXF OffsetY= 0
DXF ScaleX= 1
DXF ScaleY= 10

--- WILLIE TANK CREEK.p01 (plan) ---

Plan Title=Multiple Run
Short Identifier=Multiple
Geom File=g01
Flow File=f01
Subcritical Flow
K Sum by GR= 0
Std Step Tol= 0.01
Critical Tol= 0.01
Num of Std Step Trials= 20
Max Error Tol= 0.3
Flow Tol Ratio= 0.001
Split Flow NTrial= 30
Split Flow Tol= 0.02
Split Flow Ratio= 0.02
Log Output Level= 0
Friction Slope Method= 1
Unsteady Friction Slope Method= 2
Unsteady Bridges Friction Slope Method= 1
Parabolic Critical Depth
Global Vel Dist=  1 , 1 , 1
Global Log Level= 0
CheckData=True
Encroach Param= -1, 0, 0, 0
BEGIN DESCRIPTION:
Multiple Run
END DESCRIPTION:

--- WILLIE TANK CREEK.f01 (steady flow) ---

Flow Title=Multiple
Number of Profiles=7
Profile Names=10-year,25-year,50-year,1pct_min,100-year,1pct_plu,500-year
River Rch & RM= WILLIE TANK CREE,Reach-1,4785
     132     177     213     189     256     346     375
River Rch & RM= WILLIE TANK CREE,Reach-1,3919
     259     362     449     410     554     749     857
River Rch & RM= WILLIE TANK CREE,Reach-1,2334
     270     378     469     428     578     782     894
Boundary for River Rch & Prof#=WILLIE TANK CREE,Reach-1,1
Up Type=0
Dn Type=3
Dn Slope=0.005
Boundary for River Rch & Prof#=WILLIE TANK CREE,Reach-1,2
Up Type=0
Dn Type=3
Dn Slope=0.005
Boundary for River Rch & Prof#=WILLIE TANK CREE,Reach-1,3
Up Type=0
Dn Type=3
Dn Slope=0.005
Boundary for River Rch & Prof#=WILLIE TANK CREE,Reach-1,4
Up Type=0
Dn Type=3
Dn Slope=0.005
Boundary for River Rch & Prof#=WILLIE TANK CREE,Reach-1,5
Up Type=0
Dn Type=3
Dn Slope=0.005
Boundary for River Rch & Prof#=WILLIE TANK CREE,Reach-1,6
Up Type=0
Dn Type=3
Dn Slope=0.005
Boundary for River Rch & Prof#=WILLIE TANK CREE,Reach-1,7
Up Type=0
Dn Type=3
Dn Slope=0.005

--- WILLIE TANK CREEK.g01 (geometry) ---

Geom Title=Existing Conditions
Program Version=4.10

River Reach=WILLIE TANK CREE,Reach-1
Reach XY= 30
      2227253.67     13186530.91      2227137.72     13186646.85
      2226937.72     13186696.85      2226637.72     13186896.86
      2226387.72     13186896.86      2226337.72     13186946.85
      2226287.72     13187146.85      2226237.72     13187146.85
      2226237.72     13187546.86      2226337.72     13187696.85
      2226337.72     13187946.85      2226287.72     13187996.85
      2226287.72     13188296.85      2226237.72     13188396.86
      2226337.72     13188496.85      2226437.72     13188496.85
      2226487.72     13188546.86      2226687.72     13188546.86
      2226737.72     13188496.85      2226987.72     13188496.85
      2227037.72     13188546.86      2227437.72     13188546.86
      2227487.72     13188496.85      2227787.72     13188446.85
      2227837.72     13188496.85      2228037.72     13188496.85
      2228187.72     13188546.86      2228237.72     13188646.85
      2228337.72     13188646.85      2228387.72     13188596.85

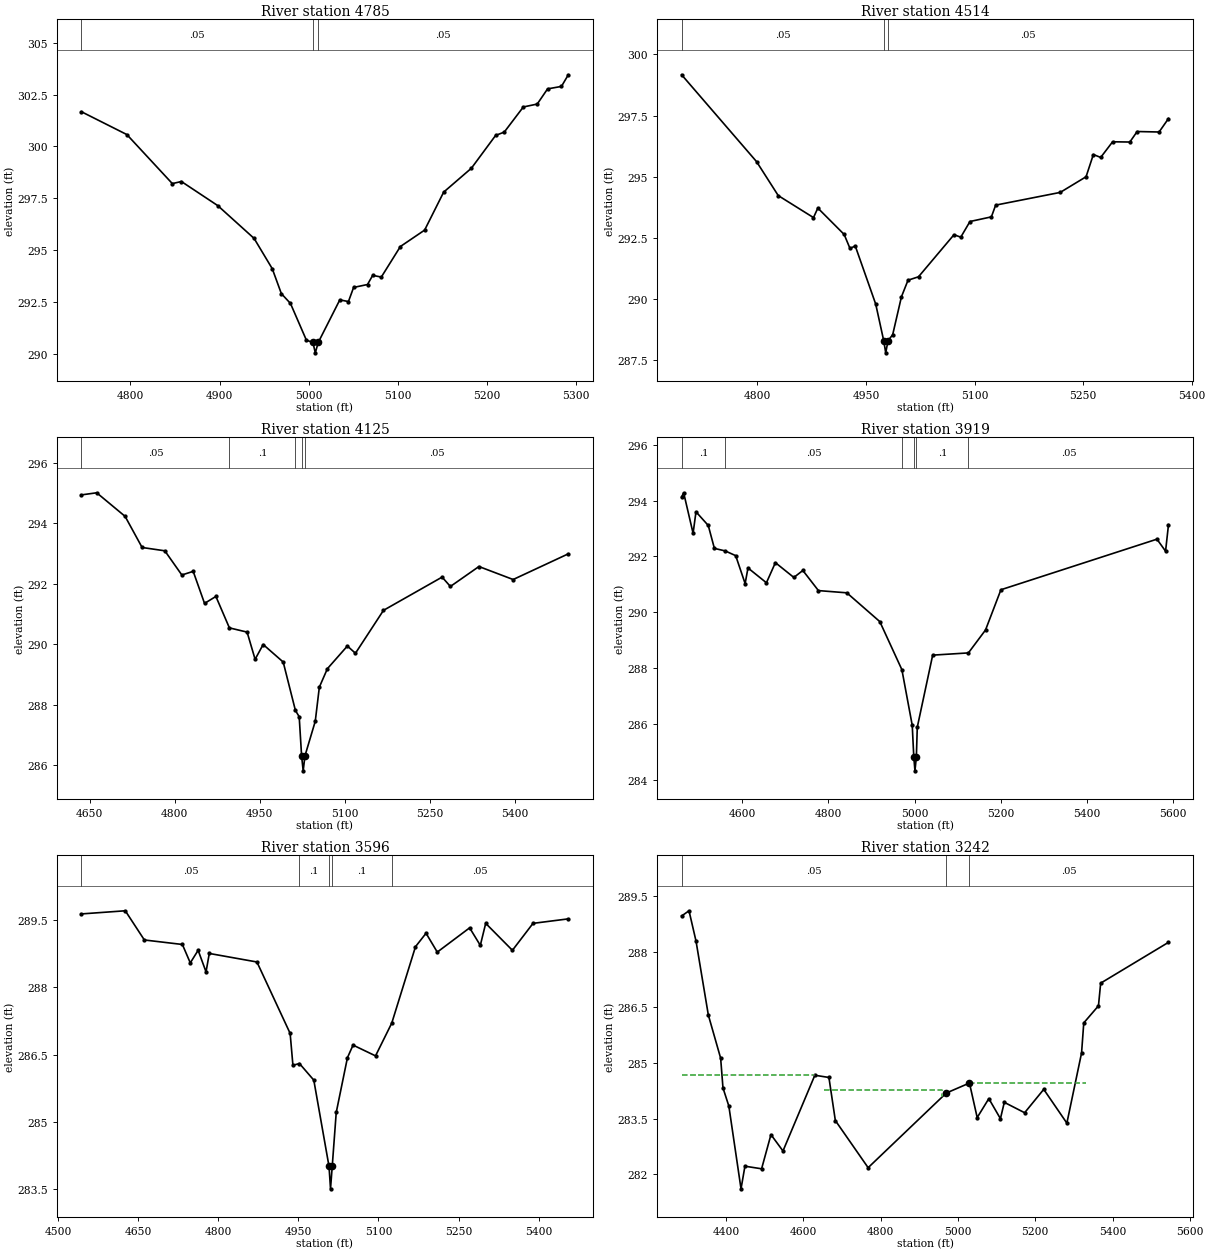
Type RM Length L Ch R = 1 ,4785    ,271,271,271
BEGIN DESCRIPTION:
WILLIE TANK CREEK 2.0
END DESCRIPTION:
XS GIS Cut Line= 3
      2226937.71     13186446.81      2226987.72     13186696.85
      2227237.68     13186846.83
#Sta/Elev= 30
    4745  301.67    4796  300.57    4847  298.21  4857.2  298.31    4898  297.15
  4938.8  295.57  4959.2  294.11  4969.4  292.91  4979.6  292.44  4997.5  290.67
  5004.8  290.56  5007.5  290.06  5010.8  290.56    5035  292.61  5044.7  292.53
  5050.5  293.21  5066.1  293.35  5071.9  293.79  5081.6  293.71    5103  295.18
  5130.2  295.97  5151.6   297.8  5182.7  298.95  5209.9  300.53  5219.6  300.69
    5241   301.9  5256.6  302.04  5268.2  302.77  5283.8  302.89  5291.5  303.45
#Mann= 3 ,-1 , 0
    4745     .05       0  5004.8     .03       0  5010.8     .05       0
Bank Sta=5004.8,5010.8
XS Rating Curve= 0 ,0
Exp/Cntr=0.3,0.1

Type RM Length L Ch R = 1 ,4514    ,389,389,389
BEGIN DESCRIPTION:
Mapping XS 23bfa130
END DESCRIPTION:
XS GIS Cut Line= 4
      2226696.56     13186533.37      2226696.56     13186706.97
      2226861.49     13186967.39      2227050.59      13186941.6
#Sta/Elev= 30
  4695.2  299.17  4798.7  295.62  4828.7  294.23  4877.4  293.33  4883.4  293.72
  4919.8  292.64  4927.8  292.07  4935.1  292.17  4963.4  289.79  4974.4   288.3
  4977.2   287.8  4980.4   288.3  4986.8  288.54  4998.9  290.09    5008  290.77
  5022.5  290.91  5071.5  292.63  5080.9  292.53  5093.6  293.17  5123.2  293.36
  5129.1  293.84  5218.3  294.36    5254     295  5264.1  295.91  5274.2  295.79
  5290.7  296.43  5314.5  296.42  5324.6  296.85  5354.9  296.83  5367.9  297.38
#Mann= 3 ,-1 , 0
  4695.2     .05       0  4974.4     .03       0  4980.4     .05       0
Bank Sta=4974.4,4980.4
XS Rating Curve= 0 ,0
Exp/Cntr=0.3,0.1

Type RM Length L Ch R = 1 ,4125    ,206,206,206
BEGIN DESCRIPTION:
Mapping XS a3baa377
END DESCRIPTION:
XS GIS Cut Line= 4
      2226338.16     13186559.99       2226342.5     13186826.96
      2226542.15     13187033.12      2226844.33      13187065.5
#Sta/Elev= 30
  4635.7  294.94  4662.6  295.01  4712.6  294.23  4742.6   293.2  4782.6  293.09
  4812.6  292.29  4832.6  292.41  4852.6  291.35  4872.6  291.58  4896.4  290.54
  4927.6   290.4  4941.7   289.5  4955.9  289.99  4991.2  289.41  5012.7  287.81
  5019.4   287.6  5023.6  286.31  5026.4  285.81  5029.6  286.31  5047.7  287.45
  5054.9  288.58  5069.1  289.19  5104.3  289.94  5118.5   289.7  5167.9  291.12
  5271.2  292.22  5285.8  291.91  5336.1  292.57  5396.4  292.14  5493.6  292.99
#Mann= 5 ,-1 , 0
  4635.7     .05       0  4896.4      .1       0  5012.7     .05       0
  5023.6     .07       0  5029.6     .05       0
Bank Sta=5023.6,5029.6
XS Rating Curve= 0 ,0
Exp/Cntr=0.3,0.1

Type RM Length L Ch R = 1 ,3919    ,323,323,323
BEGIN DESCRIPTION:
WILLIE TANK CREEK 3.0
END DESCRIPTION:
XS GIS Cut Line= 4
      2225882.45     13186724.99      2226116.81     13186996.23
      2226524.79      13187100.4      2226874.53     13187104.71
#Sta/Elev= 30
  4459.4  294.13  4464.1  294.28    4486  292.83  4492.7   293.6  4521.2  293.11
  4535.4  292.29  4560.4   292.2  4584.8  292.03  4606.7  291.03  4613.3  291.59
  4656.1  291.06  4676.9  291.78  4719.7  291.25  4740.6   291.5  4776.7  290.78
  4842.6   290.7  4919.1  289.67  4970.3  287.95  4994.3  285.96  4997.9  284.83
  5000.6  284.33  5003.9  284.83    5006  285.89  5041.7  288.47  5124.6  288.55
  5164.3  289.37    5200  290.81  5561.9  292.62  5581.9  292.19  5588.7  293.14
#Mann= 6 ,-1 , 0
  4459.4      .1       0  4560.4     .05       0  4970.3      .1       0
  4997.9     .07       0  5003.9      .1       0  5124.6     .05       0
Bank Sta=4997.9,5003.9
XS Rating Curve= 0 ,0
Exp/Cntr=0.3,0.1

Type RM Length L Ch R = 1 ,3596    ,354,354,354
BEGIN DESCRIPTION:
Mapping XS db4ec3e6
END DESCRIPTION:
XS GIS Cut Line= 4
      2225925.39     13187004.46      2226116.37     13187271.84
      2226449.71     13187379.48      2226682.31     13187369.06
#Sta/Elev= 30
  4543.9  289.63    4626   289.7  4661.7  289.05  4732.9  288.95  4747.7  288.54
  4762.4  288.82  4777.2  288.34  4783.3  288.75  4872.5  288.56  4934.7  286.97
  4939.9  286.26  4952.1   286.3    4979  285.93  5007.5  284.01  5010.3  283.51
  5013.5  284.01    5021  285.21    5042  286.43  5052.5  286.71  5094.6  286.47
    5125   287.2  5169.4   288.9  5189.2   289.2  5210.2  288.78  5270.8  289.32
  5290.8  288.93  5300.9  289.42  5350.9  288.82  5389.5  289.42  5455.6  289.52
#Mann= 5 ,-1 , 0
  4543.9     .05       0  4952.1      .1       0  5007.5     .07       0
  5013.5      .1       0    5125     .05       0
Bank Sta=5007.5,5013.5
XS Rating Curve= 0 ,0
Exp/Cntr=0.3,0.1

Type RM Length L Ch R = 1 ,3242    ,252,252,252
BEGIN DESCRIPTION:
Mapping XS 3905b5ef
END DESCRIPTION:
XS GIS Cut Line= 4
       2225602.5     13187466.29      2226088.59     13187636.42
       2226425.4     13187650.31      2226782.88     13187455.95
#Sta/Elev= 30
  4285.7  288.96  4304.8   289.1    4323  288.28  4354.8  286.29  4386.6  285.13
  4392.6  284.33  4407.8  283.84  4439.3  281.61  4449.4  282.22  4492.5  282.15
  4516.7  283.07  4547.8  282.63  4630.2  284.67  4666.6  284.61  4683.2  283.45
    4768  282.18    4970  284.19    5030  284.46    5050  283.53  5080.1  284.04
  5110.1   283.5  5120.1  283.94  5172.7  283.66  5222.1  284.29  5281.9  283.38
  5319.9  285.27  5325.6  286.08  5363.6  286.54  5369.3  287.15  5544.7  288.25
#Mann= 3 , 0 , 0
  4285.7     .05       0    4970     .03       0    5030     .05       0
#XS Ineff= 3 ,-1
  4285.7 4630.34  284.67    4655 4959.66  284.27 5030.45 5331.14  284.47
Permanent Ineff=
       T       T       T
Bank Sta=4970,5030
XS Rating Curve= 0 ,0
Exp/Cntr=0.3,0.1

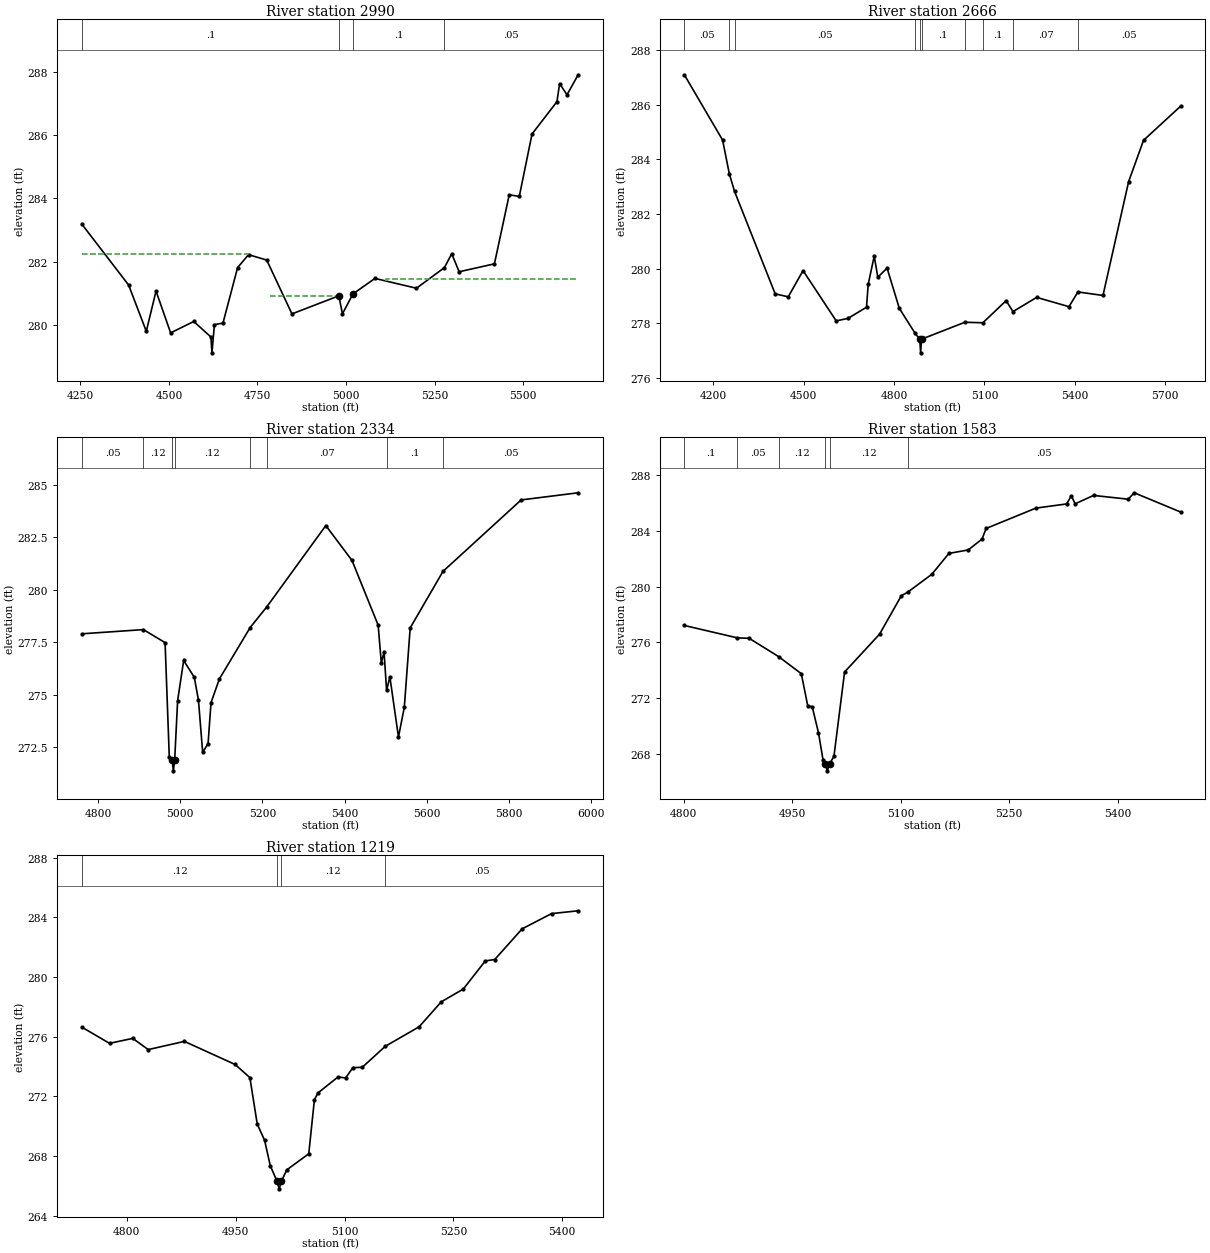
Type RM Length L Ch R = 1 ,2990    ,324,324,324
BEGIN DESCRIPTION:
Mapping XS 4767d71a
END DESCRIPTION:
XS GIS Cut Line= 4
      2225611.45     13187800.71       2226097.6     13187922.25
      2226505.59     13187844.12      2226825.78     13187480.66
#Sta/Elev= 30
  4254.4  283.18  4386.3  281.26  4436.1   279.8  4463.6  281.07  4504.8  279.75
  4570.1  280.11  4618.6  279.62  4621.4  279.12  4628.5  280.01  4652.6  280.06
  4693.8  281.81  4724.7  282.22    4776  282.05  4847.3  280.35  4979.6  280.92
  4989.8  280.35  5019.4  280.98  5081.6  281.47  5198.7  281.16  5277.6  281.81
  5298.3  282.25  5319.2  281.68  5418.8  281.93  5460.6  284.11    5489  284.06
    5525  286.03  5595.3  287.05  5602.8  287.62  5623.7  287.27  5655.3   287.9
#Mann= 4 ,-1 , 0
  4254.4      .1       0  4979.6     .07       0  5019.4      .1       0
  5277.6     .05       0
#XS Ineff= 3 ,-1
  4254.4 4724.55  282.23 4786.36 4974.55  280.92 5111.82  5655.3  281.45
Permanent Ineff=
       F       F       F
Bank Sta=4979.6,5019.4
XS Rating Curve= 0 ,0
Exp/Cntr=0.3,0.1

Type RM Length L Ch R = 1 ,2666    ,332,332,332
BEGIN DESCRIPTION:
Mapping XS 406faccc
END DESCRIPTION:
XS GIS Cut Line= 4
      2225433.02     13187999.26      2226047.62     13188218.02
      2226636.16     13188124.27      2226927.86     13187853.41
#Sta/Elev= 30
  4104.5   287.1  4231.5  284.71  4253.9  283.47  4271.1  282.83  4405.9  279.08
  4449.2  278.97  4498.4  279.93  4608.4  278.09  4647.3  278.18  4708.9  278.59
  4714.5  279.43  4734.5  280.46  4746.4  279.69  4777.2  280.02  4817.7  278.55
  4870.4  277.63  4885.6  277.42  4888.4  276.92  4891.6  277.42  5035.3  278.04
  5094.9  278.02  5172.1  278.83  5194.8  278.43  5273.4  278.95  5380.6  278.61
  5410.2  279.15  5493.4  279.02  5578.5  283.19  5627.9   284.7  5750.9  285.95
#Mann= 10 ,-1 , 0
  4104.5     .05       0  4253.9      .1       0  4271.1     .05       0
  4870.4      .1       0  4885.6     .07       0  4891.6      .1       0
  5035.3     .07       0  5094.9      .1       0  5194.8     .07       0
  5410.2     .05       0
Bank Sta=4885.6,4891.6
XS Rating Curve= 0 ,0
Exp/Cntr=0.3,0.1

Type RM Length L Ch R = 1 ,2334    ,751,751,751
BEGIN DESCRIPTION:
Mapping XS 70226652
END DESCRIPTION:
XS GIS Cut Line= 3
      2226068.44     13188504.48      2226573.66     13188415.94
       2227099.7     13187962.82
#Sta/Elev= 30
  4760.8   277.9  4910.4   278.1  4963.1  277.48  4973.3  272.06  4980.4  271.88
  4983.2  271.38  4986.4  271.88  4993.6  274.72  5008.3  276.63  5034.2  275.83
  5044.3  274.74  5054.5  272.26  5067.7  272.68  5074.8  274.62  5095.1  275.75
  5170.1   278.2  5210.4  279.18  5354.1  283.05  5417.8  281.39  5481.4  278.31
  5489.1   276.5  5495.7  277.05  5501.9  275.21  5509.9  275.85  5530.8  272.99
    5545   274.4  5559.3  278.18  5639.1  280.87  5829.2  284.27    5968  284.61
#Mann= 8 ,-1 , 0
  4760.8     .05       0  4910.4     .12       0  4980.4     .07       0
  4986.4     .12       0  5170.1      .1       0  5210.4     .07       0
  5501.9      .1       0  5639.1     .05       0
Bank Sta=4980.4,4986.4
XS Rating Curve= 0 ,0
Exp/Cntr=0.3,0.1

Type RM Length L Ch R = 1 ,1583    ,364,364,364
BEGIN DESCRIPTION:
Mapping XS bd757199
END DESCRIPTION:
XS GIS Cut Line= 3
      2226886.17     13188671.13      2227104.91     13188343.02
       2227203.3     13188068.56
#Sta/Elev= 30
  4801.1  277.21  4874.4  276.32  4890.7  276.29  4931.3  274.98  4962.8  273.75
  4971.8  271.41  4977.8  271.39  4986.5  269.52  4992.9  267.54  4995.9  267.28
  4998.6  266.78  5001.9  267.28  5007.9  267.82  5022.6  273.87    5071  276.59
    5101  279.34  5109.9   279.6  5143.1  280.88  5166.8  282.38  5193.5  282.63
  5212.6  283.41  5218.2  284.17    5287  285.63  5329.5  285.93  5335.9  286.51
  5341.3  285.94  5366.7  286.54  5414.5  286.27  5422.9  286.73    5487  285.35
#Mann= 6 ,-1 , 0
  4801.1      .1       0  4874.4     .05       0  4931.3     .12       0
  4995.9     .07       0  5001.9     .12       0  5109.9     .05       0
Bank Sta=4995.9,5001.9
XS Rating Curve= 0 ,0
Exp/Cntr=0.3,0.1

Type RM Length L Ch R = 1 ,1219    ,0,0,0
BEGIN DESCRIPTION:
WILLIE TANK CREEK 1.0
END DESCRIPTION:
XS GIS Cut Line= 3
      2227162.17     13188691.99      2227328.87     13188629.48
        2227412.      13188130.7
#Sta/Elev= 30
  4738.2  276.63  4776.2  275.55  4808.2  275.88  4829.6  275.13  4879.3  275.68
  4949.3  274.13  4969.6  273.25  4979.7  270.14  4989.9  269.04  4997.7  267.34
  5007.1  266.29  5009.9  265.79  5013.1  266.29  5020.3  267.06  5050.7  268.14
  5058.5  271.77  5063.6  272.23  5091.2   273.3  5101.4  273.22  5111.5  273.92
  5124.4  273.94  5156.1  275.35  5202.8  276.66  5233.2  278.33  5263.6  279.19
    5294  281.08  5306.9  281.17  5344.7  283.23  5385.2  284.25  5421.9  284.44
#Mann= 4 ,-1 , 0
  4738.2     .12       0  5007.1     .07       0  5013.1     .12       0
  5156.1     .05       0
Bank Sta=5007.1,5013.1
XS Rating Curve= 0 ,0
Exp/Cntr=0.3,0.1

Chan Stop Cuts=-1
Use User Specified Reach Order=0
Composite Channel Slope=5