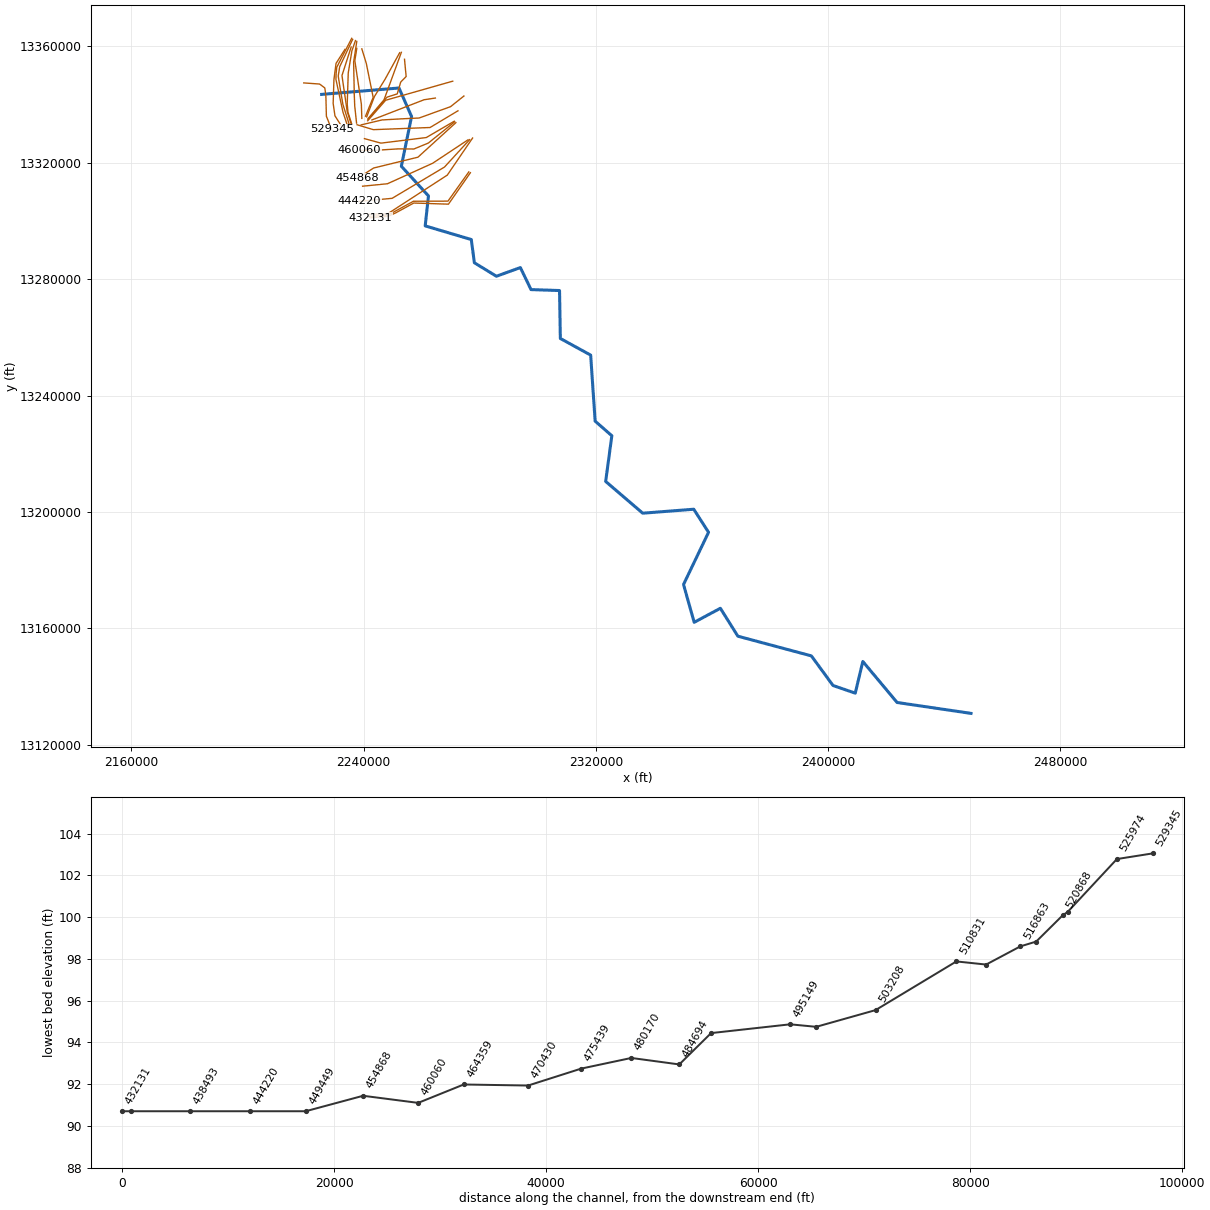
--- NUECES RIVER.prj (project) ---

Proj Title=NUECES RIVER Base Level Engineering
Current Plan=p01
Default Exp/Contr=0.3,0.1
English Units
Geom File=g01
Flow File=f01
Plan File=p01
Y Axis Title=Elevation
X Axis Title(PF)=Main Channel Distance
X Axis Title(XS)=Station
BEGIN DESCRIPTION:
NUECES RIVER
END DESCRIPTION:
DSS Export Rating Curves= 0
DSS Export Rating Curve Sorted= 0
DSS Export Volume Flow Curves= 0
DXF OffsetX= 0
DXF OffsetY= 0
DXF ScaleX= 1
DXF ScaleY= 10

--- NUECES RIVER.p01 (plan) ---

Plan Title=Multiple Run
Short Identifier=Multiple
Geom File=g01
Flow File=f01
Subcritical Flow
K Sum by GR= 0
Std Step Tol= 0.01
Critical Tol= 0.01
Num of Std Step Trials= 20
Max Error Tol= 0.3
Flow Tol Ratio= 0.001
Split Flow NTrial= 30
Split Flow Tol= 0.02
Split Flow Ratio= 0.02
Log Output Level= 0
Friction Slope Method= 1
Unsteady Friction Slope Method= 2
Unsteady Bridges Friction Slope Method= 1
Parabolic Critical Depth
Global Vel Dist=  1 , 1 , 1
Global Log Level= 0
CheckData=True
Encroach Param= -1, 0, 0, 0
BEGIN DESCRIPTION:
Multiple Run
END DESCRIPTION:

--- NUECES RIVER.f01 (steady flow) ---

Flow Title=Multiple
Program Version=4.10
Number of Profiles= 7
Profile Names=10-year,25-year,50-year,1pct_min,100-year,1pct_plu,500-year
River Rch & RM=NUECES RIVER,Reach-1         ,529345
   31111   41499   50140   53038   71728   97004  130960
River Rch & RM=NUECES RIVER,Reach-1         ,520868
   31111   41499   50140   53038   71728   97004  130960
River Rch & RM=NUECES RIVER,Reach-1         ,487693
   41098   54946   66472   70266   95026  128512  172742
River Rch & RM=NUECES RIVER,Reach-1         ,484694
   41098   54946   66472   70266   95026  128512  172742
River Rch & RM=NUECES RIVER,Reach-1         ,454868
   41098   54946   66472   70266   95026  128512  172742
River Rch & RM=NUECES RIVER,Reach-1         ,438493
   41098   54946   66472   70266   95026  128512  172742
River Rch & RM=NUECES RIVER,Reach-1         ,422065
   41098   54946   66472   70266   95026  128512  172742
River Rch & RM=NUECES RIVER,Reach-1         ,398509
   41098   54946   66472   70266   95026  128512  172742
River Rch & RM=NUECES RIVER,Reach-1         ,368841
   41098   54946   66472   70266   95026  128512  172742
River Rch & RM=NUECES RIVER,Reach-1         ,348200
   41098   54946   66472   70266   95026  128512  172742
River Rch & RM=NUECES RIVER,Reach-1         ,336726
   41098   54946   66472   70266   95026  128512  172742
River Rch & RM=NUECES RIVER,Reach-1         ,299162
   41098   54946   66472   70266   95026  128512  172742
River Rch & RM=NUECES RIVER,Reach-1         ,259097
   43312   57863   69957   73865   99894  135095  181094
River Rch & RM=NUECES RIVER,Reach-1         ,254363
   52846   72114   88487   94871  128302  173513  239820
River Rch & RM=NUECES RIVER,Reach-1         ,251756
   52846   72114   88487   94871  128302  173513  239820
River Rch & RM=NUECES RIVER,Reach-1         ,226842
   52846   72114   88487   94871  128302  173513  239820
River Rch & RM=NUECES RIVER,Reach-1         ,221985
   54623   74392   91150   97538  131909  178392  245472
River Rch & RM=NUECES RIVER,Reach-1         ,179949
   54623   74392   91150   97538  131909  178392  245472
River Rch & RM=NUECES RIVER,Reach-1         ,143467
   54623   74392   91150   97538  131909  178392  245472
River Rch & RM=NUECES RIVER,Reach-1         ,89346
   54623   74392   91150   97538  131909  178392  245472
River Rch & RM=NUECES RIVER,Reach-1         ,50843
   54623   74392   91150   97538  131909  178392  245472
Boundary for River Rch & Prof#=NUECES RIVER,Reach-1         , 1
Up Type= 0
Dn Type= 3
Dn Slope=0.00002
Boundary for River Rch & Prof#=NUECES RIVER,Reach-1         , 2
Up Type= 0
Dn Type= 3
Dn Slope=0.00002
Boundary for River Rch & Prof#=NUECES RIVER,Reach-1         , 3
Up Type= 0
Dn Type= 3
Dn Slope=0.00002
Boundary for River Rch & Prof#=NUECES RIVER,Reach-1         , 4
Up Type= 0
Dn Type= 3
Dn Slope=0.00002
Boundary for River Rch & Prof#=NUECES RIVER,Reach-1         , 5
Up Type= 0
Dn Type= 3
Dn Slope=0.00002
Boundary for River Rch & Prof#=NUECES RIVER,Reach-1         , 6
Up Type= 0
Dn Type= 3
Dn Slope=0.00002
Boundary for River Rch & Prof#=NUECES RIVER,Reach-1         , 7
Up Type= 0
Dn Type= 3
Dn Slope=0.00002
DSS Import GetInterval= 0
DSS Import GetPeak= 0
DSS Import FillOption= 0

--- NUECES RIVER.g01 (geometry) ---

Geom Title=Existing Conditions
Program Version=4.10

River Reach=NUECES RIVER    ,Reach-1
Reach XY= 30
      2225566.31     13343462.04      2252218.69     13345651.74
       2256544.8     13335865.65      2253024.18     13318778.22
      2262355.55     13308586.27      2261238.34     13298285.72
      2277117.65     13293588.62       2278171.7     13285614.16
      2285762.33     13280984.53      2294013.96     13283962.66
      2297689.25     13276398.31      2307507.66     13276073.79
      2307781.38     13259605.21      2318224.94     13253890.11
      2319769.41     13231201.65      2325520.33     13226189.12
       2323393.6       13210486.      2336154.94     13199578.02
      2353736.85     13200940.62      2358826.28     13193012.53
      2350208.48     13175086.02      2353882.09     13162090.33
      2362903.13     13166911.34       2368921.2     13157325.02
      2394231.73     13150562.34      2401694.66     13140391.53
       2409352.6     13137754.66      2411964.99     13148641.08
      2423763.32     13134547.61      2449222.43     13130808.42

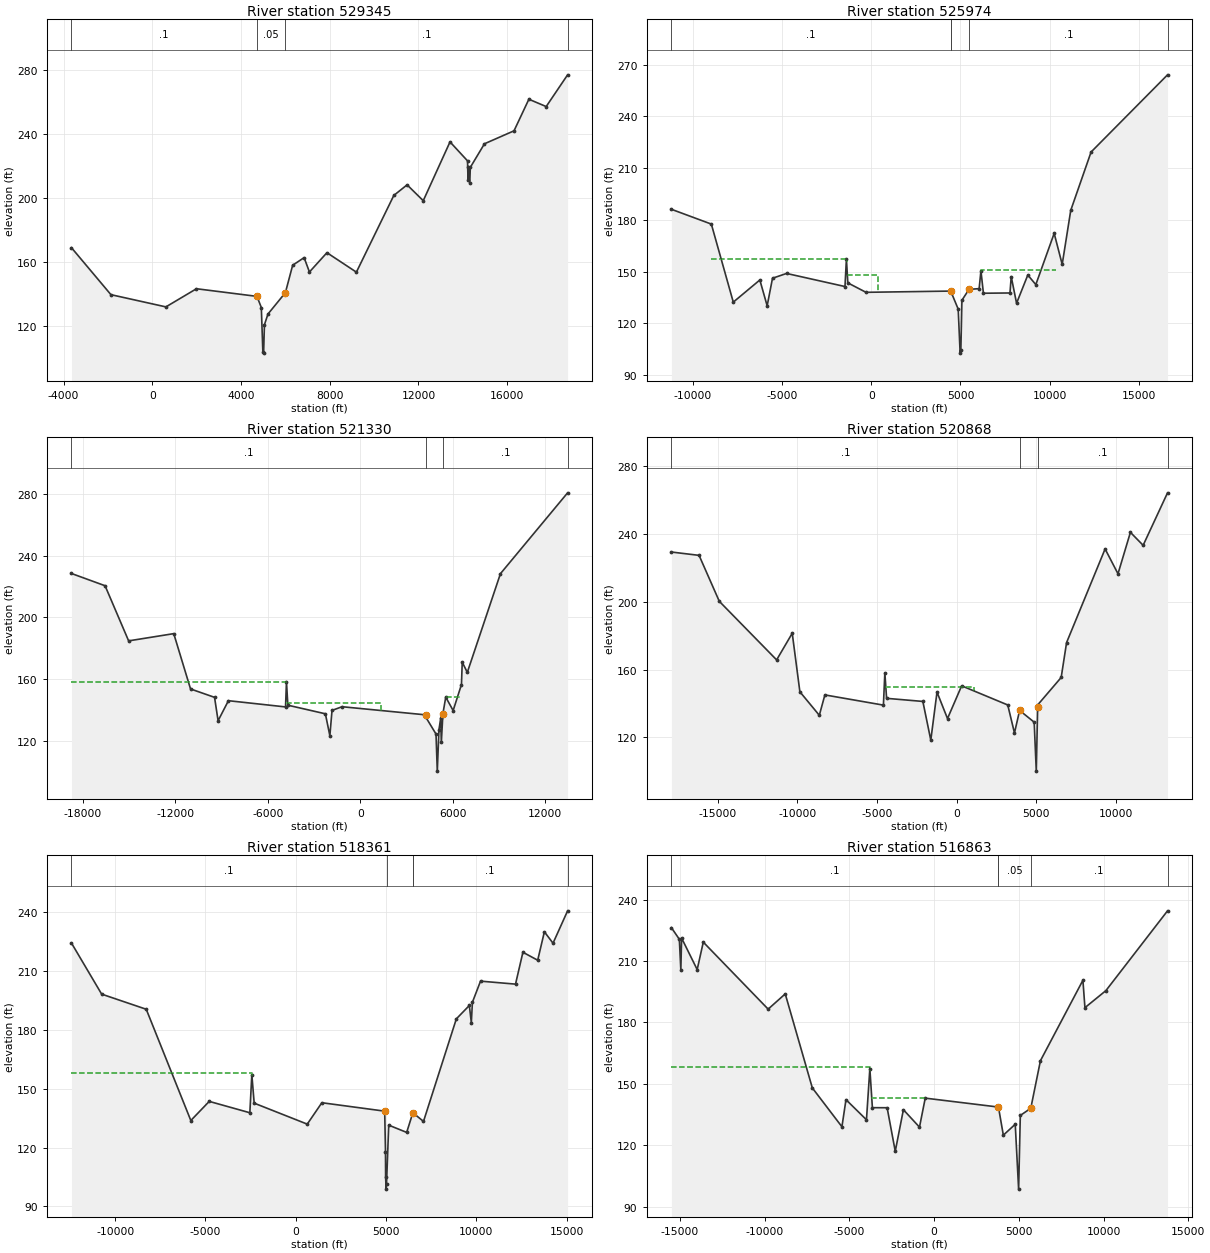
Type RM Length L Ch R = 1 ,529345  ,3371,3371,3371
BEGIN DESCRIPTION:
LOWER NUECES 2.0
END DESCRIPTION:
XS GIS Cut Line= 6
      2219394.36     13347399.71      2224857.61     13347021.63
      2226663.19     13345677.36      2227029.08     13343033.73
      2227206.51     13335952.64      2228996.89     13331431.07
#Sta/Elev= 30
 -3645.2  169.03 -1866.2  139.64612.1499  131.99 1990.47  143.35 4718.91  138.57
  4914.6  131.59  4984.7   103.5  5017.7  103.05  5054.7  120.81  5214.8  127.53
 5999.54  140.89 6327.25  158.05 6844.04  162.83 7083.74  153.82 7872.73  165.91
 9201.05  153.73 10888.9  201.7611487.49  208.38 12215.5  198.4513422.19  235.26
 14211.3   223.4 14234.5  211.29 14253.5  219.84 14312.9  209.38 14337.2  219.31
 14974.9  234.08 16308.6   242.2 16977.5  261.96 17758.6  257.38   18724  277.24
#Mann= 4 ,-1 , 0
 -3645.2      .1       0 4718.91     .05       0 5999.54      .1       0
   18724     .05       0
#XS Ineff= 2 , 0
         2013.89  143.04
Permanent Ineff=
       F       F
Bank Sta=4718.91,5999.54
XS Rating Curve= 0 ,0
Exp/Cntr=0.3,0.1

Type RM Length L Ch R = 1 ,525974  ,4644,4644,4644
BEGIN DESCRIPTION:
LOWER NUECES 3.0
END DESCRIPTION:
XS GIS Cut Line= 6
      2233602.69      13358941.4      2230529.75     13354097.63
      2229800.59     13348524.71      2229540.17     13340347.63
      2230165.17      13336076.8      2232300.57     13332743.49
#Sta/Elev= 30
-11204.4  186.16 -8965.5  177.58-7735.24  132.34-6246.19  145.18-5836.45  130.21
-5536.64  146.19-4747.91  148.97-1473.44  141.38-1393.57  157.32-1313.71   143.5
  -295.4  138.03 4454.01  138.75  4872.6  128.32  4982.4  102.78  5022.6  104.74
  5082.7  133.45 5478.15  139.73  6047.6  140.16  6147.5  150.526287.359   137.5
  7775.9  137.65 7845.83  147.138145.539   131.7 8775.01  148.05 9224.65   142.5
10253.85  172.21 10703.5  154.2211183.12  185.5612322.23  219.35 16608.5   264.1
#Mann= 5 ,-1 , 0
-11204.4      .1       0  4452.3     .05       0  4452.3     .05       0
 5478.15      .1       0 16608.5      .1       0
#XS Ineff= 3 ,-1
-9010.31-1384.88  157.58-1353.53  395.09     148 6138.2910352.78   150.8
Permanent Ineff=
       T       F       F
Bank Sta=4454.01,5478.15
XS Rating Curve= 0 ,0
Exp/Cntr=0.3,0.1

Type RM Length L Ch R = 1 ,521330  ,462,462,462
BEGIN DESCRIPTION:
LOWER NUECES 4.0
END DESCRIPTION:
XS GIS Cut Line= 6
      2235922.72     13362715.94      2230786.26     13352810.17
      2230557.02     13350704.59      2230494.18     13348614.45
      2232916.54     13337371.65      2234587.95     13332367.07
#Sta/Elev= 30
-18722.8  228.37-16544.8  220.43-15017.4  184.69-12091.9  189.38-11003.8  153.52
-9446.58  148.08-9216.98  132.93-8548.16  145.91-4844.31  141.87-4784.57  158.27
-4694.94  142.99-2261.18  137.41-1971.28  123.18-1831.35  139.61 -1181.6     142
  4230.2  136.74  4244.7  135.28  4910.6  124.29  4993.5  100.25  5101.4  127.07
  5214.6  134.53  5255.9  118.82  5357.5  137.49 5542.25  148.22  6021.5  139.52
 6560.66  156.38 6610.58  170.856940.061  164.269087.449  228.25   13442  280.66
#Mann= 4 ,-1 , 0
-18722.8      .1       0  4244.7     .05       0  5357.5      .1       0
   13442     .05       0
#XS Ineff= 3 ,-1
-18722.8-4788.33  158.24-4788.33 1368.77   144.7 5541.56 6459.64  148.19
Permanent Ineff=
       T       T       F
Bank Sta=4230.2,5357.5
XS Rating Curve= 0 ,0
Exp/Cntr=0.3,0.1

Type RM Length L Ch R = 1 ,520868  ,2507,2507,2507
BEGIN DESCRIPTION:
LOWER NUECES 5.0
END DESCRIPTION:
XS GIS Cut Line= 6
      2236252.91     13362367.43      2231790.86     13352974.69
      2231284.49     13349770.03      2231954.37     13345529.18
      2232890.21     13340039.74      2235196.61     13332751.49
#Sta/Elev= 30
-17901.7  229.49-16164.2  227.52-14894.3  200.38-11294.8  165.78-10314.9  181.51
-9835.02  146.95-8615.15  133.07-8265.18   145.1-4590.39  139.07-4500.55  158.21
-4390.74  143.08-2114.33  141.25-1615.11  118.39-1225.72  146.77 -566.75  131.13
321.7402  150.47 3216.08  139.16  3637.6  122.62  3962.2  135.94  4875.7  128.99
  5007.4  100.09  5093.3  137.74    5099  139.23 6570.32   155.46910.051  176.02
 9328.16  231.3110137.53  216.6310916.92  241.1211716.29  233.45   13248  264.45
#Mann= 4 ,-1 , 0
-17901.7      .1       0  3962.2     .05       0    5099      .1       0
   13248      .1       0
#XS Ineff= 2 ,-1
-17901.7   -4500   157.7-4468.75 1097.22  149.94
Permanent Ineff=
       F       F
Bank Sta=3962.2,5093.3
XS Rating Curve= 0 ,0
Exp/Cntr=0.3,0.1

Type RM Length L Ch R = 1 ,518361  ,1498,1498,1498
BEGIN DESCRIPTION:
LOWER NUECES 6.0
END DESCRIPTION:
XS GIS Cut Line= 4
      2235734.13     13359734.79      2232569.57      13349920.7
      2234371.58     13337601.07       2235802.8     13333122.08
#Sta/Elev= 30
-12415.3  224.25-10744.3  198.22-8276.34  190.51-5808.34   133.8-4789.16  143.55
-2540.95  137.76-2431.04  157.18-2301.14  142.65636.5898  131.96 1445.96  142.87
  4924.2  138.57  4967.7  117.88  4974.8  104.84  5004.8   98.83  5025.3  101.53
  5146.6  131.44  6141.2  127.74  6483.5  137.77 7071.59  133.34 8890.17  185.62
  9609.6  192.43 9719.52  183.689779.471  194.0810229.12  204.8412165.87  203.32
12575.16  219.5613393.73  215.5113763.09  229.9914242.26  224.18 15049.2  240.68
#Mann= 5 ,-1 , 0
-12415.3      .1       0  5025.3     .05       0  6483.5     .16       0
  6483.5      .1       0 15049.2      .1       0
#XS Ineff= 2 , 0
         -2437.5  157.93
Permanent Ineff=
       F       F
Bank Sta=4924.2,6483.5
XS Rating Curve= 0 ,0
Exp/Cntr=0.3,0.1

Type RM Length L Ch R = 1 ,516863  ,3225,3225,3225
BEGIN DESCRIPTION:
LOWER NUECES 7.0
END DESCRIPTION:
XS GIS Cut Line= 6
      2237214.96     13361955.79      2235977.48     13358362.94
      2234728.26     13350795.42      2234385.36     13340162.51
      2234637.14      13337307.6      2235955.32     13333206.51
#Sta/Elev= 30
-15504.9  226.31-15036.4  220.62  -14948   205.7-14903.2  221.23  -13983  205.83
  -13623  219.23-9794.68  186.51 -8785.7  193.95-7187.65  148.04-5439.82  129.06
-5200.12  142.29-3991.57  132.47 -3791.6  157.45-3641.62  138.38-2771.72  138.35
-2291.78  117.08-1811.84  137.39 -861.96  128.87    -522  143.04  3799.2  138.68
4087.211  124.96  4789.7  130.28  4989.5    98.6  5089.8  134.595706.891  138.07
6276.779  161.32 8783.73   200.6 8903.57  187.22 10142.4  195.56 13778.7  234.52
#Mann= 5 ,-1 , 0
-15504.9      .1       0  3799.2     .05       0  3799.2     .05       0
5706.891      .1       0 13778.7      .1       0
#XS Ineff= 2 ,-1
-15504.9-3781.25  158.06-3734.18 -525.95  143.26
Permanent Ineff=
       F       F
Bank Sta=3799.2,5706.891
XS Rating Curve= 0 ,0
Exp/Cntr=0.3,0.1

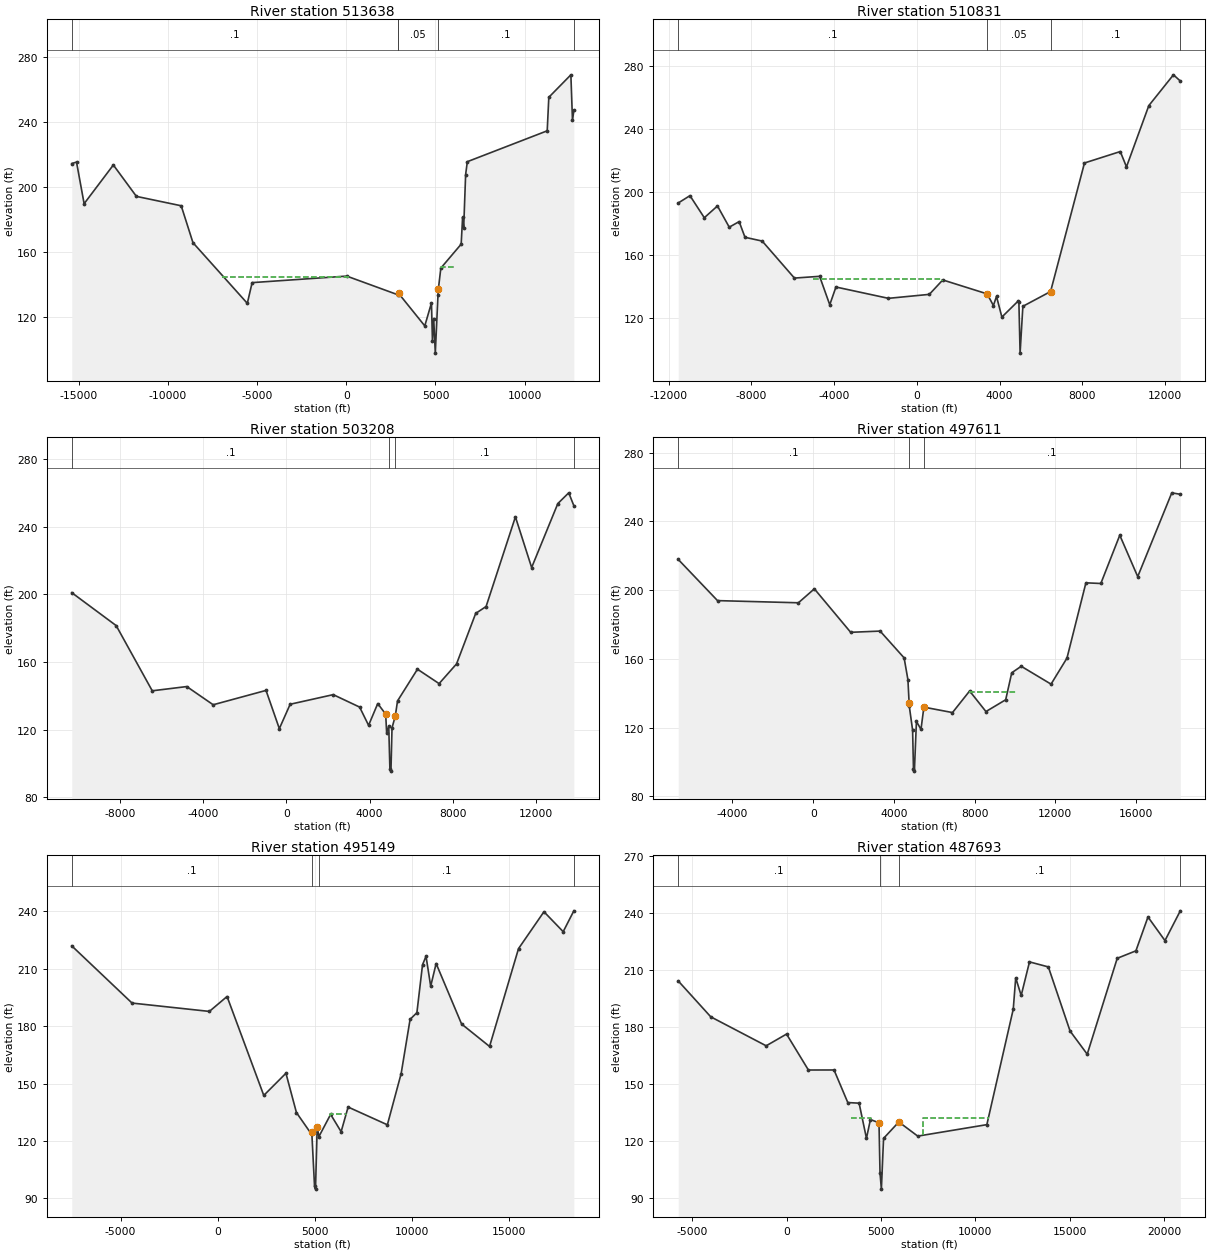
Type RM Length L Ch R = 1 ,513638  ,2807,2807,2807
BEGIN DESCRIPTION:
LOWER NUECES 8.0
END DESCRIPTION:
XS GIS Cut Line= 5
       2237673.7     13361641.61      2236585.97     13354555.14
       2236819.4     13343143.81      2236966.12       13339456.
      2237599.84     13333601.21
#Sta/Elev= 30
-15400.9  214.31-15134.5   215.2-14708.1  189.62-13069.1  213.42-11774.3  194.11
 -9262.3  188.34-8602.57  165.64-5554.13  128.35-5284.29  141.0822.59961   145.1
  2919.2   133.5  2929.2   134.5  4400.2  114.48  4775.3  128.57  4830.5  105.45
  4900.6  119.01  4990.9   97.73  5140.8  133.39  5160.8  136.97  5300.9     150
  6441.8  164.73  6521.9  181.18  6581.9   174.6    6692  207.54  6787.3  215.45
 11267.7  234.43 11358.2  255.05 12595.4  268.86 12685.9  240.82   12762  246.98
#Mann= 5 ,-1 , 0
-15400.9      .1       0  2919.2     .05       0  2919.2     .05       0
  5140.8      .1       0   12762      .1       0
#XS Ineff= 2 ,-1
-6994.36  150.52  144.62 5302.08 6079.86  150.76
Permanent Ineff=
       F       F
Bank Sta=2929.2,5160.8
XS Rating Curve= 0 ,0
Exp/Cntr=0.3,0.1

Type RM Length L Ch R = 1 ,510831  ,7623,7623,7623
BEGIN DESCRIPTION:
LOWER NUECES 9.0
END DESCRIPTION:
XS GIS Cut Line= 4
      2237681.27     13359276.46        2237006.     13355038.32
      2239249.74     13340092.82      2239415.22     13335214.41
#Sta/Elev= 30
-11541.6  193.11-10974.4  197.75-10280.5  183.75 -9643.8  191.23 -9074.2  177.76
 -8595.3   181.3 -8313.2  171.35 -7479.9  168.95-5922.02  145.48 -4702.6  146.59
-4212.84  128.56-3912.98  139.81-1374.21  132.63604.8301  135.15 1254.52   144.3
 3403.47  135.44 3703.33  128.04 3853.26  133.87 4113.13  120.75  4915.3  131.12
  4936.5  130.17  4994.2   97.88  5128.6  127.57  6468.5  136.94  8109.1  218.48
  9840.1  225.73 10140.3  216.01 11220.9  254.86 12411.6  274.39 12744.2  270.47
#Mann= 4 ,-1 , 0
-11541.6      .1       0 3403.47     .05       0  6468.5      .1       0
 12744.2      .1       0
#XS Ineff= 1 ,-1
-5009.41 1199.44  145.15
Permanent Ineff=
       F
Bank Sta=3403.47,6468.5
XS Rating Curve= 0 ,0
Exp/Cntr=0.3,0.1

Type RM Length L Ch R = 1 ,503208  ,5597,5597,5597
BEGIN DESCRIPTION:
LOWER NUECES 10.0
END DESCRIPTION:
XS GIS Cut Line= 4
      2239416.43     13359096.02      2240950.93     13354112.95
      2243322.06     13342429.76      2240679.63     13335965.99
#Sta/Elev= 30
-10307.4  200.99 -8173.7  181.53-6441.46  143.01-4783.23  145.52-3514.13  134.76
 -975.96  143.24-336.419  120.66183.1904  135.06 2251.68  140.74 3520.75  133.38
 3950.43  122.61 4390.11  135.45  4772.4  129.23  4817.9  118.24  4919.2  122.07
    4975   96.82  5025.4   95.55  5076.3  121.09  5233.1  128.07  5341.2  137.03
6298.699  155.777337.789  147.268176.971  158.92 9096.07  188.74 9595.58  192.81
11004.21  245.7811783.44  215.8413042.21  253.65   13566  259.98   13811  252.38
#Mann= 4 ,-1 , 0
-10307.4      .1       0  4919.2     .05       0  5233.1      .1       0
   13811      .1       0
#XS Ineff= 2 ,-1
-4896.52-1001.88  142.99 -917.22 2328.32     140
Permanent Ineff=
       F       F
Bank Sta=4772.4,5233.1
XS Rating Curve= 0 ,0
Exp/Cntr=0.3,0.1

Type RM Length L Ch R = 1 ,497611  ,2462,2462,2462
BEGIN DESCRIPTION:
LOWER NUECES 11.0
END DESCRIPTION:
XS GIS Cut Line= 4
      2252445.26     13357780.32      2247425.61     13348687.35
      2243717.32     13342667.11      2241089.32     13335726.78
#Sta/Elev= 30
   -6688  217.87-4741.66  193.92 -733.02  192.6656.70996  200.77 1856.11  175.49
 3315.63   176.2 4504.46  160.62  4693.5  147.91  4751.5  134.54  4757.3   132.8
  4925.3   118.6  4967.9   96.23  5013.9   94.75  5114.6  123.67  5340.6  119.04
  5484.3  131.97 6901.34  128.81 7750.23  141.36 8559.18   129.4 9537.91  136.26
 9837.51  151.9410306.87  155.7411785.04  145.3412574.12  160.4813513.01  204.27
14252.15  203.8815191.04  231.96   16080  207.8817768.02  256.61 18190.4  255.76
#Mann= 4 ,-1 , 0
   -6688      .1       0  4757.3     .05       0  5484.3      .1       0
 18190.4      .1       0
#XS Ineff= 1 ,-1
  7695.210065.85  140.92
Permanent Ineff=
       F
Bank Sta=4751.5,5484.3
XS Rating Curve= 0 ,0
Exp/Cntr=0.3,0.1

Type RM Length L Ch R = 1 ,495149  ,7456,7456,7456
BEGIN DESCRIPTION:
LOWER NUECES 12.0
END DESCRIPTION:
XS GIS Cut Line= 3
      2253033.69     13357920.78      2247055.82     13341589.68
      2241591.62     13335164.86
#Sta/Elev= 30
 -7507.7  221.95-4407.64  192.07-429.759  187.71  479.75   195.5 2368.75  143.82
 3508.16   155.4 4047.88  134.88  4831.7  123.44  4838.5  124.46  4978.9   96.46
  5029.1   94.87  5115.4  127.15  5207.1  122.36 5806.95  133.92 6346.67  124.86
 6706.48  137.75 8725.43  128.48 9435.02  155.25 9894.75  183.5710244.51  187.05
10534.31  212.1110714.19  216.5210954.02  200.8811233.83  212.7312542.93  181.13
13981.93  169.4115470.91   220.516780.01  239.7817769.33  229.37 18317.3  240.26
#Mann= 4 ,-1 , 0
 -7507.7      .1       0  4831.7     .05       0  5207.1      .1       0
 18317.3      .1       0
#XS Ineff= 2 ,-1
 5776.11 6594.54  134.02  6792.1 9727.19  137.24
Permanent Ineff=
       F       F
Bank Sta=4838.5,5115.4
XS Rating Curve= 0 ,0
Exp/Cntr=0.3,0.1

Type RM Length L Ch R = 1 ,487693  ,2999,2999,2999
BEGIN DESCRIPTION:
LOWER NUECES 12.5
END DESCRIPTION:
XS GIS Cut Line= 6
      2254107.83     13355518.06      2254678.18     13349604.29
      2252803.18     13347694.57      2251608.62     13343631.95
      2248092.06     13342511.28      2241522.69     13334898.55
#Sta/Elev= 30
 -5735.8   204.3-4012.56  185.36-1076.91  170.07 1.47998  176.26 1159.86   157.3
    2518  157.32 3247.03  140.13 3846.27   139.8 4235.78  121.25 4445.51  131.18
  4900.1  129.44  4953.6  102.99  5026.3   94.45  5141.2  121.22 5943.61  129.81
 5983.55  129.64 6952.32  122.4210613.52  128.4712012.57  189.4112142.52  205.95
 12432.4  196.6212872.23  214.3513871.84  211.6915021.39  177.8815931.04  165.64
17520.41  216.2418510.03  220.1819149.78  238.0420049.43  225.59 20862.5  241.29
#Mann= 4 ,-1 , 0
 -5735.8      .1       0  4953.6     .05       0 5983.55      .1       0
 20862.5      .1       0
#XS Ineff= 2 ,-1
 3400.75  4487.3  131.72 7215.9310716.18  132.21
Permanent Ineff=
       F       F
Bank Sta=4900.1,5943.61
XS Rating Curve= 0 ,0
Exp/Cntr=0.3,0.1

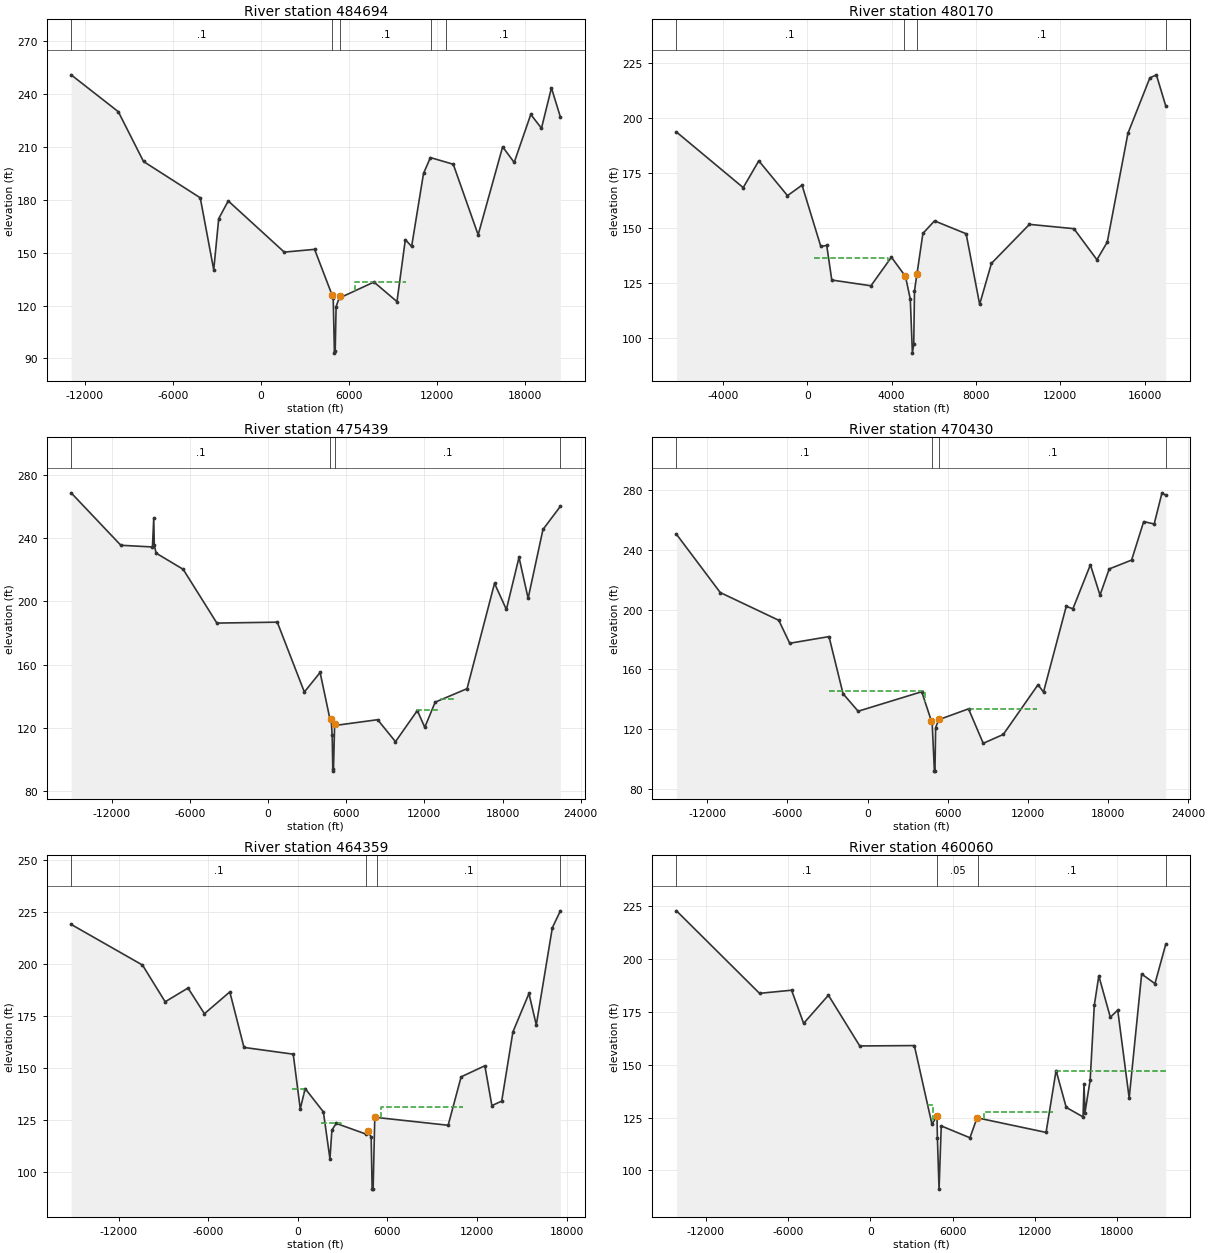
Type RM Length L Ch R = 1 ,484694  ,4524,4524,4524
BEGIN DESCRIPTION:
LOWER NUECES 13.0
END DESCRIPTION:
XS GIS Cut Line= 3
      2270717.07     13347997.42      2247610.95     13341440.96
      2241442.69      13334406.8
#Sta/Elev= 30
-12945.7  251.06-9727.22  230.12-8007.35  201.83-4137.64  181.19-3217.71  140.29
-2877.73  169.37-2227.77  179.42 1591.97  150.34 3661.84  151.91  4860.4  125.83
  4932.7  124.21  5015.6   92.95  5067.8   94.22  5129.9  119.38    5388  125.46
  5393.2   124.4 7711.84  133.34 9281.84  122.22 9851.84   157.410281.84  153.55
11091.84  195.0111561.65  204.0513121.04  200.2614820.38  160.1516489.73  210.17
17279.42  201.2818408.98  228.5719138.69   220.719818.43  243.65 20428.2  227.13
#Mann= 5 ,-1 , 0
-12945.7      .1       0  4860.4     .05       0  5393.2      .1       0
 11571.9     .05       0 12644.7      .1       0
#XS Ineff= 1 ,-1
  6411.1    9873  133.56
Permanent Ineff=
       F
Bank Sta=4860.4,5388
XS Rating Curve= 0 ,0
Exp/Cntr=0.3,0.1

Type RM Length L Ch R = 1 ,480170  ,4731,4731,4731
BEGIN DESCRIPTION:
LOWER NUECES 32.0
END DESCRIPTION:
XS GIS Cut Line= 3
      2264744.18     13342196.16      2260881.49     13341627.42
      2242887.48     13334681.26
#Sta/Elev= 30
 -6197.6  193.53 -3033.6  168.31-2294.67  180.47-934.799  164.68-244.859  169.43
645.0601  141.62  925.04   142.1 1165.02  126.413021.789123.7968 3991.67136.7789
  4656.8  128.08  4886.8  117.79  4986.1   93.26  5050.5   97.31  5085.8  121.33
    5195  128.92  5214.2  129.86  5484.6  147.55 6034.55  153.23  7534.4  147.39
 8174.34   115.4 8734.28  133.9710534.09  151.6512643.79  149.6913733.63  135.62
14223.57  143.5915203.43  192.9316243.28  218.0716553.23  219.46 16994.9  205.41
#Mann= 4 ,-1 , 0
 -6197.6      .1       0  4578.7     .05       0  5214.2      .1       0
 16994.9      .1       0
#XS Ineff= 2 ,-1
  333.33  3812.5  136.54 6145.8315083.33  152.37
Permanent Ineff=
       F       F
Bank Sta=4656.8,5195
XS Rating Curve= 0 ,0
Exp/Cntr=0.3,0.1

Type RM Length L Ch R = 1 ,475439  ,5009,5009,5009
BEGIN DESCRIPTION:
LOWER NUECES 14.0
END DESCRIPTION:
XS GIS Cut Line= 6
       2274568.2     13342900.71      2269974.24     13339245.54
      2259143.42     13335345.15      2253991.44     13335104.88
      2246381.26     13334681.08      2239181.76     13332985.52
#Sta/Elev= 30
-15118.5  268.46  -11302  235.35-8875.59  234.28-8775.66  252.49-8735.68  235.57
-8595.79  230.39-6517.27  220.18-3929.14  186.22   707.5   186.8 2786.09   142.7
3995.539  155.04  4772.3  124.81  4842.4  125.55  4922.5  115.55  4972.3   92.75
  5022.6   94.07  5112.7  122.57  5126.4  121.57    8413  125.229781.631  111.35
11459.95  131.0212029.38   120.412828.58  136.2915276.27  144.8117385.41  211.31
18295.05  194.8119264.67  227.7319964.39  201.8621103.95  245.32 22439.9  259.94
#Mann= 4 ,-1 , 0
-15118.5      .1       0  4772.3     .05       0  5126.4      .1       0
 22439.9      .1       0
#XS Ineff= 2 ,-1
11467.5413113.83  131.4213301.9814430.86  138.12
Permanent Ineff=
       F       F
Bank Sta=4842.4,5112.7
XS Rating Curve= 0 ,0
Exp/Cntr=0.3,0.1

Type RM Length L Ch R = 1 ,470430  ,6071,6071,6071
BEGIN DESCRIPTION:
LOWER NUECES 15.0
END DESCRIPTION:
XS GIS Cut Line= 4
      2272527.58     13337823.83      2262926.17     13332084.34
      2243371.94     13331340.74      2237770.97     13333028.86
#Sta/Elev= 30
-14293.4  250.55-11018.1  211.52-6639.66  192.94-5819.94  177.56-2880.87  182.02
-1830.97  143.79 -701.08  132.054058.449  145.11  4786.8  125.26  4836.9  124.46
    5004   91.94    5047   92.14  5097.1  121.15  5347.3  126.83  5357.3  126.47
7558.109  133.65    8658  110.5610157.85   116.5 12757.6  149.7913167.56  144.88
14867.39  202.2415367.35  200.6516677.24  230.11   17395  209.79 18084.3  227.32
 19758.8  233.25 20664.1  259.03 21447.4  257.41 22032.3  278.28 22310.9  276.61
#Mann= 4 ,-1 , 0
-14293.4      .1       0  4836.9     .05       0  5357.3      .1       0
 22310.9      .1       0
#XS Ineff= 2 ,-1
-2861.11 4305.56  145.32 7539.98 12695.2  133.65
Permanent Ineff=
       F       T
Bank Sta=4786.8,5347.3
XS Rating Curve= 0 ,0
Exp/Cntr=0.3,0.1

Type RM Length L Ch R = 1 ,464359  ,4299,4299,4299
BEGIN DESCRIPTION:
LOWER NUECES 16.0
END DESCRIPTION:
XS GIS Cut Line= 4
      2271233.42     13334239.17      2261619.53     13328631.79
      2246001.28     13326715.37       2240300.5     13328262.31
#Sta/Elev= 30
-15186.5  219.01-10407.1   199.5-8887.18  181.88-7357.25  188.48-6257.27  176.15
-4557.27  186.62 -3607.4  159.98 -308.36  156.74   161.5  130.49491.4004  140.23
1711.029  129.052150.881  106.51 2280.84  120.31 2570.74  123.53  4559.1  118.41
  4669.9  120.01  4911.7  117.04  4975.9   92.11  5042.7   91.99  5153.5  126.47
10068.24  122.6310937.95  145.8712527.21  151.1812996.94  132.0713656.55  134.21
14406.11  167.43 15481.7  185.86   15972  170.74 17046.8  217.39 17585.5  225.52
#Mann= 4 ,-1 , 0
-15186.5      .1       0  4559.1     .05       0  5304.2      .1       0
 17585.5      .1       0
#XS Ineff= 4 ,-1
 -361.11  388.89  139.97 1583.33 2861.11  123.68 5550.3311044.21  131.49
12511.7614581.37  151.11
Permanent Ineff=
       F       F       F       F
Bank Sta=4669.9,5153.5
XS Rating Curve= 0 ,0
Exp/Cntr=0.3,0.1

Type RM Length L Ch R = 1 ,460060  ,5192,5192,5192
BEGIN DESCRIPTION:
LOWER NUECES 17.0
END DESCRIPTION:
XS GIS Cut Line= 6
       2271385.5      13334038.2       2262331.9     13326748.85
      2257346.34     13324695.39      2251999.85     13324740.66
      2243531.48     13324216.47      2238671.82     13324264.05
#Sta/Elev= 30
-14153.5  222.82-8090.48  183.77-5751.85  185.25-4872.37  169.55-3063.43  182.88
-776.349  158.87 3207.98  159.05  4490.4  121.87  4860.4  125.63  4890.4  115.28
  5010.7   91.11  5170.5  121.03  7265.6  115.417785.301  124.91 7835.27   124.8
12822.34  117.9513551.92  147.2514291.48   129.815520.76  125.2915590.72  140.95
15660.68  127.3416040.46  142.8316340.28  178.0716670.09  192.0417510.08  172.46
18050.08  175.82 18886.9  134.21 19796.9  192.92   20767  188.36 21552.9  206.92
#Mann= 4 ,-1 , 0
-14153.5      .1       0  4890.4     .05       0 7835.27      .1       0
 21552.9      .1       0
#XS Ineff= 3 ,-1
 4164.35  4539.7  130.88 8305.5613305.56  127.8213535.71 21552.9  147.02
Permanent Ineff=
       T       T       T
Bank Sta=4860.4,7785.301
XS Rating Curve= 0 ,0
Exp/Cntr=0.3,0.1

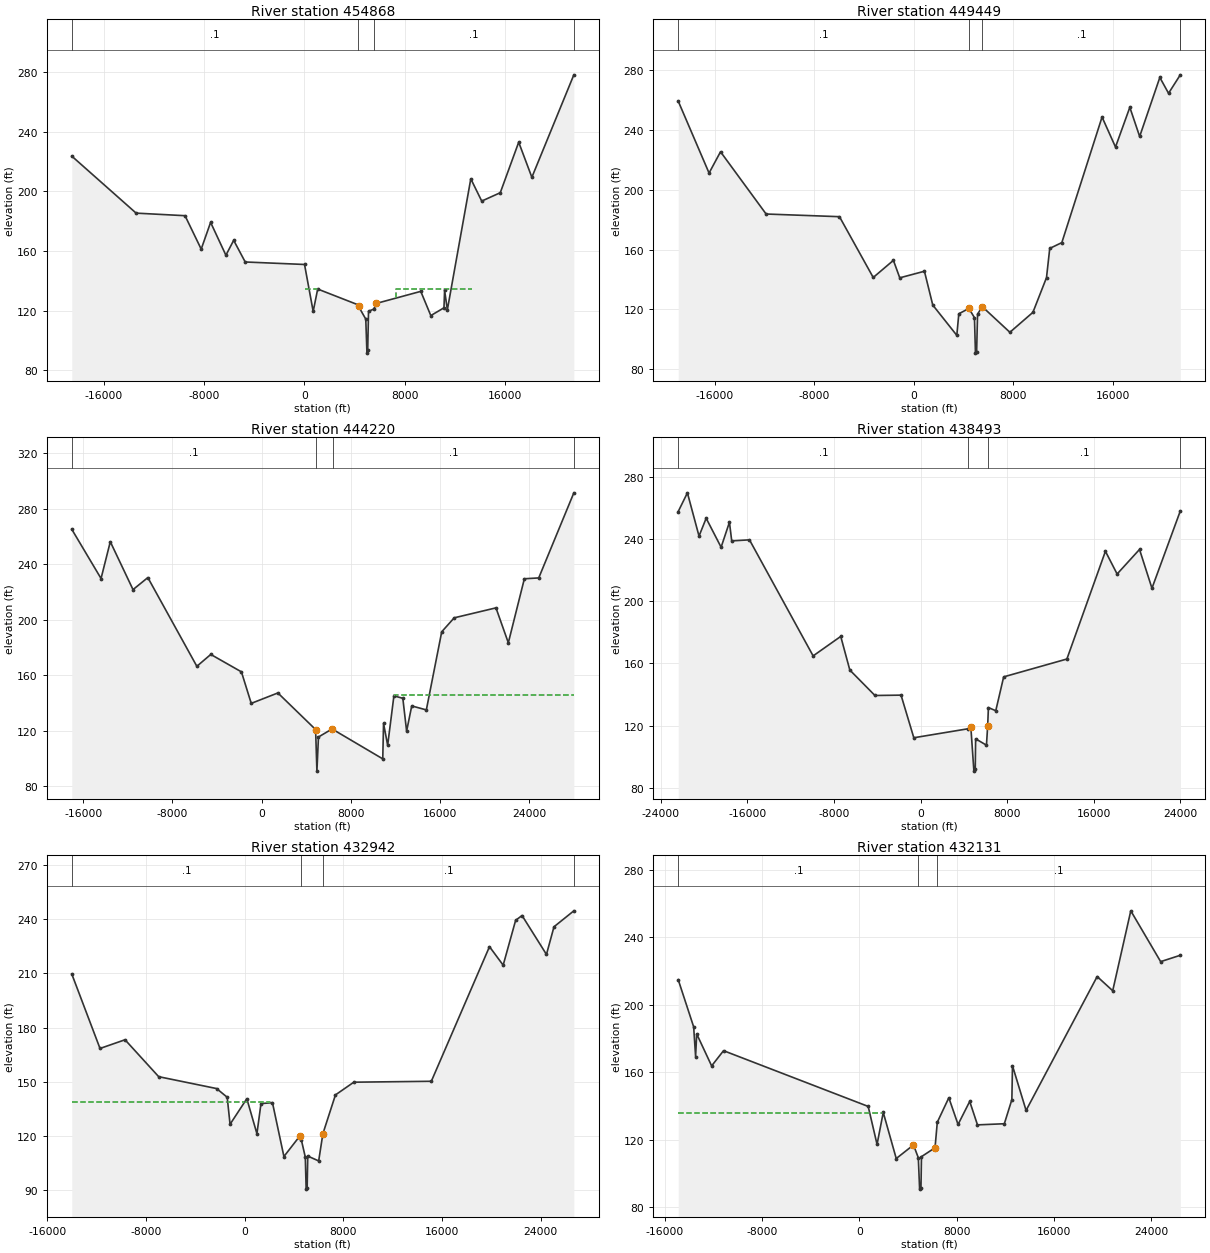
Type RM Length L Ch R = 1 ,454868  ,5419,5419,5419
BEGIN DESCRIPTION:
LOWER NUECES 18.0
END DESCRIPTION:
XS GIS Cut Line= 4
      2271813.07     13333750.38      2258738.24     13321883.22
       2243476.5     13318163.21      2237853.25     13314581.57
#Sta/Elev= 30
-18538.8  223.52-13407.7   185.3-9508.38  183.58-8218.59  161.18-7468.71   179.1
-6248.91  157.08-5629.01  167.07-4709.16  152.5520.06055  150.88709.9707   119.4
 1069.93  134.41 4321.66  123.73 4329.52  122.71  4903.6  114.27  4997.4   91.45
    5058   93.59  5122.7  119.47  5539.7  120.99 5749.35  124.78  9288.9  132.85
 10088.8  116.6311138.67  121.8211188.67  133.5711408.64  120.46 13278.4   208.3
 14148.3  193.3715627.97  198.99 17097.4  232.8318146.99  209.32 21494.1  278.01
#Mann= 4 ,-1 , 0
-18538.8      .1       0 4321.66     .05       0  5539.7      .1       0
 21494.1     .05       0
#XS Ineff= 2 ,-1
   43.69  1070.7  134.65 7281.2813396.05  134.29
Permanent Ineff=
       T       T
Bank Sta=4329.52,5749.35
XS Rating Curve= 0 ,0
Exp/Cntr=0.3,0.1

Type RM Length L Ch R = 1 ,449449  ,5229,5229,5229
BEGIN DESCRIPTION:
LOWER NUECES 19.0
END DESCRIPTION:
XS GIS Cut Line= 4
      2276000.67     13327859.29      2263788.46       13319789.
      2248244.26     13312762.45      2239678.69     13311917.38
#Sta/Elev= 30
  -18912  259.27-16437.3  211.17-15517.4  225.41  -11858  183.77-5968.87  181.98
-3259.21  141.31 -1639.3  152.77-1129.32  141.08850.6309  145.491520.619  122.86
 3450.57   102.6 3610.57  117.034420.551  120.58  4867.1  114.44  4947.2   90.71
  5039.9   91.21  5114.7  116.72 5490.52  121.827710.471  104.65 9560.42     118
10650.39  141.2210910.39  160.7611880.36  164.6415109.43  248.6416189.01  228.57
17338.56  255.1418128.25  235.6319747.62  275.1220447.35  264.53 21391.6  276.88
#Mann= 5 ,-1 , 0
  -18912      .1       04420.551     .05       0 5490.52      .1       0
 21391.6     .16       0 21391.6     .05       0
Bank Sta=4420.551,5490.52
XS Rating Curve= 0 ,0
Exp/Cntr=0.3,0.1

Type RM Length L Ch R = 1 ,444220  ,5727,5727,5727
BEGIN DESCRIPTION:
LOWER NUECES 20.0
END DESCRIPTION:
XS GIS Cut Line= 4
       2276554.9     13327912.23      2267877.33     13318496.98
      2249848.12      13307748.9      2238643.43     13306720.67
#Sta/Elev= 30
-17034.8  265.27-14408.2  229.74-13578.5   256.3-11539.5  221.73-10210.1   230.4
-5812.14  166.37-4562.72  174.94-1812.88  162.36-932.879  139.611457.119  147.14
  4842.4  120.73  4958.9   90.71  5097.4  115.346327.119  121.186407.119  120.73
10867.12   99.5610937.12  125.1511307.12  109.3911867.12  145.0212667.12   143.3
13007.12  119.5813467.12  137.7714777.12  134.8916157.12  191.2817276.72  201.36
21023.79  208.5522132.92  183.33 23571.8  229.5524860.79  230.16   28011  291.58
#Mann= 4 ,-1 , 0
-17034.8      .1       0  4842.4     .05       06407.119      .1       0
   28011     .05       0
#XS Ineff= 1 ,-1
   11875   28011  145.79
Permanent Ineff=
       T
Bank Sta=4842.4,6327.119
XS Rating Curve= 0 ,0
Exp/Cntr=0.3,0.1

Type RM Length L Ch R = 1 ,438493  ,5551,5551,5551
BEGIN DESCRIPTION:
LOWER NUECES 21.0
END DESCRIPTION:
XS GIS Cut Line= 4
      2277560.43     13328471.23      2268847.66     13315728.97
      2248353.13     13302463.18      2241840.96      13302248.7
#Sta/Elev= 30
-22377.1   257.6-21530.3  269.61-20457.4  241.79-19797.6  253.27-18417.9  234.64
-17648.1  250.72-17438.2  238.71-15798.6  239.39-9920.09  164.78-7370.74   177.3
-6530.96  155.69-4211.51  139.33-1802.02  139.56-622.269  112.16 4416.65  117.98
  4645.7  118.86  4926.4   90.71  5050.6   91.76  5086.9  111.476086.289  107.39
6198.381  119.68 6266.25  131.57  6946.1  129.547675.949   151.313514.15  162.78
17072.76  232.0418152.07  217.4220220.45  233.2221369.55  208.27 23988.1  257.95
#Mann= 4 ,-1 , 0
-22377.1      .1       0 4416.65     .05       0 6266.25      .1       0
 23988.1      .1       0
Bank Sta=4645.7,6198.381
XS Rating Curve= 0 ,0
Exp/Cntr=0.3,0.1

Type RM Length L Ch R = 1 ,432942  ,811,811,811
XS GIS Cut Line= 5
  2276258.09628913316826.7100224 2269078.301594113306787.4276076
 2257185.940536313306744.0248072 2248331.773861513301926.3162668
 2241951.565493313301579.0941922
#Sta/Elev= 30
-14028.8  209.64-11739.3  168.46-9710.63  173.27-6982.35  152.87-2285.15   146.3
-1425.66  141.48-1195.81  126.55163.3301  140.69982.7998  121.35 1312.59  137.99
    2242   138.53171.449  108.734480.689  120.234590.619  117.75  4904.3  108.43
  4974.1   90.71  5054.3   91.21  5104.3  108.975989.801   106.3  6329.6   121.3
    7349  142.798838.131  149.8215122.52  150.3219837.85  224.7320947.38   214.5
21957.38  239.2822477.38  241.9524457.38  220.4325067.38  235.7226677.38  244.54
#Mann= 4 ,-1 , 0
-14028.8      .1       04590.619     .05       0  6329.6      .1       0
26677.38      .1       0
#XS Ineff= 2 , 0
         2083.33  138.74
Permanent Ineff=
       F       F
Bank Sta=4480.689,6329.6
XS Rating Curve= 0 ,0
Exp/Cntr=0.3,0.1

Type RM Length L Ch R = 1 ,432131  ,10066,10066,10066
BEGIN DESCRIPTION:
LOWER NUECES 22.0
END DESCRIPTION:
XS GIS Cut Line= 6
      2276804.01     13316553.07      2269251.91     13305745.76
      2257316.15     13306136.39      2251066.15     13302750.97
      2248505.38     13301579.09       2242255.4     13301058.26
#Sta/Elev= 30
  -14911   214.9-13641.5  186.95-13481.6  169.37-13391.6  182.76-12162.1   163.8
-11182.5  172.82721.9902  139.76 1451.49  117.251961.189   136.23030.561  108.86
 4449.73  116.91  4846.6  109.33  4954.5   90.71  5065.7   91.45  5106.8  109.97
  6223.2  115.25 6408.58  130.377358.029   144.9 8117.58  129.06 9077.02  142.73
9716.641  128.8211926.35  129.4912546.35  143.7912596.35  163.8913716.35   137.4
19566.35   216.820845.52  208.3722333.77  255.7724790.89  225.6326408.99  229.41
#Mann= 3 ,-1 , 0
  -14911      .1       0  4846.6     .05       0 6408.58      .1       0
#XS Ineff= 2 , 0
         1944.44  136.12 7361.11          144.26
Permanent Ineff=
       F       F
Bank Sta=4449.73,6223.2
XS Rating Curve= 0 ,0
Exp/Cntr=0.3,0.1