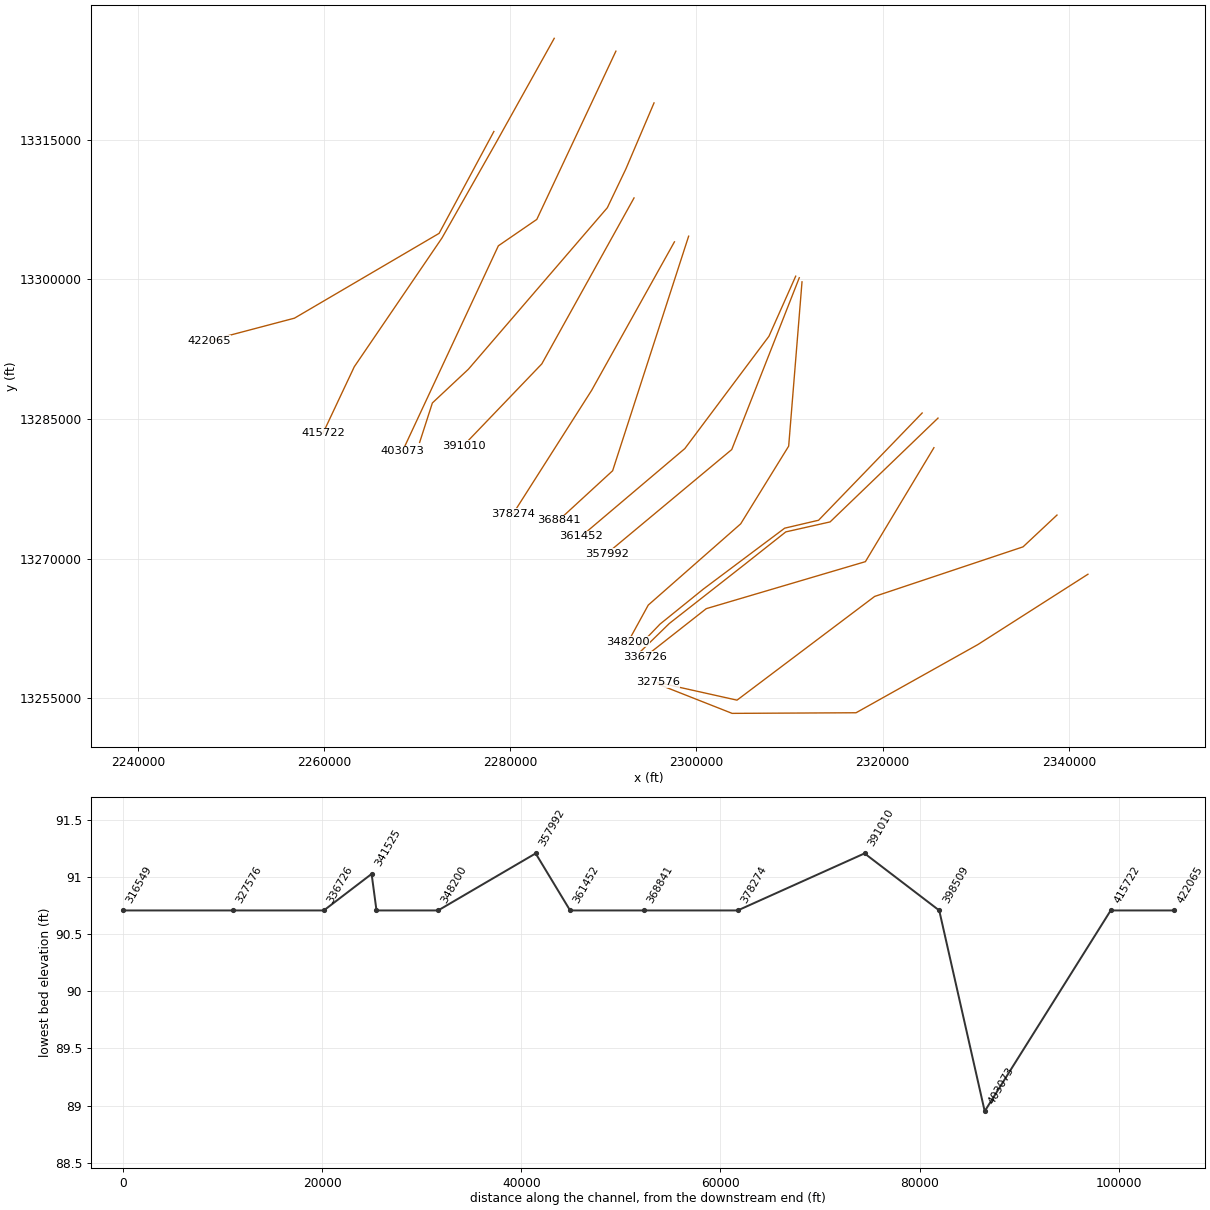
HEC-RAS study NUECES RIVER.prj: NUECES RIVER Base Level Engineering

--- NUECES RIVER.g01 (geometry) --- (continued)

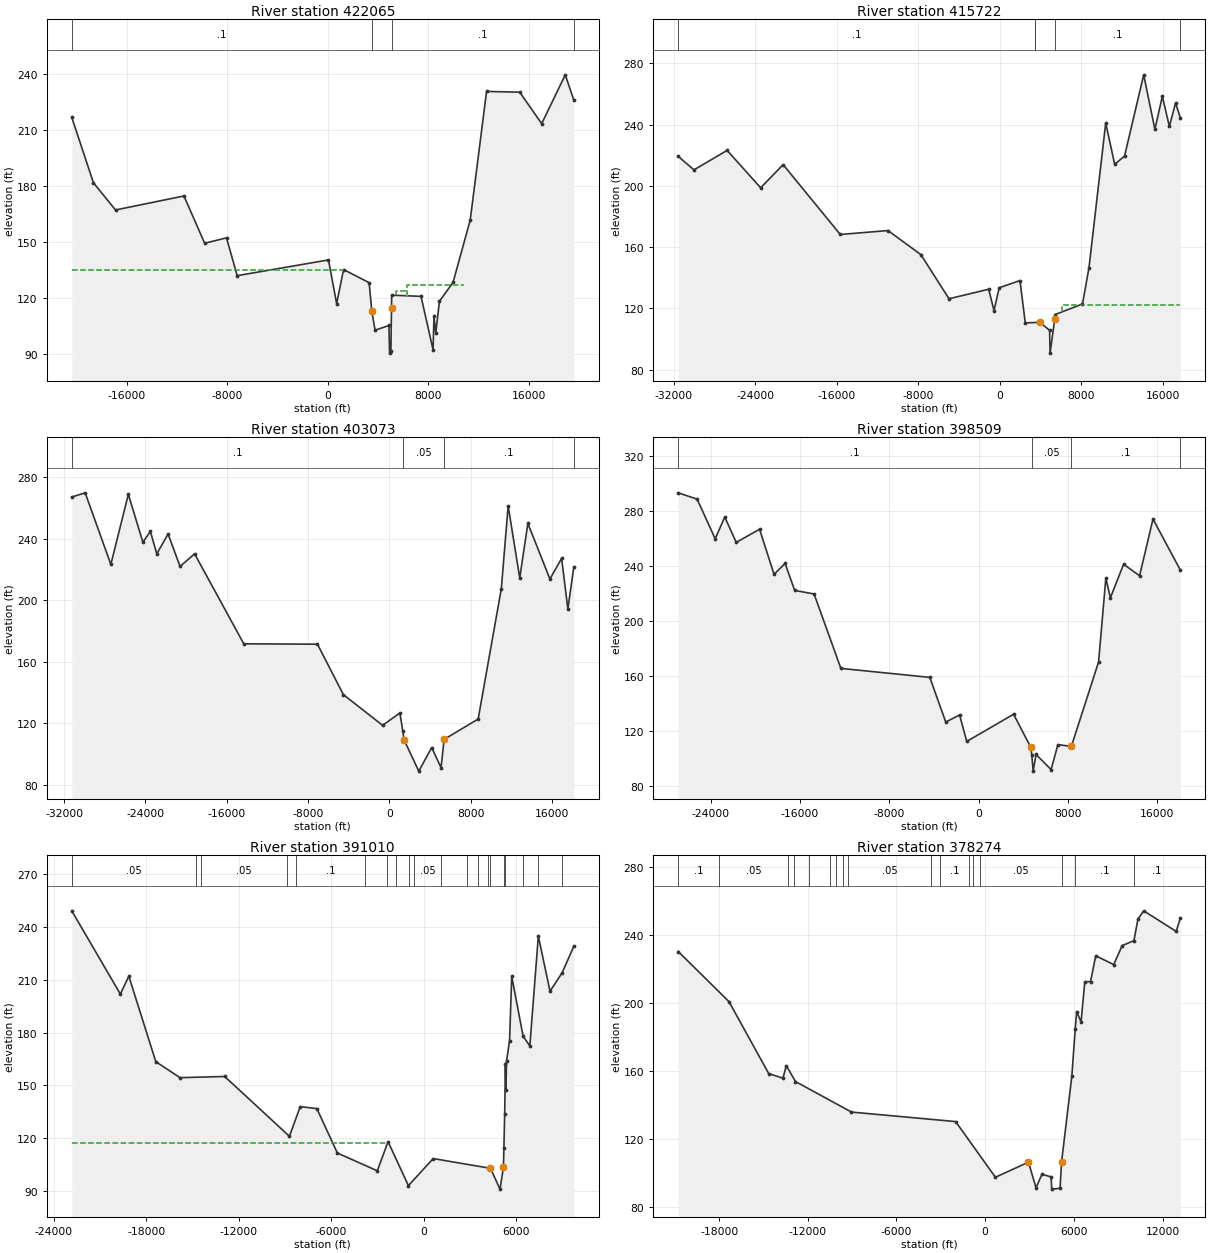
Type RM Length L Ch R = 1 ,422065  ,6343,6343,6343
BEGIN DESCRIPTION:
LOWER NUECES 23.0
END DESCRIPTION:
XS GIS Cut Line= 4
      2278236.05     13315911.93      2272354.17     13304960.33
      2256818.94     13295842.59      2247613.62     13293411.62
#Sta/Elev= 30
-20362.7  216.71-18638.2  181.74-16879.4  167.21-11433.3  174.69 -9784.5  149.42
-8045.69   152.3-7196.05   132.171.10938  140.51720.8594  117.151270.641  135.38
 3309.84  128.34 3519.76  113.14 3779.66  102.95    4885  105.49  4934.7   90.71
  5039.3   91.58  5088.1  115.04  5103.8  121.68 7438.23  121.048397.859   92.46
 8467.83  110.52 8607.77  101.51 8907.66  118.47 9987.23  128.4911355.95  161.86
12654.73  230.5515292.67  230.15 17041.3  213.3318919.83  239.42 19602.6  225.89
#Mann= 4 ,-1 , 0
-20362.7      .1       0  3503.6     .05       0  5103.8      .1       0
 19602.6     .05       0
#XS Ineff= 3 ,-1
-20362.7 1326.43  135.38 5410.88  6298.9  123.74 6307.8710873.55  127.12
Permanent Ineff=
       F       F       F
Bank Sta=3519.76,5088.1
XS Rating Curve= 0 ,0
Exp/Cntr=0.3,0.1

Type RM Length L Ch R = 1 ,415722  ,12649,12649,12649
BEGIN DESCRIPTION:
LOWER NUECES 24.0
END DESCRIPTION:
XS GIS Cut Line= 5
      2284719.35     13325927.24      2278439.51     13314655.68
      2272663.64     13304465.45      2263244.02     13290622.51
      2259868.52     13283450.69
#Sta/Elev= 30
-31564.2   219.2-30020.8  210.38-26762.6  223.09-23474.4  198.66-21265.6  213.79
-15658.8  168.18-10971.6  170.75 -7743.5  155.02-4984.74  126.23-1086.26  132.43
 -566.46  118.43-56.6601  133.381982.539  138.11 2502.34  110.463911.789   110.8
    4889  105.65  4939.6   90.71  5399.9  113.27  5406.8  115.858120.141  122.79
8759.891  146.6110399.25  240.9811278.91  214.0512248.53  219.3614127.79  272.44
15227.36  236.8215957.08   258.416646.81  238.7617256.57  253.98 17722.3  244.51
#Mann= 5 ,-1 , 0
-31564.2      .1       0 3458.33     .05       0 3458.33     .05       0
  5406.8      .1       0 17722.3     .05       0
#XS Ineff= 2 , 0
                            6125          121.89
Permanent Ineff=
       F       F
Bank Sta=3911.789,5399.9
XS Rating Curve= 0 ,0
Exp/Cntr=0.3,0.1

Type RM Length L Ch R = 1 ,403073  ,4564,4564,4564
BEGIN DESCRIPTION:
LOWER NUECES 25.0
END DESCRIPTION:
XS GIS Cut Line= 4
      2291342.07     13324548.07      2282845.43     13306459.17
      2278718.88     13303623.74      2268406.61     13281513.13
#Sta/Elev= 30
-31249.5  267.09-29930.9   269.8-27404.9  223.28-25685.3  268.81-24255.7  237.75
-23515.9  244.68  -22886  230.14-21776.3  243.06-20596.6  221.97  -19167  230.16
-14328.2  171.68-7081.32  171.44-4532.08  138.67-672.699   118.71027.039  126.74
 1316.99  114.991436.971   109.3 2885.46   88.954156.961  104.235076.961   91.21
5376.961  109.588726.961  122.7911006.96  207.5211676.96  261.3712816.96  214.47
13616.96  249.9415786.96  213.7816936.96  227.23 17550.6  194.33 18139.5  221.77
#Mann= 4 ,-1 , 0
-31249.5      .1       0 1316.99     .05       05376.961      .1       0
 18139.5      .1       0
Bank Sta=1436.971,5376.961
XS Rating Curve= 0 ,0
Exp/Cntr=0.3,0.1

Type RM Length L Ch R = 1 ,398509  ,7499,7499,7499
BEGIN DESCRIPTION:
LOWER NUECES 26.0
END DESCRIPTION:
XS GIS Cut Line= 6
      2295438.66     13318985.92       2292416.2      13311889.8
      2290421.77     13307714.58      2275503.05     13290356.84
       2271631.1     13286728.46      2270262.18     13282488.16
#Sta/Elev= 30
-26907.4  293.07-25213.1  288.47  -23597  259.67-22737.7  275.47-21708.7  257.02
-19620.6   266.6-18321.5  233.83-17332.2  241.71-16472.7  222.09-14733.7  219.52
-12334.1  165.41-4364.63  158.87-2934.71  126.39-1694.78  131.52-1054.82  112.29
3144.939  132.09  4679.9  108.06  4772.1  102.68  4899.2   90.71  5155.1  102.82
6504.781   91.867114.781  109.98  8320.7   108.7 10758.1  170.05 11409.2  230.93
 11819.5  216.76 13001.1  241.13   14434  232.79 15635.2     274 18082.8  236.93
#Mann= 4 ,-1 , 0
-26907.4      .1       0  4772.1     .05       0  8320.7      .1       0
 18082.8     .05       0
Bank Sta=4679.9,8320.7
XS Rating Curve= 0 ,0
Exp/Cntr=0.3,0.1

Type RM Length L Ch R = 1 ,391010  ,12736,12736,12736
BEGIN DESCRIPTION:
LOWER NUECES 27.0
END DESCRIPTION:
XS GIS Cut Line= 3
      2293290.23     13308768.83      2283385.91     13290927.65
      2274973.58     13282145.09
#Sta/Elev= 30
-22845.4  248.99-19694.6  201.79-19144.7  211.93  -17395  163.47-15825.4  154.41
-12925.9  155.07-8726.81  121.16-8026.95  137.98-6947.16  136.85-5617.42  111.69
-3027.93  101.61-2328.11  118.11-1009.11    93.2599.6602  108.54  4314.3  103.01
  4932.5   91.21  5155.9   103.6  5184.2  114.68  5236.3  133.73  5283.3  162.18
  5318.5  147.59    5354  163.73  5551.9  175.29  5693.4  211.81  6431.7  177.87
  6867.4  172.42  7418.3  234.62    8176  203.43  8956.8  213.78    9722  228.95
#Mann= 20 ,-1 , 0
-22845.4     .05       0  -14815      .1       0-14436.8     .05       0
   -8879      .1       0 -8308.8      .1       0 -3841.2      .1       0
 -2409.6     .05       0 -1807.7      .1       0  -957.7      .1       0
  -674.8     .05       0  1128.8     .05       0  2793.6      .1       0
  3479.5      .1       0    4169     .16       0  4314.3     .05       0
  5184.2     .12       0  5236.3      .1       0  6431.7     .05       0
  7418.3     .05       0  8956.8      .1       0
#XS Ineff= 2 , 0
         -2437.5  117.47
Permanent Ineff=
       F       F
Bank Sta=4314.3,5155.9
XS Rating Curve= 0 ,0
Exp/Cntr=0.3,0.1

Type RM Length L Ch R = 1 ,378274  ,9433,9433,9433
BEGIN DESCRIPTION:
LOWER NUECES 33.0
END DESCRIPTION:
XS GIS Cut Line= 3
      2297630.85     13304049.78      2288733.26     13288077.52
      2280313.79     13274840.73
#Sta/Elev= 30
-20766.7  230.34-17331.2  200.88-14642.2  158.58-13682.5  155.93-13452.6  163.29
-12832.8  153.94-9044.35  135.99-1997.01  130.41692.4609   97.682932.029  106.55
 3441.93   91.47 3841.85   99.44    4462    97.9  4504.6   90.71  5068.3   91.21
 5166.67  106.46  5865.9  157.19  6095.4  185.08  6192.7     195    6489  188.99
  6742.3  212.63  7127.5   212.6  7482.3  227.82  8698.2  222.68  9271.5  233.82
 10066.8  236.74 10335.8  249.32   10727  254.26 12922.6  242.18 13204.2  249.85
#Mann= 17 ,-1 , 0
-20766.7      .1       0  -18035     .05       0-13337.2     .05       0
-12960.1      .1       0-11930.3     .05       0-10464.6      .1       0
-10120.1     .05       0 -9616.3      .1       0 -9285.6     .05       0
 -3680.9      .1       0 -3058.6      .1       0 -1089.2     .16       0
  -791.7      .1       0 -361.11     .05       0 5166.67     .16       0
  6095.4      .1       0 10066.8      .1       0
Bank Sta=2932.029,5166.67
XS Rating Curve= 0 ,0
Exp/Cntr=0.3,0.1

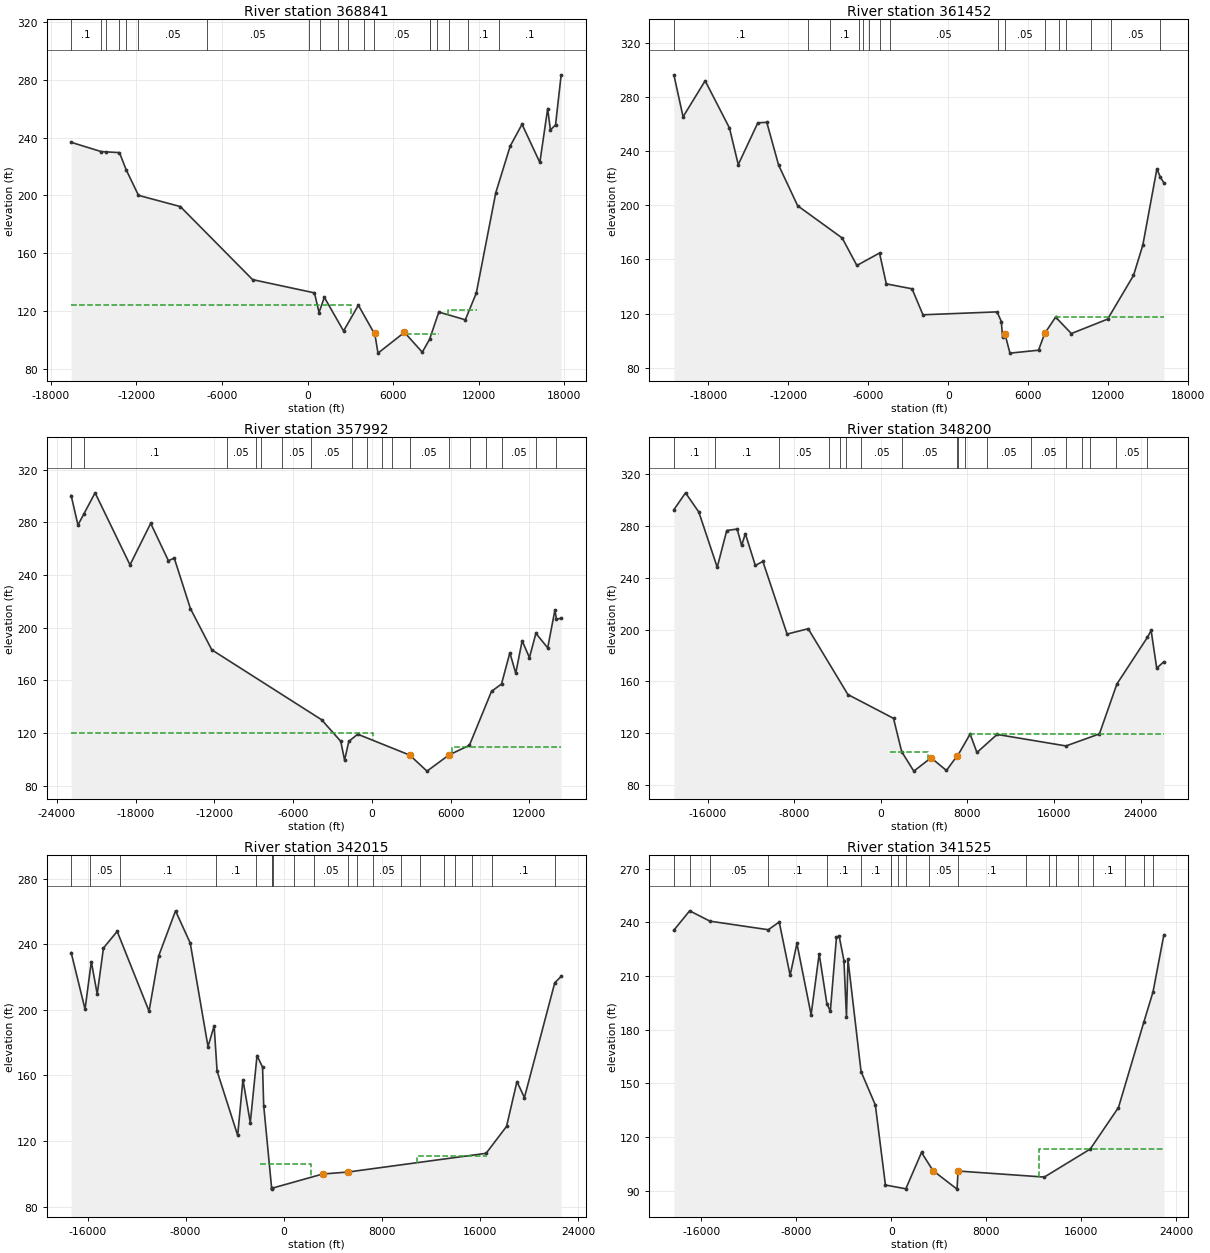
Type RM Length L Ch R = 1 ,368841  ,7389,7389,7389
BEGIN DESCRIPTION:
LOWER NUECES 28.0
END DESCRIPTION:
XS GIS Cut Line= 3
      2299155.64     13304656.33      2290992.37     13279439.74
        2285213.      13274121.6
#Sta/Elev= 30
-16577.2  236.84-14478.1  230.43-14114.9  230.22-13189.5   229.7-12723.2  217.86
-11856.4  200.07-8924.48  192.31-3855.47  141.66483.6797  132.48803.6191  118.86
1173.539  129.412523.279  106.09 3563.08  123.92  4636.4  105.09  4700.4     105
  4937.9   90.716792.449  105.118042.199   91.36  8555.7  100.31 9201.98  119.17
11060.95  113.8211830.35  132.3113199.28  201.9714208.49  234.2515037.84  249.34
16286.87  222.8616836.44  260.2517026.29  245.4117386.01  248.86 17781.7  283.62
#Mann= 19 ,-1 , 0
-16577.2      .1       0-14478.1     .16       0-14114.9      .1       0
-13189.5     .05       0-12723.2      .1       0-11856.4     .05       0
 -7086.2     .05       0    66.2      .1       0   904.6      .1       0
  2137.3     .16       0  2831.9      .1       0  3974.8      .1       0
  4636.4     .05       0  8555.7     .16       0  8555.7     .16       0
    9108     .05       0  9943.9     .16       0 11236.1      .1       0
   13438      .1       0
#XS Ineff= 3 ,-1
-16577.2 3071.43  123.75 6942.62 9238.01  103.96 9840.0811872.06  120.56
Permanent Ineff=
       F       F       F
Bank Sta=4700.4,6792.449
XS Rating Curve= 0 ,0
Exp/Cntr=0.3,0.1

Type RM Length L Ch R = 1 ,361452  ,3460,3460,3460
BEGIN DESCRIPTION:
LOWER NUECES 29.0
END DESCRIPTION:
XS GIS Cut Line= 4
      2310655.19     13300356.51      2307783.11     13293899.17
      2298748.68     13281822.65       2287611.6     13272383.32
#Sta/Elev= 30
-20574.3  296.41-19885.2   265.4-18228.8  292.02-16406.6  257.16-15746.8  230.05
-14277.4  260.95-13607.7   261.3-12718.1  229.64-11288.9  199.61 -7950.7  175.79
-6851.28   155.5-5152.18   164.7-4642.45   141.9-2713.55  138.25-1894.03  119.05
 3663.93   121.2 3983.93  114.08  4077.4  102.36 4253.65   104.9  4630.2   90.71
  6773.2   92.87 7234.81  105.22 8053.93  117.34 9233.93  105.1811953.93  115.84
13893.93  148.0914593.93  170.51 15649.3  226.87 15912.9  220.72   16174  216.52
#Mann= 16 ,-1 , 0
-20574.3      .1       0-10479.7     .05       0 -8844.1      .1       0
 -6689.6      .1       0 -6391.8      .1       0 -5918.6      .1       0
 -5080.5     .05       0 -4380.8     .05       0    3739      .1       0
 4253.65     .05       0 7234.81     .16       0  8291.3     .16       0
  8845.6     .16       0 10731.3     .05       0 12183.9     .05       0
 15912.9      .1       0
#XS Ineff= 2 , 0
                         8096.47          117.33
Permanent Ineff=
       F       F
Bank Sta=4253.65,7234.81
XS Rating Curve= 0 ,0
Exp/Cntr=0.3,0.1

Type RM Length L Ch R = 1 ,357992  ,9792,9792,9792
BEGIN DESCRIPTION:
LOWER NUECES 30.0
END DESCRIPTION:
XS GIS Cut Line= 3
      2311040.05     13300187.55      2303785.08     13281717.84
       2290351.6     13270518.09
#Sta/Elev= 30
-22905.6  300.29-22388.5  277.89-21952.4  286.05-21082.1  302.32-18423.3  247.67
-16845.8  279.17-15499.3  250.86-15049.5  252.77-13819.9  214.51-12190.4  183.22
-3823.35  130.18-2363.64  113.79-2073.64   99.49-1753.64  113.76-1073.64  119.22
2887.359  103.37  4204.3   91.215866.359  103.397436.359   110.8  9120.8  151.74
  9882.7  157.28 10519.1  180.99 10966.8  165.49 11456.3   190.1 12010.8  177.28
 12502.7  195.76 13402.2  184.71 13948.9  213.28 14070.5  206.41 14427.7  207.23
#Mann= 18 ,-1 , 0
-22905.6      .1       0-21952.4      .1       0-11065.2     .05       0
 -8851.8     .05       0 -8415.5      .1       0 -6838.3     .05       0
   -4624     .05       0 -1478.1      .1       0    -394     .05       0
   793.9     .05       0  1575.7      .1       0 2888.89     .05       0
5866.359     .05       0  7456.1      .1       0  8673.5     .05       0
  9882.7     .05       0 12502.7     .05       0 14070.5     .08       0
#XS Ineff= 2 , 0
           61.15  120.11 6119.47          109.77
Permanent Ineff=
       F       F
Bank Sta=2887.359,5866.359
XS Rating Curve= 0 ,0
Exp/Cntr=0.3,0.1

Type RM Length L Ch R = 1 ,348200  ,6185,6185,6185
BEGIN DESCRIPTION:
LOWER NUECES 31.0
END DESCRIPTION:
XS GIS Cut Line= 5
      2311333.38     13299748.98      2309900.79     13282085.77
      2304746.71     13273730.73      2294818.33     13264995.93
      2292648.19     13261035.43
#Sta/Elev= 30
-19118.3  292.67-18041.5  305.71-16812.1  290.85  -15113  248.19-14233.4  276.59
-13273.9  277.74-12854.1  265.07-12514.2  274.21-11594.7  249.59  -10895  252.72
-8656.15  196.59 -6707.1  200.72 -3038.9  149.88  1175.6   131.5  1932.5  105.72
  3052.3   90.714647.881  100.99 6067.32   91.217046.939   102.4 7076.93  102.23
8256.471  119.388886.211  105.1110745.45  119.0617112.91  110.17 20201.7  119.47
   21821  158.05 24631.1  193.99 24981.4   199.4 25496.7  170.31 26159.7  175.19
#Mann= 18 ,-1 , 0
-19118.3      .1       0-15296.7      .1       0 -9425.8     .05       0
 -4744.4      .1       0 -3812.7     .05       0 -3173.7      .1       0
 -1792.2     .05       0  1932.5     .05       0 7076.93     .16       0
  7134.6      .1       0  7785.8      .1       0  9785.4     .05       0
 13920.4     .05       0 17141.6      .1       0 18605.9      .1       0
 19372.4      .1       0 21723.2     .05       0 24631.1      .1       0
#XS Ineff= 2 ,-1
  884.29 4317.97  105.17 8316.09 26159.7  119.35
Permanent Ineff=
       F       F
Bank Sta=4647.881,7046.939
XS Rating Curve= 0 ,0
Exp/Cntr=0.3,0.1

Type RM Length L Ch R = 1 ,342015  ,490,490,490
BEGIN DESCRIPTION:
LOWER NUECES 34.0
END DESCRIPTION:
XS GIS Cut Line= 6
      2324237.14     13285647.32      2313112.51     13274117.32
       2309470.9     13273265.02      2300734.37     13266714.71
       2296080.4     13262949.29      2293799.75     13260577.81
#Sta/Elev= 30
-17335.7  234.89-16204.3  200.39-15691.8  229.39  -15212  209.58-14702.3  237.69
-13582.9  247.82-10984.2  199.18-10194.6  232.96-8825.35  260.35-7625.94   240.7
-6176.65  177.56 -5676.9  190.21-5437.02   162.7-3757.85  123.49-3328.06  157.41
-2728.36   131.2-2178.63  172.14 -1727.5  164.99 -1635.4   141.6  -987.1   91.21
  -984.4   90.71  -981.1   91.21 3170.58   99.91  5273.6  101.1716498.82  112.53
18167.65  128.9319017.06  156.2819625.95  146.51 22102.6  216.55 22622.4  220.34
#Mann= 20 ,-1 , 0
-17335.7     .05       0-15827.1     .05       0-13363.2      .1       0
   -5503      .1       0 -2249.9      .1       0  -987.1     .07       0
  -981.1      .1       0  -865.8     .05       0   836.7     .05       0
  2428.8     .05       0  5273.6     .07       0  5939.7      .1       0
  7241.9     .05       0  9551.8     .05       0 11143.2      .1       0
 13028.5      .1       0 13934.1      .1       0 15339.9     .05       0
 17005.2      .1       0 22102.6      .1       0
#XS Ineff= 2 ,-1
-1937.91 2248.35  106.0510868.06 16562.5  111.02
Permanent Ineff=
       F       F
Bank Sta=3170.58,5273.6
XS Rating Curve= 0 ,0
Exp/Cntr=0.3,0.1

Type RM Length L Ch R = 1 ,341525  ,4799,4799,4799
BEGIN DESCRIPTION:
LOWER NUECES 35.0
END DESCRIPTION:
XS GIS Cut Line= 6
      2325940.88     13285099.72      2314350.22     13273938.61
       2309592.1     13272864.13      2305235.51     13269415.42
      2297086.95     13263023.36      2293942.11     13259954.09
#Sta/Elev= 30
-18311.1  235.58-16983.6  246.38-15264.7   240.6-10355.5  235.82 -9438.1  240.16
 -8518.9  210.37 -7945.9  228.17 -6750.7  188.34 -6071.8   222.4 -5423.5  194.58
 -5131.2  190.32 -4614.9  231.72 -4388.5  232.24 -3985.4  218.63 -3773.1  186.96
   -3646  219.32 -2544.4  156.65-1340.68     138-491.019   93.331228.301   91.21
2547.789   111.5 3517.24  101.37 5540.92   91.03  5627.2  101.1412892.65   97.76
16761.14   113.419139.76  136.59 21286.7  184.48 22050.5  201.12 22964.9  233.05
#Mann= 20 ,-1 , 0
-18311.1      .1       0-16983.6     .05       0-15264.7     .05       0
-10355.5      .1       0 -5423.5      .1       0 -2544.4      .1       0
    -6.4    .033       0     -.4     .05       0   537.2     .05       0
  1282.1      .1       0  3213.6     .05       0  5627.2      .1       0
 11365.4      .1       0 13282.6     .05       0   13868      .1       0
 15708.9     .05       0 16958.3      .1       0 19679.3      .1       0
 21286.7      .1       0 22050.5      .1       0
#XS Ineff= 2 ,-1
-18311.1 2534.72  111.1112410.71 22964.9  113.56
Permanent Ineff=
       F       F
Bank Sta=3517.24,5627.2
XS Rating Curve= 0 ,0
Exp/Cntr=0.3,0.1

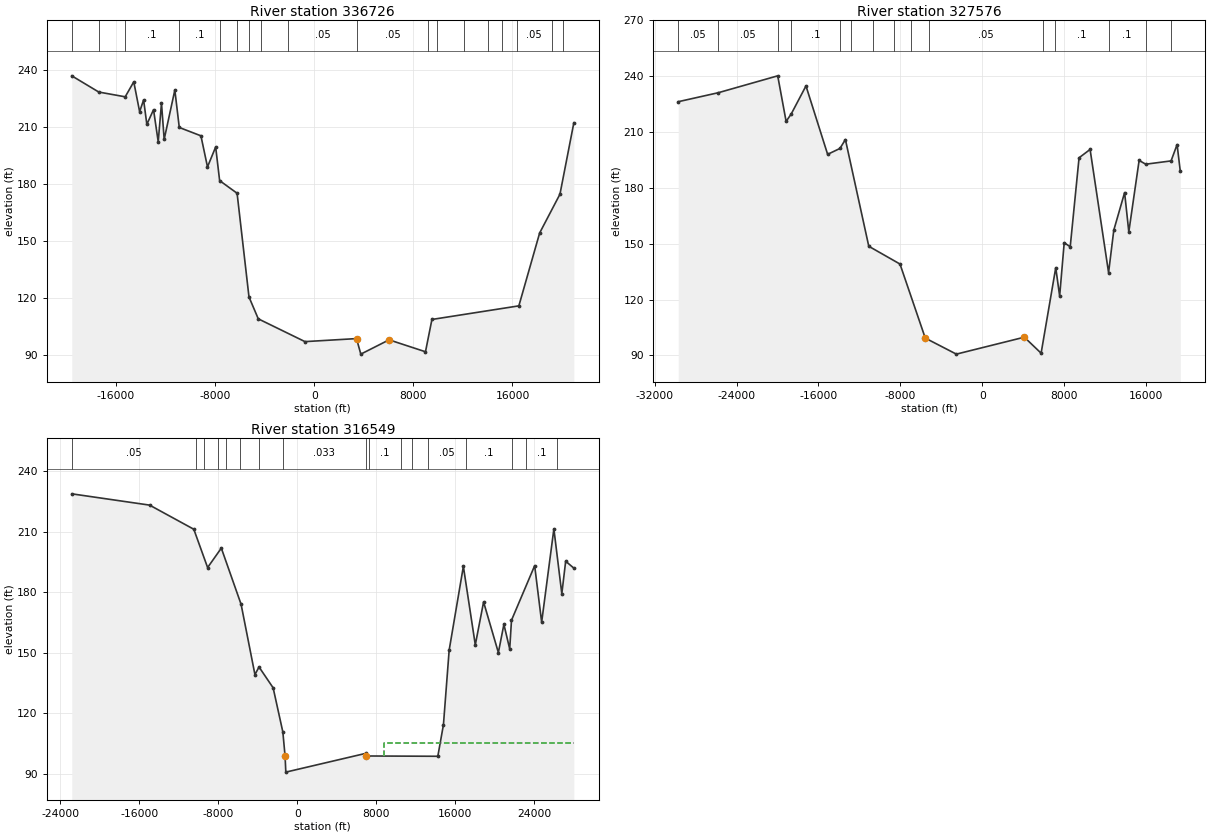
Type RM Length L Ch R = 1 ,336726  ,9150,9150,9150
BEGIN DESCRIPTION:
LOWER NUECES 37.0
END DESCRIPTION:
XS GIS Cut Line= 4
      2325502.29      13281916.8      2318141.23       13269665.
      2301049.69     13264611.62        2294443.     13259418.82
#Sta/Elev= 30
-19567.5  236.75-17387.6  228.24-15255.1  225.74-14563.7   233.6-14091.5  217.93
-13769.5  224.12-13508.6  211.27-12968.4  218.99-12591.2  202.18-12327.2  222.36
-12109.6  203.42-11249.6   229.3-10891.4  209.65-9144.06  205.27-8614.32  188.95
-7954.64  199.42 -7634.8  181.77-6225.49  175.13-5265.95  120.72-4516.25  109.23
 -747.72   97.27  3411.7   98.86  3759.6   90.716039.631   98.21 8978.48   91.95
9498.279   108.916513.99  116.0418192.68  154.2919831.39  174.65 20951.7  212.12
#Mann= 18 ,-1 , 0
-19567.5     .05       0-17387.6     .05       0-15255.1      .1       0
-10891.4      .1       0 -7597.4      .1       0 -6265.1     .05       0
 -5299.2      .1       0 -4324.1      .1       0 -2105.2     .05       0
  3411.7     .05       0  9203.2      .1       0  9885.7     .05       0
 12066.9      .1       0   14023      .1       0 15171.5     .05       0
 16367.2     .05       0 19150.2      .1       0 20086.7      .1       0
#XS Ineff= 2 , 0
                         9586.08          108.97
Permanent Ineff=
       F       F
Bank Sta=3411.7,6039.631
XS Rating Curve= 0 ,0
Exp/Cntr=0.3,0.1

Type RM Length L Ch R = 1 ,327576  ,11027,11027,11027
BEGIN DESCRIPTION:
LOWER NUECES 38.0
END DESCRIPTION:
XS GIS Cut Line= 5
      2338719.78     13274673.99      2335073.29     13271256.05
      2319135.62     13265926.69      2304351.84      13254775.5
      2295830.92     13256677.76
#Sta/Elev= 30
-29698.7  226.33  -25782  231.16-19980.2  240.23-19159.2  215.74-18653.9   219.8
-17219.3   234.8-15103.2  198.05-13901.7   201.2-13366.1  205.99-11083.1  148.66
 -8034.1  139.11 -5564.6   99.33 -2527.7   90.71 4113.73   99.81 5753.73   91.21
 7183.73  137.16 7563.73  121.91    8010  150.59    8597  148.37  9460.9   196.2
 10539.2  200.68 12344.5  134.51 12854.6  157.32 13910.1   177.5 14321.5   156.4
 15328.5  194.78 15975.1  192.75 18449.8  194.52 19038.4  203.29 19352.8  188.89
#Mann= 15 ,-1 , 0
-29698.7     .05       0  -25782     .05       0-19980.2      .1       0
-18653.9      .1       0-13901.7      .1       0-12842.1     .05       0
-10686.4     .05       0 -8574.8     .05       0 -6980.5     .05       0
-5210.07     .05       0  5967.9     .05       0  7067.7      .1       0
 12344.5      .1       0 15975.1      .1       0 18449.8      .1       0
Bank Sta=-5564.6,4113.73
XS Rating Curve= 0 ,0
Exp/Cntr=0.3,0.1

Type RM Length L Ch R = 1 ,316549  ,6312,6312,6312
BEGIN DESCRIPTION:
LOWER NUECES 39.0
END DESCRIPTION:
XS GIS Cut Line= 5
      2342044.02     13268311.36      2330213.35     13260746.19
       2317137.9     13253419.92      2303824.87     13253353.49
      2295877.33     13256488.94
#Sta/Elev= 30
-22851.7  228.71-14961.1  223.11-10483.3  211.15-9084.05  192.15-7694.29  201.79
 -5690.5  173.94 -4286.3  139.06 -3872.9  142.85 -2442.1  132.51 -1458.2  110.62
 -1231.1   98.62 -1157.2   90.71  6919.2   99.98  6929.2   98.72 14249.3   98.57
14819.08  114.2115398.86  151.1916838.29  192.7318047.82   153.818887.49  175.08
20386.55  149.9820946.11  163.9621535.65  151.7921715.51  166.0124063.67  193.08
24773.12  165.0526012.15   211.3 26816.5  179.16 27207.7  195.29 28035.9  191.86
#Mann= 17 ,-1 , 0
-22851.7     .05       0-10215.5      .1       0 -9447.6     .05       0
 -8045.6      .1       0 -7246.5     .05       0 -5821.6      .1       0
 -3872.9     .05       0 -1458.2    .033       0  6919.2     .05       0
  7281.4      .1       0 10532.3     .05       0 11585.5     .05       0
 13250.5     .05       0 17103.1      .1       0 21804.9      .1       0
 23226.3      .1       0 26362.2      .1       0
#XS Ineff= 2 , 0
                         8833.49          105.34
Permanent Ineff=
       F       F
Bank Sta=-1231.1,6929.2
XS Rating Curve= 0 ,0
Exp/Cntr=0.3,0.1