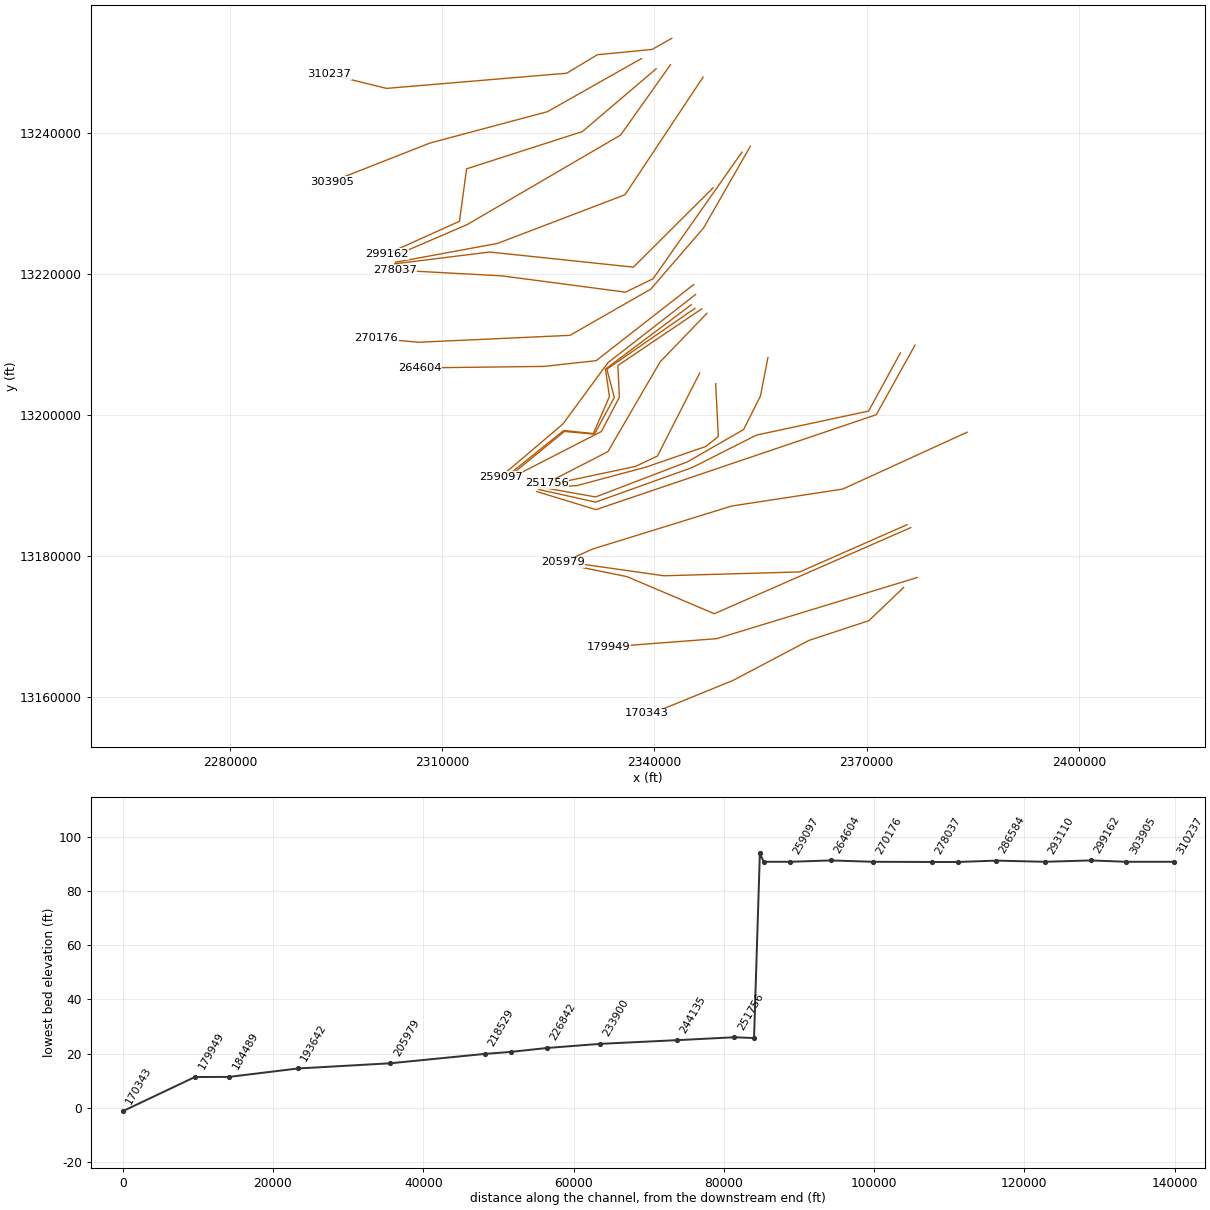
HEC-RAS study NUECES RIVER.prj: NUECES RIVER Base Level Engineering

--- NUECES RIVER.g01 (geometry) --- (continued)

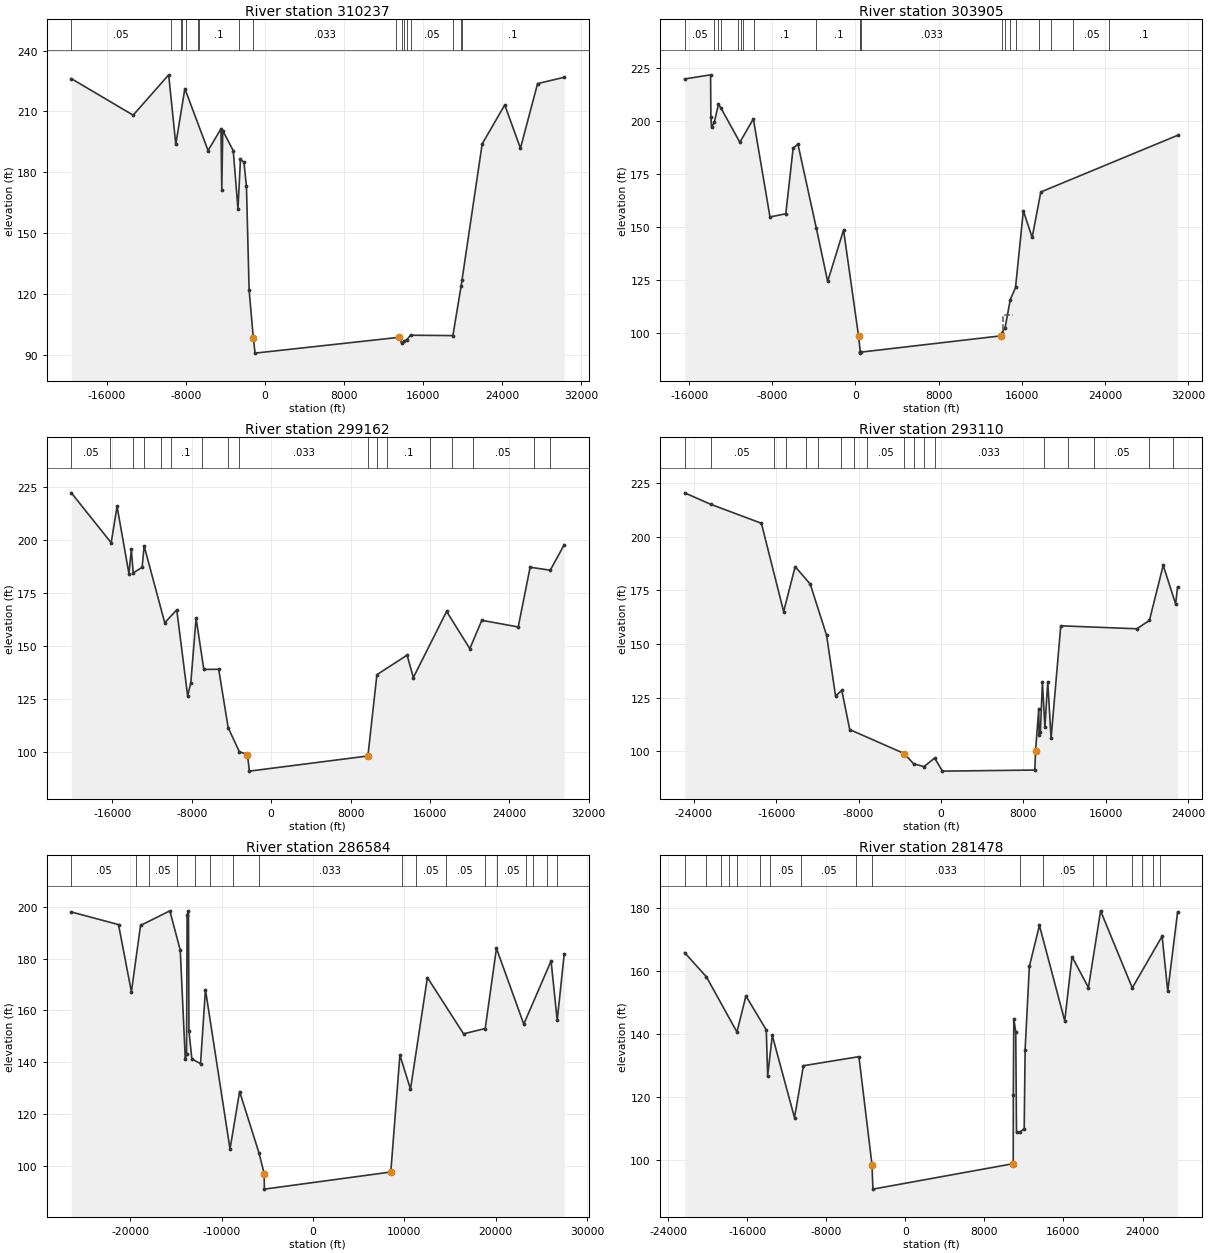
Type RM Length L Ch R = 1 ,310237  ,6332,6332,6332
BEGIN DESCRIPTION:
LOWER NUECES 40.0
END DESCRIPTION:
XS GIS Cut Line= 6
      2342448.39     13253484.62      2339661.35     13251908.57
      2331944.74     13251162.05      2327599.61     13248536.83
      2302128.33     13246382.15      2294067.41     13248381.65
#Sta/Elev= 30
-19587.8  226.16  -13328  208.13-9731.55  228.03-9012.25  193.76-8092.99   221.2
 -5744.6  190.67-4435.49  201.38-4355.55  171.26-4255.62  200.48-3196.21  190.63
-2716.35  161.77-2466.43  186.27 -2109.7  184.87 -1858.8  172.97 -1587.9  121.85
-1166.67   98.35    -986   90.71   13556   98.49 13877.4    95.5 14073.9   96.63
 14368.8    97.3 14750.3   99.55 19041.8   99.36   19872  123.83 19970.3  126.97
 22005.5  193.93 24288.5  213.17 25880.1  191.82 27613.9   223.7 30310.7  226.82
#Mann= 17 ,-1 , 0
-19587.8     .05       0 -9539.6      .1       0 -8470.1     .05       0
 -8365.1      .1       0 -8019.3     .05       0 -6779.5     .08       0
 -6666.8      .1       0 -2632.6      .1       0-1166.67    .033       0
 13286.3      .1       0 13877.4     .16       0 14073.9      .1       0
 14368.8     .16       0 14750.3     .05       0 19041.8      .1       0
   19872     .08       0 19970.3      .1       0
#XS Ineff= 1 ,-1
14730.2920580.91   98.06
Permanent Ineff=
       F
Bank Sta=-1166.67,13556
XS Rating Curve= 0 ,0
Exp/Cntr=0.3,0.1

Type RM Length L Ch R = 1 ,303905  ,4743,4743,4743
BEGIN DESCRIPTION:
LOWER NUECES 40.5
END DESCRIPTION:
XS GIS Cut Line= 4
      2338166.81     13250618.73      2324874.75     13243077.52
      2308273.19     13238628.74      2294384.26     13233149.12
#Sta/Elev= 30
-16427.9  219.65  -13934  221.59-13903.2  201.65-13838.3  196.96  -13578   199.2
  -13181  207.67-12958.6  206.16-11119.6  189.88 -9820.3  200.86-8221.08  154.76
-6701.82  156.25-5992.17  187.13-5532.39  188.97 -3762.9  149.43 -2673.3  124.43
 -1145.6  148.62  291.67   98.87   463.4   91.21   466.1   90.71   469.4   91.21
   570.5   91.2114041.67   98.87 14082.3  100.37 14384.8  102.52   14879  115.73
 15393.1  121.6216142.07  157.6816991.44  145.0917820.79  166.49 30972.5  193.13
#Mann= 20 ,-1 , 0
-16427.9     .05       0  -13578      .1       0  -13181     .05       0
-12958.6      .1       0-11344.9     .05       0-11024.4      .1       0
-10802.3     .05       0 -9803.1      .1       0 -3762.9      .1       0
   463.4    .033       0   469.4      .1       0   570.5    .033       0
 14082.3      .1       0 14384.8     .16       0   14879      .1       0
 15393.1      .1       0 17605.3     .05       0 18826.1      .1       0
 20934.7     .05       0 24425.3      .1       0
#XS Ineff= 1 ,-1
14232.3715103.73  108.51
Permanent Ineff=
       F
Bank Sta=291.67,14041.67
XS Rating Curve= 0 ,0
Exp/Cntr=0.3,0.1

Type RM Length L Ch R = 1 ,299162  ,6052,6052,6052
BEGIN DESCRIPTION:
LOWER NUECES 41.0
END DESCRIPTION:
XS GIS Cut Line= 5
      2340242.56     13249164.26      2329816.92      13240258.6
      2313453.59     13234972.51      2312446.04     13227531.62
      2302190.97     13222890.59
#Sta/Elev= 30
-20138.7  222.36-16119.4  198.82-15529.8  215.99-14330.6  184.27-14090.7  195.68
-13900.8  184.62-13001.4  187.24-12801.5  197.35-10722.8  161.12-9513.56  167.23
-8414.24  126.66-8094.43  132.91-7564.75  163.31-6785.23  139.15 -5285.7   139.2
 -4329.7  111.64 -3205.6  100.38-2386.31   99.03-2196.35   91.21    9750   98.35
 10657.1  136.6613700.75  145.8714330.75  135.3317680.75  166.4820020.07  148.93
21229.59  162.2924898.16  159.1526097.69  187.29 28128.8   185.9 29533.9  197.92
#Mann= 17 ,-1 , 0
-20138.7     .05       0-16248.3     .05       0  -13895     .05       0
-12792.3      .1       0-11050.3     .05       0-10126.1      .1       0
 -6990.8      .1       0 -4329.7      .1       0 -3205.6    .033       0
    9750     .05       0 10657.1      .1       0 11634.2      .1       0
 15998.6     .05       0 18260.6      .1       0 20295.6     .05       0
 26439.1      .1       0 28128.8      .1       0
Bank Sta=-2386.31,9750
XS Rating Curve= 0 ,0
Exp/Cntr=0.3,0.1

Type RM Length L Ch R = 1 ,293110  ,6526,6526,6526
BEGIN DESCRIPTION:
LOWER NUECES 42.0
END DESCRIPTION:
XS GIS Cut Line= 4
      2342276.45     13249742.15      2335218.69     13239762.82
       2313537.6     13227063.03       2303894.4     13222897.69
#Sta/Elev= 30
-24892.4  220.42-22380.8  215.11-17441.3  206.23-15282.6  165.06-14163.2  186.01
-12704.1  177.93-11114.3  154.07-10244.4  125.81-9634.46  128.33-8864.54  110.08
 -3564.5   98.88 -2669.7   94.17 -1663.2   92.79  -619.9   96.81   132.4   90.71
  9107.8   91.21  9173.4  100.14  9488.1  119.89  9515.4  107.669642.219  108.98
9842.219  132.3210082.22  111.1710362.22  132.3910682.22  105.9211622.22  158.44
18999.66  157.0620229.18  160.9421568.66  186.65   22771  168.65 22961.6  176.51
#Mann= 18 ,-1 , 0
-24892.4     .05       0-22380.8     .05       0-16257.4     .05       0
-15021.7     .05       0-13092.8      .1       0  -11980     .05       0
 -9715.9      .1       0   -8440      .1       0 -7147.8     .05       0
 -3564.5     .05       0 -2669.7     .05       0 -1663.2     .05       0
  -619.9    .033       0    9968     .08       0 12316.5      .1       0
 14869.7     .05       0 20175.2      .1       0 22563.2      .1       0
Bank Sta=-3564.5,9173.4
XS Rating Curve= 0 ,0
Exp/Cntr=0.3,0.1

Type RM Length L Ch R = 1 ,286584  ,5106,5106,5106
BEGIN DESCRIPTION:
LOWER NUECES 43.0
END DESCRIPTION:
XS GIS Cut Line= 4
      2346877.69     13247986.21      2335839.61     13231293.92
      2317828.97     13224392.37      2303414.98     13221721.64
#Sta/Elev= 30
-26467.8  197.97-21299.1  193.09-19889.7  167.18-18890.1  192.76-15681.3   198.4
-14541.8  183.24  -13992  141.34  -13852  143.06-13792.1  196.69-13642.1  198.22
-13592.1  152.16-13272.3  141.34-12322.6  139.47-11782.8  168.01-9093.94  106.59
-8044.35  128.76 -5921.6  105.08 -5358.3   97.16 -5331.3   91.14  8506.6   97.74
  9502.3  142.81 10662.7  129.66 12512.7  172.69 16472.7     151 18842.7  153.04
 20072.7  183.95 23062.7  154.74 26052.7  179.09 26722.7  156.18   27491  181.77
#Mann= 17 ,-1 , 0
-26467.8     .05       0-19373.7     .05       0-17924.3     .05       0
-14914.1     .05       0-12882.7     .05       0-11331.1     .05       0
 -8714.2     .05       0 -5921.6    .033       0  9714.2      .1       0
 11277.6     .05       0 14497.1     .05       0 18781.2      .1       0
 20112.9     .05       0 23294.7      .1       0   24127     .05       0
 25592.7      .1       0 26668.7      .1       0
Bank Sta=-5358.3,8506.6
XS Rating Curve= 0 ,0
Exp/Cntr=0.3,0.1

Type RM Length L Ch R = 1 ,281478  ,3441,3441,3441
BEGIN DESCRIPTION:
LOWER NUECES 44.0
END DESCRIPTION:
XS GIS Cut Line= 4
      2348281.65     13232276.32      2337032.12     13221025.45
      2316709.11     13223170.42      2303280.84      13221493.9
#Sta/Elev= 30
-22332.1  165.88-20130.7   158.2-17040.3  140.63-16130.8  152.11-14072.1   141.3
-13932.2  126.68-13462.5  139.53-11213.8  113.36-10314.3  129.91-4696.99  132.79
   -3375   98.42 -3280.4   90.6410916.67   98.74 10928.3  120.67 10976.2  144.78
 11172.1  140.65 11250.1  108.68 11567.4  108.75 12028.2  109.85   12121  135.06
12549.73  161.4813569.58  174.5516128.68  144.1916868.39  164.5918527.74  154.77
19757.26  179.19   22966  154.6725984.82  171.13 26554.6  153.58 27546.5   178.7
#Mann= 18 ,-1 , 0
-22332.1     .05       0-20130.7     .05       0-18654.7     .05       0
-17845.4     .05       0-16994.5      .1       0-14660.8     .05       0
-13662.7     .05       0-10594.8     .05       0 -4958.7      .1       0
   -3375    .033       0 11567.4      .1       0 13904.1     .05       0
 18945.6      .1       0 20355.9     .05       0 22969.4      .1       0
 23985.6     .05       0   25041     .05       0 25762.3      .1       0
Bank Sta=-3375,10916.67
XS Rating Curve= 0 ,0
Exp/Cntr=0.3,0.1

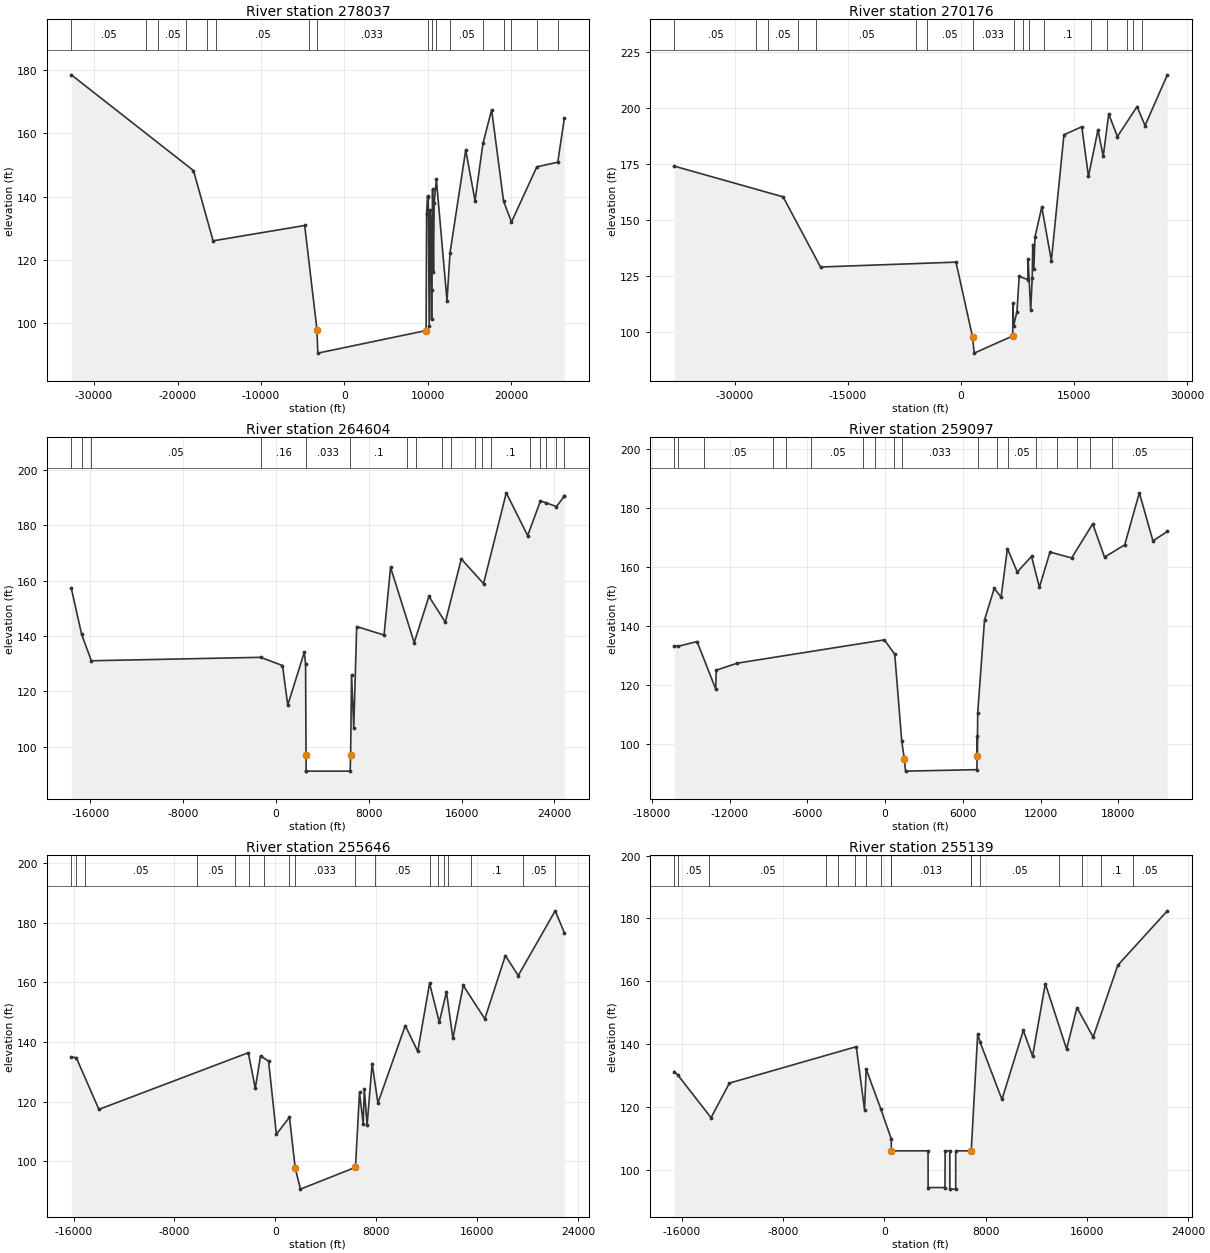
Type RM Length L Ch R = 1 ,278037  ,7861,7861,7861
BEGIN DESCRIPTION:
LOWER NUECES 45.0
END DESCRIPTION:
XS GIS Cut Line= 5
      2352372.36     13237347.63      2339800.36     13219371.69
      2335902.84     13217478.39      2318391.49     13219792.72
      2303283.07     13220608.25
#Sta/Elev= 30
-32727.1  178.47-18089.7  148.25-15740.2  126.08-4768.63  130.92-3298.61   98.09
   -3195   90.64 9777.78   97.77  9837.6  134.69    9951  140.15 10039.3  140.07
 10150.3   99.27 10271.3  135.82   10352  132.02 10436.8  101.32 10466.2   110.5
 10553.7  142.31 10662.2  116.29 10740.7  138.06   11009  145.44 12280.9  107.21
 12648.9  122.39 14524.1  154.75 15641.5  138.73   16586   156.8 17628.7  167.42
 19058.3  138.58 20008.3  132.03 23045.7  149.44 25549.9  150.89   26336  164.69
#Mann= 17 ,-1 , 0
-32727.1     .05       0-23814.3     .05       0-22296.1     .05       0
-18932.6     .05       0-16489.3     .05       0-15354.3     .05       0
 -4257.9      .1       0-3298.61    .033       0    9951     .16       0
 10466.2      .1       0   11009     .05       0 12648.9     .05       0
   16586      .1       0 19058.3      .1       0 20008.3     .05       0
 23045.7     .05       0 25549.9      .1       0
Bank Sta=-3298.61,9777.78
XS Rating Curve= 0 ,0
Exp/Cntr=0.3,0.1

Type RM Length L Ch R = 1 ,270176  ,5572,5572,5572
BEGIN DESCRIPTION:
LOWER NUECES 46.0
END DESCRIPTION:
XS GIS Cut Line= 6
      2353562.71       13238190.      2346950.55     13226596.34
      2339491.07      13217915.3      2328062.94     13211351.23
      2306660.25     13210366.46      2300703.16     13210927.31
#Sta/Elev= 30
-37993.4  174.01-23570.9  160.34-18602.8  129.08 -634.96  131.25  1562.5   97.87
  1783.1   90.71 6881.87   98.35  6933.4  112.88  6993.4  102.79  7453.4  109.17
7745.949   124.9 8894.77  123.47 8934.77   132.69274.762  109.72 9474.75  124.22
 9544.75   139.1 9694.75  128.39 9834.75  142.4210744.72  155.79 12014.7  131.94
13684.66     188 16054.6  191.5616934.58  169.4618194.55  190.1318894.54  178.41
19624.52  197.25 20774.5  187.1923382.21  200.5424440.96   192.1 27399.5   214.7
#Mann= 17 ,-1 , 0
-37993.4     .05       0-27102.7     .05       0-25602.6     .05       0
-21631.9     .05       0-19140.8     .05       0   -5885      .1       0
 -4490.2     .05       0  1562.5    .033       0  6993.4      .1       0
  8237.7      .1       0    9109      .1       0 11012.5      .1       0
 17259.9     .05       0 19377.6      .1       0 22076.2     .16       0
 22833.3      .1       0 24069.3      .1       0
Bank Sta=1562.5,6881.87
XS Rating Curve= 0 ,0
Exp/Cntr=0.3,0.1

Type RM Length L Ch R = 1 ,264604  ,5507,5507,5507
BEGIN DESCRIPTION:
LOWER NUECES 47.0
END DESCRIPTION:
XS GIS Cut Line= 4
      2345545.36     13218554.98      2331764.94     13207758.51
      2324386.47     13206944.71      2306808.33      13206727.7
#Sta/Elev= 30
-17643.7  157.29-16752.5  140.62  -15917   131.1 -1322.2  132.34   565.3  129.38
  1019.7  115.07  2445.2  134.19  2555.9   129.9  2596.1   96.99  2603.2   91.21
  2609.2   91.21  6401.8   91.21  6439.3    96.9  6519.8  126.05  6710.9  106.77
  6962.4  143.46 9322.09  140.39 9882.09  164.8711922.09  137.6513192.09  154.36
14602.09  145.0515982.09  167.8717902.09  158.9919862.09  191.7921702.09  176.33
 22807.5  188.87 23248.8  188.26   24190  186.82   24850  190.54 24865.1  190.63
#Mann= 18 ,-1 , 0
-17643.7     .08       0-16752.5     .05       0  -15917     .05       0
 -1322.2     .16       0  2609.2    .033       0  6401.8      .1       0
   11322      .1       0 12113.3     .05       0 14278.3     .08       0
 15063.2     .05       0 17202.1     .05       0 17747.1      .1       0
 18522.5      .1       0 21927.7     .05       0 22807.5      .1       0
 23248.8     .05       0   24190      .1       0   24850     .05       0
Bank Sta=2596.1,6439.3
XS Rating Curve= 0 ,0
Exp/Cntr=0.3,0.1

Type RM Length L Ch R = 1 ,259097  ,3451,3451,3451
BEGIN DESCRIPTION:
LOWER NUECES 48.0
END DESCRIPTION:
XS GIS Cut Line= 4
      2345816.61     13217144.37       2333446.8     13207487.24
      2327044.89     13198752.44      2318255.82     13191265.45
#Sta/Elev= 30
-16273.8  133.19-16013.4  133.04-14517.7  134.67-13078.4  118.54-13038.4  124.97
-11399.1  127.36-54.0498  135.26745.9395  130.35  1286.3  100.82    1487   94.84
  1578.6   90.71  7088.7   91.21    7118  102.48 7118.06    95.9  7153.5  110.59
7675.939  141.988425.939  152.748955.939  149.759445.939  166.2410205.94  158.28
11305.53  163.5811915.29  153.1112734.97  165.0514404.32  163.0516033.69  174.61
16943.33  163.3418502.72  167.4819632.28  185.1520681.87  168.85 21794.6  172.03
#Mann= 18 ,-1 , 0
-16273.8     .05       0-16013.4      .1       0-13950.9     .05       0
 -8632.3      .1       0 -7671.9     .05       0 -5710.4     .05       0
 -1668.1     .16       0  -777.2     .16       0   656.6      .1       0
  1286.3    .033       0  7153.5      .1       0  8679.3      .1       0
  9477.4     .05       0   11622     .05       0   13312      .1       0
 14786.5      .1       0 15836.2      .1       0 17533.6     .05       0
Bank Sta=1487,7118.06
XS Rating Curve= 0 ,0
Exp/Cntr=0.3,0.1

Type RM Length L Ch R = 1 ,255646  ,507,507,507
BEGIN DESCRIPTION:
LOWER NUECES 49.0
END DESCRIPTION:
XS GIS Cut Line= 6
      2345209.73     13215688.79      2333079.98      13206557.3
      2333639.87     13202675.35      2331362.96     13197412.33
      2327184.12      13197854.8      2319429.52     13191601.09
#Sta/Elev= 30
  -16173  134.95-15781.8  134.77-13987.3  117.43-2148.84  136.42 -1598.9   124.5
-1180.31  135.33 -544.95  133.6274.37012  109.11  1112.8  114.79  1570.2   97.63
  1982.4   90.71 6339.29   98.01  6661.1   123.1  6952.7  112.64  7040.6  124.23
  7262.9  112.267659.881  132.78 8119.43  119.5610285.93  145.5111274.09  136.86
12212.33  159.6812980.96  146.6513550.51  156.8114060.11  141.2114879.47  158.95
16588.13  147.7618216.86  168.9519236.06  162.2722163.77  183.96   22887  176.69
#Mann= 18 ,-1 , 0
  -16173     .08       0-15781.8      .1       0-15049.9     .05       0
 -6219.8     .05       0 -3167.6     .16       0 -2066.9     .16       0
    -877      .1       0  1112.8     .05       0  1570.2    .033       0
 6339.29      .1       0    7899     .05       0 12256.3      .1       0
   12884     .05       0 13360.9      .1       0 13708.2     .05       0
 15500.9      .1       0 19576.9     .05       0 22170.6     .05       0
Bank Sta=1570.2,6339.29
XS Rating Curve= 0 ,0
Exp/Cntr=0.3,0.1

Type RM Length L Ch R = 1 ,255139  ,776,776,776
BEGIN DESCRIPTION:
LOWER NUECES 50.0
END DESCRIPTION:
XS GIS Cut Line= 6
      2345717.71     13215183.12      2333272.11     13206545.23
      2334331.91     13202546.87       2331528.2     13197340.28
      2327269.34     13197713.87      2320041.62     13191774.81
#Sta/Elev= 30
-16585.8  131.25-16322.7   130.2  -13687  116.55-12237.1  127.57-2217.32  139.17
-1567.32  119.13 -1436.7  132.01  -294.3  119.48   546.5  109.76   548.4     106
  3450.1     106  3455.8    94.3  4784.6    94.3  4800.8     106  5167.5     106
    5177    93.8  5632.4    93.8 5632.56     106    6859     106    7369  143.24
  7565.4  140.55 9285.58  122.36 10973.6  144.3611702.74  136.1712711.56  159.22
14390.22  138.4115209.74   151.616488.99  142.2318438.23  165.13 22346.7  182.44
#Mann= 17 ,-1 , 0
-16585.8     .08       0-16322.7     .05       0-13810.7     .05       0
 -4634.2     .05       0 -3697.4     .16       0 -2292.4     .16       0
 -1436.7      .1       0  -294.3      .1       0   546.5     .05       0
   548.4    .013       0    6859     .05       0    6859      .1       0
  7565.4     .05       0 13761.1     .05       0 15620.6      .1       0
 17111.7      .1       0 19607.1     .05       0
Bank Sta=548.4,6859
XS Rating Curve= 0 ,0
Exp/Cntr=0.3,0.1

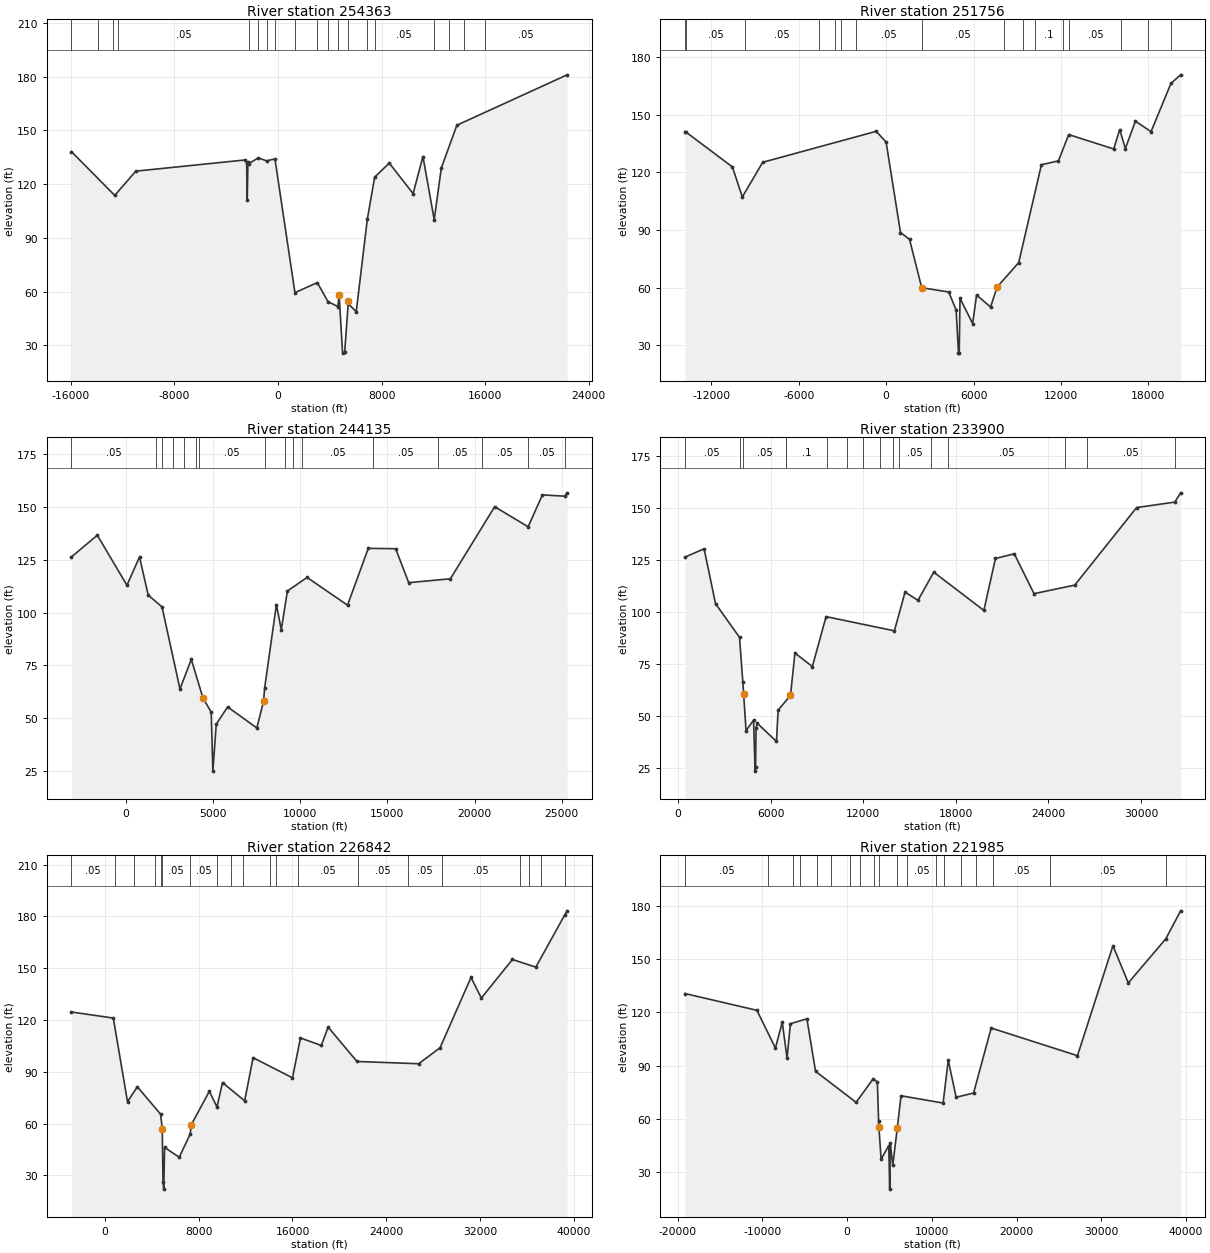
Type RM Length L Ch R = 1 ,254363  ,2607,2607,2607
BEGIN DESCRIPTION:
LOWER NUECES 51.0
END DESCRIPTION:
XS GIS Cut Line= 5
      2346678.17     13215105.13      2334834.09     13207068.07
      2335045.59     13202573.68      2332507.58     13197709.15
      2320082.94     13191311.78
#Sta/Elev= 30
-15949.7  138.11-12608.5  113.71-10979.2  127.24 -2573.1  133.45 -2423.3  132.02
 -2378.5  110.97 -2321.5  132.07 -2245.1   131.5 -1520.9  134.66  -886.5  132.97
  -237.7  134.07 1305.98   59.45    3032   65.05  3859.6   54.43  4622.6   51.69
  4720.7    57.9  4986.6   25.71  5149.3   26.44  5431.3   54.57    5440   53.13
  6040.3   48.85  6895.6   100.4  7461.6  123.898592.359  131.7310431.64  114.71
11191.34   135.4   12061  100.1712610.79  129.0513810.32  152.86 22324.9  180.97
#Mann= 19 ,-1 , 0
-15949.7     .05       0  -13876     .05       0-12750.5      .1       0
-12324.8     .05       0 -2245.1     .05       0 -1520.9     .05       0
  -886.5      .1       0  -237.7      .1       0  1318.1     .05       0
    3032     .16       0  3859.6     .12       0  4622.6     .05       0
    5440     .16       0  6895.6      .1       0  7461.6     .05       0
 12020.4      .1       0   13164      .1       0 14366.8      .1       0
 16015.4     .05       0
Bank Sta=4720.7,5431.3
XS Rating Curve= 0 ,0
Exp/Cntr=0.3,0.1

Type RM Length L Ch R = 1 ,251756  ,7621,7621,7621
BEGIN DESCRIPTION:
LOWER NUECES 52.0
END DESCRIPTION:
XS GIS Cut Line= 4
      2347418.38     13214470.59      2340808.99     13207596.83
      2333423.48     13194854.21      2324761.45     13190380.21
#Sta/Elev= 30
  -13805  141.18-13757.9  141.07-10548.4  122.81 -9868.7  107.18-8469.33  125.22
 -681.61  141.32-1.67968  135.73   986.1   88.71  1607.3   85.14  2442.1   60.02
 4297.68   57.79    4804    48.4  4965.9   26.01  5017.1   26.18  5069.9   54.55
5937.359   41.396207.311   56.197167.119      50  7613.7   60.35 9096.75   73.06
10656.48  123.9511826.46  125.9612526.46  139.6315616.42  132.1416026.41  142.23
16416.41  132.38 17106.4  146.6218176.39  141.14 19546.4  166.25 20208.3  170.69
#Mann= 16 ,-1 , 0
  -13805     .05       0-13757.9     .05       0 -9673.6     .05       0
 -4594.3     .05       0 -3486.4     .05       0 -3075.3      .1       0
 -2070.9     .05       0  2442.1     .05       0 8111.11     .05       0
  9390.6      .1       0 10225.5      .1       0 12111.2      .1       0
 12572.9     .05       0 16136.8      .1       0 17994.5     .05       0
 19546.4      .1       0
Bank Sta=2442.1,7613.7
XS Rating Curve= 0 ,0
Exp/Cntr=0.3,0.1

Type RM Length L Ch R = 1 ,244135  ,10235,10235,10235
BEGIN DESCRIPTION:
LOWER NUECES 53.0
END DESCRIPTION:
XS GIS Cut Line= 4
      2346394.23     13205999.07      2340426.76     13194227.62
      2337320.41     13192756.19      2325794.18      13190303.8
#Sta/Elev= 30
 -3109.8  126.39-1627.27  136.6872.43994  112.97792.3101  126.39 1292.22  108.31
 2082.08  102.72  3111.9   63.86 3761.79   77.86  4426.9   59.64  4901.4   52.91
  4998.4   24.94  5190.9   47.12 5841.41   55.36  7521.2   45.39  7902.1   58.02
  7968.9   64.44 8640.86  103.82 8920.81   91.93 9270.74  110.2510400.33  116.68
 12718.5  103.5413907.65  130.4615476.78  130.2916226.37  114.2118615.05  116.04
21153.65  150.1923072.59  140.6823892.14  155.79 25171.3  155.17 25309.3  156.76
#Mann= 16 ,-1 , 0
 -3109.8     .05       0  1715.6     .05       0  2069.1      .1       0
  2702.7     .16       0  3370.2      .1       0  4053.4     .05       0
 4211.81     .05       0  7968.9     .16       0  9134.1      .1       0
  9598.2     .16       0 10119.2     .05       0 14206.9     .05       0
 17896.2     .05       0 20419.3     .05       0 23089.9     .05       0
 25171.3      .1       0
Bank Sta=4426.9,7902.1
XS Rating Curve= 0 ,0
Exp/Cntr=0.3,0.1

Type RM Length L Ch R = 1 ,233900  ,7058,7058,7058
BEGIN DESCRIPTION:
Mapping XS 28f61c3d
END DESCRIPTION:
XS GIS Cut Line= 6
      2348659.38      13204487.7      2349026.25     13196992.92
      2347244.28     13195577.83      2338753.72     13192642.82
       2329005.3     13190022.27      2325755.79     13189865.04
#Sta/Elev= 30
   450.7  126.36 1691.97  130.36 2431.35  104.02  3986.4   87.82  4200.8   66.34
 4253.47   60.71  4408.2   43.04  4896.9   48.04  4996.7   23.58    5027   25.56
  5057.1   44.44  5137.1   46.57  6378.6   37.83  6488.8   52.87 7287.33   59.94
 7577.09   80.29  8705.3    73.8 9593.56   97.7814019.62   90.9614709.13  109.54
15548.54  105.6316567.81  119.1319815.41  100.7720564.97   125.721784.26  127.96
23063.51  108.8125701.96  112.9229708.99  150.16 32181.7  152.79 32561.3  157.24
#Mann= 16 ,-1 , 0
   450.7     .05       0  3986.4     .16       0  4200.8     .05       0
  6987.6     .16       0  6987.6      .1       0  9666.8     .05       0
 10948.4      .1       0 11986.7     .05       0 13096.7      .1       0
 13934.4      .1       0 14295.6     .05       0 16362.2      .1       0
 17508.1     .05       0 25078.5     .05       0 26466.4     .05       0
 32181.7      .1       0
Bank Sta=4253.47,7287.33
XS Rating Curve= 0 ,0
Exp/Cntr=0.3,0.1

Type RM Length L Ch R = 1 ,226842  ,4857,4857,4857
BEGIN DESCRIPTION:
LOWER NUECES 54.0
END DESCRIPTION:
XS GIS Cut Line= 6
      2356040.26     13208206.22      2354977.55      13202729.2
      2352606.92     13197987.94      2344677.55     13193410.16
      2331679.93     13188423.65      2323505.31     13189895.08
#Sta/Elev= 30
 -2846.6  124.65  722.47  121.15 1932.29    72.7 2772.11   81.35  4754.5   65.45
  4894.3   57.02  4961.4   26.25  5022.6   22.06  5095.5   46.21 6345.96   40.51
 7274.35   53.94 7374.17   59.41 8912.61   78.76  9562.3   69.6210032.07   83.78
11921.17    73.212640.83   98.1915999.44   86.5116679.17  109.6118458.23  105.27
19037.89   115.921496.45      9626763.36   94.6828582.29  103.9731220.54  144.68
32100.19  132.7334749.16  155.0636748.38  150.64 39210.6   180.9 39416.7  183.25
#Mann= 20 ,-1 , 0
 -2846.6     .05       0   825.1      .1       0  2512.7     .05       0
  4236.3      .1       0  4754.5     .07       0  4894.3     .05       0
 7274.35     .05       0  9601.4      .1       0 10787.2      .1       0
   11765     .05       0 14070.4     .05       0   14607      .1       0
 16427.8     .05       0 21623.7     .05       0 25807.2     .05       0
 28716.8     .05       0 35362.4     .12       0 36162.7     .05       0
 37176.6      .1       0 39210.6     .05       0
Bank Sta=4894.3,7374.17
XS Rating Curve= 0 ,0
Exp/Cntr=0.3,0.1

Type RM Length L Ch R = 1 ,221985  ,3456,3456,3456
BEGIN DESCRIPTION:
LOWER NUECES 54.5
END DESCRIPTION:
XS GIS Cut Line= 6
      2374760.08     13208860.14      2370264.06     13200603.81
      2354424.57     13197202.57      2345331.52      13192592.7
      2331679.93     13187687.94      2323670.73     13189485.92
#Sta/Elev= 30
-19148.6  130.59-10650.5  121.15-8466.96   99.92-7657.67  114.52-7098.16   94.21
-6698.51  113.62-4750.23  116.39-3730.37   86.84 1059.23    69.43089.061   82.76
  3568.5   80.76  3711.3   59.13    3750   55.41    4007   37.43  4914.4   45.07
  5023.3   20.61  5097.9    46.3  5381.4    33.9 5916.67   54.896358.801    73.1
11326.03   69.0111935.68    93.112865.15   72.2814924.21   74.63 17003.4  111.19
27189.42   95.6431377.84  157.4833187.57  136.56 37622.2   161.4 39366.5  177.09
#Mann= 19 ,-1 , 0
-19148.6     .05       0 -9360.1      .1       0 -6438.6      .1       0
 -5618.5     .05       0 -3545.2     .05       0 -1872.3      .1       0
   328.5      .1       0  1553.5      .1       0  3207.7      .1       0
  3711.3     .05       0 5916.67     .05       0  7042.3     .05       0
 10517.5      .1       0 11385.1     .05       0 13445.2     .16       0
 15161.9      .1       0 17211.7     .05       0 23985.5     .05       0
 37622.2      .1       0
Bank Sta=3750,5916.67
XS Rating Curve= 0 ,0
Exp/Cntr=0.3,0.1

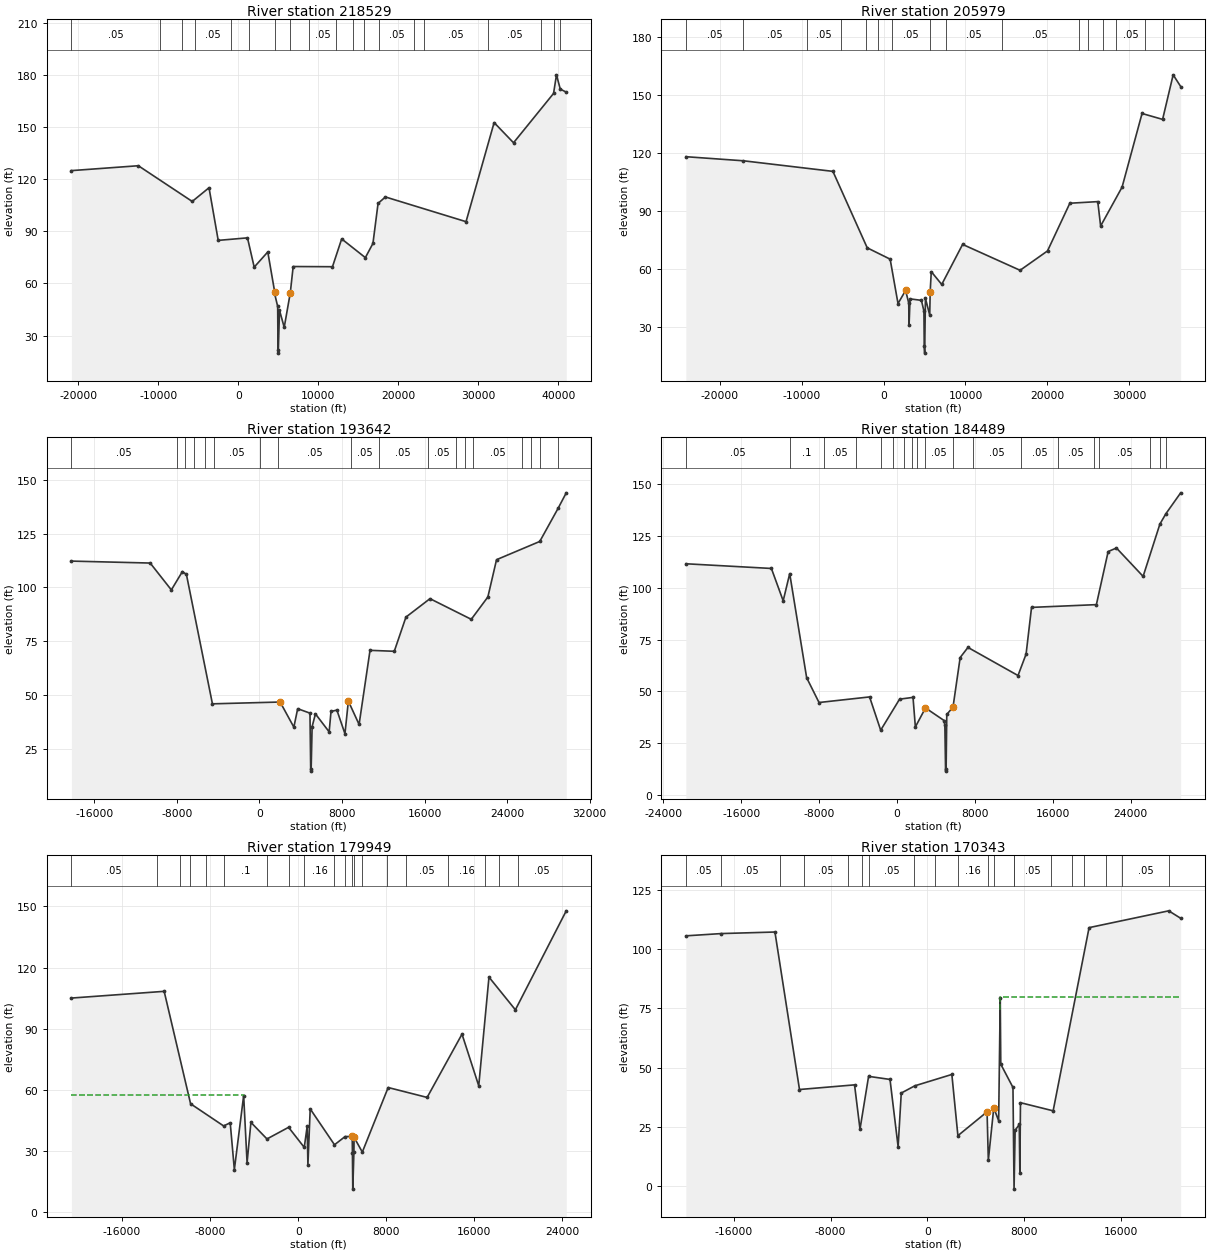
Type RM Length L Ch R = 1 ,218529  ,12550,12550,12550
BEGIN DESCRIPTION:
LOWER NUECES 55.0
END DESCRIPTION:
XS GIS Cut Line= 4
      2376825.45     13209962.71      2371351.17     13200092.36
      2331723.79     13186623.54      2323377.75     13189189.05
#Sta/Elev= 30
-20867.1  125.01-12499.4  127.83-5760.85  107.25-3661.21  115.14-2511.43   84.82
 1147.85   86.28 1987.68   69.41 3687.35   78.16  4560.3   54.86  4565.6   53.65
  4924.7   46.75  4962.9   21.72    4994   19.87  5151.2   44.56  5742.1   34.74
    6500    54.6  6861.3   69.7611775.77   69.6512925.75   85.6715885.75   74.89
16835.75   83.0717475.75  106.1418395.75  109.8428475.75    95.631985.75  152.69
34413.38  141.06 39419.4  169.49 39780.9   180.2 40257.7  171.98 41004.9  170.22
#Mann= 19 ,-1 , 0
-20867.1     .05       0 -9830.6     .05       0 -7077.2      .1       0
 -5442.3     .05       0  -891.6     .05       0  1331.8     .05       0
  4565.6     .05       0    6500     .05       0  8810.6     .05       0
 12230.2     .05       0 14287.4      .1       0 15675.8      .1       0
 17564.2     .05       0 22008.9     .05       0 23228.9     .05       0
 31207.7     .05       0   37896      .1       0 39419.4      .1       0
 40257.7     .05       0
Bank Sta=4560.3,6500
XS Rating Curve= 0 ,0
Exp/Cntr=0.3,0.1

Type RM Length L Ch R = 1 ,205979  ,12337,12337,12337
BEGIN DESCRIPTION:
LOWER NUECES 56.0
END DESCRIPTION:
XS GIS Cut Line= 5
      2384195.58      13197611.4      2366610.99     13189541.08
      2350927.69     13187137.76      2331261.52     13181034.36
       2327053.6     13179131.51
#Sta/Elev= 30
-24145.8  118.03-17105.2  115.91-6185.77  110.44-1996.46   70.89802.9902   65.03
1762.801   42.072692.619   48.863072.539   42.293112.539   30.75 3232.51   44.48
 4622.24   43.72  4927.8   38.14  4965.5   19.85  5018.6   16.42  5109.9   44.78
  5635.9    36.1  5692.8   48.25  5824.6   58.57 7101.76   51.949651.059   72.66
16668.32   59.2720017.01   69.2822745.94   93.9626154.61   94.7926504.47   82.17
29123.45  102.29 31562.5  140.3834071.52  137.3335361.01  160.38 36278.3  154.34
#Mann= 17 ,-1 , 0
-24145.8     .05       0-17105.2     .05       0   -9341     .05       0
 -5147.5     .05       0 -2185.2      .1       0  -709.6     .05       0
  1062.5     .05       0  5692.8     .05       0  7592.7     .05       0
 14432.5     .05       0 23825.7      .1       0 24951.4     .05       0
 26737.1     .05       0 28435.1     .05       0 31875.5      .1       0
 34142.3     .05       0 35509.6      .1       0
Bank Sta=2692.619,5692.8
XS Rating Curve= 0 ,0
Exp/Cntr=0.3,0.1

Type RM Length L Ch R = 1 ,193642  ,9153,9153,9153
BEGIN DESCRIPTION:
LOWER NUECES 57.0
END DESCRIPTION:
XS GIS Cut Line= 4
      2375696.49     13184486.68      2360545.69     13177790.08
        2341352.      13177240.5       2329312.1     13178955.15
#Sta/Elev= 30
-18206.6  112.18-10576.4  111.27-8527.03   98.77-7457.35  107.31-7067.46  105.99
 -4548.2   45.79 2009.51   46.63 3338.99   34.94 3708.84   43.53  4898.8   41.46
  4968.8    15.3  5008.6   14.49  5108.9    35.2 5428.17   41.12 6757.65   32.75
 6937.58   42.247507.359   42.878287.051   31.88 8616.93   47.06 9656.52   36.19
10716.11   70.6713065.19   70.2314194.75   86.1316523.84    94.720521.12    85.1
22129.86   95.49 22969.2  112.83 27155.1  121.31 28936.8  136.77 29721.1  143.93
#Mann= 18 ,-1 , 0
-18206.6     .05       0 -8022.8     .05       0 -7191.8      .1       0
 -6290.6      .1       0 -5300.2     .16       0 -4407.3     .05       0
    33.1     .16       0  1797.5     .05       0  8900.4     .05       0
 11575.1     .05       0 16297.9     .05       0 19006.8     .16       0
 19898.5      .1       0 20655.6     .05       0 25476.1     .05       0
   26316      .1       0 27155.1     .05       0 28936.8      .1       0
Bank Sta=2009.51,8616.93
XS Rating Curve= 0 ,0
Exp/Cntr=0.3,0.1

Type RM Length L Ch R = 1 ,184489  ,4540,4540,4540
BEGIN DESCRIPTION:
LOWER NUECES 58.0
END DESCRIPTION:
XS GIS Cut Line= 4
      2376219.35     13184072.46      2348461.43     13171856.55
      2336143.67     13177111.94      2329210.95      13178537.7
#Sta/Elev= 30
-21678.3  111.63-12894.8  109.36-11684.9   93.72  -11015  106.86-9275.18   56.53
 -8005.3   44.56 -2815.8   47.26 -1675.9   31.18263.9102   46.181643.779   47.04
 1883.76   32.75    2924   41.94  4828.9   35.86  4911.3   33.57  4986.5   11.39
  5038.9   12.21  5108.9   38.78    5750   42.39 6483.33   66.31 7283.25   71.19
12420.84    57.613250.31   67.9713809.95   90.54 20465.7   91.8721674.92  117.53
 22524.5  119.2525263.43  105.53 26986.3  130.82 27603.4  135.84 29118.6  145.92
#Mann= 19 ,-1 , 0
-21678.3     .05       0-10935.7      .1       0 -7529.1     .05       0
 -4163.3      .1       0 -1602.7      .1       0  -436.9      .1       0
   715.8     .16       0  1488.4      .1       0    2073     .16       0
    2924     .05       0    5750     .16       0  7819.4     .05       0
 12697.1     .05       0 16564.6     .05       0 20225.1      .1       0
 20748.2     .05       0 25988.9      .1       0 26986.3     .05       0
 27603.4      .1       0
Bank Sta=2924,5750
XS Rating Curve= 0 ,0
Exp/Cntr=0.3,0.1

Type RM Length L Ch R = 1 ,179949  ,9606,9606,9606
BEGIN DESCRIPTION:
LOWER NUECES 59.0
END DESCRIPTION:
XS GIS Cut Line= 3
      2377138.51     13176992.73      2348790.61     13168315.98
      2333533.62     13167150.61
#Sta/Elev= 30
-20600.5  105.07-12175.1  108.37-9775.38   53.22 -6773.4   42.34 -6175.9   43.89
 -5799.8   20.89 -4954.6   57.24 -4643.7   24.32 -4295.1   44.09 -2836.7   35.96
  -874.2   41.67   549.8   31.82   818.2   42.28   880.9   23.13  1090.1    50.7
  3295.9   33.11  4254.4   37.11  4907.2   37.19  4924.2    29.3    4957   11.35
  5060.5   29.53  5074.6   36.77  5823.8   29.52 8171.57   61.1911709.83   56.33
 14878.5   87.3716397.91   62.0417327.55  115.3519726.61   99.31   24347  147.86
#Mann= 20 ,-1 , 0
-20600.5     .05       0-12849.8     .05       0-10730.7     .05       0
 -9819.8      .1       0 -8400.8     .05       0 -6773.4      .1       0
 -2836.7      .1       0  -874.2     .16       0   549.8     .16       0
  3295.9     .16       0  4254.4     .16       0  4924.2     .05       0
  5060.5     .16       0  5823.8     .16       0  8095.9     .05       0
  9801.2     .05       0 13649.8     .16       0 16953.5     .05       0
 18203.2      .1       0 19922.9     .05       0
#XS Ineff= 2 , 0
        -4959.79   57.42
Permanent Ineff=
       F       F
Bank Sta=4907.2,5074.6
XS Rating Curve= 0 ,0
Exp/Cntr=0.3,0.1

Type RM Length L Ch R = 1 ,170343  ,19624,19624,19624
BEGIN DESCRIPTION:
LOWER NUECES 61.0
END DESCRIPTION:
XS GIS Cut Line= 6
      2375217.89     13175577.16      2370306.31     13170873.08
      2361841.75     13168072.79      2351103.15     13162396.39
      2341398.15     13158426.64      2338971.65     13157721.05
#Sta/Elev= 30
-19953.6  105.57-17013.5  106.53-12593.3  107.18-10564.3   40.75 -6016.6   42.71
-5566.82   24.02-4857.16    46.3-3087.81      45-2418.02   16.59 -2158.1   39.26
-1038.44   42.31  2020.6    47.12520.449   21.28  4929.6   31.34  5033.8   10.91
    5479   32.83    5501   32.77  5885.9   27.58    6018   79.44    6062   51.43
7069.039   41.62 7159.01   -1.27 7248.98   23.517588.869   26.037638.859    5.59
 7688.84   35.19 10387.8   31.7613356.64  109.03 19934.1  116.12 20922.1  112.98
#Mann= 20 ,-1 , 0
-19953.6     .05       0-17013.5     .05       0  -12195      .1       0
-10231.7     .05       0 -6589.7      .1       0 -5422.9     .12       0
 -4789.7     .05       0 -1131.7     .05       0   617.2     .05       0
  2540.5     .16       0  5033.8     .05       0    5501     .05       0
  7154.9     .07       0  7160.9     .05       0   10191     .12       0
 11975.9      .1       0   12949      .1       0 14753.7     .05       0
 16092.9     .05       0 19934.1     .05       0
#XS Ineff= 2 , 0
                         6005.36           79.72
Permanent Ineff=
       F       F
Bank Sta=4929.6,5479
XS Rating Curve= 0 ,0
Exp/Cntr=0.3,0.1