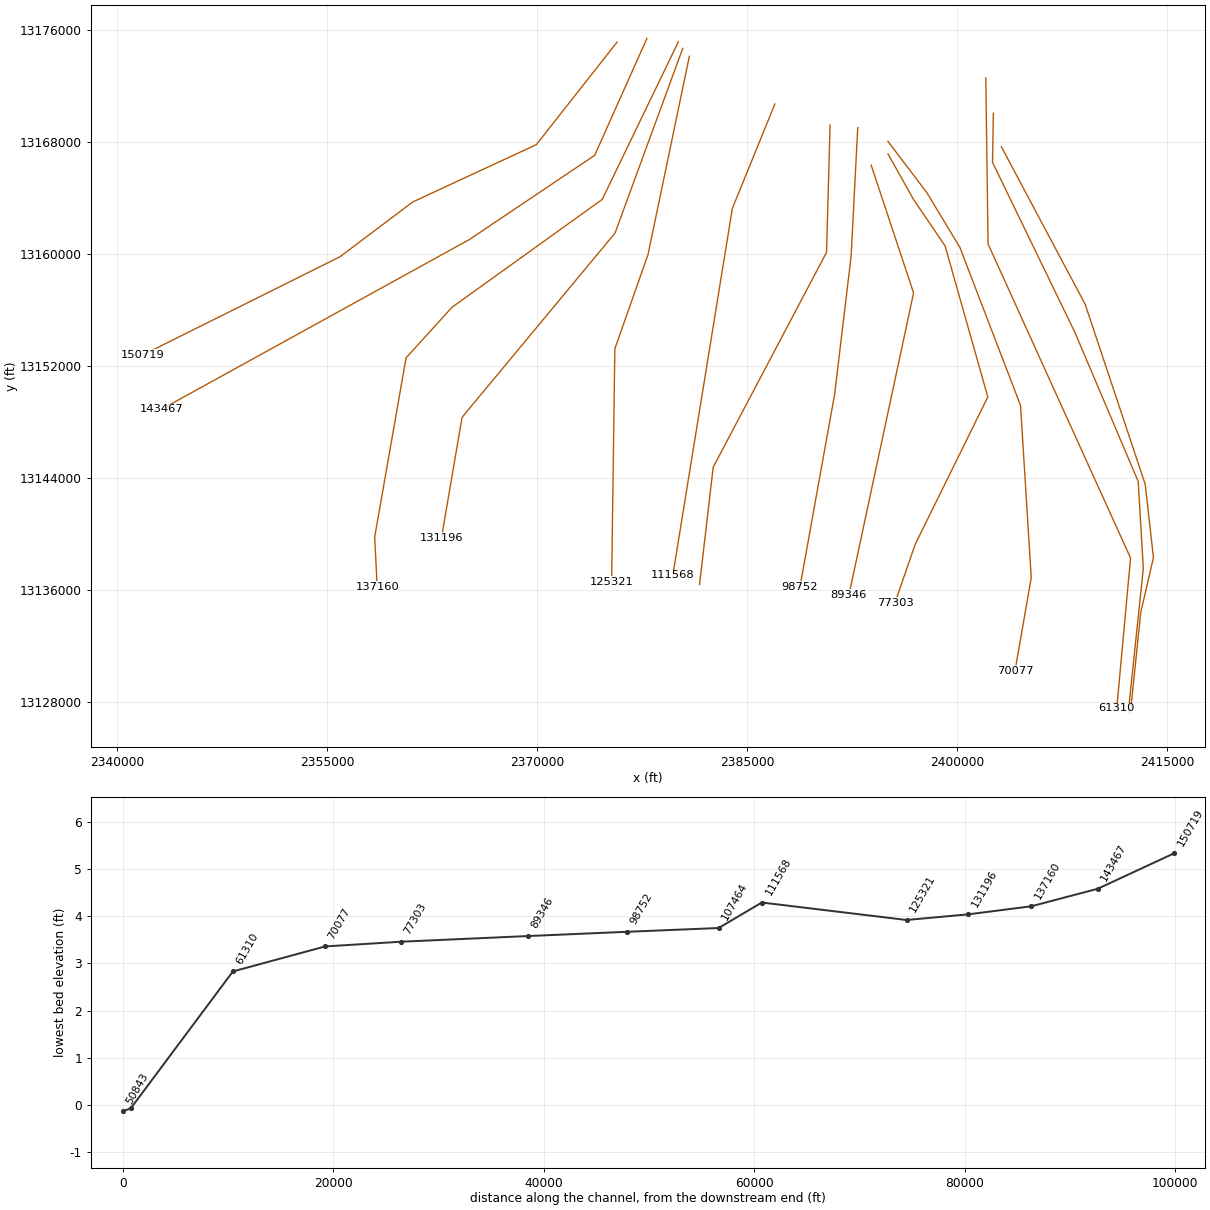
HEC-RAS study NUECES RIVER.prj: NUECES RIVER Base Level Engineering

--- NUECES RIVER.g01 (geometry) --- (continued)

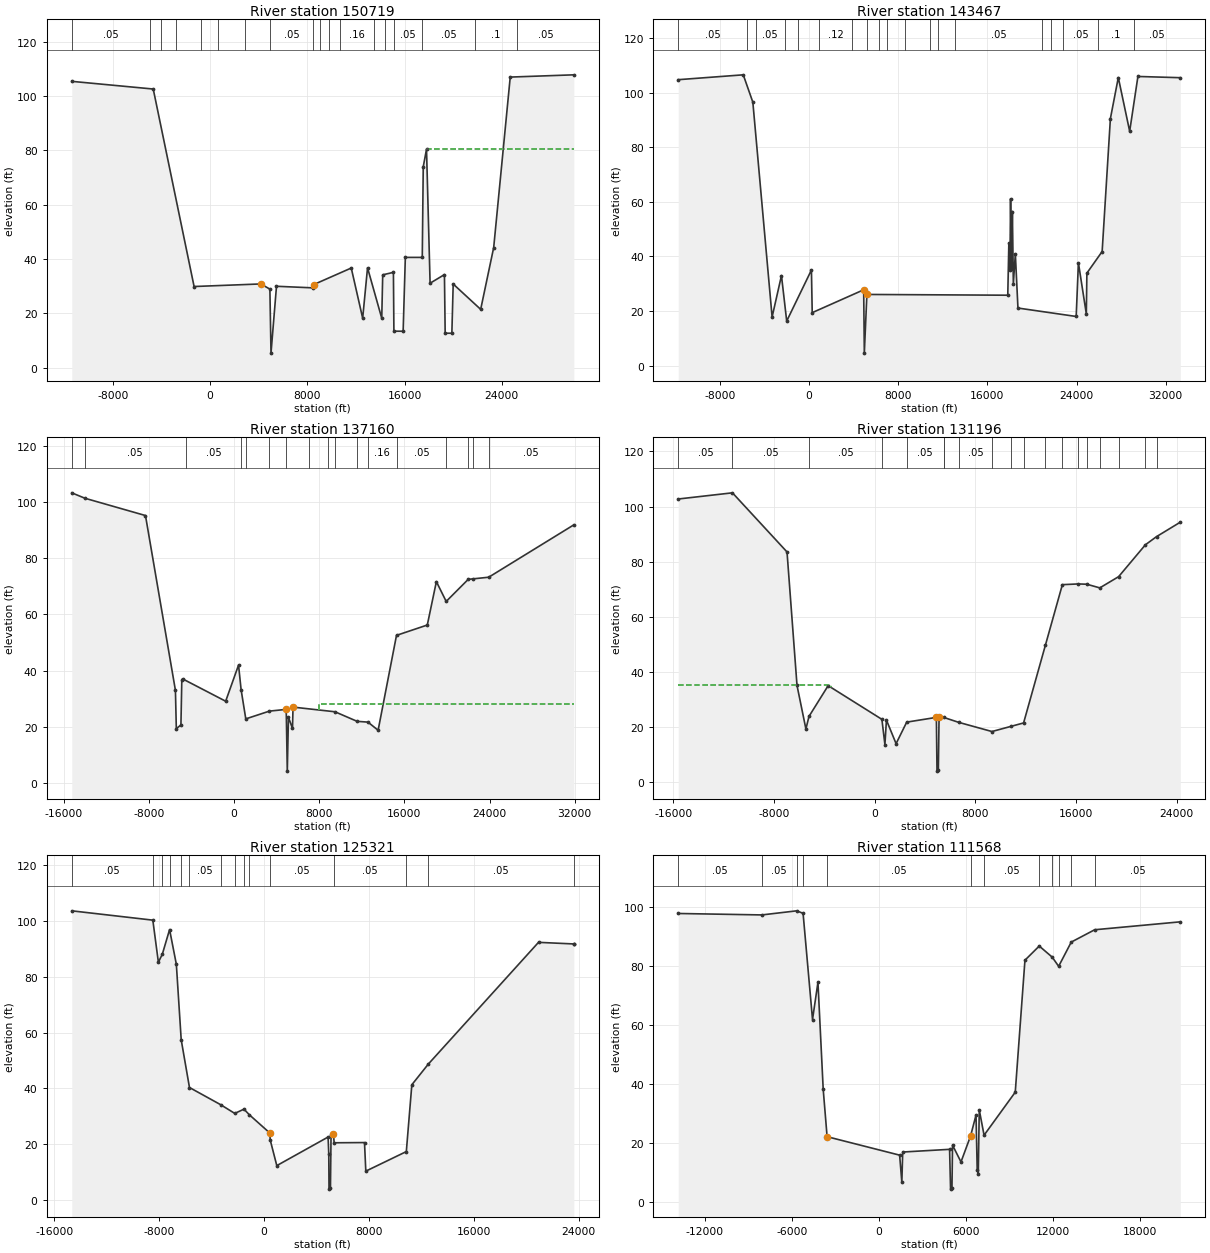
Type RM Length L Ch R = 1 ,150719  ,7252,7252,7252
BEGIN DESCRIPTION:
LOWER NUECES 62.0
END DESCRIPTION:
XS GIS Cut Line= 5
      2375688.67     13175162.67       2369918.8     13167830.76
      2361090.49     13163732.18      2355899.88     13159818.24
      2341833.41      13152806.6
#Sta/Elev= 30
-11362.3  105.38-4664.03  102.55-1304.56   29.85 4176.86    30.8  4927.2    28.9
  5018.6    5.33  5470.4   29.948467.971   29.368537.881   30.5811617.69   36.66
12556.41   18.1812955.86   36.7514124.26   18.1814204.15   34.1515083.98   35.07
15123.97   13.4115883.82   13.3916063.79   40.57 17456.3   40.57 17536.6   73.91
 17805.2   80.4118099.39   31.0719279.16   34.2419339.14   12.6619889.04   12.66
19999.02   30.7722258.73   21.4423328.73   44.2124688.71  106.95   29919  107.78
#Mann= 18 ,-1 , 0
-11362.3     .05       0 -4925.1     .05       0   -4014     .05       0
 -2769.8     .05       0  -695.9     .05       0   663.2      .1       0
    2884      .1       0  4927.2     .05       08467.971     .16       0
  9023.3      .1       0  9801.5      .1       0 10714.8     .16       0
 13488.1     .05       0 14395.4      .1       0 15110.2     .05       0
 17456.3     .05       0 21773.8      .1       0 25267.8     .05       0
#XS Ineff= 2 , 0
                        17801.61           80.61
Permanent Ineff=
       F       F
Bank Sta=4176.86,8537.881
XS Rating Curve= 0 ,0
Exp/Cntr=0.3,0.1

Type RM Length L Ch R = 1 ,143467  ,6307,6307,6307
BEGIN DESCRIPTION:
LOWER NUECES 63.0
END DESCRIPTION:
XS GIS Cut Line= 4
      2377823.07     13175433.29      2374087.89     13167065.84
      2365131.56     13161042.56      2343172.03     13148923.76
#Sta/Elev= 30
-11725.9  104.77-5893.27  106.55-5033.89   96.53-3305.15   17.82-2465.75      33
-1996.04   16.33222.6201   35.04292.5801   19.41  4909.2   27.79  4966.8    4.58
    5198   26.08 17835.2    25.8 17932.1   44.97 18025.4   35.21   18085   61.12
 18166.4   35.46 18247.7   56.45 18334.8   30.08 18513.6   40.98 18747.4    21.1
 23971.7   18.0124171.62   37.6824881.34   18.9624931.32   33.8926300.79   41.81
 27040.5   90.5227750.22  105.5628769.82   85.8629509.53  105.95 33312.3   105.5
#Mann= 19 ,-1 , 0
-11725.9     .05       0 -5524.5      .1       0   -4769     .05       0
 -2187.6     .16       0   -1006     .05       0   909.8     .12       0
  3872.2     .05       0    5198     .16       0  6258.9     .05       0
  7030.6     .16       0    8574     .16       0 10889.6      .1       0
   11573      .1       0 13085.4     .05       0 20943.7      .1       0
   21728     .05       0 22797.8     .05       0 25900.5      .1       0
 29147.9     .05       0
Bank Sta=4909.2,5198
XS Rating Curve= 0 ,0
Exp/Cntr=0.3,0.1

Type RM Length L Ch R = 1 ,137160  ,5964,5964,5964
BEGIN DESCRIPTION:
LOWER NUECES 64.0
END DESCRIPTION:
XS GIS Cut Line= 6
      2380064.11      13175183.5      2374627.25     13163914.59
      2363895.59     13156200.92      2360613.56     13152582.41
      2358373.31     13139765.79      2358552.25     13136226.32
#Sta/Elev= 30
-15245.1   103.3-14008.2  101.37 -8320.5   95.21 -5506.6   32.97 -5422.6   19.33
 -4989.6   20.66 -4907.7   36.64 -4834.2   37.06-786.669    29.1422.9697   41.97
   662.8   33.23    1103   22.81  3325.1   25.58  4901.9   26.19  5002.3    4.21
    5111   23.39  5491.1   19.39  5541.4   27.01  9485.5   25.34 11560.3   21.94
 12581.6   21.66 13535.8   18.76 15262.3   52.55 18155.5   56.23 19008.2   71.69
 19930.6   64.63 21999.4   72.49 22430.5   72.66 23924.3   73.25 31923.2    91.9
#Mann= 17 ,-1 , 0
-15245.1     .05       0-14008.2     .05       0 -4546.4     .05       0
   662.8     .16       0    1103     .12       0  3325.1     .12       0
  4901.9     .05       0  7030.4     .16       0  8868.9      .1       0
  9485.5      .1       0 11560.3     .16       0 12581.6     .16       0
 15262.3     .05       0 19930.6     .05       0 21999.4      .1       0
 22430.5     .05       0 23924.3     .05       0
#XS Ineff= 2 , 0
                         7939.79            28.2
Permanent Ineff=
       F       F
Bank Sta=4901.9,5541.4
XS Rating Curve= 0 ,0
Exp/Cntr=0.3,0.1

Type RM Length L Ch R = 1 ,131196  ,5875,5875,5875
BEGIN DESCRIPTION:
LOWER NUECES 65.0
END DESCRIPTION:
XS GIS Cut Line= 4
      2380378.86     13174716.19      2375545.19     13161514.39
      2364616.36     13148335.51      2363146.35     13139733.29
#Sta/Elev= 30
-15613.8  102.72-11304.7  104.96 -6967.4   83.52 -6173.1    35.1 -5465.8   19.32
 -5221.8   23.88 -3696.4   35.04   573.8   22.82   813.6   13.65   934.7   22.55
  1701.8      14    2546   21.81  4904.1   23.53  4953.3    4.04  5060.4    4.55
  5117.7   23.67  5471.4   23.54  6677.8   21.73  9321.5    18.4 10862.8   20.31
 11836.3   21.51 13576.2   49.81 14918.4   71.66 16178.9   71.92 16856.8   71.82
 17892.5   70.49 19389.7   74.56 21518.4   86.12 22403.6   89.08 24292.8   94.32
#Mann= 19 ,-1 , 0
-15613.8     .05       0-11304.7     .05       0 -5221.8     .05       0
   573.8     .12       0    2546     .05       0  5471.4     .05       0
  5471.4     .16       0  6677.8     .05       0  9321.5     .05       0
 10862.8     .05       0 11836.3     .05       0 13576.2     .05       0
 14918.4      .1       0 16178.9     .05       0 16856.8     .05       0
 17892.5     .05       0 19389.7     .05       0 21518.4     .05       0
 22403.6     .05       0
#XS Ineff= 2 , 0
        -3453.98   35.18
Permanent Ineff=
       F       F
Bank Sta=4904.1,5117.7
XS Rating Curve= 0 ,0
Exp/Cntr=0.3,0.1

Type RM Length L Ch R = 1 ,125321  ,13753,13753,13753
BEGIN DESCRIPTION:
LOWER NUECES 66.0
END DESCRIPTION:
XS GIS Cut Line= 4
      2380850.39     13174145.44      2377896.66     13159962.84
      2375529.79     13153232.42      2375299.11     13136561.49
#Sta/Elev= 30
-14674.7   103.6 -8492.2  100.26 -8068.7   85.18 -7769.5   88.04 -7214.3   96.88
 -6698.6   84.46   -6328   57.41 -5697.9   40.32 -3318.3   34.16 -2243.1   31.04
 -1540.5   32.56 -1125.6   30.53   422.2   24.06   465.2   21.45   963.4   12.34
  4874.9   22.58  4927.9   16.42  4945.9    3.92  5055.1    4.42    5101   23.14
  5281.5    23.8  5338.1   20.52  7652.3    20.6  7752.3   10.36 10842.1   17.37
 11262.7    41.3 12518.5    48.7 20923.6   92.31 23602.2   91.74 23619.2   91.64
#Mann= 15 ,-1 , 0
-14674.7     .05       0 -8492.2      .1       0 -7769.5      .1       0
 -7214.3     .16       0   -6328     .16       0 -5697.9     .05       0
 -3318.3     .05       0 -2243.1     .16       0 -1540.5     .16       0
 -1125.6     .05       0   465.2     .05       0  5338.1     .05       0
 10842.1      .1       0 12518.5     .05       0 23602.2     .05       0
Bank Sta=422.2,5281.5
XS Rating Curve= 0 ,0
Exp/Cntr=0.3,0.1

Type RM Length L Ch R = 1 ,111568  ,4104,4104,4104
BEGIN DESCRIPTION:
LOWER NUECES 67.0
END DESCRIPTION:
XS GIS Cut Line= 3
      2386961.14     13170736.66      2383923.43     13163273.26
      2379672.76     13137051.57
#Sta/Elev= 30
-13826.3   97.74 -8060.2   97.25 -5654.4   98.64 -5217.2   97.79 -4566.5   61.79
 -4191.7   74.42 -3829.3   38.11-3561.22   22.07  1440.9   15.81  1592.9    6.61
  1653.7   16.87  4885.3   17.78  4953.2    4.29  5049.9    4.69  5087.9   19.21
  5671.4    13.5    6334   22.33  6708.8   29.42  6789.8   10.87  6862.8    9.34
  6931.7   31.16  7263.4   22.57  9413.7   37.16 10082.3    81.9   11068    86.7
 11959.8   82.95 12406.1   79.83   13275   88.04 14889.2   92.22 20795.6   94.91
#Mann= 12 ,-1 , 0
-13826.3     .05       0 -8060.2     .05       0 -5654.4     .16       0
 -5217.2      .1       0-3561.22     .05       0    6334      .1       0
  7263.4     .05       0   11068     .16       0 11959.8     .16       0
 12406.1     .16       0   13275     .05       0 14889.2     .05       0
Bank Sta=-3561.22,6334
XS Rating Curve= 0 ,0
Exp/Cntr=0.3,0.1

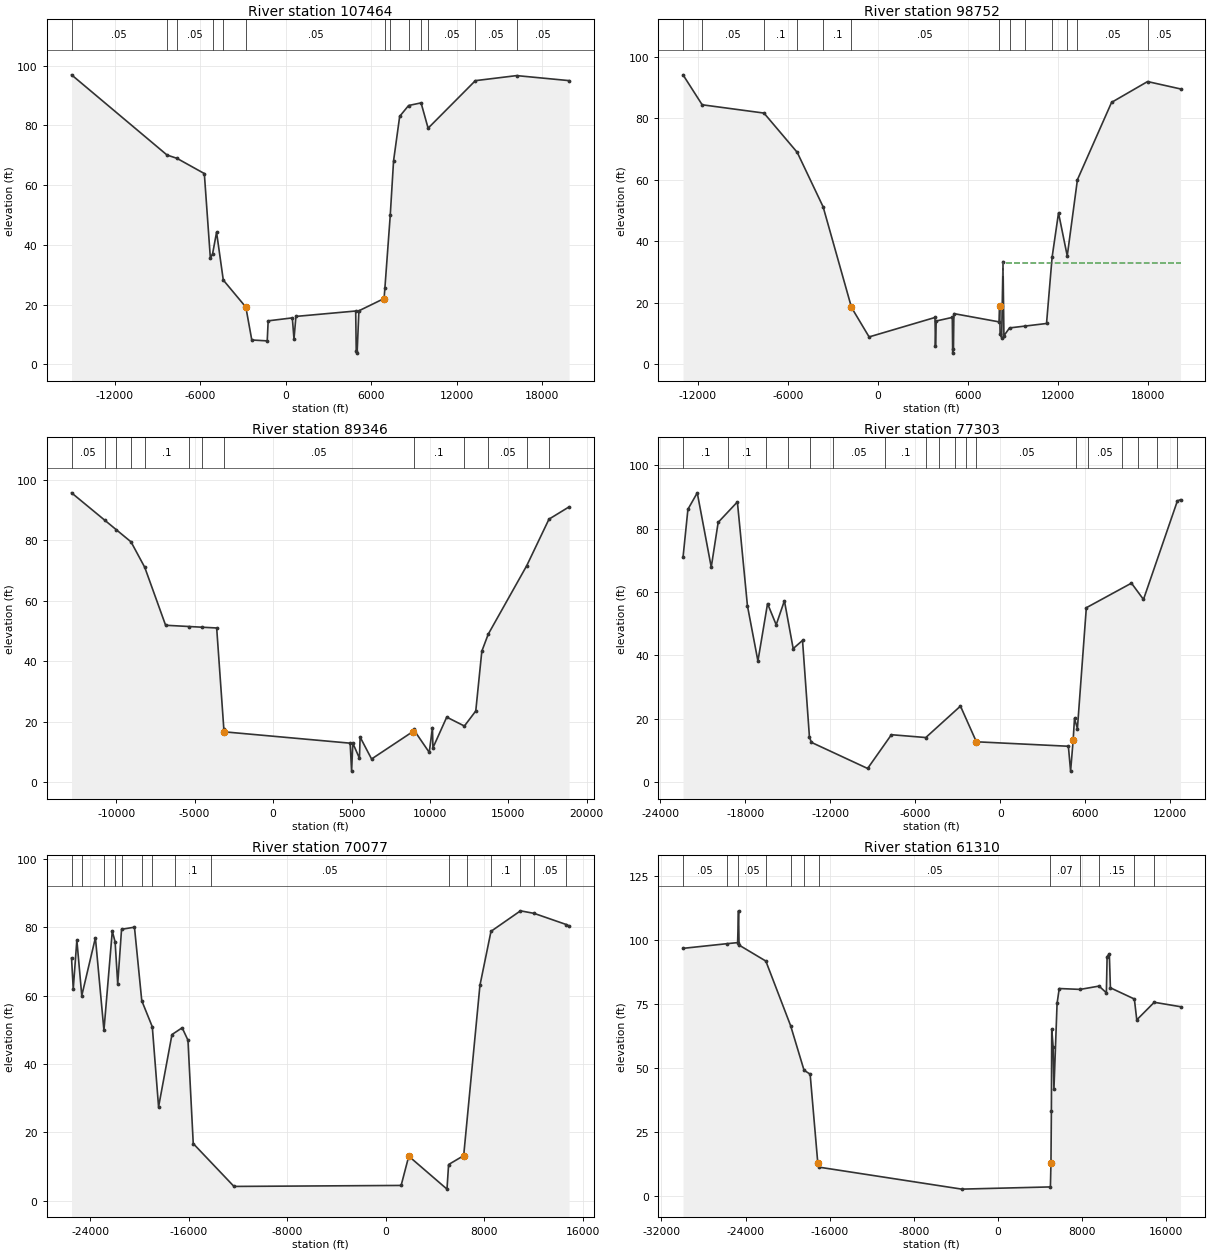
Type RM Length L Ch R = 1 ,107464  ,8712,8712,8712
BEGIN DESCRIPTION:
LOWER NUECES 68.0
END DESCRIPTION:
XS GIS Cut Line= 4
      2390904.29     13169232.92      2390651.52     13160131.33
      2382555.45     13144769.78       2381579.5     13136383.92
#Sta/Elev= 30
-15018.9   96.92 -8317.9   70.07 -7625.1   68.97 -5700.8   63.87 -5277.2   35.52
   -5120   37.04 -4842.2   44.22 -4370.5   28.21 -2788.2   19.16 -2370.6    8.15
 -1287.4    7.85 -1221.3   14.56   473.7   15.55     591    8.47   726.6   16.04
  4920.4   17.85  4958.8    4.35    5019    3.75  5145.8   17.92  6912.5   22.03
  6972.9   25.71  7344.8   49.85  7578.4   68.13  8007.6   83.02    8634   86.65
  9508.3   87.53 10002.1   79.05 13318.9   94.97 16215.3   96.66 19893.1   94.98
#Mann= 13 ,-1 , 0
-15018.9     .05       0 -8317.9     .05       0 -7625.1     .05       0
   -5120      .1       0 -4370.5     .16       0 -2788.2     .05       0
  6972.9     .12       0  7344.8      .1       0    8634     .05       0
  9508.3      .1       0 10002.1     .05       0 13318.9     .05       0
 16215.3     .05       0
Bank Sta=-2788.2,6912.5
XS Rating Curve= 0 ,0
Exp/Cntr=0.3,0.1

Type RM Length L Ch R = 1 ,98752   ,9406,9406,9406
BEGIN DESCRIPTION:
LOWER NUECES 69.0
END DESCRIPTION:
XS GIS Cut Line= 4
      2392881.02     13169051.03      2392404.25     13159828.68
      2391227.28     13149964.72      2388751.34     13136204.69
#Sta/Elev= 30
-12999.4   94.19-11724.5   84.45 -7606.5   81.75 -5389.3   68.97 -3663.9   51.25
-1773.91   18.52  -600.6    8.94  3790.3   15.27  3820.5    5.94  3870.9   14.12
  4942.5   15.29  4968.4    3.67    5019    4.88  5049.2   16.52  8055.1   13.84
  8097.5      19    8128    9.92  8231.2    8.71  8321.1   33.46    8382    9.32
  8756.4   11.87  9773.8   12.46 11221.2   13.31 11591.4   34.81 12019.5   49.27
 12601.2   35.29 13280.1   60.09 15555.4   85.23 17953.4      92 20150.2    89.6
#Mann= 13 ,-1 , 0
-12999.4     .05       0-11724.5     .05       0 -7606.5      .1       0
 -5389.3     .05       0 -3663.9      .1       0-1773.91     .05       0
  8055.1     .12       0  8756.4     .05       0  9773.8     .07       0
 11591.4      .1       0 12601.2      .1       0 13280.1     .05       0
 17953.4     .05       0
#XS Ineff= 2 , 0
                         8333.33           33.12
Permanent Ineff=
       F       F
Bank Sta=-1773.91,8097.5
XS Rating Curve= 0 ,0
Exp/Cntr=0.3,0.1

Type RM Length L Ch R = 1 ,89346   ,12043,12043,12043
BEGIN DESCRIPTION:
LOWER NUECES 70.0
END DESCRIPTION:
XS GIS Cut Line= 3
      2393838.56     13166368.77      2396868.84     13157229.04
      2392250.34     13135631.22
#Sta/Elev= 30
-12847.6   95.77-10716.6   86.64 -9984.3    83.5 -9054.8   79.52 -8180.8   71.09
   -6851    51.9 -5331.3   51.48 -4512.9   51.25 -3595.6      51 -3141.2   17.63
-3114.39    16.6  4913.4   12.84  5005.1    3.58  5082.9   12.85  5506.5    7.84
  5547.4   14.86  6278.9     7.6  8913.1   16.69  8957.5   17.37  9954.8    9.79
 10159.3   18.01   10190    11.3 11069.5   21.47 12195.1   18.52 12920.4    23.5
 13306.4    43.3 13713.6   48.93 16170.5   71.65 17587.2   87.05 18867.5   91.11
#Mann= 13 ,-1 , 0
-12847.6     .05       0-10716.6     .16       0 -9984.3      .1       0
 -9054.8     .05       0 -8180.8      .1       0 -5331.3     .16       0
 -4512.9      .1       0 -3141.2     .05       0  8957.5      .1       0
 12195.1     .05       0 13713.6     .05       0 16170.5     .05       0
 17587.2     .05       0
Bank Sta=-3114.39,8913.1
XS Rating Curve= 0 ,0
Exp/Cntr=0.3,0.1

Type RM Length L Ch R = 1 ,77303   ,7226,7226,7226
BEGIN DESCRIPTION:
LOWER NUECES 71.0
END DESCRIPTION:
XS GIS Cut Line= 6
      2395041.43     13167169.44      2396862.86     13163913.79
      2399116.85     13160597.62      2402172.34      13149790.1
      2396988.13     13139261.78      2395542.58      13135083.6
#Sta/Elev= 30
  -22398   70.89-22052.1   86.09-21392.1   91.28  -20405   67.83-19916.3   81.96
-18559.4   88.41-17849.5   55.63-17109.6   38.21-16429.6   56.32-15819.7   49.64
-15239.7   57.22-14619.8   42.12-13960.3   44.71-13470.7   14.15-13330.8   12.53
-9363.96     4.3-7685.28   14.95-5257.17   14.06-2808.85   23.98-1685.27   12.72
  4810.5   11.31  4967.5    3.46  5147.5   13.19  5242.9   20.12 5447.93   16.88
 6077.68   55.029264.939   62.7810113.28   57.63 12508.8   88.74   12730   89.12
#Mann= 18 ,-1 , 0
  -22398      .1       0  -19220      .1       0-16540.9      .1       0
-14964.9      .1       0-13441.9     .12       0-11843.7     .05       0
 -8127.2      .1       0 -5213.6     .12       0 -4329.1     .16       0
   -3200     .07       0 -2404.6      .1       0 -1683.2     .05       0
  5377.7     .05       0  6205.1     .05       0    8626     .08       0
  9724.4     .05       0   11099     .05       0 12508.8     .05       0
Bank Sta=-1685.27,5147.5
XS Rating Curve= 0 ,0
Exp/Cntr=0.3,0.1

Type RM Length L Ch R = 1 ,70077   ,8767,8767,8767
BEGIN DESCRIPTION:
LOWER NUECES 72.0
END DESCRIPTION:
XS GIS Cut Line= 6
      2395031.13     13168074.87      2397816.08     13164398.44
      2400168.01     13160502.91      2404509.09     13149182.99
      2405273.72      13136868.9      2404112.29     13130190.33
#Sta/Elev= 30
-25530.9   71.02-25392.5   62.02-25099.1   76.31-24699.9   60.03-23592.9   76.99
-22900.2   49.88-22221.9   78.96-21992.1   75.76-21780.8   63.44-21469.9   79.47
-20421.3   80.09-19828.3   58.55-18971.9    50.9  -18463   27.45-17375.2   48.64
  -16547   50.62-16077.5   46.99-15647.7    16.7-12339.3    4.151235.119    4.44
    1855   13.01  4959.1    3.36  5089.6   10.576314.131   13.17  7634.5   63.05
  8532.2   78.87 10927.8   84.88 12037.4   84.13   14660   80.85 14872.1   80.45
#Mann= 15 ,-1 , 0
-25530.9      .1       0-24699.9      .1       0-22900.2      .1       0
-21992.1     .05       0-21469.9      .1       0-19828.3     .16       0
-18986.7      .1       0-17092.3      .1       0-14234.2     .05       0
  5089.6     .07       0    6579     .05       0  8532.2      .1       0
 10927.8     .05       0 12037.4     .05       0   14660     .05       0
Bank Sta=1855,6314.131
XS Rating Curve= 0 ,0
Exp/Cntr=0.3,0.1

Type RM Length L Ch R = 1 ,61310   ,9704,9704,9704
BEGIN DESCRIPTION:
LOWER NUECES 73.0
END DESCRIPTION:
XS GIS Cut Line= 4
      2402028.02     13172605.25      2402189.25      13160729.4
      2412368.47     13138274.59      2411383.27     13127532.22
#Sta/Elev= 30
-29942.8   96.63-25737.8   98.46-24749.6   98.87-24663.9  111.25-24613.9   97.91
-22066.5   91.68-19709.9   66.51-18431.6   49.13-17853.1   47.63-17123.3   12.91
-16973.3   11.37-3436.05    2.83  4999.8    3.69  5051.5   12.93  5092.2   33.26
  5126.2   65.25  5257.4   58.26  5334.1    41.7  5633.1   75.18  5839.4   80.98
    7830   80.64  9626.4   81.93 10321.8   79.31 10392.1   93.42   10603   94.53
 10705.6   81.26 12983.4    76.9 13213.9   68.77 14874.9   75.62 17375.9    73.9
#Mann= 12 ,-1 , 0
-29942.8     .05       0-25737.8     .08       0-24749.6     .05       0
-22066.5      .1       0-19709.9      .1       0-18431.6      .1       0
-16973.3     .05       0  4999.8     .07       0    7830     .05       0
  9626.4     .15       0 12983.4     .05       0 14874.9     .05       0
Bank Sta=-17123.3,5051.5
XS Rating Curve= 0 ,0
Exp/Cntr=0.3,0.1

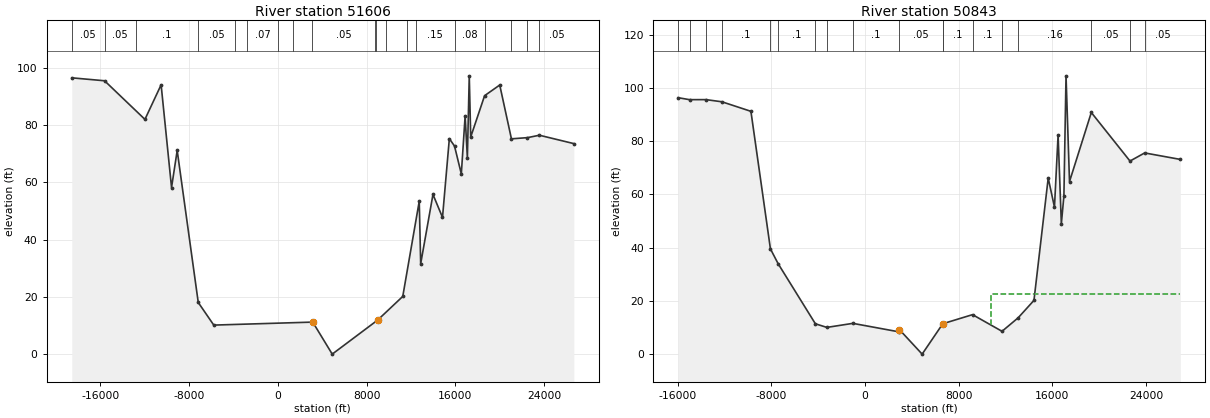
Type RM Length L Ch R = 1 ,51606   ,763,763,763
BEGIN DESCRIPTION:
LOWER NUECES 74.0
END DESCRIPTION:
XS GIS Cut Line= 6
      2402568.68     13170082.54      2402507.44     13166566.13
      2408390.83     13154410.86      2412915.65     13143745.09
      2413279.91     13137526.07      2412196.86     13127181.04
#Sta/Elev= 30
-18570.1   96.62-15615.3   95.59-11975.1   82.08-10516.1   94.18-9576.76   58.24
-9067.11   71.19 -7168.4      18-5769.43   10.09    3092   11.13  3138.4   11.22
  4907.9    -.07 9003.35   11.8511265.66   20.1212751.33   53.4212881.08   31.56
13988.91   55.8114847.23   47.78 15464.3   75.34 15929.3   72.75 16543.6      63
 16887.7   83.28 17088.8   68.65 17259.7   97.32 17390.5   75.92 18642.4   90.37
 20006.7    94.1 21060.4   75.27 22507.4   75.69 23580.5   76.53 26686.8    73.6
#Mann= 19 ,-1 , 0
-18570.1     .05       0-15615.3     .05       0-12804.2      .1       0
   -7189     .05       0 -3824.8      .1       0 -2814.4     .07       0
    50.7     .07       0  1404.1     .07       0    3092     .05       0
  8753.1     .07       0  8893.7     .05       0  9795.6     .15       0
 11605.5     .15       0   12427     .15       0 15929.3     .08       0
 18642.4     .05       0 21060.4      .1       0 22507.4     .05       0
 23580.5     .05       0
Bank Sta=3138.4,9003.35
XS Rating Curve= 0 ,0
Exp/Cntr=0.3,0.1

Type RM Length L Ch R = 1 ,50843   ,2480,2480,2480
BEGIN DESCRIPTION:
LOWER NUECES 75.0
END DESCRIPTION:
XS GIS Cut Line= 6
      2403137.78     13167684.72      2409123.55     13156423.86
      2413415.51     13143546.55      2414003.39     13138308.48
      2413096.19     13134375.39      2412349.55      13127165.4
#Sta/Elev= 30
-15963.7   96.38-15001.2   95.65  -13591   95.66-12232.7   94.85 -9753.8   91.26
   -8087   39.48 -7425.5   33.88 -4246.4   11.29 -3265.2    9.93 -1046.8   11.45
    2904    8.25  2936.2    9.09  4875.5    -.13    6637    11.3  6640.9   11.31
  9181.4   14.73 11701.1    8.46 13079.4   13.55 14429.3    20.1   15646   66.13
 16181.2   55.21 16490.9   82.34   16768   48.94   16987   59.41 17168.4  104.62
 17465.8   64.82 19328.5   90.82 22633.9   72.54 23888.5    75.6 26932.6   73.16
#Mann= 18 ,-1 , 0
-15963.7     .05       0-15001.2     .05       0  -13591     .05       0
-12232.7      .1       0   -8087     .16       0 -7425.5      .1       0
 -4246.4     .05       0 -3265.2     .07       0 -1046.8      .1       0
    2904     .05       0  6640.9     .07       0  6640.9      .1       0
  9181.4      .1       0 11701.1      .1       0 13079.4     .16       0
 19328.5     .05       0 22633.9     .05       0 23888.5     .05       0
#XS Ineff= 2 , 0
                        10798.61           22.52
Permanent Ineff=
       F       F
Bank Sta=2936.2,6637
XS Rating Curve= 0 ,0
Exp/Cntr=0.3,0.1