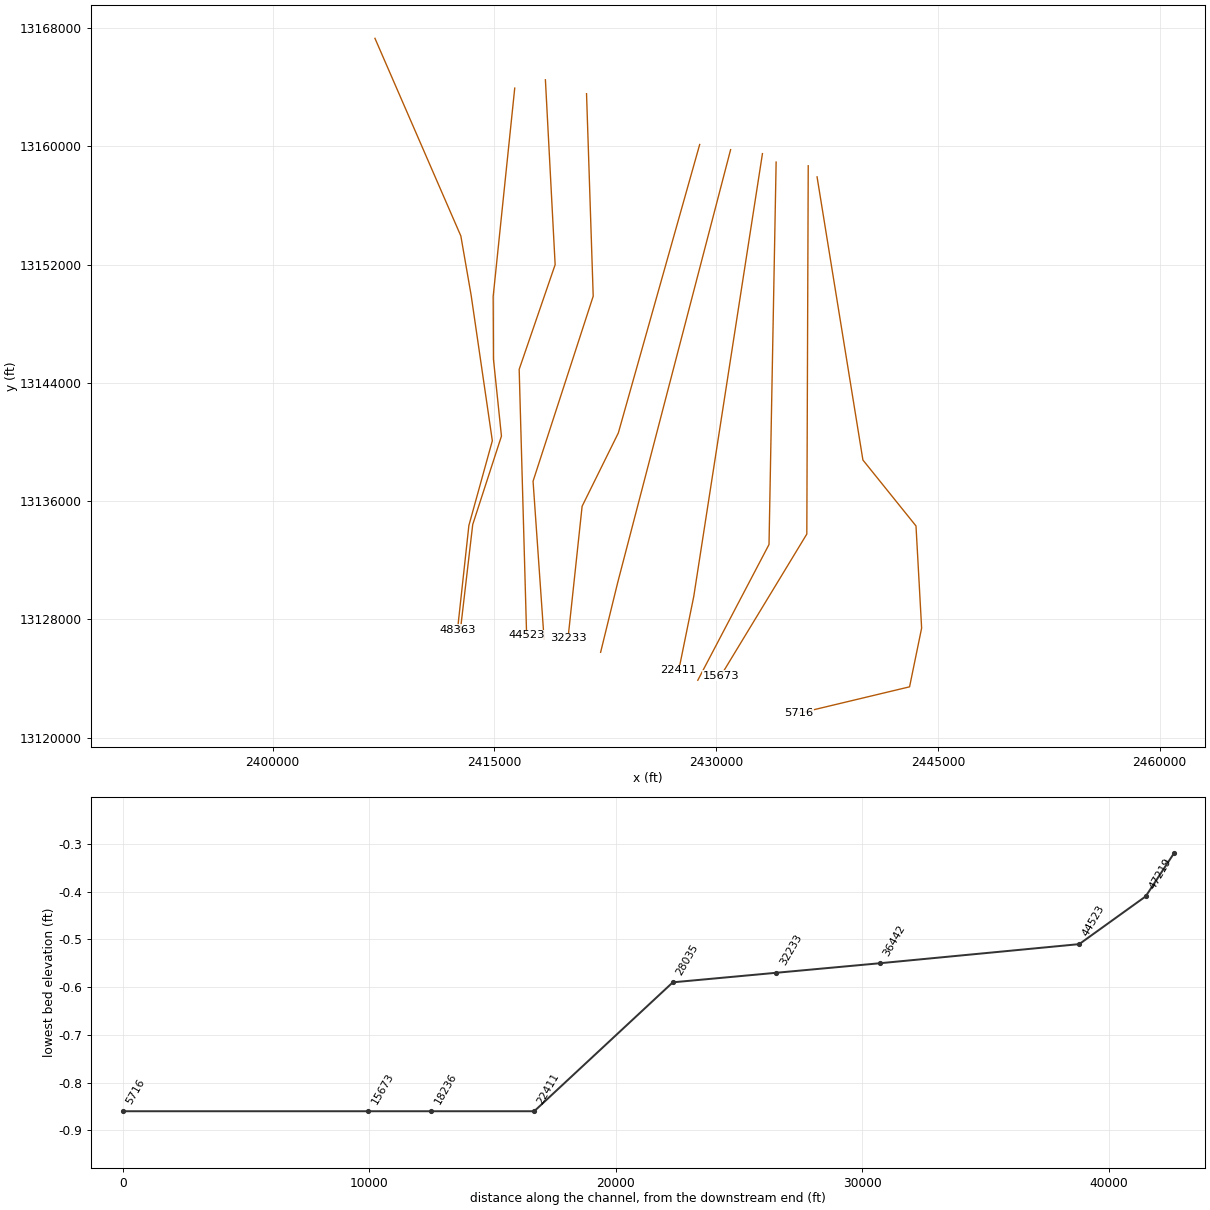
HEC-RAS study NUECES RIVER.prj: NUECES RIVER Base Level Engineering

--- NUECES RIVER.g01 (geometry) --- (continued)

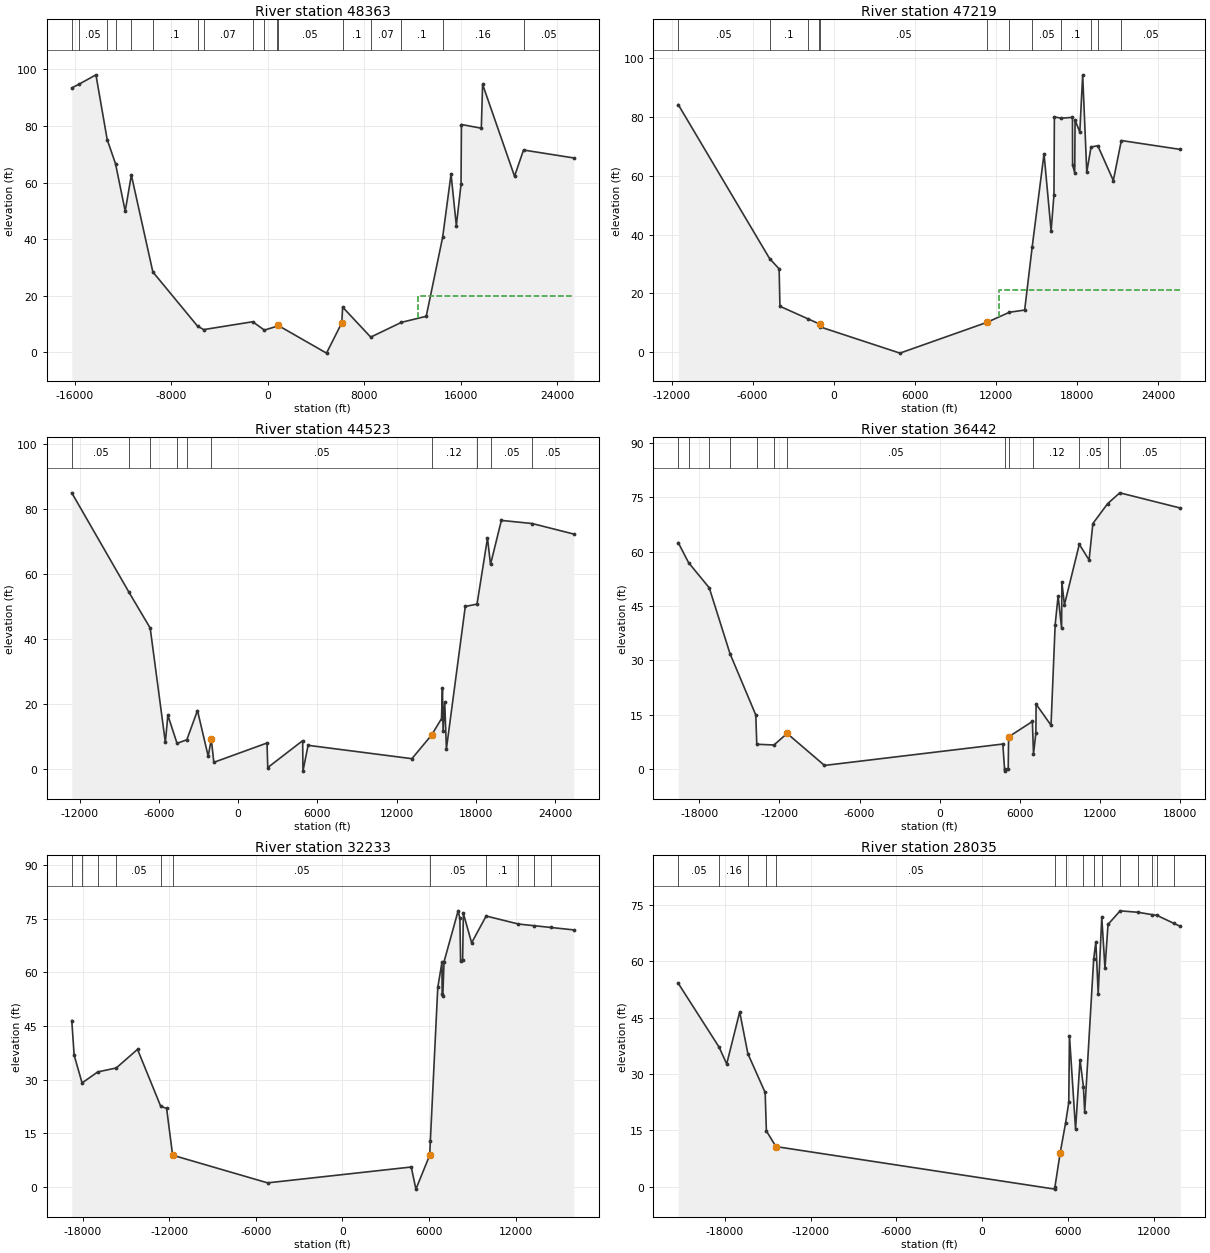
Type RM Length L Ch R = 1 ,48363   ,1144,1144,1144
BEGIN DESCRIPTION:
LOWER NUECES 76.0
END DESCRIPTION:
XS GIS Cut Line= 6
      2406915.18     13167315.58      2412726.45     13153943.31
      2413421.11     13149943.52      2414856.88     13140088.04
      2413269.94     13134354.52      2412500.86     13127296.37
#Sta/Elev= 30
-16252.8   93.48-15656.4   94.77-14247.1    98.1-13314.8   75.19-12623.2   66.66
  -11820   49.87-11310.6   62.66 -9526.6   28.39 -5819.1    9.23 -5311.3       8
 -1242.5   10.78    -278    7.82   785.7     9.2     831    9.56  4879.7    -.32
  6146.3   10.41  6216.3   15.96  8546.5    5.34 11095.1   10.57 13150.9   12.71
 14514.1    40.7   15209   62.96 15647.6   44.79 16036.4   59.33 16070.7   80.53
 17720.4   79.22 17826.5   94.73 20476.4   62.23 21221.7   71.51 25395.8    68.7
#Mann= 17 ,-1 , 0
-16252.8     .05       0-15656.4     .05       0-13314.8      .1       0
-12623.2      .1       0-11310.6      .1       0 -9526.6      .1       0
 -5819.1      .1       0 -5311.3     .07       0 -1242.5     .07       0
    -278     .07       0   785.7     .07       0     831     .05       0
  6216.3      .1       0  8546.5     .07       0 11095.1      .1       0
 14514.1     .16       0 21221.7     .05       0
#XS Ineff= 2 , 0
                           12500           19.74
Permanent Ineff=
       F       F
Bank Sta=831,6146.3
XS Rating Curve= 0 ,0
Exp/Cntr=0.3,0.1

Type RM Length L Ch R = 1 ,47219   ,2696,2696,2696
BEGIN DESCRIPTION:
LOWER NUECES 77.0
END DESCRIPTION:
XS GIS Cut Line= 6
      2416372.45     13163948.42      2414912.57       13149842.
      2414933.02     13145605.26      2415473.87     13140403.69
      2413530.09     13134420.89      2412696.33     13127275.68
#Sta/Elev= 30
-11502.8   84.29 -4748.1   31.83 -4041.6    28.3 -3981.3   15.56   -1900   11.26
 -1094.8    9.59 -1017.2    9.43 -1012.2    8.54  4893.9    -.41 11312.5   10.05
 12995.3   13.52 14118.4   14.27 14676.6   35.86 15550.6   67.53 16074.5   41.24
 16284.8   53.53 16316.3   80.09 16809.3   79.66 17653.8   79.92 17662.2   63.77
 17819.9   61.02 17845.6   78.96 18197.1   74.96 18408.7   94.43 18711.9   61.28
 19027.2   69.84 19526.7   70.27 20675.1    58.4 21268.7   72.04 25629.7   69.01
#Mann= 12 ,-1 , 0
-11502.8     .05       0 -4748.1      .1       0   -1900     .07       0
 -1094.8     .07       0 -1012.2     .05       0 11312.5     .05       0
 12995.3      .1       0 14676.6     .05       0 16809.3      .1       0
 19027.2      .1       0 19526.7     .05       0 21268.7     .05       0
#XS Ineff= 2 , 0
                        12218.75            21.1
Permanent Ineff=
       F       F
Bank Sta=-1017.2,11312.5
XS Rating Curve= 0 ,0
Exp/Cntr=0.3,0.1

Type RM Length L Ch R = 1 ,44523   ,8081,8081,8081
BEGIN DESCRIPTION:
LOWER NUECES 78.0
END DESCRIPTION:
XS GIS Cut Line= 4
      2418447.44     13164511.36      2419106.08     13152000.81
      2416672.76     13144919.09      2417176.41     13126931.92
#Sta/Elev= 30
-12596.4   84.97 -8262.2   54.41 -6658.9   43.43 -5512.1    8.32 -5321.8   16.68
 -4626.9    8.02   -3886    9.12 -3078.7   18.11 -2267.6    4.05 -2033.4    9.35
 -1843.1    2.19  2185.4    8.13  2240.8     .59  4884.2    8.85  4905.6    -.51
  5293.8    7.42 13154.1    3.31 14644.6   10.58 15394.9    15.6   15465   24.99
   15515   11.77 15637.8   20.76 15765.1    6.31 17195.6   50.07 18084.8   50.79
 18876.3   71.06 19105.4   62.98 19927.3    76.5 22261.8   75.54 25413.8    72.3
#Mann= 10 ,-1 , 0
-12596.4     .05       0 -8262.2     .05       0 -6658.9      .1       0
 -4626.9     .07       0   -3886     .16       0 -2033.4     .05       0
 14644.6     .12       0 18084.8     .05       0 19105.4     .05       0
 22261.8     .05       0
Bank Sta=-2033.4,14644.6
XS Rating Curve= 0 ,0
Exp/Cntr=0.3,0.1

Type RM Length L Ch R = 1 ,36442   ,4209,4209,4209
BEGIN DESCRIPTION:
LOWER NUECES 79.0
END DESCRIPTION:
XS GIS Cut Line= 4
      2421230.16     13163569.83       2421681.7      13149871.1
      2417612.26     13137352.78      2418358.46     13126660.81
#Sta/Elev= 30
-19578.7   62.46-18806.6   56.95-17255.5   49.98-15702.5   31.84-13772.6   14.93
-13698.3    6.86-12413.7    6.66-11425.5    9.84 -8629.8    1.02  4720.6    6.92
  4862.6    -.55  4865.9    -.05  5123.7    -.05  5155.5     8.9  6933.7   13.14
    7017    4.17  7194.5    9.95  7212.7   17.92  8329.1    12.1  8639.8   39.85
  8860.4   47.78    9121   38.84    9141   51.61  9331.5   45.29   10447      62
 11178.2   57.67 11462.1   67.72 12570.2   73.22 13478.1   76.19 18008.6      72
#Mann= 13 ,-1 , 0
-19578.7     .05       0-18806.6     .05       0-17255.5     .05       0
-15702.5     .05       0-13698.3     .05       0-12413.7     .05       0
-11425.5     .05       0  4865.9     .05       0  5155.5     .07       0
    7017     .12       0   10447     .05       0 12570.2     .05       0
 13478.1     .05       0
Bank Sta=-11425.5,5155.5
XS Rating Curve= 0 ,0
Exp/Cntr=0.3,0.1

Type RM Length L Ch R = 1 ,32233   ,4198,4198,4198
BEGIN DESCRIPTION:
LOWER NUECES 80.0
END DESCRIPTION:
XS GIS Cut Line= 4
      2428886.82     13160134.18      2423381.58     13140616.37
      2420931.17     13135655.64      2419976.18     13126710.07
#Sta/Elev= 30
-18766.4   46.53-18600.8   36.84-18051.4    29.1  -16966   32.17-15683.1   33.28
-14207.9   38.48-12603.2    22.6-12190.7   21.96-11774.7    8.91 -5189.2    1.18
  4769.2    5.61  5092.4    -.57  6047.6    8.89  6092.5   12.79  6608.7   55.77
  6899.6   62.83  6911.6   53.84  6956.5   53.37  7044.1   62.98  8020.2   77.18
  8140.9   75.06  8191.2   63.05    8332   63.52  8382.2   76.48  8955.5   68.24
  9962.3   75.73 12203.4   73.49 13253.9   73.04 14450.8   72.53 16042.3   71.85
#Mann= 11 ,-1 , 0
-18766.4     .16       0-18051.4     .12       0  -16966     .05       0
-15683.1     .05       0-12603.2     .16       0-11774.7     .05       0
  6092.5     .05       0  9962.3      .1       0 12203.4     .05       0
 13253.9      .1       0 14450.8     .05       0
Bank Sta=-11774.7,6047.6
XS Rating Curve= 0 ,0
Exp/Cntr=0.3,0.1

Type RM Length L Ch R = 1 ,28035   ,5624,5624,5624
BEGIN DESCRIPTION:
LOWER NUECES 81.0
END DESCRIPTION:
XS GIS Cut Line= 3
       2430978.1     13159782.53      2423340.98     13130504.13
      2422183.07     13125775.29
#Sta/Elev= 30
-21259.4   54.13-18398.4   37.14-17869.7   32.68-16959.3   46.51-16385.5    35.4
-15179.1    25.1-15091.2   14.86-14423.1   10.72  5089.1    -.59  5092.4    -.09
  5466.1    9.14  5839.3   16.96  6062.9   22.47  6112.5   40.19  6538.4   15.31
  6851.9   33.79  7086.9   26.68    7177   19.87  7807.6   60.64  7959.4   65.16
  8121.4   51.33  8373.1   71.65  8596.8   58.08  8809.8   69.78  9658.1   73.39
 10915.3      73 11913.6   72.36 12243.3   72.17 13409.3   70.07 13867.2   69.27
#Mann= 15 ,-1 , 0
-21259.4     .05       0-18398.4     .16       0-16385.5     .05       0
-15091.2      .1       0-14423.1     .05       0  5092.4     .05       0
  5839.3     .05       0  7086.9     .05       0  7807.6     .16       0
  8373.1     .16       0  9658.1     .08       0 10915.3      .1       0
 11913.6      .1       0 12243.3     .05       0 13409.3     .05       0
Bank Sta=-14423.1,5466.1
XS Rating Curve= 0 ,0
Exp/Cntr=0.3,0.1

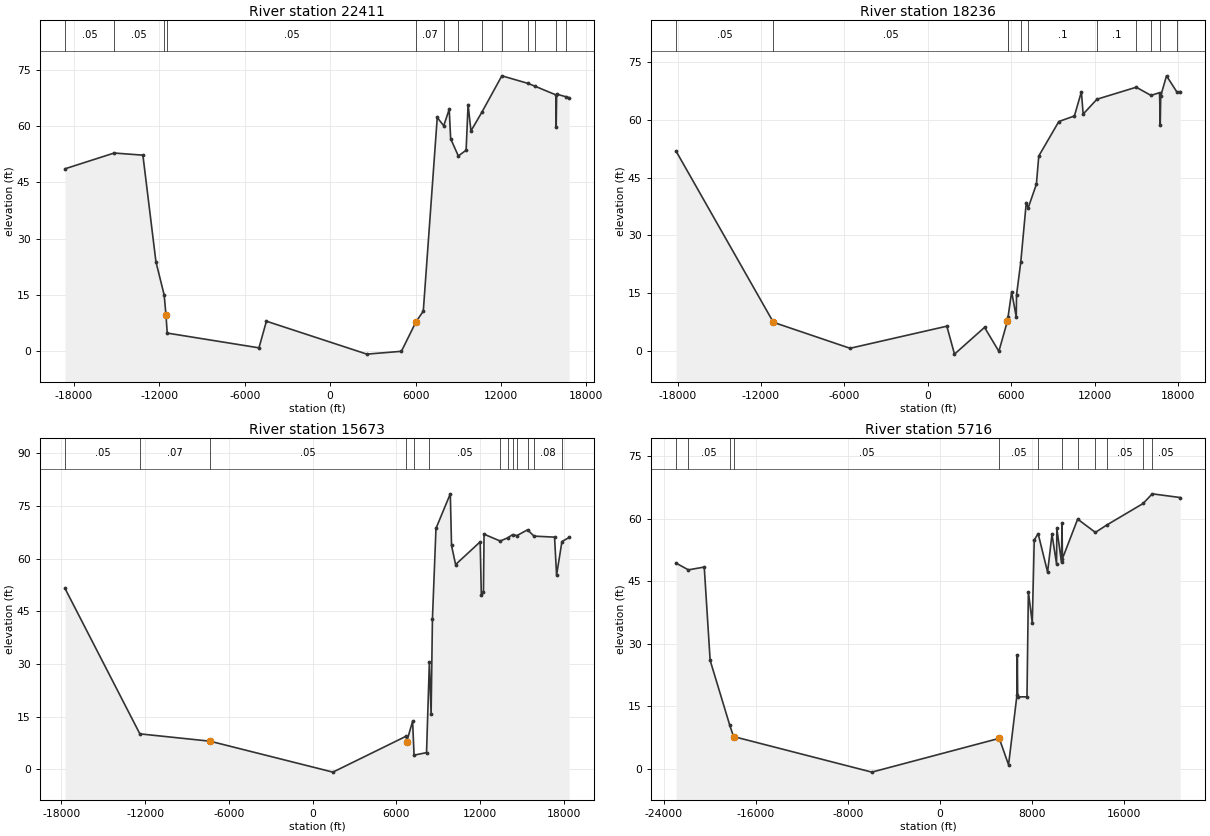
Type RM Length L Ch R = 1 ,22411   ,4175,4175,4175
BEGIN DESCRIPTION:
LOWER NUECES 82.0
END DESCRIPTION:
XS GIS Cut Line= 3
       2433132.5     13159515.19      2428485.53     13129556.65
      2427468.05     13124551.22
#Sta/Elev= 30
  -18632   48.62-15178.4   52.83  -13159   52.26-12241.5   23.78-11661.3   14.89
-11538.3    9.62-11448.8    4.76   -5003     .82 -4478.9    7.93  2576.7    -.86
  5005.7    -.11 6027.78    7.74  6543.8   10.62  7524.1   62.32  7979.2    60.1
  8365.4   64.52  8466.6   56.64  9005.7   52.05  9552.3   53.58    9691   65.78
  9893.4   58.72 10664.1   63.76 12063.7   73.44 13893.7   71.43 14390.6   70.67
 15858.2   68.36 15881.1   59.77 15915.1   68.54   16597   67.83 16792.6   67.62
#Mann= 13 ,-1 , 0
  -18632     .05       0-15178.4     .05       0-11661.3     .07       0
-11448.8     .05       0 6027.78     .07       0  7979.2      .1       0
  9005.7     .15       0 10664.1      .1       0 12063.7     .15       0
 13893.7      .1       0 14390.6     .08       0 15881.1     .05       0
   16597     .15       0
Bank Sta=-11538.3,6027.78
XS Rating Curve= 0 ,0
Exp/Cntr=0.3,0.1

Type RM Length L Ch R = 1 ,18236   ,2563,2563,2563
BEGIN DESCRIPTION:
LOWER NUECES 83.0
END DESCRIPTION:
XS GIS Cut Line= 3
      2434058.31     13158943.91      2433576.44      13133068.9
      2428758.94     13123885.61
#Sta/Elev= 30
-18106.4   51.89-11108.2    7.41 -5597.2     .66    1364     6.4  1913.9    -.86
  4074.5    6.09  5104.7    -.13  5724.8     7.8    5766    8.83  6024.8   15.33
  6354.9    8.79  6374.9    14.5  6679.9   23.06    7075    38.5  7208.4   37.09
  7803.1   43.29  7973.9   50.62  9417.8   59.58 10536.4   61.02 11038.9   67.31
 11164.7    61.5 12155.7   65.37 14981.5   68.49 16043.4   66.36 16659.3   67.08
 16707.7   58.75 16741.6   66.22 17159.4   71.45 17906.5   67.24 18143.3   67.36
#Mann= 11 ,-1 , 0
-18106.4     .05       0-11108.2     .05       0    5766     .07       0
    5766      .1       0  6679.9     .16       0  7208.4      .1       0
 12155.7      .1       0 14981.5      .1       0 16043.4      .1       0
 16659.3     .05       0 17906.5     .05       0
Bank Sta=-11108.2,5724.8
XS Rating Curve= 0 ,0
Exp/Cntr=0.3,0.1

Type RM Length L Ch R = 1 ,15673   ,9957,9957,9957
BEGIN DESCRIPTION:
LOWER NUECES 84.0
END DESCRIPTION:
XS GIS Cut Line= 3
        2436230.     13158694.03      2436134.28     13133775.93
      2430320.28     13124197.08
#Sta/Elev= 30
-17744.1   51.53-12380.1   10.05 -7349.9    7.96    1453    -.86  6713.3    9.41
  6733.3    7.73  7163.3   13.65  7266.4    3.98  8160.8     4.7  8362.7   30.43
  8488.4   15.77  8583.4   42.82  8837.3   68.64  9863.6    78.5  9951.9   63.77
 10242.7   58.33 12004.3   64.81 12086.1   49.63 12238.3    50.4 12281.8   66.99
 13438.9   65.04 13976.8   65.95 14320.9   66.85   14643    66.6 15398.7   68.24
 15860.5   66.44 17333.3   66.15 17478.9   55.34 17861.9   64.88 18379.4   66.07
#Mann= 13 ,-1 , 0
-17744.1     .05       0-12380.1     .07       0 -7349.9     .05       0
  6713.3     .07       0  7266.4     .05       0  8362.7     .05       0
 13438.9      .1       0 13976.8     .05       0 14320.9     .08       0
   14643     .08       0 15398.7      .1       0 15860.5     .08       0
 17861.9     .05       0
Bank Sta=-7349.9,6733.3
XS Rating Curve= 0 ,0
Exp/Cntr=0.3,0.1

Type RM Length L Ch R = 1 ,5716    ,0,0,0
BEGIN DESCRIPTION:
LOWER NUECES 85.0
END DESCRIPTION:
XS GIS Cut Line= 6
      2436827.32     13157943.26      2439929.39      13138786.6
      2443521.26     13134323.97      2443902.21     13127412.35
      2443085.88     13123439.53      2435575.62      13121643.6
#Sta/Elev= 30
-22946.1   49.32  -21875    47.7-20494.3   48.37-19981.3   25.97-18279.9   10.44
-17946.4    7.68 -5918.5    -.86  5158.6    7.25  5969.8      .9  6700.9   17.64
  6730.9   27.34  6766.1    17.2  7572.2   17.22  7692.4   42.44  8032.9   34.93
  8203.2   54.89  8541.6   56.38  9364.8   47.15  9747.4   56.24 10145.6   49.06
   10166   57.66 10574.3   49.49 10615.2   58.87 10658.4   50.41 11978.6   59.88
 13519.3   56.69   14521   58.48 17672.6   63.63 18464.3   65.95 20896.9   65.06
#Mann= 12 ,-1 , 0
-22946.1     .05       0  -21875     .05       0-18279.9     .07       0
-17946.4     .05       0  5158.6     .05       0  8541.6     .05       0
 10658.4      .1       0 11978.6     .15       0 13519.3      .1       0
   14521     .05       0 17672.6      .1       0 18464.3     .05       0
Bank Sta=-17946.4,5158.6
XS Rating Curve= 0 ,0
Exp/Cntr=0.3,0.1

Chan Stop Cuts=-1
Use User Specified Reach Order=0
Composite Channel Slope=5