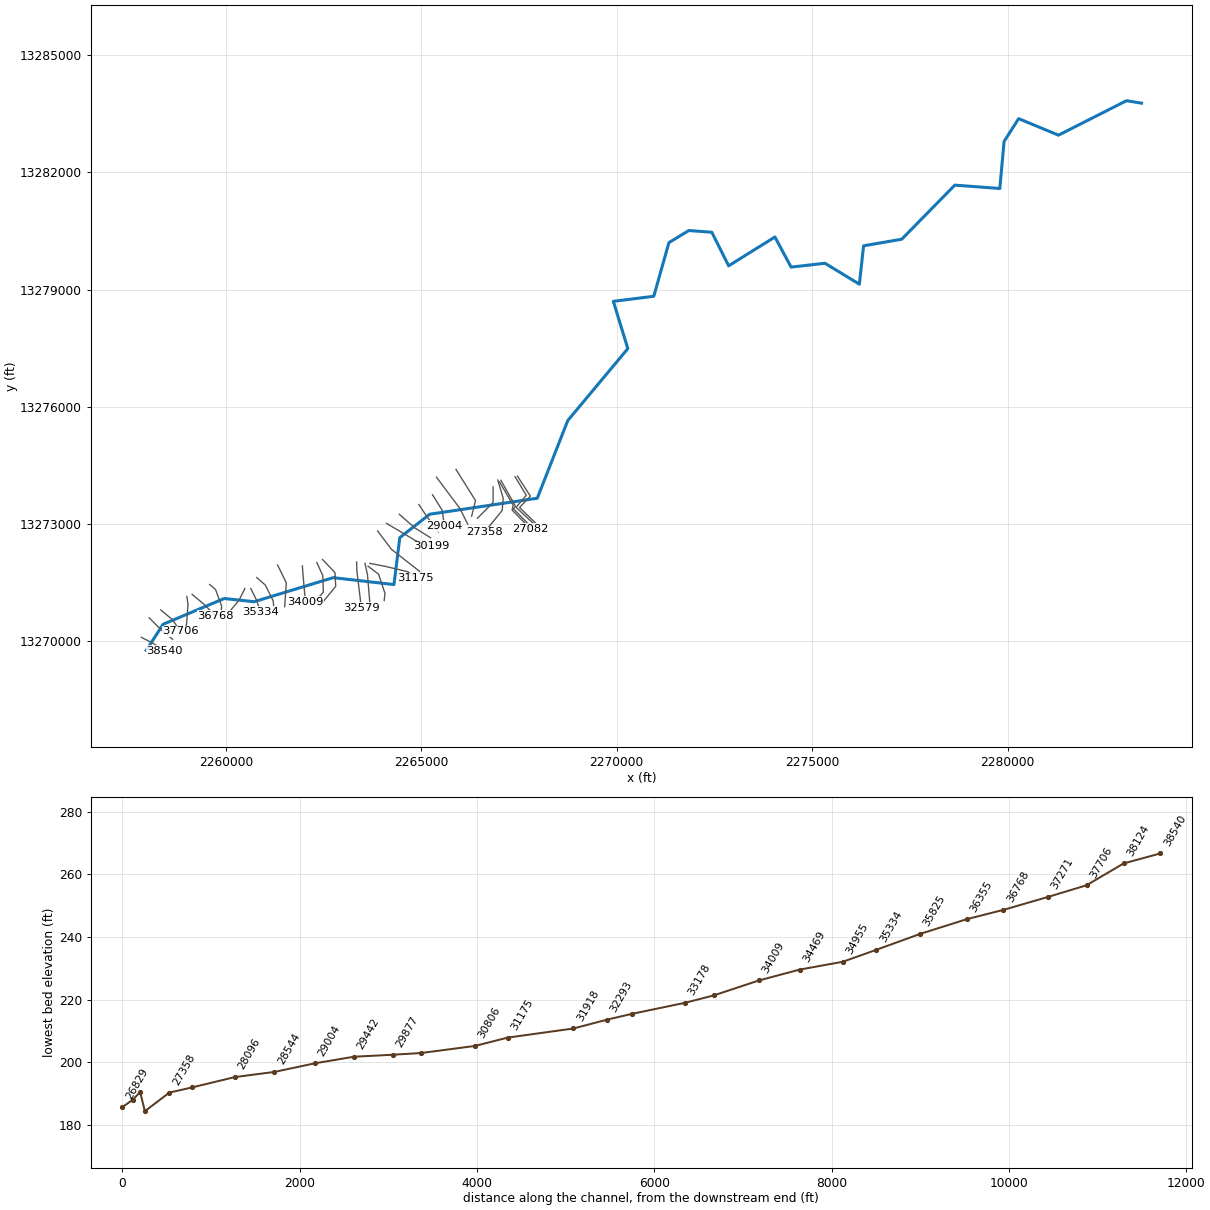
--- GILDEN CREEK.prj (project) ---

Proj Title=GILDEN CREEK Base Level Engineering
Current Plan=p01
Default Exp/Contr=0.3,0.1
English Units
Geom File=g01
Flow File=f01
Plan File=p01
Y Axis Title=Elevation
X Axis Title(PF)=Main Channel Distance
X Axis Title(XS)=Station
BEGIN DESCRIPTION:
GILDEN CREEK
END DESCRIPTION:
DSS Export Rating Curves= 0
DSS Export Rating Curve Sorted= 0
DSS Export Volume Flow Curves= 0
DXF OffsetX= 0
DXF OffsetY= 0
DXF ScaleX= 1
DXF ScaleY= 10

--- GILDEN CREEK.p01 (plan) ---

Plan Title=Multiple Run
Short Identifier=Multiple
Geom File=g01
Flow File=f01
Subcritical Flow
K Sum by GR= 0
Std Step Tol= 0.01
Critical Tol= 0.01
Num of Std Step Trials= 20
Max Error Tol= 0.3
Flow Tol Ratio= 0.001
Split Flow NTrial= 30
Split Flow Tol= 0.02
Split Flow Ratio= 0.02
Log Output Level= 0
Friction Slope Method= 1
Unsteady Friction Slope Method= 2
Unsteady Bridges Friction Slope Method= 1
Parabolic Critical Depth
Global Vel Dist=  1 , 1 , 1
Global Log Level= 0
CheckData=True
Encroach Param= -1, 0, 0, 0
BEGIN DESCRIPTION:
Multiple Run
END DESCRIPTION:

--- GILDEN CREEK.f01 (steady flow) ---

Flow Title=Multiple
Number of Profiles=7
Profile Names=10-year,25-year,50-year,1pct_min,100-year,1pct_plu,500-year
River Rch & RM= GILDEN CREEK,Reach-1,38540
     202     279     343     310     420     568     639
River Rch & RM= GILDEN CREEK,Reach-1,32579
     525     762     967     903    1221    1651    1975
River Rch & RM= GILDEN CREEK,Reach-1,27082
     832    1233    1587    1499    2027    2742    3361
River Rch & RM= GILDEN CREEK,Reach-1,24585
     910    1348    1736    1638    2216    2996    3668
River Rch & RM= GILDEN CREEK,Reach-1,18101
    1001    1487    1919    1814    2454    3318    4077
River Rch & RM= GILDEN CREEK,Reach-1,15912
    1060    1575    2032    1920    2597    3512    4311
River Rch & RM= GILDEN CREEK,Reach-1,9210
    1173    1747    2257    2136    2889    3907    4809
River Rch & RM= GILDEN CREEK,Reach-1,7631
    1214    1806    2331    2204    2980    4031    4949
Boundary for River Rch & Prof#=GILDEN CREEK,Reach-1,1
Up Type=0
Dn Type=3
Dn Slope=0.005
Boundary for River Rch & Prof#=GILDEN CREEK,Reach-1,2
Up Type=0
Dn Type=3
Dn Slope=0.005
Boundary for River Rch & Prof#=GILDEN CREEK,Reach-1,3
Up Type=0
Dn Type=3
Dn Slope=0.005
Boundary for River Rch & Prof#=GILDEN CREEK,Reach-1,4
Up Type=0
Dn Type=3
Dn Slope=0.005
Boundary for River Rch & Prof#=GILDEN CREEK,Reach-1,5
Up Type=0
Dn Type=3
Dn Slope=0.005
Boundary for River Rch & Prof#=GILDEN CREEK,Reach-1,6
Up Type=0
Dn Type=3
Dn Slope=0.005
Boundary for River Rch & Prof#=GILDEN CREEK,Reach-1,7
Up Type=0
Dn Type=3
Dn Slope=0.005

--- GILDEN CREEK.g01 (geometry) ---

Geom Title=Existing Conditions
Program Version=4.10

River Reach=GILDEN CREEK    ,Reach-1
Reach XY= 30
      2257962.72     13269761.86      2258396.07      13270431.1
      2259957.88     13271090.72       2260722.2     13271008.71
      2262747.64     13271624.35      2264301.03     13271447.56
      2264451.42     13272650.04      2265216.13     13273248.35
       2267967.3     13273657.77      2268747.72     13275646.86
      2270284.18     13277488.27      2269913.37     13278699.32
       2270948.2     13278828.01      2271335.82     13280202.84
      2271845.25     13280511.44      2272432.08     13280468.06
      2272863.53      13279608.6      2274047.16     13280346.15
      2274461.11     13279575.19      2275326.47     13279673.83
      2276207.52     13279137.62        2276316.     13280120.27
      2277291.98     13280289.41       2278649.1     13281673.51
       2279800.5     13281587.82      2279909.43     13282791.11
      2280281.69       13283376.      2281301.66     13282952.73
      2283040.88     13283835.18      2283426.42     13283772.14

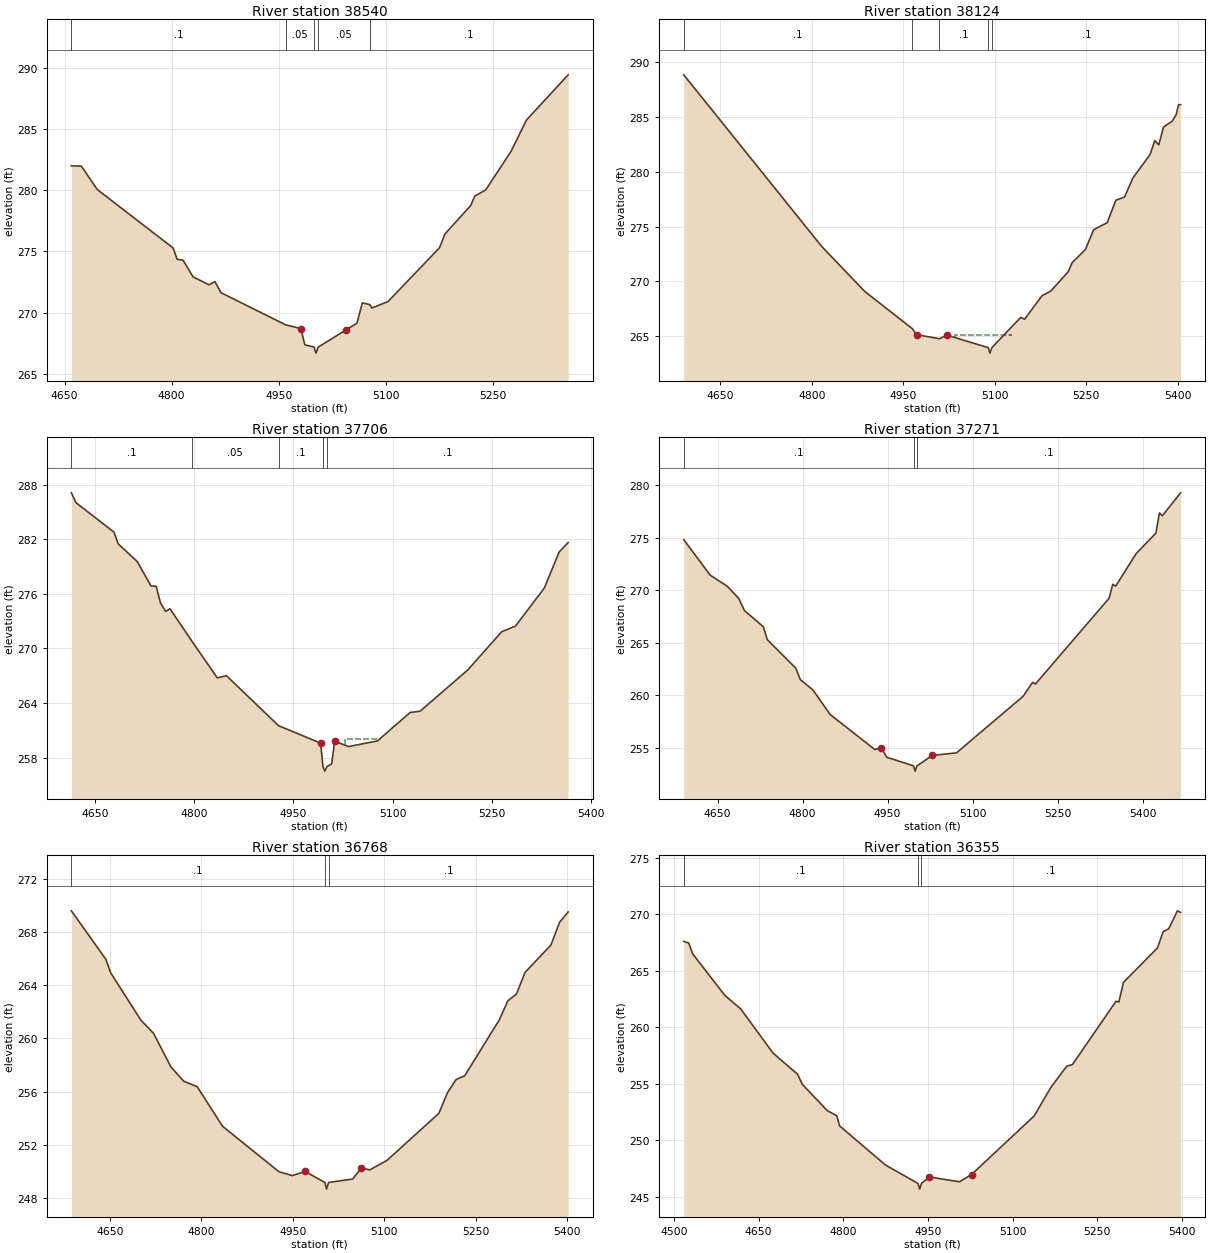
Type RM Length L Ch R = 1 ,38540   ,416,416,416
BEGIN DESCRIPTION:
GILDEN CREEK 72.0
END DESCRIPTION:
XS GIS Cut Line= 3
      2257837.74     13270096.84      2258137.72     13269946.85
      2258437.69     13269746.88
#Sta/Elev= 30
  4659.6     282  4673.6  281.97  4695.9  280.06  4802.1  275.28  4807.7  274.36
  4816.1  274.27  4830.1  272.91  4852.4  272.27  4860.8  272.52  4869.2  271.62
  4959.9  268.99    4981  268.69  4986.6  267.36  4999.5  267.18  5002.2  266.68
  5005.5  267.18  5044.6  268.59  5059.6  269.12  5067.1  270.79  5077.5  270.65
  5080.6  270.37  5103.2   270.9  5175.3   275.3  5182.8  276.42  5218.8  278.74
  5224.8  279.53  5239.9  280.02  5275.9  283.22    5297  285.74  5355.5  289.44
#Mann= 5 ,-1 , 0
  4659.6      .1       0  4959.9     .05       0  4999.5     .04       0
  5005.5     .05       0  5077.5      .1       0
Bank Sta=4981,5044.6
XS Rating Curve= 0 ,0
Exp/Cntr=0.3,0.1

Type RM Length L Ch R = 1 ,38124   ,418,418,418
BEGIN DESCRIPTION:
GILDEN CREEK 71.0
END DESCRIPTION:
XS GIS Cut Line= 3
      2258037.71     13270596.87      2258337.72     13270296.85
      2258637.73     13270046.85
#Sta/Elev= 30
  4589.8  288.82  4816.1  273.18  4886.8  269.08  4964.4  265.71  4971.7  265.15
  5009.2  264.78  5021.2  265.11  5089.2  263.97  5091.9  263.47  5095.2  263.97
  5142.3  266.72  5148.8  266.56  5177.4   268.7  5191.8  269.13  5220.4  270.89
  5226.9  271.72  5248.4   272.9  5262.1  274.71  5284.2  275.35  5298.5   277.4
  5312.8  277.69  5326.5  279.44  5354.5  281.55  5362.3  282.83  5368.8  282.44
  5376.6  284.06  5390.9   284.6  5397.4   285.2  5401.3   286.1  5404.6   286.1
#Mann= 5 ,-1 , 0
  4589.8      .1       0  4964.4     .05       0  5009.2      .1       0
  5089.2     .04       0  5095.2      .1       0
#XS Ineff= 1 ,-1
 5034.38 5128.33  265.09
Permanent Ineff=
       F
Bank Sta=4971.7,5021.2
XS Rating Curve= 0 ,0
Exp/Cntr=0.3,0.1

Type RM Length L Ch R = 1 ,37706   ,435,435,435
BEGIN DESCRIPTION:
GILDEN CREEK 70.0
END DESCRIPTION:
XS GIS Cut Line= 3
      2258337.76     13270796.82      2258637.72     13270546.85
      2258837.71     13270246.87
#Sta/Elev= 30
  4614.3  287.11  4621.4  286.02  4678.7  282.79  4685.2  281.49  4713.8  279.56
  4734.7  276.87  4742.5  276.83    4749     275  4756.8  274.06  4763.3  274.37
  4796.6  270.79  4834.9  266.76  4848.6  267.01  4927.6   261.5  4991.1  259.59
  4994.6  257.01  4997.4  256.51  5000.6  257.01  5007.8  257.31  5012.3   259.8
  5033.3  259.21  5076.9  259.83  5126.5  262.96  5141.5   263.1  5213.6  267.64
  5264.7  271.83  5285.7  272.46  5329.3  276.65  5351.8  280.62  5365.3  281.65
#Mann= 5 ,-1 , 0
  4614.3      .1       0  4796.6     .05       0  4927.6      .1       0
  4994.6     .07       0  5000.6      .1       0
#XS Ineff= 1 ,-1
 5027.28 5082.64     260
Permanent Ineff=
       F
Bank Sta=4991.1,5012.3
XS Rating Curve= 0 ,0
Exp/Cntr=0.3,0.1

Type RM Length L Ch R = 1 ,37271   ,503,503,503
BEGIN DESCRIPTION:
GILDEN CREEK 69.0
END DESCRIPTION:
XS GIS Cut Line= 4
      2259003.81     13271142.93      2259032.28     13270936.51
      2258996.69     13270445.37      2258953.98     13270274.53
#Sta/Elev= 30
  4590.2  274.82  4636.7  271.45    4667  270.39  4687.2  269.23  4697.3  268.07
  4730.6  266.54  4737.7   265.3  4788.1  262.58  4795.9   261.5  4818.3  260.51
  4848.4  258.19  4927.2  254.85  4938.6  255.02  4948.6  254.11  4995.8  253.29
  4998.5  252.79  5001.8  253.29  5028.8  254.28  5071.6  254.53  5189.3  259.92
  5205.9  261.24  5210.9  261.08    5341  269.25  5347.4  270.57  5352.5   270.4
  5388.6  273.49  5423.5  275.44  5429.8  277.36    5435   277.1  5467.1  279.28
#Mann= 3 ,-1 , 0
  4590.2      .1       0  4995.8     .07       0  5001.8      .1       0
Bank Sta=4938.6,5028.8
XS Rating Curve= 0 ,0
Exp/Cntr=0.3,0.1

Type RM Length L Ch R = 1 ,36768   ,413,413,413
BEGIN DESCRIPTION:
GILDEN CREEK 68.0
END DESCRIPTION:
XS GIS Cut Line= 3
      2259137.74     13271196.83      2259437.72     13270946.85
      2259737.69     13270646.89
#Sta/Elev= 30
  4586.7   269.6  4643.3  265.95  4651.1  264.94  4700.6  261.38  4721.4  260.39
    4750  257.85  4770.9  256.78    4793  256.37  4834.6  253.39  4927.1  249.97
  4949.2  249.68    4970  249.99  5002.5  249.16  5005.2  248.66  5008.5  249.16
  5047.9  249.42    5062  250.24  5076.2  250.11  5104.5  250.83  5189.3  254.36
  5203.5  255.91  5217.6  256.91  5231.7  257.19  5288.3  261.38  5302.5  262.83
  5316.6  263.34  5330.7  264.97  5373.2  267.03  5387.3  268.74  5401.4  269.52
#Mann= 3 ,-1 , 0
  4586.7      .1       0  5002.5     .07       0  5008.5      .1       0
Bank Sta=4970,5062
XS Rating Curve= 0 ,0
Exp/Cntr=0.3,0.1

Type RM Length L Ch R = 1 ,36355   ,530,530,530
BEGIN DESCRIPTION:
GILDEN CREEK 67.0
END DESCRIPTION:
XS GIS Cut Line= 4
       2259587.5     13271449.01      2259736.97     13271320.89
      2259893.57     13270893.81      2259872.21     13270666.06
#Sta/Elev= 30
  4517.3  267.59  4526.2  267.44  4532.8  266.51  4589.9  262.83  4618.4  261.61
  4675.5  257.72    4719  255.85  4727.3  254.97  4771.7  252.63  4788.3  252.19
  4793.7  251.28  4874.5  247.84  4932.5   246.2  4935.3   245.7  4938.5   246.2
  4952.8  246.77    5006  246.35  5027.3  246.99  5138.4  252.17  5167.8  254.68
  5196.1  256.57  5206.2  256.71  5283.4   262.3  5288.4  262.23  5296.6  263.97
  5356.8  267.01  5366.9  268.44  5376.9  268.71  5392.2  270.29  5397.8  270.15
#Mann= 3 ,-1 , 0
  4517.3      .1       0  4932.5     .07       0  4938.5      .1       0
Bank Sta=4952.8,5027.3
XS Rating Curve= 0 ,0
Exp/Cntr=0.3,0.1

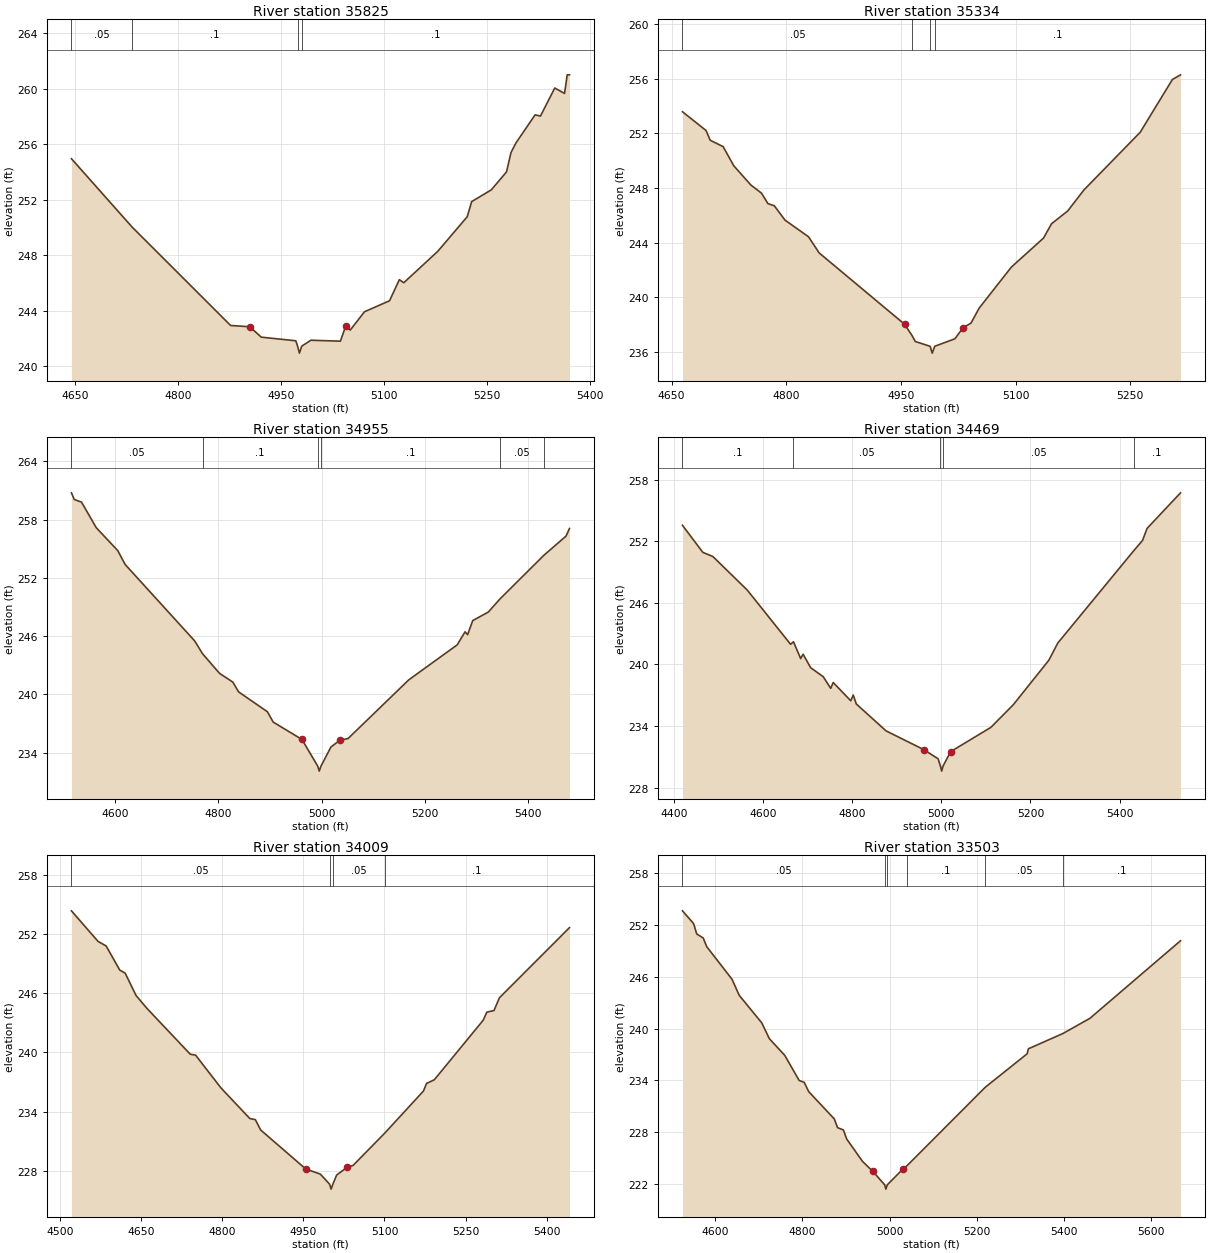
Type RM Length L Ch R = 1 ,35825   ,491,491,491
BEGIN DESCRIPTION:
GILDEN CREEK 66.0
END DESCRIPTION:
XS GIS Cut Line= 3
       2260487.7     13271346.82      2260337.72     13271046.85
      2260087.71     13270746.84
#Sta/Elev= 30
  4644.6  254.96    4733  250.04  4876.6  242.95  4904.5  242.86  4921.3  242.11
  4971.6  241.85  4974.2  241.46  4976.9  240.96  4980.2  241.46  4993.6  241.89
  5036.6  241.82  5044.4  242.92  5050.9  242.62  5071.7  243.94  5108.2  244.73
  5122.5  246.25    5129  246.03  5178.5  248.29  5221.4  250.78  5227.9  251.87
  5256.6  252.72  5278.7  254.01  5285.2   255.4  5292.4  256.09  5320.4  258.12
  5328.2  258.03    5349  260.05  5363.3  259.66  5367.2     261  5370.5     261
#Mann= 4 ,-1 , 0
  4644.6     .05       0    4733      .1       0  4974.2     .07       0
  4980.2      .1       0
Bank Sta=4904.5,5044.4
XS Rating Curve= 0 ,0
Exp/Cntr=0.3,0.1

Type RM Length L Ch R = 1 ,35334   ,379,379,379
BEGIN DESCRIPTION:
GILDEN CREEK 65.0
END DESCRIPTION:
XS GIS Cut Line= 3
       2260637.7      13271346.9      2260787.72     13271046.85
      2260887.73     13270746.84
#Sta/Elev= 30
  4664.1  253.58  4694.9  252.21  4700.5  251.49  4717.3  251.03  4731.2  249.63
  4753.6  248.22  4767.6  247.62  4775.9  246.86  4784.3   246.7  4798.3  245.65
  4829.1  244.43    4843  243.25  4954.8  238.03  4964.7  237.19  4968.8  236.77
  4988.2  236.42  4990.9  235.92  4994.2  236.42  5020.6  236.97  5031.2  237.77
  5041.7  238.12  5052.3  239.21  5094.4  242.21  5136.6  244.34  5147.1  245.39
  5168.2  246.32  5189.3  247.85  5263.1  252.08  5305.2  255.94  5315.8  256.28
#Mann= 4 ,-1 , 0
  4664.1     .05       0  4964.7      .1       0  4988.2     .07       0
  4994.2      .1       0
Bank Sta=4954.8,5031.2
XS Rating Curve= 0 ,0
Exp/Cntr=0.3,0.1

Type RM Length L Ch R = 1 ,34955   ,486,486,486
BEGIN DESCRIPTION:
GILDEN CREEK 64.0
END DESCRIPTION:
XS GIS Cut Line= 4
      2260790.46     13271626.95       2261011.1     13271434.78
      2261210.41     13271036.17       2261231.6     13270810.12
#Sta/Elev= 30
  4515.1  260.76  4520.5  260.08  4534.7   259.8  4563.2  257.17    4605   254.8
  4619.2  253.38    4754  245.51  4769.2  244.19  4802.3  242.16  4827.7  241.28
  4839.1  240.26  4894.8  238.22  4906.2  237.15  4961.9  235.36  4992.6   232.6
  4995.4   232.1  4998.6   232.6    5018  234.58  5034.7  235.26  5051.3  235.46
  5168.9   241.5  5262.7   245.1    5278  246.45    5283  246.15  5292.8   247.6
    5323  248.48  5345.8  249.84  5430.8  254.33  5473.6   256.3  5480.4  257.09
#Mann= 6 ,-1 , 0
  4515.1     .05       0  4769.2      .1       0  4992.6     .07       0
  4998.6      .1       0  5345.8     .05       0  5430.8      .1       0
Bank Sta=4961.9,5034.7
XS Rating Curve= 0 ,0
Exp/Cntr=0.3,0.1

Type RM Length L Ch R = 1 ,34469   ,460,460,460
BEGIN DESCRIPTION:
GILDEN CREEK 63.0
END DESCRIPTION:
XS GIS Cut Line= 3
       2261324.9     13271947.71      2261547.14     13271492.82
      2261505.48     13270881.82
#Sta/Elev= 30
  4418.3  253.55  4464.1  250.91  4486.6  250.51  4563.9  247.24  4661.2  241.96
  4667.7  242.21  4683.8  240.57  4689.3  240.99  4706.3  239.68  4734.4  238.81
  4751.3  237.67  4756.9  238.24  4796.4  236.46  4801.9  237.02  4808.8  236.15
  4875.6  233.53  4960.6   231.7  4992.6  230.81  4997.7  230.11  5000.5  229.61
  5003.7  230.11  5020.8  231.51    5111  233.87  5161.1  236.06  5241.3  240.41
  5261.3  242.08  5431.7  251.06  5451.8  252.08  5461.8  253.24    5537  256.71
#Mann= 5 ,-1 , 0
  4418.3      .1       0  4667.7     .05       0  4997.7     .03       0
  5003.7     .05       0  5431.7      .1       0
Bank Sta=4960.6,5020.8
XS Rating Curve= 0 ,0
Exp/Cntr=0.3,0.1

Type RM Length L Ch R = 1 ,34009   ,506,506,506
BEGIN DESCRIPTION:
GILDEN CREEK 62.0
END DESCRIPTION:
XS GIS Cut Line= 3
       2261957.8     13271925.97      2261979.16     13271648.32
       2262036.1     13271007.71
#Sta/Elev= 30
  4520.8  254.33  4570.1  251.23    4585  250.77  4610.2  248.33  4620.2  248.02
  4640.3  245.76  4660.3  244.46  4740.6  239.81  4750.6  239.71  4797.5  236.39
  4850.9  233.29    4861  233.18    4871  232.13  4954.4  228.18  4981.4  227.66
  4998.5  226.64  5001.3  226.14  5004.5  226.64  5011.6  227.57  5031.6  228.38
  5041.7  228.53  5100.7  231.82  5172.2  236.08  5177.8  236.84  5192.3  237.22
  5282.6  243.24  5289.5  244.07  5302.7  244.23  5312.7  245.52  5442.4  252.63
#Mann= 4 ,-1 , 0
  4520.8     .05       0  4998.5     .03       0  5004.5     .05       0
  5100.7      .1       0
Bank Sta=4954.4,5031.6
XS Rating Curve= 0 ,0
Exp/Cntr=0.3,0.1

Type RM Length L Ch R = 1 ,33503   ,325,325,325
BEGIN DESCRIPTION:
GILDEN CREEK 61.0
END DESCRIPTION:
XS GIS Cut Line= 4
      2262328.41     13272010.15      2262481.17     13271676.85
      2262495.06     13271253.23      2262258.95     13270992.82
#Sta/Elev= 30
  4525.1  253.67  4550.7  252.19  4557.8  250.99  4572.7  250.52  4580.8  249.51
  4638.7  245.74  4655.3  243.87  4706.8  240.69  4724.3  238.85  4759.7  236.91
  4792.7     234  4804.3  233.78  4814.7   232.7  4873.3  229.54  4880.7  228.53
  4894.2  228.26  4901.7  227.21  4937.9  224.62  4961.8  223.45  4988.8   221.9
  4991.5   221.4  4994.8   221.9  5031.8  223.79  5039.3  224.08  5219.8  233.23
  5315.6   237.1  5318.3  237.67  5398.1  239.46  5459.5  241.21  5667.1   250.2
#Mann= 6 ,-1 , 0
  4525.1     .05       0  4988.8     .03       0  4994.8     .05       0
  5039.3      .1       0  5219.8     .05       0  5398.1      .1       0
Bank Sta=4961.8,5031.8
XS Rating Curve= 0 ,0
Exp/Cntr=0.3,0.1

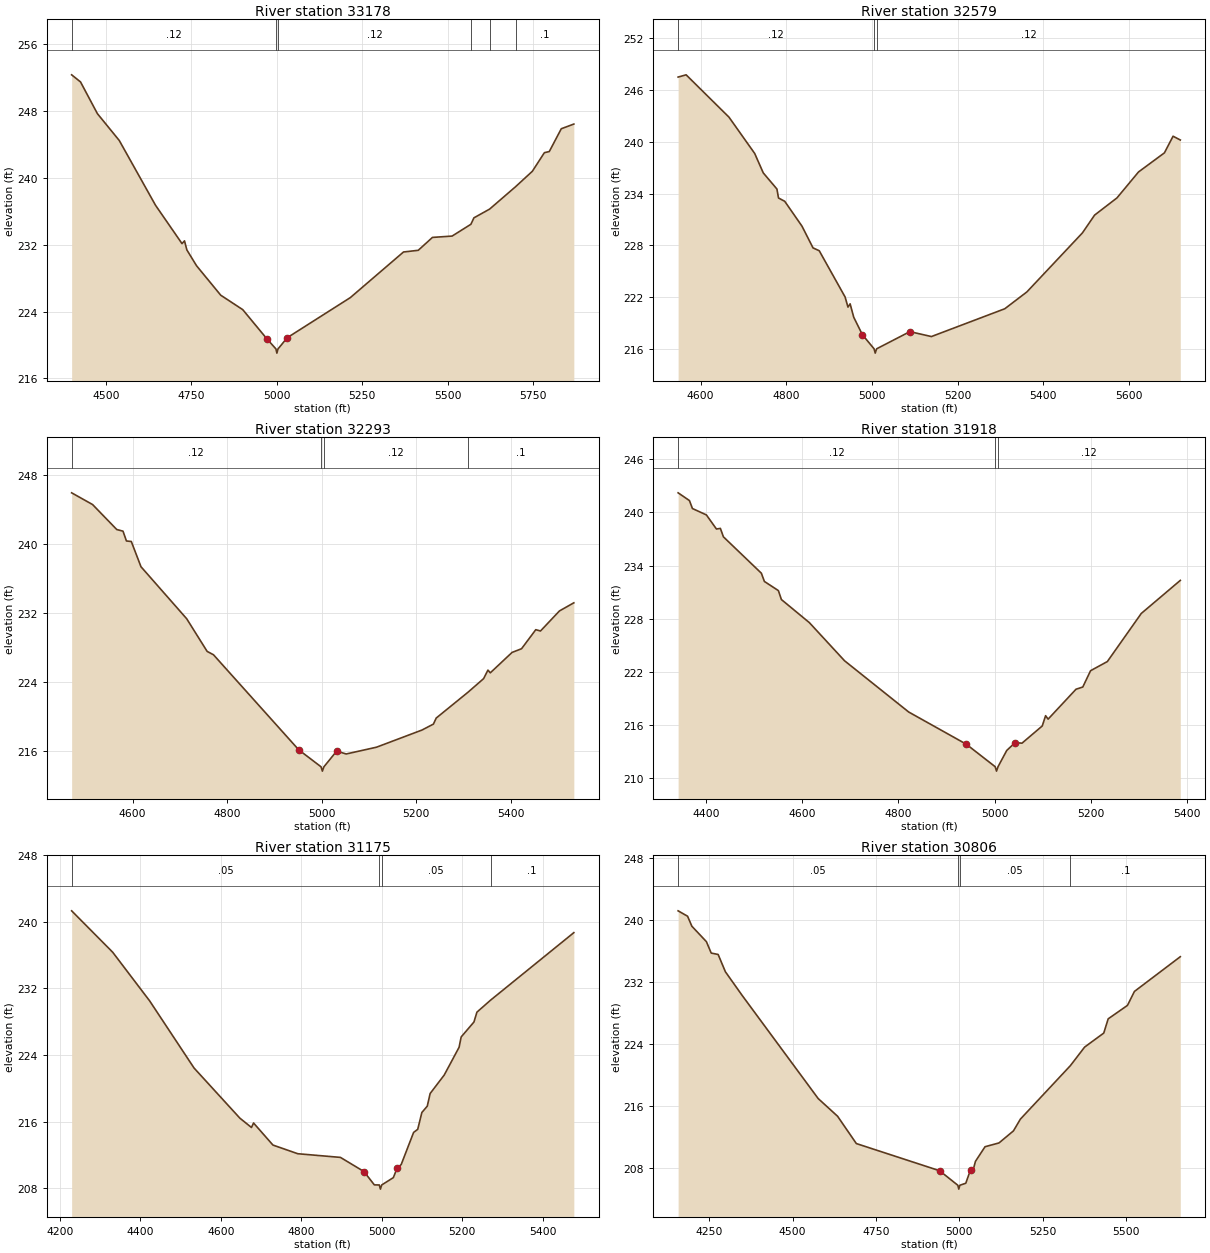
Type RM Length L Ch R = 1 ,33178   ,599,599,599
BEGIN DESCRIPTION:
GILDEN CREEK 60.0
END DESCRIPTION:
XS GIS Cut Line= 4
       2262474.2     13272090.07      2262793.67     13271753.23
      2262811.03     13271402.54      2262397.82     13270895.57
#Sta/Elev= 30
  4399.5  252.27  4425.5  251.42  4474.9  247.63  4538.8  244.43  4644.8   236.7
  4722.4  232.11  4729.7  232.44  4736.6  231.36  4764.9  229.47  4835.7  225.95
  4900.2  224.22  4970.3  220.76  4997.3  219.53    5000  219.03  5003.3  219.53
  5030.3  220.87  5214.9  225.66  5370.5  231.11  5413.6  231.31  5455.2  232.85
  5512.7  233.01  5567.7  234.42  5576.6  235.19  5622.4  236.23  5698.8  238.92
  5747.5  240.75  5782.7  242.97  5797.1  243.11  5832.2  245.83  5868.9  246.39
#Mann= 6 ,-1 , 0
  4399.5     .12       0  4997.3     .07       0  5003.3     .12       0
  5567.7      .1       0  5622.4     .05       0  5698.8      .1       0
Bank Sta=4970.3,5030.3
XS Rating Curve= 0 ,0
Exp/Cntr=0.3,0.1

Type RM Length L Ch R = 1 ,32579   ,286,286,286
BEGIN DESCRIPTION:
GILDEN CREEK 59.0
END DESCRIPTION:
XS GIS Cut Line= 3
      2263345.82     13272025.55      2263352.94     13271790.68
       2263466.6     13270860.07
#Sta/Elev= 30
  4547.4  247.49  4566.1  247.75  4666.1  242.85  4726.2  238.64  4746.2  236.39
  4778.1  234.52  4781.8  233.48  4796.3   233.1  4836.6  230.22  4862.4   227.7
  4876.9  227.37  4937.3  222.01    4944  220.84    4949  221.22  4957.5  219.66
  4977.6  217.65  5004.9  216.01  5007.6  215.51  5010.9  216.01  5088.5     218
  5138.8  217.43  5310.1  220.65  5361.7   222.6  5491.4  229.44  5519.8   231.5
    5572  233.49  5622.4   236.5  5682.8  238.71    5703  240.64  5719.9   240.2
#Mann= 3 ,-1 , 0
  4547.4     .12       0  5004.9     .07       0  5010.9     .12       0
Bank Sta=4977.6,5088.5
XS Rating Curve= 0 ,0
Exp/Cntr=0.3,0.1

Type RM Length L Ch R = 1 ,32293   ,375,375,375
BEGIN DESCRIPTION:
GILDEN CREEK 58.0
END DESCRIPTION:
XS GIS Cut Line= 3
      2263559.36     13271990.03      2263623.43     13271705.26
      2263687.49     13270936.51
#Sta/Elev= 30
  4470.8  245.93  4515.1  244.57  4566.3  241.67  4579.5  241.48  4586.8  240.34
  4597.1  240.28  4617.6  237.35  4714.4  231.31  4757.7  227.52  4771.1  227.13
  4951.7  216.09  4998.9  214.12  5001.7  213.62  5004.9  214.12    5032  215.95
  5052.1  215.61  5116.4   216.4  5212.6  218.39  5236.8  219.08  5242.7  219.78
  5309.8  222.77  5343.1  224.36  5352.2  225.35  5357.2  225.03  5403.3   227.4
  5423.4  227.83  5453.5  230.04  5463.5  229.89  5503.7  232.22  5534.1  233.16
#Mann= 4 ,-1 , 0
  4470.8     .12       0  4998.9     .07       0  5004.9     .12       0
  5309.8      .1       0
Bank Sta=4951.7,5032
XS Rating Curve= 0 ,0
Exp/Cntr=0.3,0.1

Type RM Length L Ch R = 1 ,31918   ,743,743,743
BEGIN DESCRIPTION:
GILDEN CREEK 57.0
END DESCRIPTION:
XS GIS Cut Line= 4
      2263637.63     13271918.83      2263908.15     13271712.38
      2264071.86     13271221.24      2264050.51     13271036.17
#Sta/Elev= 30
    4342   242.2  4365.5  241.33  4371.8  240.43  4400.8  239.71  4421.7  238.12
  4429.9  238.19  4436.2  237.24  4515.1  233.14  4521.4  232.21  4550.5  231.18
  4556.8  230.17  4614.9  227.57  4688.1  223.27  4821.6  217.49  4941.1  213.87
  5001.3  211.33  5004.1  210.83  5007.3  211.33  5025.4  213.16  5042.9  214.05
  5057.1  213.98  5099.2  215.92  5106.2  217.08  5111.4  216.69  5169.4  220.06
  5183.5  220.31  5199.7  222.15  5234.6  223.18  5305.1   228.6  5386.3  232.33
#Mann= 3 ,-1 , 0
    4342     .12       0  5001.3     .07       0  5007.3     .12       0
Bank Sta=4941.1,5042.9
XS Rating Curve= 0 ,0
Exp/Cntr=0.3,0.1

Type RM Length L Ch R = 1 ,31175   ,369,369,369
BEGIN DESCRIPTION:
GILDEN CREEK 56.0
END DESCRIPTION:
XS GIS Cut Line= 4
      2263687.51     13271989.98      2264057.63     13271918.81
      2264655.55     13271776.45       2264853.8     13271613.59
#Sta/Elev= 30
  4229.5  241.32  4331.5  236.35  4423.2  230.52  4533.7  222.45  4647.6  216.43
  4676.4  215.31  4681.6  215.85  4729.8   213.2  4791.5  212.16  4897.5  211.72
    4956  210.02  4981.8  208.42  4994.1  208.41  4996.9  207.91  5000.1  208.41
    5029  209.29  5038.2  210.41  5048.5  210.86  5079.4  214.72  5089.6  215.09
  5099.9  217.11  5113.3  217.87  5120.5  219.39  5155.5  221.61  5192.4  224.94
  5197.6  226.18  5229.3  227.97  5236.8  229.16  5270.8   230.6  5477.6   238.7
#Mann= 4 ,-1 , 0
  4229.5     .05       0  4994.1     .03       0  5000.1     .05       0
  5270.8      .1       0
Bank Sta=4956,5038.2
XS Rating Curve= 0 ,0
Exp/Cntr=0.3,0.1

Type RM Length L Ch R = 1 ,30806   ,607,607,607
BEGIN DESCRIPTION:
GILDEN CREEK 55.0
END DESCRIPTION:
XS GIS Cut Line= 3
      2263881.91     13272819.73      2264237.54     13272349.92
      2264958.31     13271785.01
#Sta/Elev= 30
    4157  241.23  4185.4  240.53  4198.2  239.24  4241.7  237.25  4256.2  235.77
    4277  235.59  4298.6  233.36  4348.7  230.31  4576.7  216.97  4634.9  214.68
  4691.1  211.15  4940.5  207.64  4995.3  205.76  4998.1  205.26  5001.3  205.76
  5019.1  206.02  5033.6  207.79    5040  207.55  5048.1  208.85  5076.8  210.74
  5118.6  211.23    5162  212.79  5182.8  214.31  5332.6  221.22  5375.3  223.62
  5432.6  225.43  5445.9  227.27  5503.7  229.01  5524.5  230.81    5662   235.3
#Mann= 4 ,-1 , 0
    4157     .05       0  4995.3     .03       0  5001.3     .05       0
  5332.6      .1       0
Bank Sta=4940.5,5033.6
XS Rating Curve= 0 ,0
Exp/Cntr=0.3,0.1

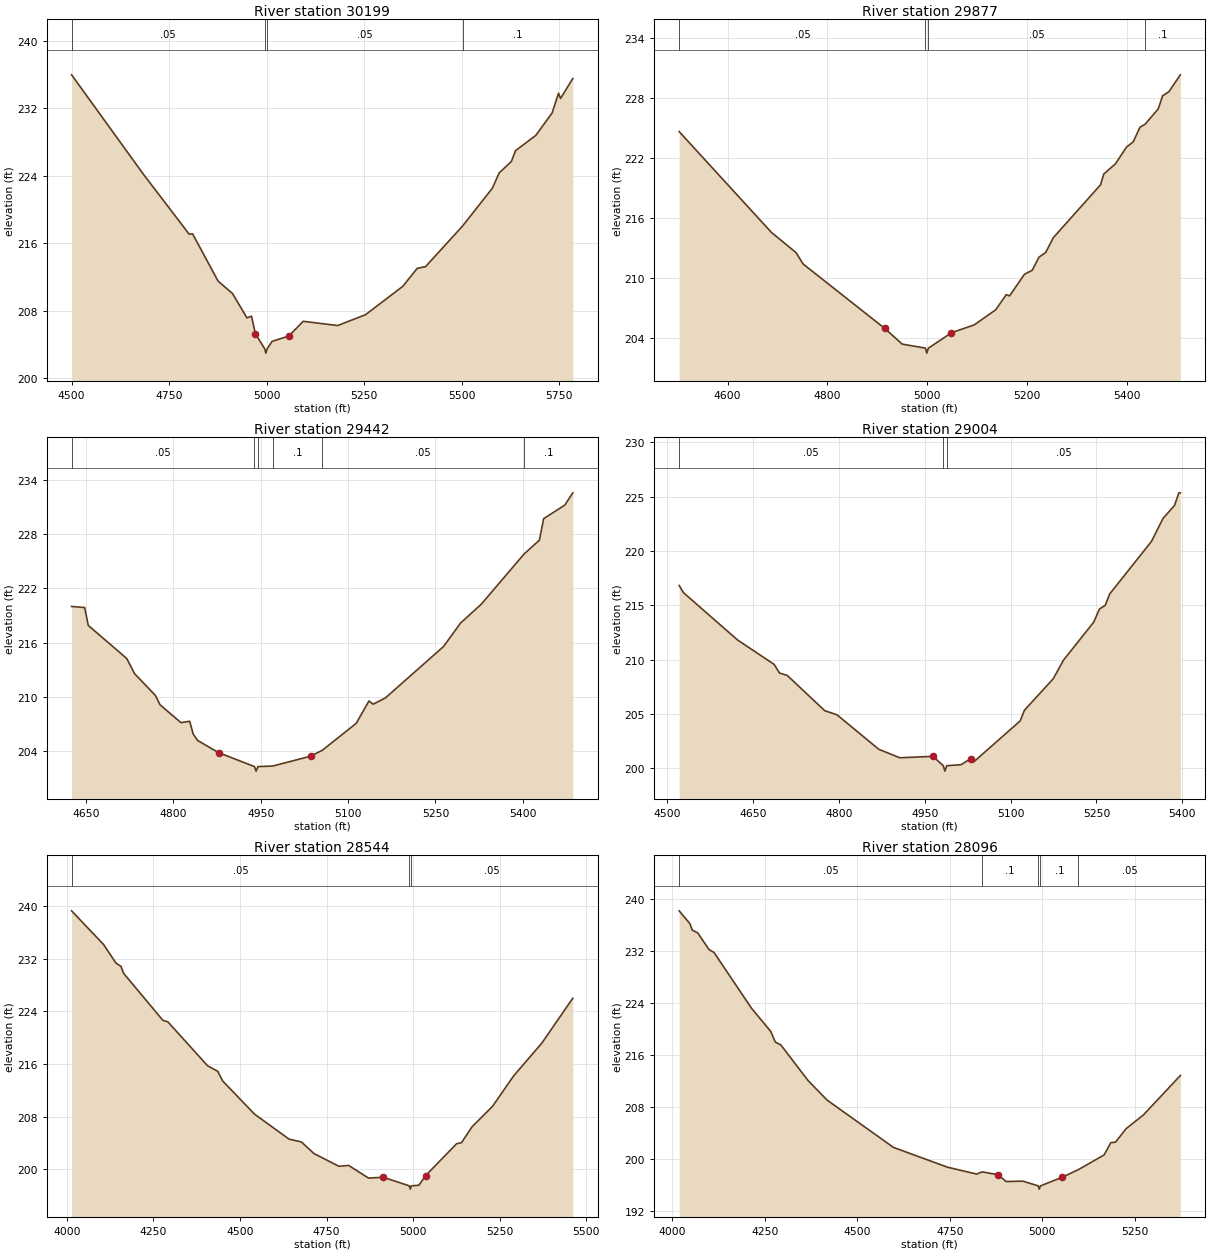
Type RM Length L Ch R = 1 ,30199   ,322,322,322
BEGIN DESCRIPTION:
GILDEN CREEK 54.0
END DESCRIPTION:
XS GIS Cut Line= 3
      2264111.02     13273014.22       2264930.5     13272528.09
      2265248.28     13272431.37
#Sta/Elev= 30
    4500  235.97  4684.5  224.17  4801.5  217.09  4810.1  217.14  4875.5  211.54
  4912.6  210.06  4949.6  207.18  4961.3  207.38  4971.1  205.32  4995.3   203.5
    4998     203  5001.3   203.5  5013.9  204.39  5056.8  205.02  5093.8  206.77
  5182.2  206.27  5253.6  207.55  5349.1  210.91  5386.1  213.04  5407.6  213.25
  5502.8  218.08  5578.9  222.54  5596.3  224.35  5627.6  225.71  5638.1  226.98
  5690.3   228.8  5732.1  231.46  5748.4  233.79  5753.6  233.17    5785  235.53
#Mann= 4 ,-1 , 0
    4500     .05       0  4995.3    .035       0  5001.3     .05       0
  5502.8      .1       0
Bank Sta=4971.1,5056.8
XS Rating Curve= 0 ,0
Exp/Cntr=0.3,0.1

Type RM Length L Ch R = 1 ,29877   ,435,435,435
BEGIN DESCRIPTION:
GILDEN CREEK 53.0
END DESCRIPTION:
XS GIS Cut Line= 3
      2264437.68     13273246.89      2264837.72     13272896.85
      2265237.76     13272646.83
#Sta/Elev= 30
  4503.1   224.6  4687.8  214.52  4737.1   212.5  4751.3  211.36  4914.6  204.92
  4949.7  203.35  4996.1  202.95  4998.8  202.45  5002.1  202.95  5048.2  204.49
  5093.6  205.27  5136.7  206.78  5157.9   208.3  5164.4  208.17  5194.4  210.34
  5209.8  210.73  5223.3  212.04  5236.9  212.52  5252.2     214  5346.6  219.28
  5353.1  220.36  5376.6  221.39  5398.5  223.05    5412  223.58  5425.6  225.04
  5435.8  225.34  5462.1  226.87    5471  228.19  5483.4  228.59  5506.4  230.28
#Mann= 4 ,-1 , 0
  4503.1     .05       0  4996.1     .03       0  5002.1     .05       0
  5435.8      .1       0
Bank Sta=4914.6,5048.2
XS Rating Curve= 0 ,0
Exp/Cntr=0.3,0.1

Type RM Length L Ch R = 1 ,29442   ,438,438,438
BEGIN DESCRIPTION:
GILDEN CREEK 52.0
END DESCRIPTION:
XS GIS Cut Line= 3
      2264937.71     13273496.87      2265137.72     13273196.85
      2265437.74     13272796.83
#Sta/Elev= 30
  4625.2  219.99  4647.7  219.87  4653.8   217.9  4719.9  214.25  4733.4  212.57
  4769.4  210.15  4776.9  209.15    4813  207.17    4828  207.32    4834  205.91
  4841.5  205.21  4877.6  203.86  4939.2  202.32    4942  201.82  4945.2  202.32
  4970.5  202.38  5035.8  203.47  5055.9  204.13  5113.9  207.09  5135.8  209.56
  5143.1  209.21  5163.9  209.89  5263.9  215.57  5293.1  218.16  5328.5  220.23
  5402.2  225.78  5428.5  227.31  5435.8  229.68  5472.2  231.18  5485.8  232.53
#Mann= 6 ,-1 , 0
  4625.2     .05       0  4939.2     .07       0  4945.2     .05       0
  4970.5      .1       0  5055.9     .05       0  5402.2      .1       0
Bank Sta=4877.6,5035.8
XS Rating Curve= 0 ,0
Exp/Cntr=0.3,0.1

Type RM Length L Ch R = 1 ,29004   ,460,460,460
BEGIN DESCRIPTION:
GILDEN CREEK 51.0
END DESCRIPTION:
XS GIS Cut Line= 3
       2265287.7     13273746.89      2265537.72     13273346.85
      2265587.73     13272946.81
#Sta/Elev= 30
  4521.5  216.83  4529.2  216.16  4623.5  211.81  4687.2  209.57  4696.7  208.77
  4710.2  208.55  4775.7   205.3  4796.9  204.93    4870  201.75  4906.6  200.97
  4964.4   201.1  4982.6  200.24  4985.3  199.74  4988.6  200.24  5013.4  200.33
    5031   200.9  5036.1  200.61  5116.7  204.36  5124.3  205.35  5174.6  208.25
  5192.3  209.95  5245.2  213.46  5255.3  214.67  5265.3     215  5272.9  216.04
    5346  220.89  5366.1     223  5386.3  224.21  5393.8  225.36  5396.4  225.36
#Mann= 3 ,-1 , 0
  4521.5     .05       0  4982.6     .03       0  4988.6     .05       0
Bank Sta=4964.4,5031
XS Rating Curve= 0 ,0
Exp/Cntr=0.3,0.1

Type RM Length L Ch R = 1 ,28544   ,448,448,448
BEGIN DESCRIPTION:
GILDEN CREEK 50.0
END DESCRIPTION:
XS GIS Cut Line= 3
      2265387.71     13274196.87      2265987.72     13273396.85
      2266187.71     13272996.88
#Sta/Elev= 30
  4013.8  239.25  4106.5  234.11  4141.9  231.31  4156.5  230.81  4163.8  229.77
  4277.4  222.61  4291.9  222.38  4406.5  215.71  4435.7  214.87  4450.3  213.39
  4541.9  208.37  4641.9  204.56  4677.4  204.14  4713.8  202.37  4785.7  200.44
  4813.8  200.57  4871.1  198.65  4913.8  198.77  4988.9  197.47  4991.7  196.97
  4994.9  197.47  5016.6  197.56  5036.2  199.03  5125.6  203.87  5139.6  204.02
  5170.3  206.45    5229  209.53  5290.5  214.19  5371.6  219.15    5461  225.97
#Mann= 3 ,-1 , 0
  4013.8     .05       0  4988.9     .03       0  4994.9     .05       0
Bank Sta=4913.8,5036.2
XS Rating Curve= 0 ,0
Exp/Cntr=0.3,0.1

Type RM Length L Ch R = 1 ,28096   ,482,482,482
BEGIN DESCRIPTION:
GILDEN CREEK 49.0
END DESCRIPTION:
XS GIS Cut Line= 3
      2265887.74     13274396.82      2266387.72     13273596.85
      2266287.71     13273196.83
#Sta/Elev= 30
  4018.1   238.2    4047  236.23  4053.4  235.23  4068.2  234.81  4098.8  232.23
  4112.4  231.78  4214.4  223.14  4265.7  219.63  4278.1  217.99  4293.4  217.52
  4366.5  212.07  4418.4  209.03  4597.7  201.75  4743.9   198.7  4822.9  197.64
  4837.7  197.98  4880.7  197.54  4902.5  196.49  4947.9  196.55  4989.4  195.82
  4992.1  195.32  4995.4  195.82  5054.2  197.15  5097.8  198.32  5167.6  200.59
  5185.7  202.48  5198.5  202.56  5226.9  204.63  5273.3  206.72  5373.8  212.83
#Mann= 5 ,-1 , 0
  4018.1     .05       0  4837.7      .1       0  4989.4     .07       0
  4995.4      .1       0  5097.8     .05       0
Bank Sta=4880.7,5054.2
XS Rating Curve= 0 ,0
Exp/Cntr=0.3,0.1

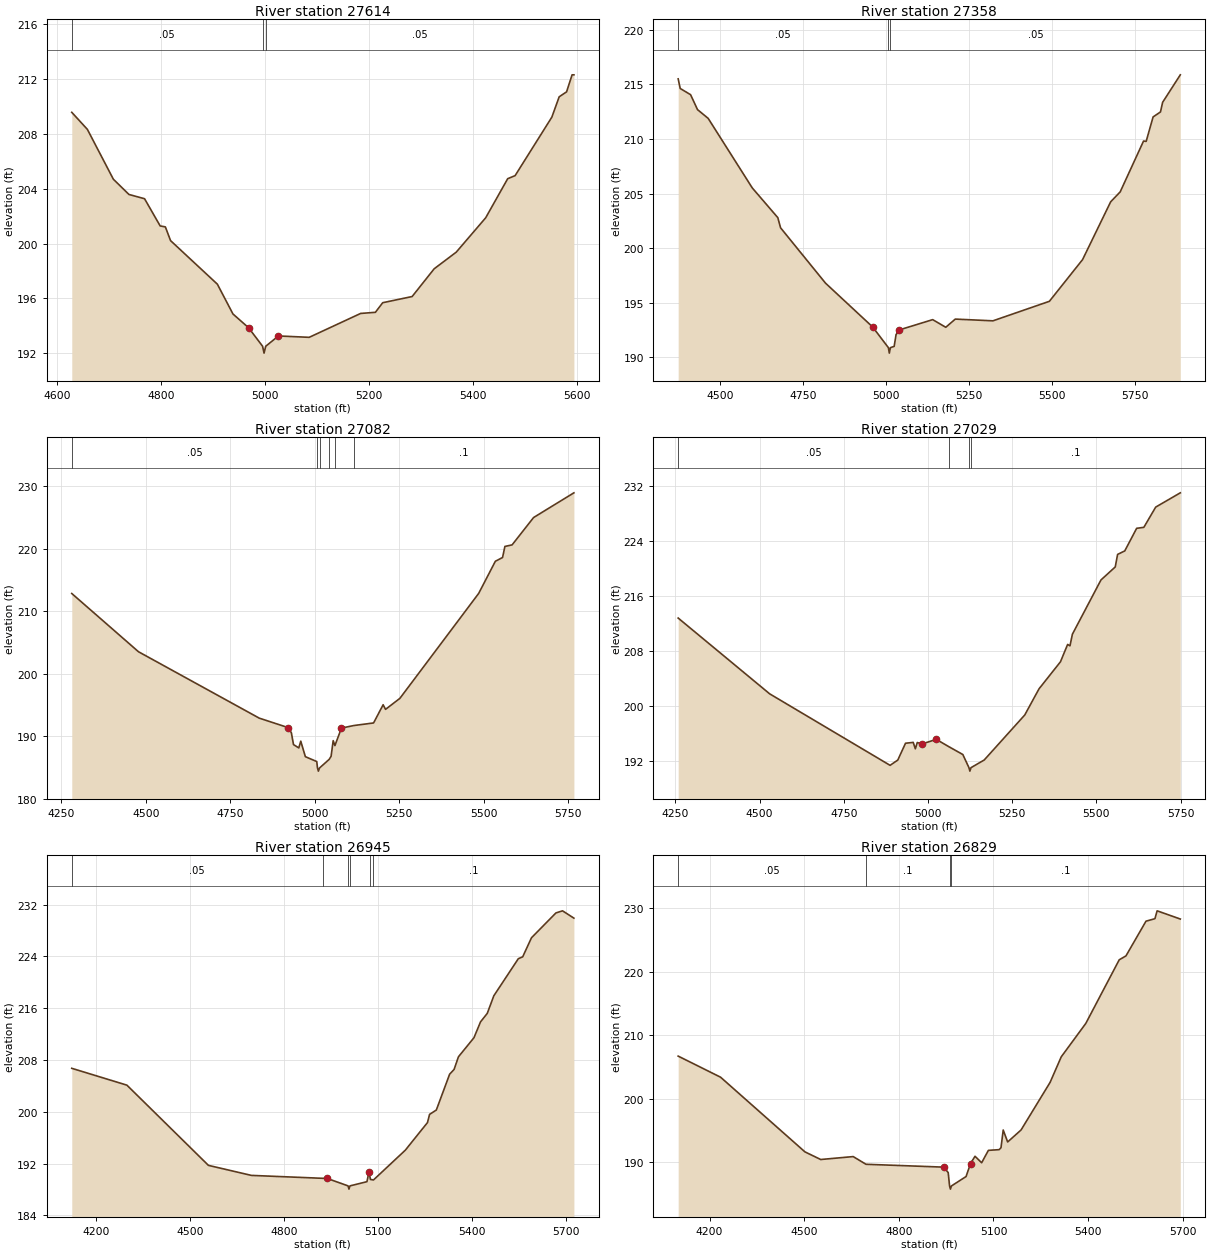
Type RM Length L Ch R = 1 ,27614   ,256,256,256
BEGIN DESCRIPTION:
GILDEN CREEK 48.0
END DESCRIPTION:
XS GIS Cut Line= 3
      2266837.72     13273946.89      2266837.72     13273546.85
      2266437.73     13273146.87
#Sta/Elev= 30
  4628.7  209.55  4658.7  208.31  4708.7  204.68  4738.7  203.57  4768.7  203.26
  4798.7  201.28  4808.7  201.21  4818.7  200.21  4908.7  197.04  4938.7  194.87
  4968.7  193.87  4995.7  192.52  4998.5  192.02  5001.7  192.52  5026.2  193.27
  5085.3  193.17  5184.3  194.91  5212.6  194.99  5226.7  195.69  5283.3  196.14
  5325.7  198.16  5368.1  199.37  5424.7  201.87  5467.1  204.72  5481.3  204.94
    5552   209.2  5566.1  210.68  5580.3  211.04  5590.9  212.28  5594.4  212.28
#Mann= 3 ,-1 , 0
  4628.7     .05       0  4995.7     .03       0  5001.7     .05       0
Bank Sta=4968.7,5026.2
XS Rating Curve= 0 ,0
Exp/Cntr=0.3,0.1

Type RM Length L Ch R = 1 ,27358   ,276,276,276
BEGIN DESCRIPTION:
GILDEN CREEK 74.0
END DESCRIPTION:
XS GIS Cut Line= 4
      2266958.28     13274122.72      2267097.17     13273653.96
      2267069.39     13273344.93      2266619.01     13272790.62
#Sta/Elev= 30
  4374.5  215.51  4380.6  214.63  4411.9  214.06  4432.8  212.69  4464.9  211.89
  4597.9  205.51  4674.8  202.79  4683.1  201.86  4818.7  196.78  4960.9  192.76
  5008.1  190.87  5010.9  190.37  5014.1  190.87  5025.5  190.99  5031.2  192.07
  5041.2   192.5  5141.6  193.44    5181  192.74  5209.7  193.49  5323.2  193.33
  5493.3  195.12  5593.3  198.94    5678  204.24  5706.7  205.15  5777.1  209.81
    5785  209.78  5805.9  212.02  5828.2  212.48  5834.6  213.36  5887.9  215.88
#Mann= 3 ,-1 , 0
  4374.5     .05       0  5008.1     .03       0  5014.1     .05       0
Bank Sta=4960.9,5041.2
XS Rating Curve= 0 ,0
Exp/Cntr=0.3,0.1

Type RM Length L Ch R = 1 ,27082   ,53,53,53
BEGIN DESCRIPTION:
GILDEN CREEK 47.0
END DESCRIPTION:
XS GIS Cut Line= 4
      2266999.94     13274077.59      2267350.64     13273480.35
      2267322.86     13273355.35       2267790.5     13272880.78
#Sta/Elev= 30
  4280.7  212.82  4478.3  203.51  4835.8   192.9  4921.7  191.38    4931  190.56
  4937.3  188.67    4953  188.14  4958.8  189.22  4972.4  186.74  5006.2  185.96
  5008.3  184.93    5011  184.43  5014.3  184.93  5042.8   186.3  5048.6   186.8
  5054.8   189.3  5059.9  188.51  5079.3  191.31  5116.3  191.72  5174.4  192.13
  5202.7  195.04  5209.8   194.3  5252.3  196.06  5485.6  212.83    5535  217.97
  5556.3  218.57  5563.3  220.34  5584.6  220.59  5648.2  224.96  5767.6  228.91
#Mann= 6 ,-1 , 0
  4280.7     .05       0  5008.3     .04       0  5014.3     .05       0
  5042.8      .1       0  5059.9     .05       0  5116.3      .1       0
Bank Sta=4921.7,5079.3
XS Rating Curve= 0 ,0
Exp/Cntr=0.3,0.1

Type RM Length L Ch R = 1 ,27029   ,84,84,84
BEGIN DESCRIPTION:
GILDEN CREEK 73.0
END DESCRIPTION:
XS GIS Cut Line= 5
      2267038.13     13274115.78      2267392.31     13273483.82
      2267402.73     13273445.62      2267357.59      13273386.6
      2267815.68     13272921.57
#Sta/Elev= 30
  4258.1  212.78  4529.8  201.78  4887.4   191.4  4910.3  192.17  4933.2  194.61
  4956.1  194.73  4962.4   193.8  4968.1  194.71  4982.5  194.51  5024.5  195.17
  5062.2   194.1  5103.4  192.97  5121.6  191.06  5124.3  190.56  5127.6  191.06
    5167  192.18  5287.3  198.71  5329.7  202.51  5393.3  206.43  5414.6  208.95
  5421.6  208.75  5428.7  210.43  5513.6  218.31    5556   220.2    5563  222.02
  5584.3  222.53  5619.6  225.81  5640.9  225.95  5676.2  228.89  5749.2  230.96
#Mann= 4 ,-1 , 0
  4258.1     .05       0  5062.2      .1       0  5121.6     .04       0
  5127.6      .1       0
Bank Sta=4982.5,5024.5
XS Rating Curve= 0 ,0
Exp/Cntr=0.3,0.1

Type RM Length L Ch R = 1 ,26945   ,116,116,116
BEGIN DESCRIPTION:
GILDEN CREEK 75.0
END DESCRIPTION:
XS GIS Cut Line= 4
      2267399.82      13274209.1      2267686.29     13273732.52
      2267425.87     13273425.22      2267897.21     13272985.14
#Sta/Elev= 30
  4121.8  206.72  4297.9  204.12  4558.2  191.74  4695.3  190.19  4922.8  189.74
  4935.9  189.75  5004.3  188.57  5007.1  188.07  5010.3  188.57  5064.5  189.22
    5071  190.71  5075.7  189.57  5085.3  189.48    5187  194.08  5257.8  198.34
  5264.6  199.61  5286.1  200.28  5328.6  205.81  5342.8  206.54  5356.8   208.5
  5406.3  211.44  5427.3  213.89  5448.8   215.2  5469.8  217.92    5548  223.64
    5562  223.93    5590  226.87  5668.2  230.71  5689.2  231.03  5725.5   229.9
#Mann= 6 ,-1 , 0
  4121.8     .05       0  4922.8      .1       0  5004.3     .07       0
  5010.3      .1       0  5075.7     .05       0  5085.3      .1       0
Bank Sta=4935.9,5071
XS Rating Curve= 0 ,0
Exp/Cntr=0.3,0.1

Type RM Length L Ch R = 1 ,26829   ,498,498,498
BEGIN DESCRIPTION:
GILDEN CREEK 46.0
END DESCRIPTION:
XS GIS Cut Line= 4
      2267459.72     13274224.71      2267790.46     13273711.68
      2267514.42     13273420.02      2267931.08     13273016.37
#Sta/Elev= 30
  4100.3   206.7  4234.8  203.38  4502.3  191.63  4552.3  190.43  4655.3  190.89
  4695.8  189.68  4942.3  189.23  4956.5  188.37  4960.8  186.27  4963.5  185.77
  4966.8  186.27  5013.1  187.75  5027.3   189.8  5041.5  190.94  5062.5  189.92
  5083.9  191.87  5118.1  191.98  5123.9  192.29  5130.9  195.07    5145  193.19
  5187.5  195.08  5279.6  202.57  5314.8  206.58  5392.7  211.84  5498.7  221.85
  5520.1  222.47  5583.6  227.93  5611.9  228.32  5618.9  229.56  5692.4  228.27
#Mann= 4 ,-1 , 0
  4100.3     .05       0  4695.8      .1       0  4960.8     .07       0
  4966.8      .1       0
Bank Sta=4942.3,5027.3
XS Rating Curve= 0 ,0
Exp/Cntr=0.3,0.1