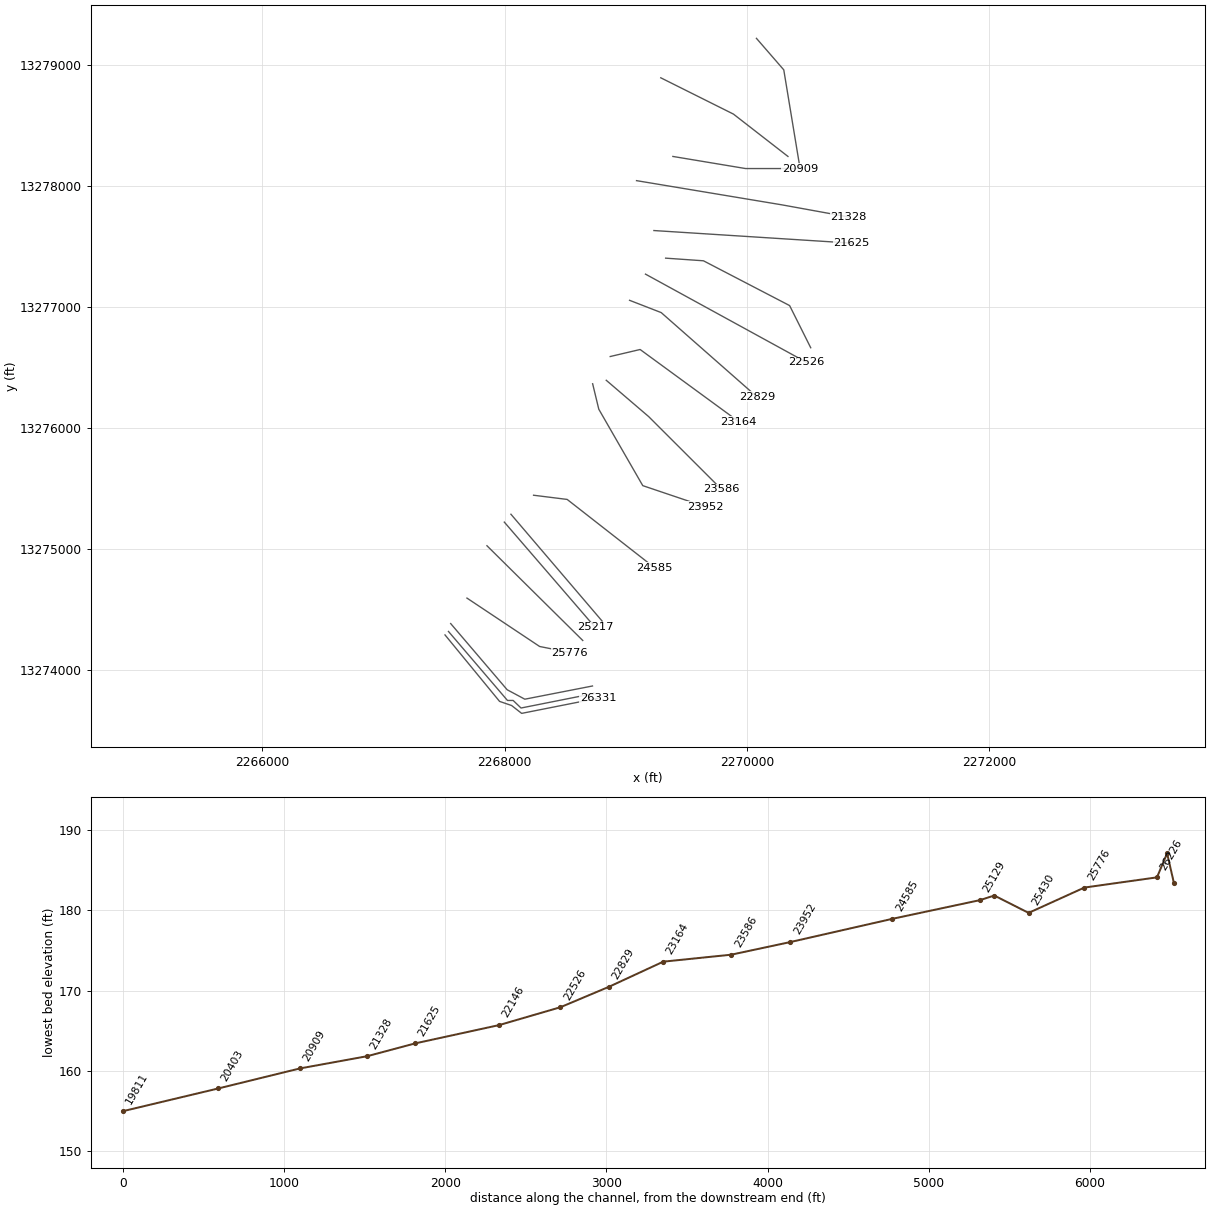
HEC-RAS study GILDEN CREEK.prj: GILDEN CREEK Base Level Engineering

--- GILDEN CREEK.g01 (geometry) --- (continued)

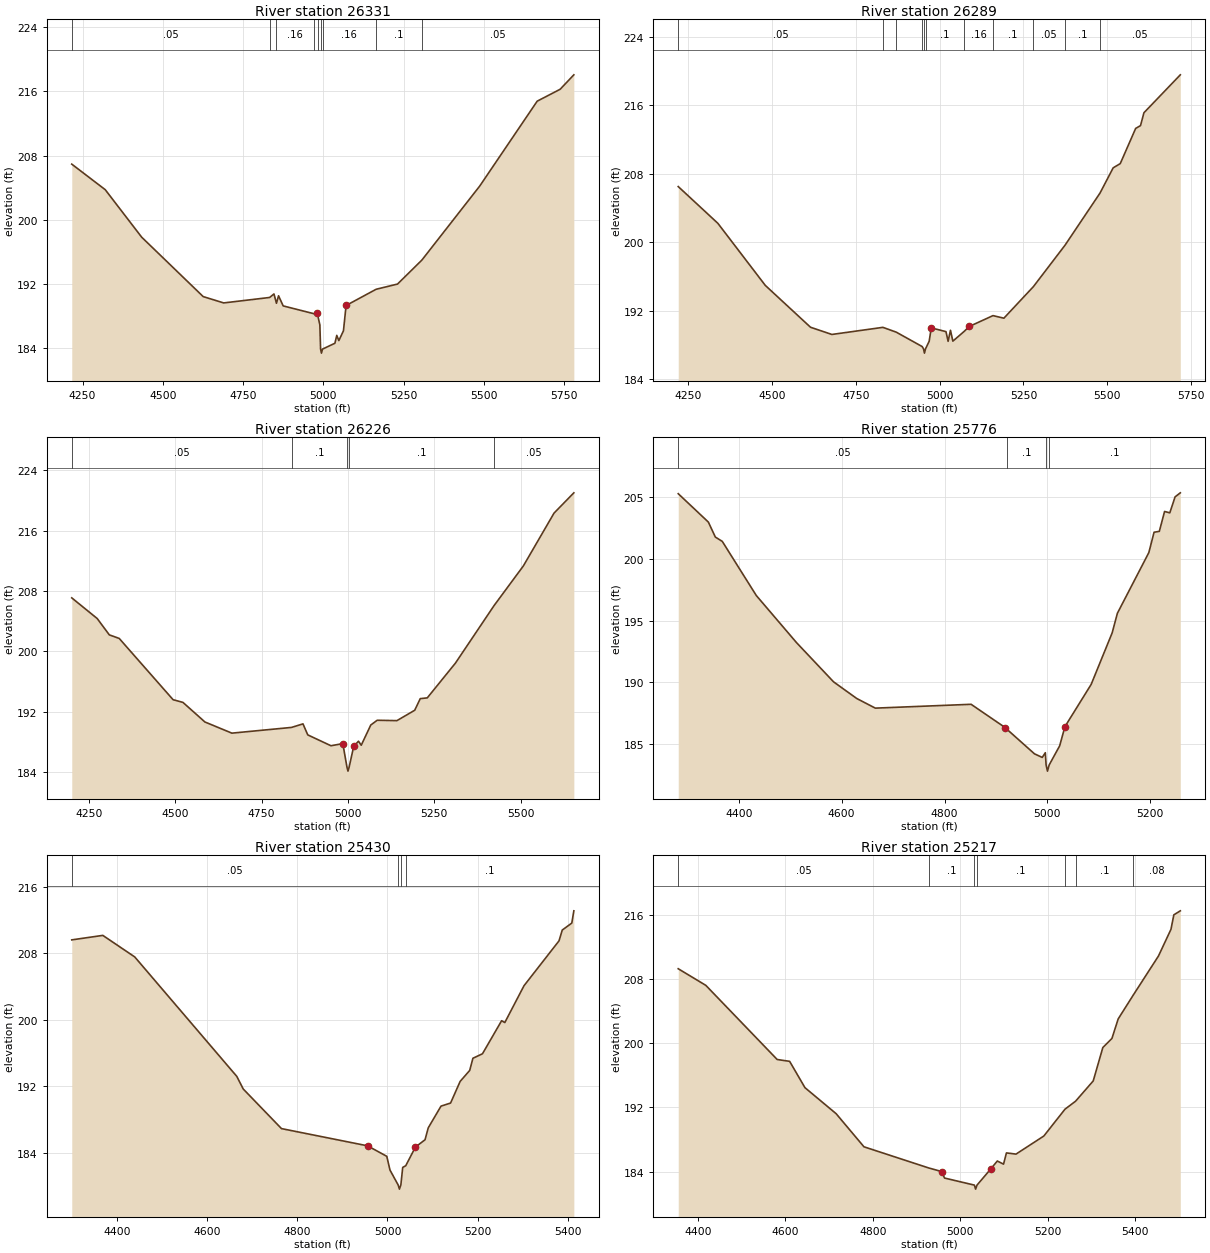
Type RM Length L Ch R = 1 ,26331   ,42,42,42
BEGIN DESCRIPTION:
GILDEN CREEK 76.0
END DESCRIPTION:
XS GIS Cut Line= 5
       2267506.6     13274292.41      2267957.12     13273742.93
      2268056.08     13273709.08      2268139.42     13273643.97
      2268769.64     13273768.98
#Sta/Elev= 30
  4216.5  206.94  4320.7  203.76  4434.1  197.85  4625.7  190.45  4689.6  189.66
  4832.7  190.34  4846.1  190.78    4851  190.05  4853.9  189.62  4860.4  190.55
  4874.8  189.29  4971.3  188.31  4980.5  188.43  4982.3  188.11    4989  186.94
  4991.3  183.91    4994  183.41  4997.3  183.91  5035.9  184.64  5041.7  185.62
  5048.1  184.97  5062.5  186.19  5070.7  189.34  5164.2  191.36  5230.9  192.01
  5306.6  194.99  5486.8  204.21  5665.8  214.78  5737.2  216.26  5779.9  218.06
#Mann= 9 ,-1 , 0
  4216.5     .05       0  4832.7      .1       0    4851     .16       0
  4971.3      .1       0  4982.3     .16       0  4991.3     .07       0
  4997.3     .16       0  5164.2      .1       0  5306.6     .05       0
Bank Sta=4980.5,5070.7
XS Rating Curve= 0 ,0
Exp/Cntr=0.3,0.1

Type RM Length L Ch R = 1 ,26289   ,63,63,63
BEGIN DESCRIPTION:
GILDEN CREEK 45.0
END DESCRIPTION:
XS GIS Cut Line= 5
      2267535.24     13274321.07      2268022.23     13273750.75
       2268069.1     13273750.75      2268134.21     13273688.25
      2268734.25     13273807.74
#Sta/Elev= 30
  4219.4  206.52  4337.7  202.23  4479.3  194.98  4614.4  190.09  4678.1  189.25
  4830.4  190.08  4870.2  189.52  4947.6  187.84  4951.7  187.57  4954.5  187.07
  4957.7  187.57  4968.6  188.46  4974.8  190.02  5018.7  189.58  5025.1  188.45
  5032.1  189.74  5039.3  188.47  5072.8   189.6  5088.7  190.19  5159.1  191.45
  5191.6  191.15  5279.6  194.83  5373.9  199.66  5478.7  205.77  5517.9  208.71
    5539   209.2    5585  213.31  5599.5  213.64  5609.7  215.14  5718.3  219.57
#Mann= 11 ,-1 , 0
  4219.4     .05       0  4830.4      .1       0  4870.2     .16       0
  4947.6      .1       0  4951.7     .07       0  4957.7      .1       0
  5072.8     .16       0  5159.1      .1       0  5279.6     .05       0
  5373.9      .1       0  5478.7     .05       0
Bank Sta=4974.8,5088.7
XS Rating Curve= 0 ,0
Exp/Cntr=0.3,0.1

Type RM Length L Ch R = 1 ,26226   ,450,450,450
BEGIN DESCRIPTION:
GILDEN CREEK 77.0
END DESCRIPTION:
XS GIS Cut Line= 4
       2267553.5     13274386.14      2268019.62     13273839.29
      2268165.46     13273761.16        2268724.     13273870.27
#Sta/Elev= 30
  4200.6  207.08  4274.2  204.34  4309.3  202.17  4337.9   201.7  4493.8  193.57
  4522.4  193.21    4586  190.61    4664  189.13  4836.7  189.89  4869.8  190.36
  4883.6   188.9  4950.7  187.46  4985.1  187.74  4997.2  184.59    5000  184.09
  5003.2  184.59  5016.5  187.36  5030.4  188.06  5038.4  187.53    5066  190.21
  5084.6  190.84  5141.7  190.79  5193.2  192.17  5209.2  193.71  5229.5  193.81
  5311.1  198.43  5422.7  206.05  5507.6  211.32  5596.4  218.33  5653.7  221.02
#Mann= 5 ,-1 , 0
  4200.6     .05       0  4836.7      .1       0  4997.2     .07       0
  5003.2      .1       0  5422.7     .05       0
Bank Sta=4985.1,5016.5
XS Rating Curve= 0 ,0
Exp/Cntr=0.3,0.1

Type RM Length L Ch R = 1 ,25776   ,346,346,346
BEGIN DESCRIPTION:
GILDEN CREEK 44.0
END DESCRIPTION:
XS GIS Cut Line= 3
      2267687.75     13274596.84      2268287.72     13274196.85
      2268537.69     13274146.86
#Sta/Elev= 30
  4282.4  205.28    4341  202.98  4354.5  201.77    4368  201.42  4434.1  197.04
  4512.2  193.23  4584.3  190.05  4629.4   188.7  4665.5  187.92  4851.7  188.23
  4917.8  186.35  4922.4  186.17  4974.9  184.22    4990  183.93    4996  184.31
  4997.5  183.32  5000.2  182.82  5003.5  183.32  5023.9  184.87  5034.1  186.42
  5085.1  189.84  5125.9  194.01  5136.1   195.6  5197.2  200.51  5207.4  202.16
  5217.6  202.23  5227.8  203.84    5238  203.73  5248.2  205.02  5258.4  205.35
#Mann= 4 ,-1 , 0
  4282.4     .05       0  4922.4      .1       0  4997.5     .07       0
  5003.5      .1       0
Bank Sta=4917.8,5034.1
XS Rating Curve= 0 ,0
Exp/Cntr=0.3,0.1

Type RM Length L Ch R = 1 ,25430   ,213,213,213
BEGIN DESCRIPTION:
GILDEN CREEK 78.0
END DESCRIPTION:
XS GIS Cut Line= 2
      2267852.92     13275029.42      2268643.68     13274246.47
#Sta/Elev= 30
  4300.3  209.61  4369.1  210.15  4439.9  207.56  4666.1  193.21  4680.3   191.7
  4765.1  186.94    4956  184.87  4998.5  183.61  5005.6  181.96  5023.7  180.17
  5026.5  179.67  5029.7  180.17  5033.8  182.28  5040.5  182.48  5062.1  184.73
  5083.3   185.6  5090.4  187.03  5118.7  189.64  5139.9  190.01  5161.1  192.61
  5182.3  193.93  5189.4  195.39  5210.6  195.93    5253   199.9  5260.1  199.68
  5302.6   204.1  5380.3   209.5  5387.4  210.79  5408.6  211.63  5413.1   213.1
#Mann= 4 ,-1 , 0
  4300.3     .05       0  5023.7     .04       0  5029.7     .05       0
  5040.5      .1       0
Bank Sta=4956,5062.1
XS Rating Curve= 0 ,0
Exp/Cntr=0.3,0.1

Type RM Length L Ch R = 1 ,25217   ,88,88,88
BEGIN DESCRIPTION:
GILDEN CREEK 43.0
END DESCRIPTION:
XS GIS Cut Line= 2
      2267996.22     13275224.67      2268746.16     13274354.95
#Sta/Elev= 30
    4355  209.27  4418.1   207.2  4581.3  197.97  4609.8  197.74  4644.9  194.46
  4716.2  191.22  4779.8   187.1  4928.2  184.46  4957.5  184.02  4964.1  183.21
  5032.4  182.33  5035.2  181.83  5038.4  182.33  5070.6  184.39  5084.8  185.33
  5099.1  184.94  5105.7  186.34  5127.6  186.19  5191.2  188.44  5239.6  191.78
  5263.9  192.78  5304.2   195.3  5326.2  199.46    5347  200.59  5361.3  203.02
  5395.3  205.95  5453.4  210.85    5482  214.17  5488.6  215.98  5503.4  216.48
#Mann= 7 ,-1 , 0
    4355     .05       0  4928.2      .1       0  5032.4     .07       0
  5038.4      .1       0  5239.6     .05       0  5263.9      .1       0
  5395.3     .08       0
Bank Sta=4957.5,5070.6
XS Rating Curve= 0 ,0
Exp/Cntr=0.3,0.1

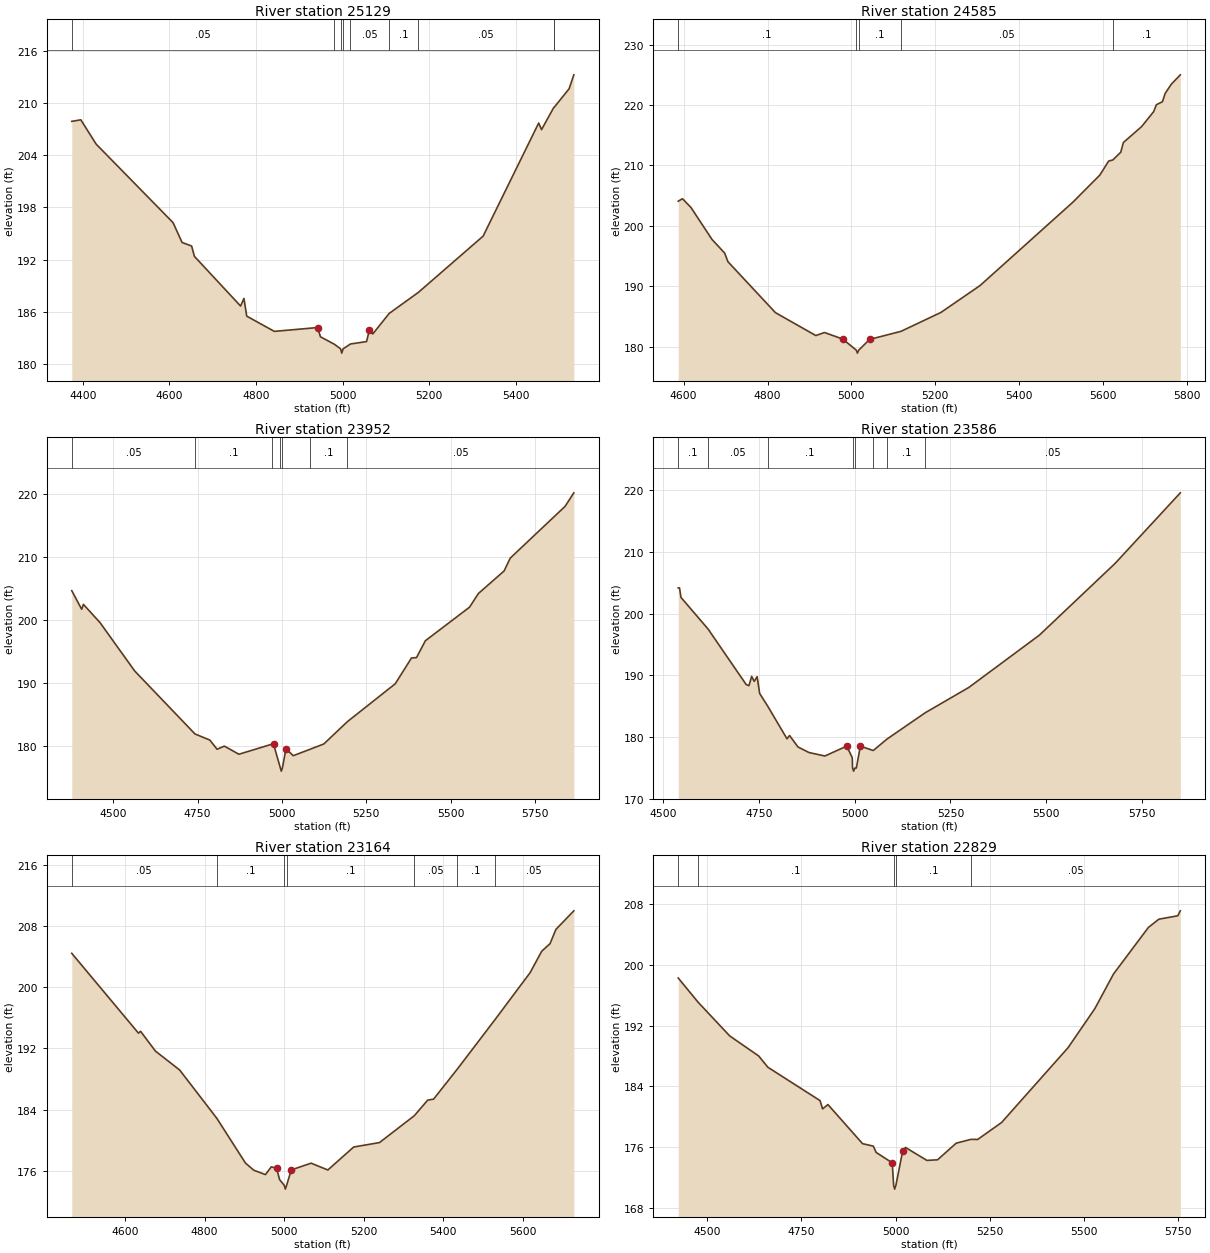
Type RM Length L Ch R = 1 ,25129   ,544,544,544
BEGIN DESCRIPTION:
GILDEN CREEK 42.0
END DESCRIPTION:
XS GIS Cut Line= 2
      2268050.88      13275289.8      2268803.11     13274407.42
#Sta/Elev= 30
  4374.5   207.9  4395.4  208.08  4430.9  205.28  4608.4  196.26  4629.3  193.98
  4651.3  193.57  4657.8  192.38  4764.4  186.67  4772.1  187.55  4778.6  185.51
  4842.3  183.76  4942.3   184.2  4948.8  183.14  4980.9  182.28  4995.2  181.76
    4998  181.26  5001.2  181.76  5018.2  182.31  5055.3  182.59  5061.9  183.93
  5069.6  183.46  5107.5  185.82  5174.9  188.24  5324.5  194.71  5452.8  207.71
  5459.4  206.95  5487.2  209.46  5488.5  209.51  5523.1  211.65    5534  213.25
#Mann= 9 ,-1 , 0
  4374.5     .05       0  4980.9      .1       0  4995.2     .07       0
  5001.2      .1       0  5018.2     .05       0  5107.5      .1       0
  5174.9     .05       0  5487.2     .08       0  5488.5      .1       0
Bank Sta=4942.3,5061.9
XS Rating Curve= 0 ,0
Exp/Cntr=0.3,0.1

Type RM Length L Ch R = 1 ,24585   ,633,633,633
BEGIN DESCRIPTION:
GILDEN CREEK 41.0
END DESCRIPTION:
XS GIS Cut Line= 3
      2268237.76     13275446.85      2268514.96     13275412.22
      2269237.74     13274846.84
#Sta/Elev= 30
  4587.1  204.07  4597.1  204.49  4617.3  203.05  4667.7  197.74  4697.9  195.48
  4705.5  194.07  4818.8  185.63  4915.1  181.84  4935.9  182.34  4979.3  181.26
  5011.5  179.43  5014.3  178.93  5017.5  179.43  5043.5   181.2  5118.3  182.54
  5213.5  185.67  5306.6  190.11  5528.1  203.92  5592.4  208.41  5613.2  210.71
  5623.2   210.9  5642.1  212.18  5648.4  213.79  5691.8  216.42  5720.6   218.9
  5727.1  220.04  5741.6  220.54  5747.9   221.9  5762.4  223.42  5784.1  224.99
#Mann= 5 ,-1 , 0
  4587.1      .1       0  5011.5     .07       0  5017.5      .1       0
  5118.3     .05       0  5623.2      .1       0
Bank Sta=4979.3,5043.5
XS Rating Curve= 0 ,0
Exp/Cntr=0.3,0.1

Type RM Length L Ch R = 1 ,23952   ,366,366,366
BEGIN DESCRIPTION:
GILDEN CREEK 40.0
END DESCRIPTION:
XS GIS Cut Line= 4
      2268725.32     13276368.27      2268776.14     13276157.71
       2269139.1     13275526.16      2269653.58     13275352.26
#Sta/Elev= 30
  4377.2  204.68  4406.6  201.73  4411.7  202.51    4461  199.61  4563.8  191.93
  4742.4  181.94  4786.4  180.97  4807.9  179.51  4829.5  180.01  4872.6  178.72
  4970.1  180.31  4975.4  180.29  4995.5  176.54  4998.2  176.04  5001.5  176.54
  5012.1  179.58  5033.7  178.49  5082.1  179.48  5124.2  180.35  5194.1  183.89
  5336.1  189.91  5384.1     194    5399  194.06  5425.2  196.73  5556.3  202.07
  5582.4  204.23  5658.6  207.81  5676.8  209.85  5839.3  218.06  5865.3  220.21
#Mann= 7 ,-1 , 0
  4377.2     .05       0  4742.4      .1       0  4970.1     .05       0
  4995.5     .04       0  5001.5     .05       0  5082.1      .1       0
  5194.1     .05       0
Bank Sta=4975.4,5012.1
XS Rating Curve= 0 ,0
Exp/Cntr=0.3,0.1

Type RM Length L Ch R = 1 ,23586   ,422,422,422
BEGIN DESCRIPTION:
GILDEN CREEK 39.0
END DESCRIPTION:
XS GIS Cut Line= 3
      2268837.71     13276396.87      2269187.72     13276096.85
       2269787.7     13275496.87
#Sta/Elev= 30
    4540  204.18  4543.3  204.18  4547.2  202.63  4617.8  197.51  4717.3   188.5
  4724.4  188.33  4731.5  189.83  4738.1  189.03  4745.8  189.78  4752.4  187.06
    4773  185.04  4823.7  179.71  4830.3  180.25  4852.3  178.39  4880.8  177.49
  4922.5  176.92  4979.6  178.53  4993.9  176.64  4994.7  174.97  4997.5  174.47
  5000.7  174.97  5004.5  174.97  5015.1  178.52  5048.6  177.81    5085  179.69
  5184.6  183.95    5298  188.04  5481.8  196.51  5679.8  208.17  5849.5  219.59
#Mann= 8 ,-1 , 0
    4540      .1       0  4617.8     .05       0    4773      .1       0
  4994.7     .07       0  5000.7      .1       0  5048.6     .05       0
    5085      .1       0  5184.6     .05       0
Bank Sta=4979.6,5015.1
XS Rating Curve= 0 ,0
Exp/Cntr=0.3,0.1

Type RM Length L Ch R = 1 ,23164   ,335,335,335
BEGIN DESCRIPTION:
GILDEN CREEK 38.0
END DESCRIPTION:
XS GIS Cut Line= 3
      2268870.47     13276593.25      2269117.32     13276651.33
      2269930.32      13276056.1
#Sta/Elev= 30
  4466.4   204.4    4634  193.97  4639.2  194.22  4676.4  191.64  4737.6  189.15
  4830.8  182.85  4902.8     177  4923.6  176.07  4952.9   175.5  4967.6  176.51
  4980.8  176.33  4988.5  174.84  5000.1   174.1  5002.9   173.6  5006.1   174.1
  5017.8  176.11  5067.5  176.99  5109.7   176.1  5174.5   179.1  5239.4  179.68
  5326.9  183.19  5360.6  185.23  5375.2  185.35  5435.2   189.3  5528.7  195.68
  5617.7  201.87    5647  204.68  5667.8  205.66  5682.5  207.52  5727.6  209.95
#Mann= 7 ,-1 , 0
  4466.4     .05       0  4830.8      .1       0  5000.1     .07       0
  5006.1      .1       0  5326.9     .05       0  5435.2      .1       0
  5528.7     .05       0
Bank Sta=4980.8,5017.8
XS Rating Curve= 0 ,0
Exp/Cntr=0.3,0.1

Type RM Length L Ch R = 1 ,22829   ,303,303,303
BEGIN DESCRIPTION:
GILDEN CREEK 37.0
END DESCRIPTION:
XS GIS Cut Line= 3
      2269030.23     13277057.84      2269291.54     13276956.22
      2270081.32     13276260.63
#Sta/Elev= 30
  4422.8  198.28    4475  195.12  4559.6  190.65  4636.3  188.02  4660.8  186.53
  4799.3  182.14    4806  181.05  4820.2  181.62  4912.2  176.47  4940.7  176.15
  4948.2  175.32  4990.9  173.95  4994.6  170.99  4997.3  170.49  5000.6  170.99
  5018.5  175.49    5026  175.98  5082.9  174.27  5111.2  174.35  5160.7  176.54
  5199.9  177.04  5217.7  177.03  5281.2  179.26  5457.7  189.11  5528.9  194.26
  5578.2   198.8  5670.8  204.93  5698.7  206.02  5748.9  206.47  5755.6  207.12
#Mann= 5 ,-1 , 0
  4422.8     .05       0    4475      .1       0  4994.6     .07       0
  5000.6      .1       0  5199.9     .05       0
Bank Sta=4990.9,5018.5
XS Rating Curve= 0 ,0
Exp/Cntr=0.3,0.1

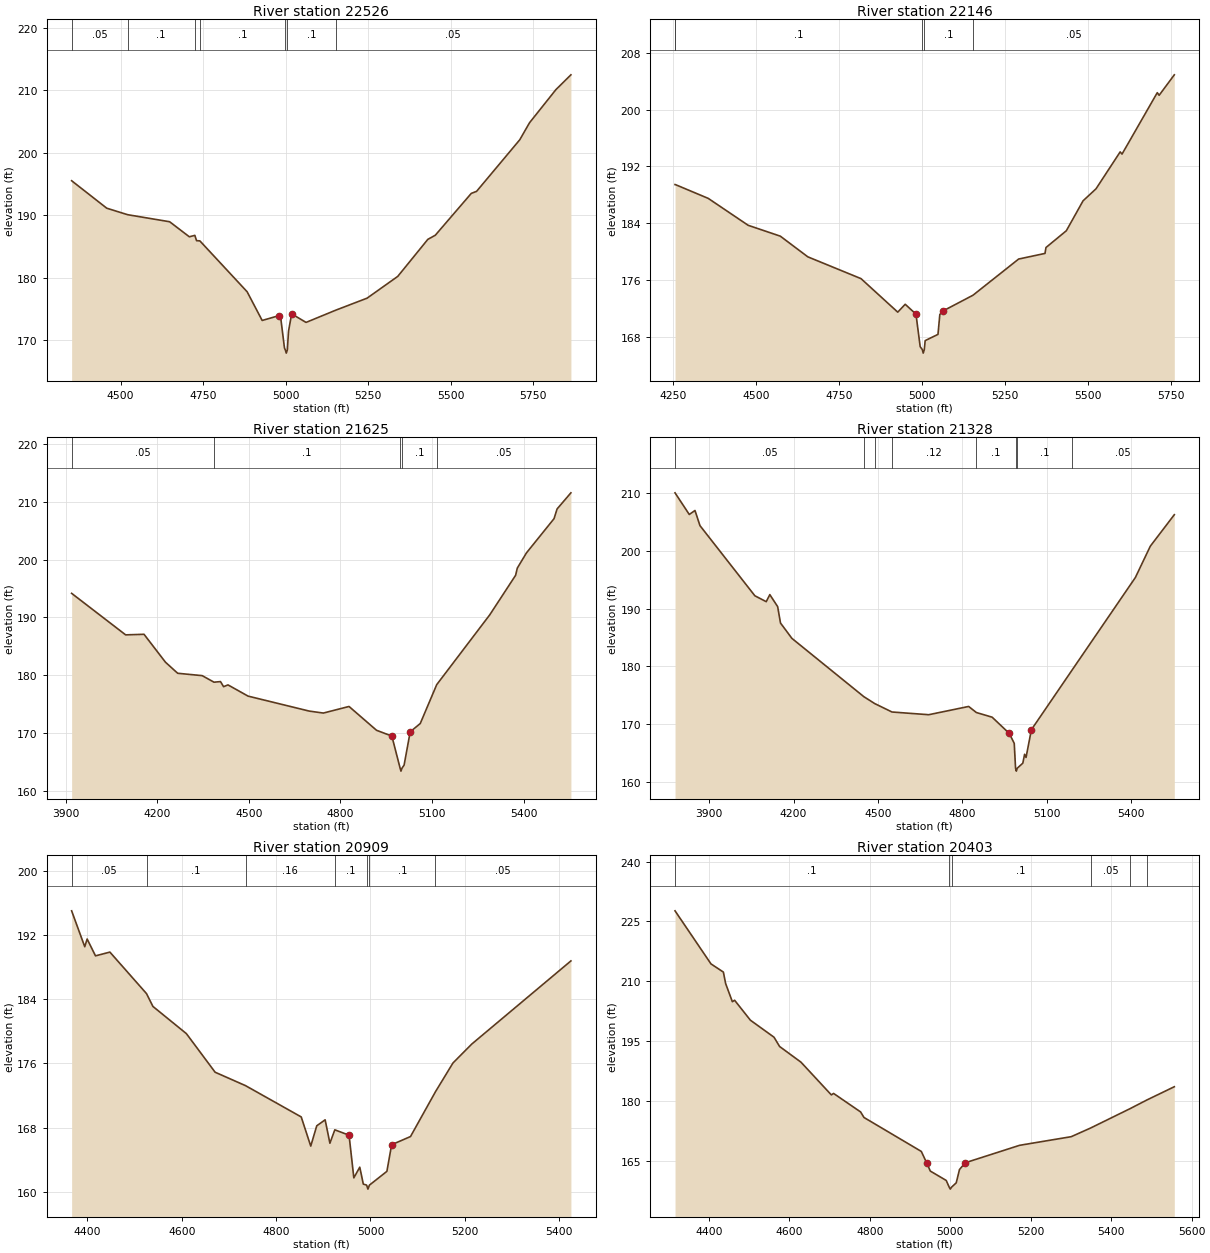
Type RM Length L Ch R = 1 ,22526   ,380,380,380
BEGIN DESCRIPTION:
GILDEN CREEK 36.0
END DESCRIPTION:
XS GIS Cut Line= 2
      2269161.65      13277274.2      2270487.68     13276546.88
#Sta/Elev= 30
  4351.5  195.54  4457.9  191.14  4521.2   190.1  4648.4  188.97  4708.1  186.56
  4724.7  186.79  4729.9  185.94  4739.9  185.91  4883.1  177.76  4928.7  173.16
    4980  173.94  4985.8   173.2  4996.2  168.76  4998.9  168.43  5001.7  167.93
  5004.9  168.43  5008.5  171.44    5018  174.22  5061.6  172.85  5151.2   174.8
  5246.4  176.73  5339.4  180.22  5430.5  186.15  5453.1  186.81  5562.1  193.51
  5578.2  193.84    5709   202.1  5738.5  204.82  5818.3  210.12  5863.9   212.5
#Mann= 7 ,-1 , 0
  4351.5     .05       0  4521.2      .1       0  4724.7     .05       0
  4739.9      .1       0  4998.9     .07       0  5004.9      .1       0
  5151.2     .05       0
Bank Sta=4980,5018
XS Rating Curve= 0 ,0
Exp/Cntr=0.3,0.1

Type RM Length L Ch R = 1 ,22146   ,521,521,521
BEGIN DESCRIPTION:
GILDEN CREEK 86.0
END DESCRIPTION:
XS GIS Cut Line= 4
      2269327.88     13277406.28      2269639.98     13277384.51
      2270351.38     13277014.29       2270525.6     13276665.85
#Sta/Elev= 30
  4255.5  189.45  4256.2  189.45  4355.6   187.5  4475.9  183.71  4572.8  182.18
  4655.6  179.27  4815.9   176.2  4926.6  171.48  4949.1  172.59  4981.5   171.2
  4994.2  166.62  5000.6  166.21  5003.3  165.71  5006.6  166.21  5009.2  167.47
  5047.8  168.35  5053.4  171.15  5061.8  171.62  5153.2  173.86  5290.9  178.96
  5370.3  179.75  5373.2  180.58  5434.5  182.94    5485  187.16    5524  188.85
  5596.8  194.05  5602.4  193.74  5708.6  202.39  5714.2  202.02  5759.9   204.9
#Mann= 5 ,-1 , 0
  4255.5     .05       0  4256.2      .1       0  5000.6     .07       0
  5006.6      .1       0  5153.2     .05       0
Bank Sta=4981.5,5061.8
XS Rating Curve= 0 ,0
Exp/Cntr=0.3,0.1

Type RM Length L Ch R = 1 ,21625   ,297,297,297
BEGIN DESCRIPTION:
GILDEN CREEK 35.0
END DESCRIPTION:
XS GIS Cut Line= 2
      2269231.14     13277634.44      2270862.91     13277530.28
#Sta/Elev= 30
  3919.8  194.17  4096.7  186.99  4156.9  187.09    4227  182.27  4267.1  180.35
  4347.3  179.94  4386.1  178.81  4407.4  178.91  4417.4  178.03  4431.9  178.34
  4497.6   176.4    4698  173.81  4744.2  173.47  4828.2  174.61  4918.4  170.49
  4968.5  169.49  4995.6  163.93  4998.3  163.43  5001.6  163.93  5008.6  164.47
  5028.6  170.23  5061.5  171.66  5115.4  178.38  5289.2  190.46  5373.8  197.29
  5379.3  198.53  5409.4  201.17  5499.6  207.08  5509.6  208.76  5554.9  211.55
#Mann= 5 ,-1 , 0
  3919.8     .05       0  4386.1      .1       0  4995.6     .07       0
  5001.6      .1       0  5115.4     .05       0
Bank Sta=4968.5,5028.6
XS Rating Curve= 0 ,0
Exp/Cntr=0.3,0.1

Type RM Length L Ch R = 1 ,21328   ,419,419,419
BEGIN DESCRIPTION:
GILDEN CREEK 34.0
END DESCRIPTION:
XS GIS Cut Line= 3
      2269087.72     13278046.85      2270287.72     13277846.85
      2270837.75     13277746.85
#Sta/Elev= 30
  3778.6  210.04  3829.3  206.29  3849.6  206.98  3867.3  204.36  4062.5  192.21
    4103  191.19  4115.7  192.41  4143.6  190.33  4153.7  187.49  4194.3  184.83
  4450.2  174.73  4489.1  173.53  4550.2  172.08  4680.9  171.61  4822.8  173.04
  4850.3  171.99  4906.4  171.18  4967.3  168.37    4985  166.64  4989.6  162.34
  4992.4  161.84  4995.6  162.34  5015.5  163.22  5021.8  164.76  5026.9  164.21
    5046  169.02  5190.6  179.34  5415.7  195.37    5469  200.81  5554.2  206.25
#Mann= 8 ,-1 , 0
  3778.6     .05       0  4450.2      .1       0  4489.1     .05       0
  4550.2     .12       0  4850.3      .1       0  4989.6     .07       0
  4995.6      .1       0  5190.6     .05       0
Bank Sta=4967.3,5046
XS Rating Curve= 0 ,0
Exp/Cntr=0.3,0.1

Type RM Length L Ch R = 1 ,20909   ,506,506,506
BEGIN DESCRIPTION:
GILDEN CREEK 33.0
END DESCRIPTION:
XS GIS Cut Line= 3
      2269387.77     13278246.85      2269987.72     13278146.85
      2270437.69     13278146.85
#Sta/Elev= 30
  4366.6  195.04  4394.4  190.56  4399.5  191.52  4417.2  189.42  4447.7  189.89
  4525.3  184.71  4538.9  183.11  4609.9  179.71  4670.7   174.9  4735.3  173.22
  4853.2  169.32  4873.4  165.68  4886.1  168.21  4903.9  168.96    4914  166.04
  4924.4  167.71  4954.6  167.04  4964.7  161.72  4977.3  163.05  4984.8  160.94
  4991.8  160.81  4994.6  160.31  4997.8  160.81  5034.8  162.53  5044.8  165.85
  5084.8  166.87  5137.7  172.46  5174.8  176.05  5214.8  178.42  5424.8  188.79
#Mann= 7 ,-1 , 0
  4366.6     .05       0  4525.3      .1       0  4735.3     .16       0
  4924.4      .1       0  4991.8     .07       0  4997.8      .1       0
  5137.7     .05       0
Bank Sta=4954.6,5044.8
XS Rating Curve= 0 ,0
Exp/Cntr=0.3,0.1

Type RM Length L Ch R = 1 ,20403   ,592,592,592
BEGIN DESCRIPTION:
GILDEN CREEK 32.0
END DESCRIPTION:
XS GIS Cut Line= 3
      2269287.73     13278896.85      2269887.72     13278596.85
      2270337.72     13278246.85
#Sta/Elev= 30
    4316  227.65  4405.4  214.33  4436.2  212.28  4441.8  209.39  4458.5  204.85
  4464.1  205.21  4503.3  200.21    4562  195.94  4575.9  193.61    4629  189.68
  4704.5  181.46  4710.1  181.83  4777.2  177.19  4785.6   175.8  4928.1  167.28
  4942.1  164.27  4950.5  162.35    4990     160  4997.4  158.32  5000.1  157.82
  5003.4  158.32  5014.9   159.4    5023  162.74  5037.5  164.44  5172.3  168.81
  5300.8  170.98  5348.8  173.15  5446.9  178.01    5490  180.25  5556.9  183.51
#Mann= 6 ,-1 , 0
    4316      .1       0  4997.4     .07       0  5003.4      .1       0
  5348.8     .05       0  5446.9      .1       0    5490     .05       0
Bank Sta=4942.1,5037.5
XS Rating Curve= 0 ,0
Exp/Cntr=0.3,0.1

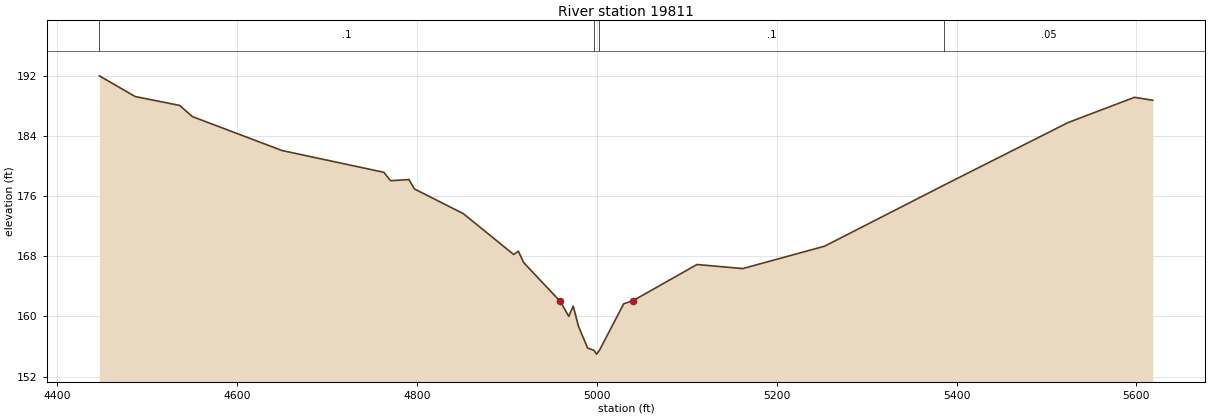
Type RM Length L Ch R = 1 ,19811   ,331,331,331
BEGIN DESCRIPTION:
GILDEN CREEK 31.0
END DESCRIPTION:
XS GIS Cut Line= 3
      2270077.45       13279223.      2270303.15     13278962.56
      2270437.73     13278146.82
#Sta/Elev= 30
  4446.8  192.04  4486.7  189.28  4536.1   188.1  4550.3  186.61  4650.1  182.09
  4763.1   179.2  4770.7  178.08  4791.1  178.23  4797.2  176.98  4851.6  173.69
  4907.6  168.25  4912.7   168.7  4918.8  167.16  4959.4     162  4968.8  160.02
  4973.8  161.38  4979.6   158.7  4989.8   155.8  4996.9  155.49  4999.7  154.99
  5002.9  155.49  5029.9  161.69  5040.5  162.12  5111.4  166.92  5162.3  166.38
  5253.3  169.36  5386.6  177.52  5523.9  185.81  5597.9  189.18  5618.2  188.79
#Mann= 4 ,-1 , 0
  4446.8      .1       0  4996.9     .07       0  5002.9      .1       0
  5386.6     .05       0
Bank Sta=4959.4,5040.5
XS Rating Curve= 0 ,0
Exp/Cntr=0.3,0.1