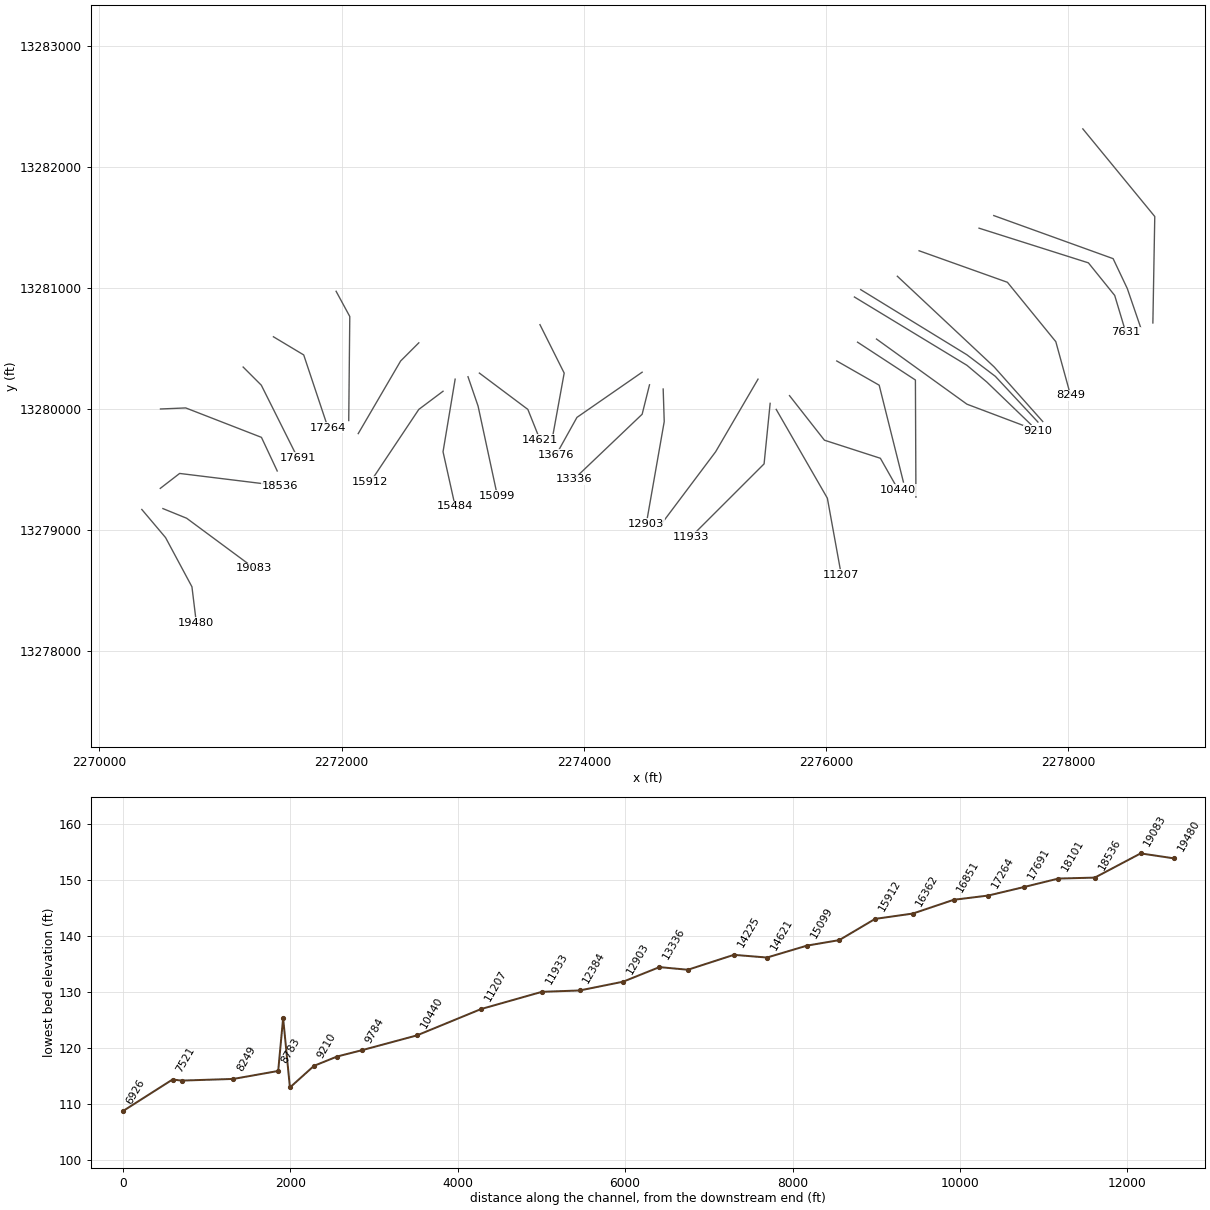
HEC-RAS study GILDEN CREEK.prj: GILDEN CREEK Base Level Engineering

--- GILDEN CREEK.g01 (geometry) --- (continued)

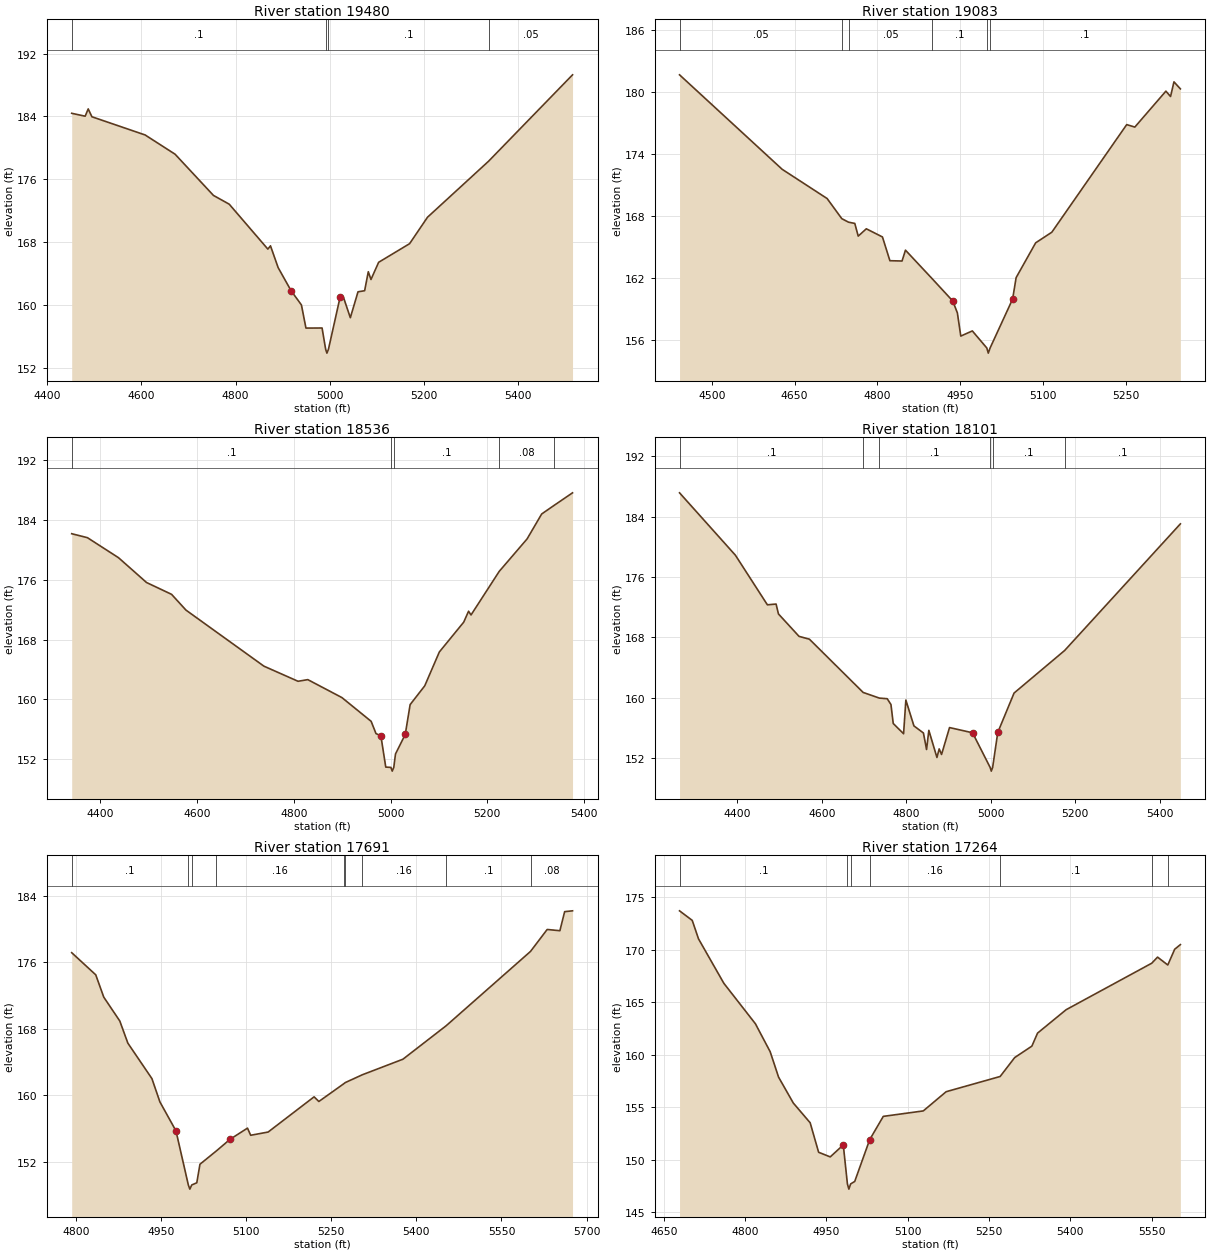
Type RM Length L Ch R = 1 ,19480   ,397,397,397
BEGIN DESCRIPTION:
GILDEN CREEK 30.0
END DESCRIPTION:
XS GIS Cut Line= 4
      2270351.37     13279170.27      2270547.38     13278937.97
      2270765.15     13278531.45      2270801.45     13278233.78
#Sta/Elev= 30
  4451.7   184.4  4480.3  184.03  4486.8  184.96  4494.6  183.96  4607.8  181.64
  4671.5  179.19  4753.1  173.94  4786.7  172.82  4868.8   167.1  4874.4  167.52
  4890.7  164.74  4918.3  161.79  4940.2  159.99  4949.8  157.04  4984.1  157.05
  4991.7  154.35  4994.4  153.85  4997.7  154.35  5022.3  160.94  5029.2  161.03
  5044.2  158.36  5060.5  161.66  5074.6   161.8  5082.4  164.22  5088.1  163.23
  5104.4  165.42  5170.2  167.79  5208.3  171.16  5338.1  178.29  5516.7   189.3
#Mann= 4 ,-1 , 0
  4451.7      .1       0  4991.7     .07       0  4997.7      .1       0
  5338.1     .05       0
Bank Sta=4918.3,5022.3
XS Rating Curve= 0 ,0
Exp/Cntr=0.3,0.1

Type RM Length L Ch R = 1 ,19083   ,547,547,547
BEGIN DESCRIPTION:
GILDEN CREEK 29.0
END DESCRIPTION:
XS GIS Cut Line= 3
      2270525.61     13279177.52       2270721.6     13279097.67
      2271280.57     13278683.88
#Sta/Elev= 30
  4441.6  181.68  4627.5  172.53  4708.9   169.7  4735.5  167.75  4747.7  167.41
    4759  167.29  4765.2  166.06  4779.9  166.77  4809.1  165.98  4822.6  163.68
  4844.6  163.65  4850.8   164.7  4899.1  161.94  4936.4  159.78  4944.8  158.63
    4951  156.38  4971.9  156.88  4998.1  155.23  5000.8  154.73  5004.1  155.23
  5044.9  159.97  5051.2  162.04  5086.6  165.41  5115.9  166.44  5251.5  176.86
  5266.2  176.62  5322.5   180.1  5330.9  179.58  5337.1     181  5348.7  180.32
#Mann= 6 ,-1 , 0
  4441.6     .05       0  4735.5      .1       0  4747.7     .05       0
  4899.1      .1       0  4998.1     .07       0  5004.1      .1       0
Bank Sta=4936.4,5044.9
XS Rating Curve= 0 ,0
Exp/Cntr=0.3,0.1

Type RM Length L Ch R = 1 ,18536   ,435,435,435
BEGIN DESCRIPTION:
GILDEN CREEK 28.0
END DESCRIPTION:
XS GIS Cut Line= 3
       2270503.8     13279344.46      2270663.52     13279467.89
      2271491.05     13279366.26
#Sta/Elev= 30
  4340.5  182.17    4373  181.64  4437.3  178.96  4495.3  175.64    4547  174.06
  4576.8  171.95    4738  164.45  4808.5  162.43  4828.7  162.65  4899.2  160.25
  4959.7  157.07  4969.7  155.43  4979.8  155.14  4989.9  150.95  5000.5  150.91
  5003.3  150.41  5006.5  150.91    5010   152.7  5030.2  155.32  5040.3  159.31
  5070.5  161.82  5100.7  166.35  5151.1  170.34  5161.1   171.8  5166.2   171.3
  5224.5  177.13  5282.1  181.47  5312.3  184.81  5337.8  185.95  5376.1  187.64
#Mann= 5 ,-1 , 0
  4340.5      .1       0  5000.5     .07       0  5006.5      .1       0
  5224.5     .08       0  5337.8      .1       0
Bank Sta=4979.8,5030.2
XS Rating Curve= 0 ,0
Exp/Cntr=0.3,0.1

Type RM Length L Ch R = 1 ,18101   ,410,410,410
BEGIN DESCRIPTION:
GILDEN CREEK 27.0
END DESCRIPTION:
XS GIS Cut Line= 4
      2270505.49     13280000.35      2270713.83     13280009.03
      2271338.83     13279765.97      2271469.04      13279488.2
#Sta/Elev= 30
  4263.3  187.17  4395.6  178.89  4471.3  172.31  4491.9  172.41  4497.5   171.1
  4546.3  168.12  4570.8  167.75  4698.1  160.68  4736.5  159.93    4755  159.85
  4763.9  159.08  4769.3  156.56  4793.8   155.2  4799.2  159.67  4818.3  156.24
  4840.8   155.3  4848.2  153.11  4853.6  155.65  4872.8  152.05  4878.1  153.19
  4883.7  152.45  4902.6  156.02  4957.1  155.33  4998.7  150.74  5001.5  150.24
  5004.7  150.74  5016.8  155.37  5055.4   160.6  5175.2  166.25  5449.2  183.05
#Mann= 6 ,-1 , 0
  4263.3      .1       0  4698.1     .16       0  4736.5      .1       0
  4998.7     .07       0  5004.7      .1       0  5175.2      .1       0
Bank Sta=4957.1,5016.8
XS Rating Curve= 0 ,0
Exp/Cntr=0.3,0.1

Type RM Length L Ch R = 1 ,17691   ,427,427,427
BEGIN DESCRIPTION:
GILDEN CREEK 26.0
END DESCRIPTION:
XS GIS Cut Line= 3
      2271187.74     13280346.84      2271337.72     13280196.85
      2271637.71     13279596.88
#Sta/Elev= 30
  4792.4  177.14  4834.8  174.48  4848.9   171.8  4877.2  168.93  4891.4  166.27
  4933.8  162.01  4947.9  159.21  4976.2  155.73    4998  149.23  5000.7  148.73
    5004  149.23  5012.9  149.49  5018.5  151.72  5047.6  153.33  5071.6  154.72
  5102.3  156.06  5107.9   155.2  5138.7  155.59  5219.7  159.82  5228.1  159.26
  5272.8  161.43  5274.6  161.53  5304.7  162.47  5376.3  164.34  5452.5  168.36
  5601.2  177.29  5630.6  179.93    5653  179.78  5661.4  182.07  5675.3  182.17
#Mann= 9 ,-1 , 0
  4792.4      .1       0    4998     .07       0    5004      .1       0
  5047.6     .16       0  5272.8     .12       0  5274.6      .1       0
  5304.7     .16       0  5452.5      .1       0  5601.2     .08       0
Bank Sta=4976.2,5071.6
XS Rating Curve= 0 ,0
Exp/Cntr=0.3,0.1

Type RM Length L Ch R = 1 ,17264   ,413,413,413
BEGIN DESCRIPTION:
GILDEN CREEK 25.0
END DESCRIPTION:
XS GIS Cut Line= 3
       2271437.7     13280596.87      2271687.72     13280446.85
      2271887.71     13279846.88
#Sta/Elev= 30
  4679.1  173.72  4702.5  172.81  4714.1  171.05  4760.8  166.82  4819.1  162.96
  4846.3   160.3  4861.8  157.88    4889  155.41  4920.1  153.53  4935.7  150.72
  4957.1  150.28  4981.2  151.42  4988.8  147.71  4991.5  147.21  4994.8  147.71
  5002.3  147.94  5029.9  151.92    5055  154.14  5128.8  154.66    5171  156.49
  5270.6  157.94  5297.4  159.74  5329.1  160.83  5339.6  162.07  5392.3   164.3
  5550.3  168.73    5561  169.31  5579.9  168.56  5592.6  170.06  5603.1   170.5
#Mann= 7 ,-1 , 0
  4679.1      .1       0  4988.8     .07       0  4994.8      .1       0
  5029.9     .16       0  5270.6      .1       0  5550.3     .05       0
  5579.9     .08       0
Bank Sta=4981.2,5029.9
XS Rating Curve= 0 ,0
Exp/Cntr=0.3,0.1

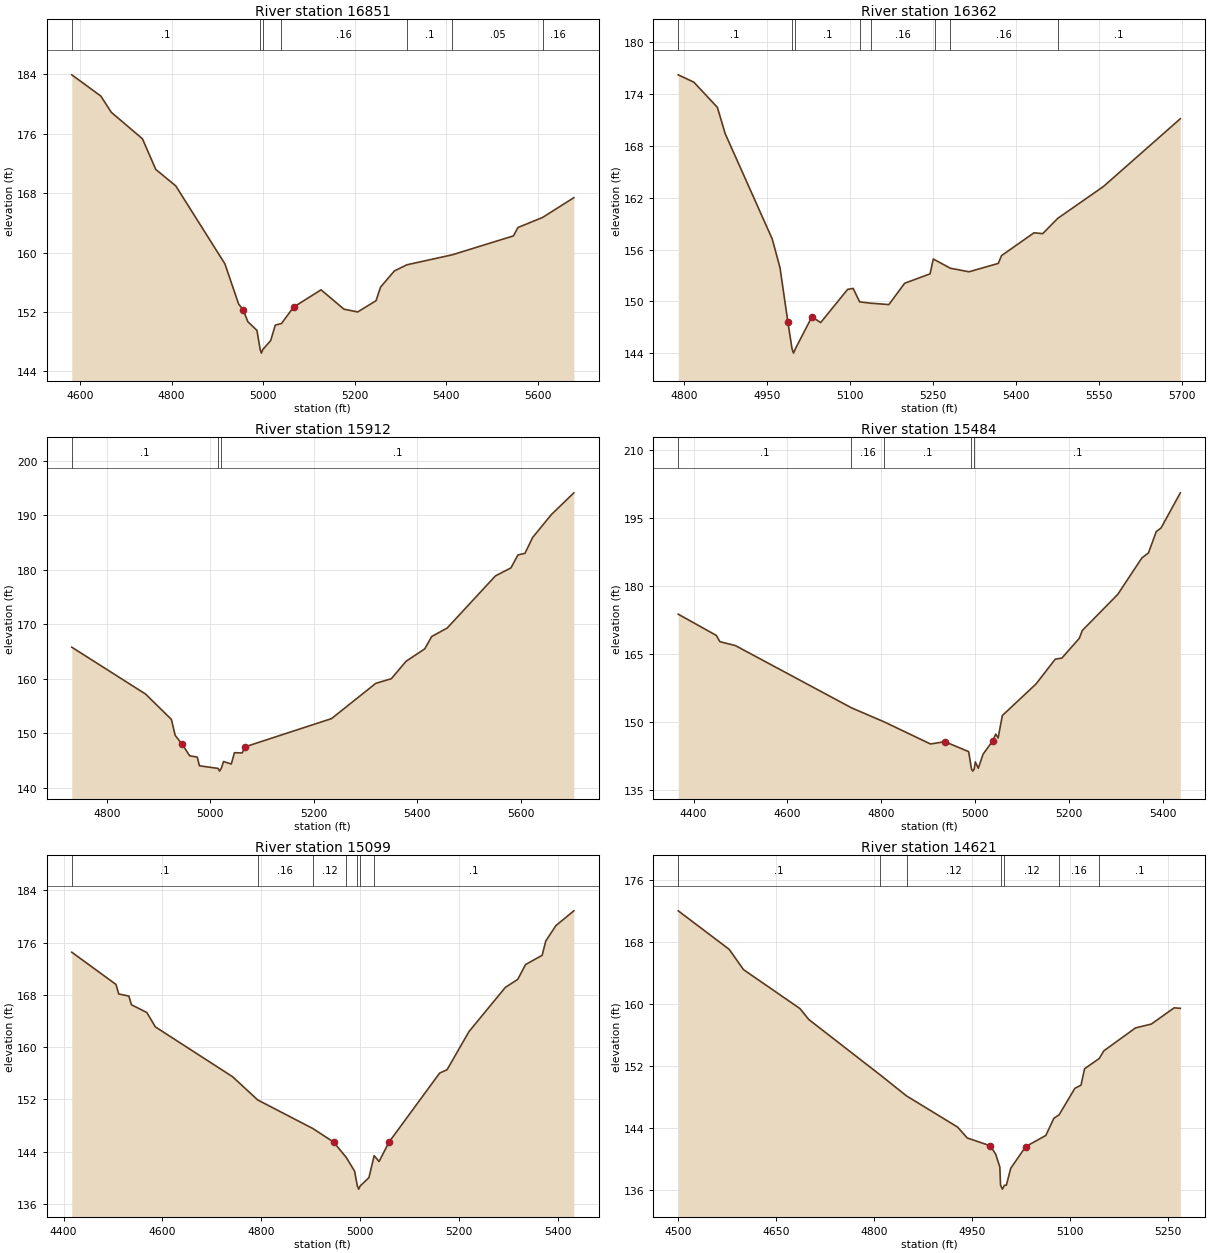
Type RM Length L Ch R = 1 ,16851   ,489,489,489
BEGIN DESCRIPTION:
GILDEN CREEK 24.0
END DESCRIPTION:
XS GIS Cut Line= 3
      2271955.13     13280972.61        2272068.     13280764.23
      2272059.32     13279904.86
#Sta/Elev= 30
  4581.9  183.94  4645.4  181.08  4668.1   178.9  4736.3  175.32  4765.3   171.2
    4809  168.98  4916.3  158.48  4946.3  153.06  4956.3   152.3  4966.3  150.69
  4986.3  149.52  4993.3  146.95    4996  146.45  4999.3  146.95  5016.3  148.14
  5026.3  150.22  5039.8  150.44  5066.3  152.65  5126.3  154.98  5176.3  152.37
  5206.3     152  5246.3  153.51  5256.3  155.35  5286.3  157.52  5313.7  158.35
  5412.5  159.69  5546.3  162.24  5556.3  163.37  5610.1  164.73  5678.3  167.39
#Mann= 7 ,-1 , 0
  4581.9      .1       0  4993.3     .07       0  4999.3      .1       0
  5039.8     .16       0  5313.7      .1       0  5412.5     .05       0
  5610.1     .16       0
Bank Sta=4956.3,5066.3
XS Rating Curve= 0 ,0
Exp/Cntr=0.3,0.1

Type RM Length L Ch R = 1 ,16362   ,450,450,450
BEGIN DESCRIPTION:
GILDEN CREEK 23.0
END DESCRIPTION:
XS GIS Cut Line= 3
      2272637.69     13280546.82      2272487.72     13280396.85
      2272137.72     13279796.86
#Sta/Elev= 30
  4789.6  176.25  4817.8   175.4  4860.3  172.48  4874.4  169.43  4959.3  157.23
  4973.4  153.89  4987.5  147.64  4995.1  144.49  4997.9  143.99  5001.1  144.49
    5031   148.2  5046.8  147.53  5095.5  151.38  5105.5  151.49  5117.2  149.93
  5136.9  149.78    5170  149.62  5198.5  152.09  5244.4  153.18  5250.2   154.9
  5253.3  154.79  5281.1  153.83  5314.7  153.42  5367.6  154.39  5373.4  155.29
  5432.1  157.94  5447.8  157.84  5474.9  159.61  5557.4   163.3  5696.3  171.16
#Mann= 8 ,-1 , 0
  4789.6      .1       0  4995.1     .07       0  5001.1      .1       0
  5117.2     .05       0  5136.9     .16       0  5253.3      .1       0
  5281.1     .16       0  5474.9      .1       0
Bank Sta=4987.5,5031
XS Rating Curve= 0 ,0
Exp/Cntr=0.3,0.1

Type RM Length L Ch R = 1 ,15912   ,428,428,428
BEGIN DESCRIPTION:
GILDEN CREEK 22.0
END DESCRIPTION:
XS GIS Cut Line= 3
      2272837.73     13280146.86      2272637.72     13279996.85
      2272237.73     13279396.87
#Sta/Elev= 30
    4732  165.77  4874.7  157.18  4924.7  152.53    4932   149.6  4945.5  147.97
  4960.1  145.85  4974.7  145.62  4978.9  144.02  5015.1  143.54  5017.8  143.04
  5021.1  143.54  5025.6   144.8  5040.6  144.35  5046.6  146.42  5061.6  146.38
  5067.6  147.51  5234.4  152.67    5320  159.14  5350.1  159.99  5378.6  163.19
  5414.7  165.46  5428.2  167.73  5458.2  169.29  5551.4  178.84  5581.4  180.31
    5595  182.69  5608.5  182.98  5623.5   185.9  5659.6  190.09  5703.1  194.08
#Mann= 3 ,-1 , 0
    4732      .1       0  5015.1     .07       0  5021.1      .1       0
Bank Sta=4945.5,5067.6
XS Rating Curve= 0 ,0
Exp/Cntr=0.3,0.1

Type RM Length L Ch R = 1 ,15484   ,385,385,385
BEGIN DESCRIPTION:
GILDEN CREEK 21.0
END DESCRIPTION:
XS GIS Cut Line= 3
      2272937.71     13280246.81      2272837.72     13279646.85
      2272937.72     13279196.87
#Sta/Elev= 30
  4367.4  173.78  4448.5  169.11  4456.1  167.73    4489  166.88  4736.3  153.18
  4806.5  150.06  4904.7  145.22  4935.1  145.73  4985.9  143.54  4991.8  139.75
  4994.6  139.25  4997.8  139.75    5000  141.27  5006.4  139.88  5016.6  142.98
  5037.1   145.9  5043.5   147.4  5048.6  146.55  5057.6  151.48  5129.3  158.42
  5170.3  163.89  5184.4  164.12  5221.5  168.47  5227.9  170.19  5303.4  178.14
  5354.7  186.15  5368.7  187.25  5385.4  191.95  5395.6  192.75  5436.6  200.48
#Mann= 5 ,-1 , 0
  4367.4      .1       0  4736.3     .16       0  4806.5      .1       0
  4991.8     .07       0  4997.8      .1       0
Bank Sta=4935.1,5037.1
XS Rating Curve= 0 ,0
Exp/Cntr=0.3,0.1

Type RM Length L Ch R = 1 ,15099   ,478,478,478
BEGIN DESCRIPTION:
GILDEN CREEK 87.0
END DESCRIPTION:
XS GIS Cut Line= 3
      2273043.79     13280266.77      2273127.11     13280023.75
       2273286.7     13279281.32
#Sta/Elev= 30
  4416.5  174.52    4506  169.59  4511.6  168.13    4532  167.81  4537.3  166.48
  4568.5  165.29  4585.6   163.1  4741.8  155.48    4793  151.91  4904.3  147.55
  4946.4  145.48  4972.1  143.12    4989  141.02  4994.5  138.77  4997.3  138.27
  5000.5  138.77    5018  140.02  5028.6  143.39  5038.5  142.49  5058.9  145.49
  5161.2  156.03  5176.2  156.54  5220.5  162.37  5294.2  169.14  5319.2  170.36
  5335.1  172.63  5368.6  174.04    5376  176.24  5396.5  178.59  5432.8  180.85
#Mann= 7 ,-1 , 0
  4416.5      .1       0    4793     .16       0  4904.3     .12       0
  4972.1     .16       0  4994.5     .07       0  5000.5     .16       0
  5028.6      .1       0
Bank Sta=4946.4,5058.9
XS Rating Curve= 0 ,0
Exp/Cntr=0.3,0.1

Type RM Length L Ch R = 1 ,14621   ,396,396,396
BEGIN DESCRIPTION:
GILDEN CREEK 19.0
END DESCRIPTION:
XS GIS Cut Line= 3
      2273137.74     13280296.84      2273537.72     13279996.85
      2273637.71     13279746.88
#Sta/Elev= 30
  4500.4  171.97  4578.5  167.01  4600.4   164.4  4686.8  159.39  4700.4  157.98
  4809.6  150.86  4850.2  148.14  4928.5  144.12  4943.1  142.73  4978.5  141.72
  4986.8  140.63  4993.1  138.99  4994.2  136.64    4997  136.14  5000.2  136.64
  5003.1  136.64  5009.8  138.82  5032.7  141.61  5063.6  143.05  5075.8  145.25
  5083.9  145.71  5108.1  149.12  5117.5  149.53  5122.9  151.64  5145.4  152.96
  5152.5  153.95    5201   156.9  5225.2  157.39  5260.2  159.48  5269.6  159.42
#Mann= 7 ,-1 , 0
  4500.4      .1       0  4809.6     .16       0  4850.2     .12       0
  4994.2     .07       0  5000.2     .12       0  5083.9     .16       0
  5145.4      .1       0
Bank Sta=4978.5,5032.7
XS Rating Curve= 0 ,0
Exp/Cntr=0.3,0.1

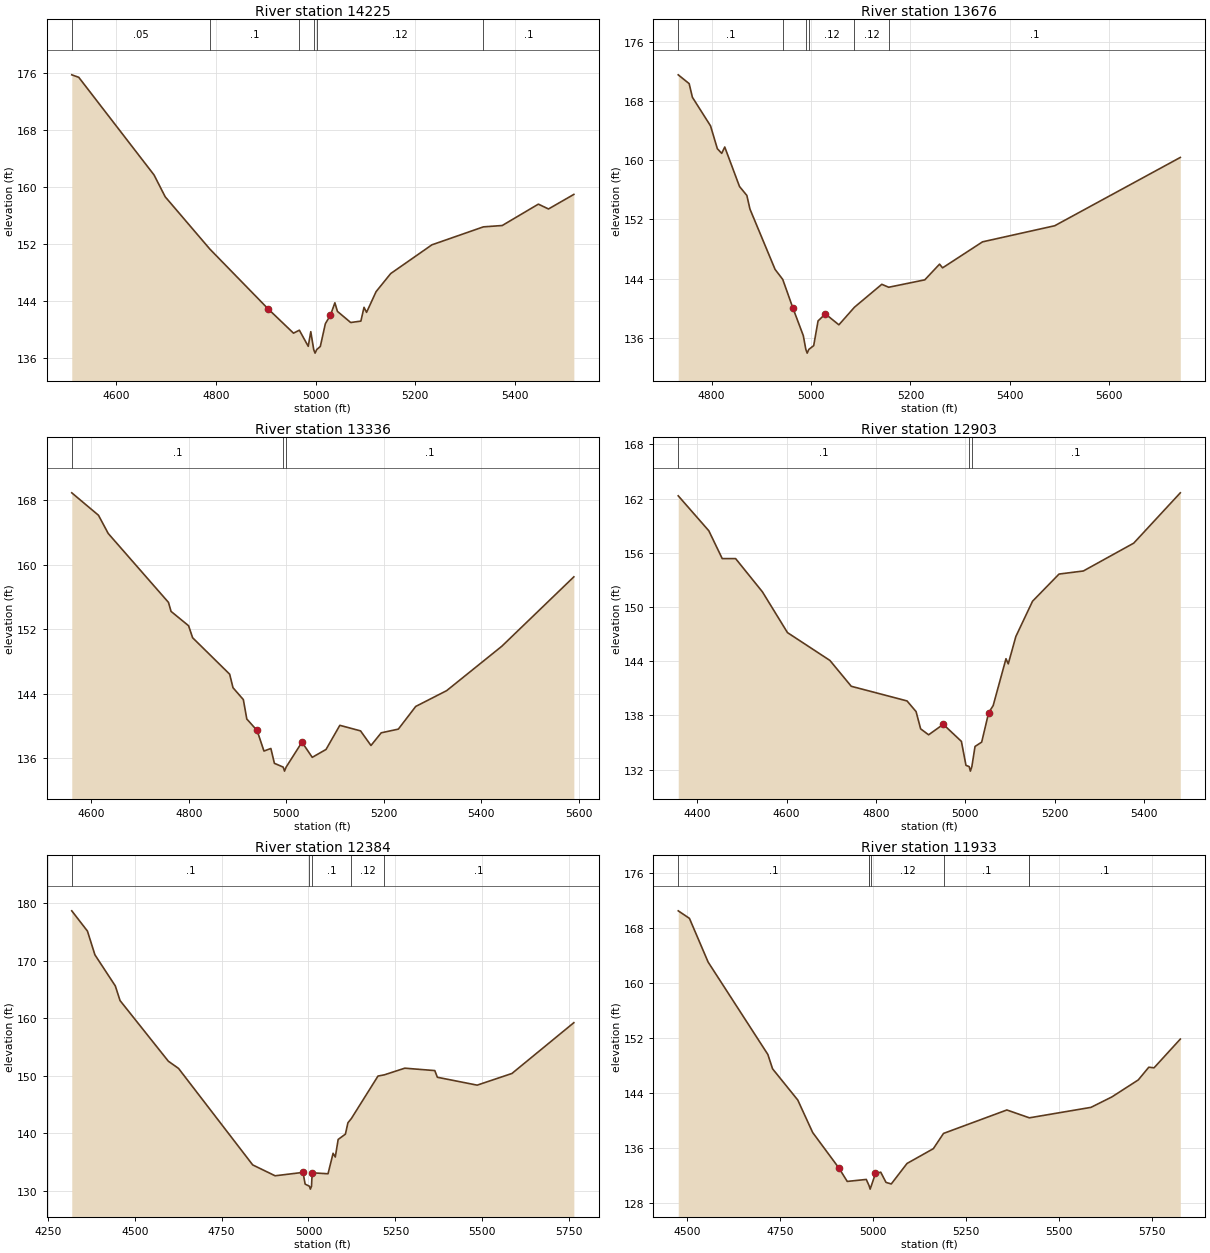
Type RM Length L Ch R = 1 ,14225   ,549,549,549
BEGIN DESCRIPTION:
GILDEN CREEK 18.0
END DESCRIPTION:
XS GIS Cut Line= 3
      2273637.71     13280696.87      2273837.72     13280296.85
      2273737.73      13279746.9
#Sta/Elev= 30
  4511.4  175.81  4525.4  175.46  4676.3  161.71  4698.7  158.63  4788.3  151.26
  4905.5  142.81  4955.8  139.43  4967.5  139.85  4985.3  137.58  4990.4  139.64
  4996.3  137.12    4999  136.62  5002.3  137.12  5009.5  137.56  5019.6  140.76
  5029.8  141.97  5038.7  143.71  5043.8   142.5  5070.4  140.93  5090.8  141.13
  5097.1  143.07  5102.2  142.36  5121.3  145.28  5150.5  147.82  5233.1  151.87
  5336.3   154.4  5374.1  154.59  5446.5   157.6  5466.8  156.92  5517.6  158.97
#Mann= 6 ,-1 , 0
  4511.4     .05       0  4788.3      .1       0  4967.5     .12       0
  4996.3     .07       0  5002.3     .12       0  5336.3      .1       0
Bank Sta=4905.5,5029.8
XS Rating Curve= 0 ,0
Exp/Cntr=0.3,0.1

Type RM Length L Ch R = 1 ,13676   ,340,340,340
BEGIN DESCRIPTION:
GILDEN CREEK 17.0
END DESCRIPTION:
XS GIS Cut Line= 3
      2274481.16     13280304.14        2273943.      13279930.9
      2273770.36     13279620.16
#Sta/Elev= 30
  4732.8  171.52  4754.8  170.33  4761.3  168.49  4797.8  164.63  4811.5  161.55
  4820.3  160.92  4826.4  161.78  4856.1  156.45  4870.9  155.24  4877.1  153.41
  4927.7  145.26  4943.1  143.91  4963.5  140.06  4984.5  136.32  4989.6  134.46
  4992.3  133.96  4995.6  134.46  5005.4  134.97  5014.2  138.31    5029  139.25
  5056.1  137.78  5087.5  140.16  5142.5  143.25  5156.3  142.85    5229  143.85
  5258.7  145.97  5264.8  145.47  5345.2  148.98  5490.4  151.15  5743.2  160.37
#Mann= 6 ,-1 , 0
  4732.8      .1       0  4943.1     .12       0  4989.6     .07       0
  4995.6     .12       0  5087.5     .12       0  5156.3      .1       0
Bank Sta=4963.5,5029
XS Rating Curve= 0 ,0
Exp/Cntr=0.3,0.1

Type RM Length L Ch R = 1 ,13336   ,433,433,433
BEGIN DESCRIPTION:
GILDEN CREEK 16.0
END DESCRIPTION:
XS GIS Cut Line= 3
      2274541.96     13280200.04      2274481.19     13279956.94
      2273916.98     13279418.77
#Sta/Elev= 30
    4560  168.94  4614.8  166.16  4634.8   163.9  4758.5  155.35  4763.7  154.24
  4799.7  152.46    4808  150.97    4884  146.45  4890.9  144.77  4912.1   143.3
  4919.2  140.89  4940.3  139.47  4954.4  136.92  4968.6  137.24  4975.8   135.4
  4993.9  134.93  4996.6  134.43  4999.9  134.93  5032.4  138.02  5053.5  136.14
  5081.8  137.12  5110.1  140.11  5152.6  139.42    5174  137.61    5195  139.18
  5230.2  139.64  5265.8  142.45  5329.3  144.41  5442.6  149.92  5590.3  158.52
#Mann= 3 ,-1 , 0
    4560      .1       0  4993.9     .07       0  4999.9      .1       0
Bank Sta=4940.3,5032.4
XS Rating Curve= 0 ,0
Exp/Cntr=0.3,0.1

Type RM Length L Ch R = 1 ,12903   ,519,519,519
BEGIN DESCRIPTION:
GILDEN CREEK 15.0
END DESCRIPTION:
XS GIS Cut Line= 3
       2274654.8     13280165.29      2274663.48     13279896.18
      2274515.91     13279054.16
#Sta/Elev= 30
  4357.4   162.3  4425.9  158.43  4455.9  155.35  4485.9  155.35  4545.9  151.67
    4602  147.16    4697  144.08  4744.8  141.22  4869.6   139.6  4889.9  138.42
  4900.1  136.51    4918  135.85  4950.8  137.01  4991.4  135.12  5001.6  132.47
  5008.8  132.33  5011.5  131.83  5014.8  132.33  5021.9  134.56  5036.8  135.04
  5052.4   138.3  5062.5  139.08  5091.2  144.27  5096.3   143.7  5113.3  146.73
  5150.6  150.63    5210  153.64  5264.4  153.98  5377.2  157.06  5481.5  162.63
#Mann= 3 ,-1 , 0
  4357.4      .1       0  5008.8     .07       0  5014.8      .1       0
Bank Sta=4950.8,5052.4
XS Rating Curve= 0 ,0
Exp/Cntr=0.3,0.1

Type RM Length L Ch R = 1 ,12384   ,451,451,451
BEGIN DESCRIPTION:
GILDEN CREEK 14.0
END DESCRIPTION:
XS GIS Cut Line= 3
      2275437.73     13280246.87      2275087.72     13279646.85
      2274637.74     13279046.88
#Sta/Elev= 30
  4318.9  178.65    4364  175.13  4385.5     171  4444.2  165.59  4457.8  163.05
  4596.8   152.5  4626.1  151.25  4839.5  134.47    4904  132.58  4984.2  133.17
  4990.4  131.13  5002.7  130.76  5005.4  130.26  5008.7  130.76  5010.6   133.1
  5056.2  132.93  5070.8  136.49  5077.1  135.84  5085.4   138.9  5106.2  139.82
  5113.5   141.8  5123.2  142.52    5200  149.92  5218.1  150.13  5277.1  151.29
  5363.5  150.87  5370.8  149.71  5485.4  148.34  5585.4  150.37  5763.5   159.2
#Mann= 5 ,-1 , 0
  4318.9      .1       0  5002.7     .07       0  5008.7      .1       0
  5123.2     .12       0  5218.1      .1       0
Bank Sta=4984.2,5010.6
XS Rating Curve= 0 ,0
Exp/Cntr=0.3,0.1

Type RM Length L Ch R = 1 ,11933   ,726,726,726
BEGIN DESCRIPTION:
GILDEN CREEK 13.0
END DESCRIPTION:
XS GIS Cut Line= 3
      2275537.72     13280046.87      2275487.72     13279546.85
      2274887.75     13278946.88
#Sta/Elev= 30
  4475.6  170.49  4505.8  169.39    4556  163.04  4716.8   149.6  4729.4  147.52
  4797.2  142.98  4837.4  138.25  4907.8   133.1  4930.4  131.14  4981.6  131.43
    4989  130.54  4989.2  130.52    4992  130.02  4995.2  130.52  5006.4   132.3
  5020.5  132.48  5034.7     131  5048.8  130.77  5091.2  133.75    5162   135.9
  5189.4  138.12  5359.9  141.53  5419.8   140.4  5420.6  140.39  5586.2  141.91
  5642.8  143.44  5713.5   145.9  5741.8  147.75  5755.9  147.66  5826.6  151.84
#Mann= 7 ,-1 , 0
  4475.6      .1       0    4989     .12       0  4989.2     .07       0
  4995.2     .12       0  5189.4      .1       0  5419.8     .12       0
  5420.6      .1       0
Bank Sta=4907.8,5006.4
XS Rating Curve= 0 ,0
Exp/Cntr=0.3,0.1

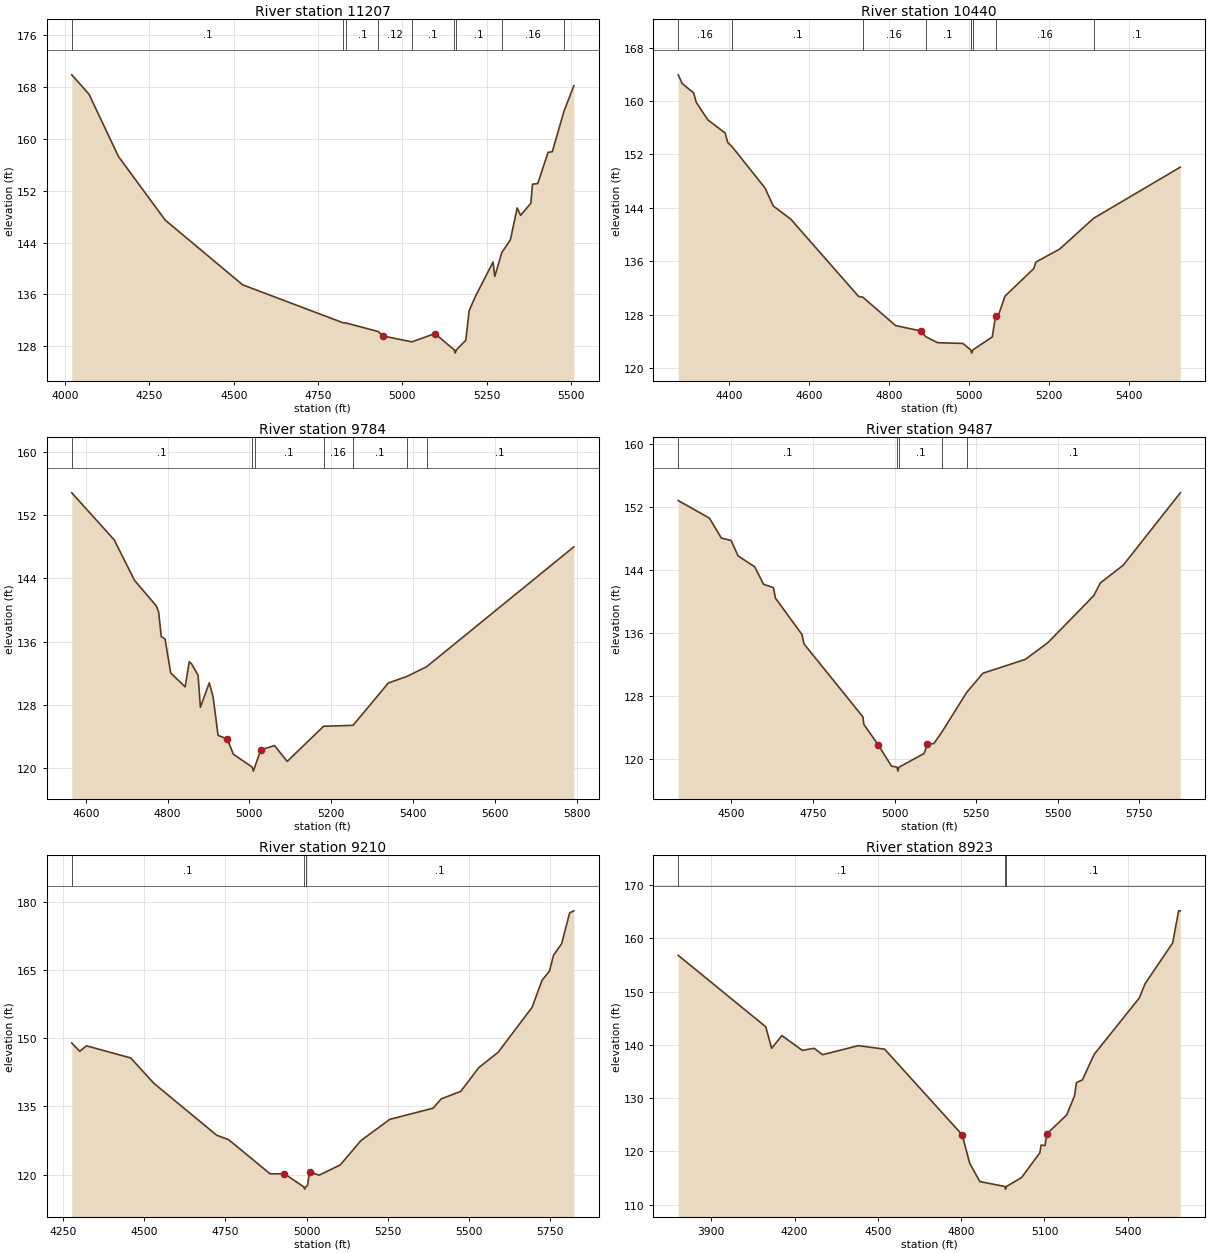
Type RM Length L Ch R = 1 ,11207   ,767,767,767
BEGIN DESCRIPTION:
GILDEN CREEK 12.0
END DESCRIPTION:
XS GIS Cut Line= 3
      2275587.74     13279996.83      2276010.08     13279263.33
      2276124.62     13278631.63
#Sta/Elev= 30
  4019.9  169.89  4070.9  166.91  4158.3  157.29  4296.8  147.48  4526.4  137.49
  4823.8  131.64    4834  131.59  4928.2  130.28    4944  129.58  5028.1  128.69
  5096.5  129.96  5153.9  127.45  5156.6  126.95  5159.9  127.45  5187.9  128.93
  5198.1  133.51  5215.4  135.59  5268.8  141.01  5273.9  138.78  5294.5  142.44
  5320.1  144.42  5340.4  149.35  5350.5   148.2  5380.8  150.08  5385.8  153.01
  5401.4  153.12  5431.8  157.93  5444.4  158.02    5479  164.26  5508.3  168.21
#Mann= 9 ,-1 , 0
  4019.9      .1       0  4823.8     .12       0    4834      .1       0
  4928.2     .12       0  5028.1      .1       0  5153.9     .07       0
  5159.9      .1       0  5294.5     .16       0    5479      .1       0
Bank Sta=4944,5096.5
XS Rating Curve= 0 ,0
Exp/Cntr=0.3,0.1

Type RM Length L Ch R = 1 ,10440   ,656,656,656
BEGIN DESCRIPTION:
GILDEN CREEK 11.0
END DESCRIPTION:
XS GIS Cut Line= 4
      2275697.56     13280110.58      2275985.77      13279742.5
      2276447.58     13279593.19      2276596.17     13279330.55
#Sta/Elev= 30
  4273.1  163.92  4282.8  162.63  4311.7  161.21  4318.1   159.8    4347  157.18
  4390.4  155.21  4396.8  153.78    4408  153.14  4489.9  146.97  4510.7  144.27
  4554.1  142.32  4724.1  130.71  4733.9  130.64  4816.2  126.37  4879.3  125.56
  4891.3  124.71  4921.3   123.8  4984.4  123.69  5003.7  122.74  5006.4  122.24
  5009.7  122.74  5057.9  124.67  5066.1  127.85  5070.7  127.47  5089.5  130.77
  5161.5   134.9  5166.8  135.88  5225.9  137.81  5311.2  142.44  5527.7  150.09
#Mann= 8 ,-1 , 0
  4273.1     .16       0    4408      .1       0  4733.9     .16       0
  4891.3      .1       0  5003.7     .07       0  5009.7      .1       0
  5066.1     .16       0  5311.2      .1       0
Bank Sta=4879.3,5066.1
XS Rating Curve= 0 ,0
Exp/Cntr=0.3,0.1

Type RM Length L Ch R = 1 ,9784    ,297,297,297
BEGIN DESCRIPTION:
GILDEN CREEK 10.0
END DESCRIPTION:
XS GIS Cut Line= 3
      2276087.69     13280396.87      2276437.72     13280196.85
      2276637.73     13279396.83
#Sta/Elev= 30
  4565.6  154.83  4669.3  148.88    4719  143.76  4772.2  140.52    4778  139.76
  4784.5  136.63  4793.8  136.32  4807.5  132.03  4842.8  130.27  4852.9  133.45
  4858.6  133.18  4874.5  131.73  4880.2  127.68  4901.8  130.78  4911.2  129.01
  4923.4  124.12  4945.7  123.68  4960.8  121.74    5007   120.1  5009.7   119.6
    5013   120.1    5028  122.31  5061.5  122.83  5092.4  120.83  5181.4  125.28
  5253.5   125.4  5339.8  130.76  5384.8  131.58  5433.2  132.81  5793.4  147.99
#Mann= 7 ,-1 , 0
  4565.6      .1       0    5007     .07       0    5013      .1       0
  5181.4     .16       0  5253.5      .1       0  5384.8     .16       0
  5433.2      .1       0
Bank Sta=4945.7,5028
XS Rating Curve= 0 ,0
Exp/Cntr=0.3,0.1

Type RM Length L Ch R = 1 ,9487    ,277,277,277
BEGIN DESCRIPTION:
GILDEN CREEK 9.0
END DESCRIPTION:
XS GIS Cut Line= 3
      2276259.36      13280552.1      2276736.78     13280239.61
      2276741.12     13279271.82
#Sta/Elev= 30
  4337.1  152.78  4432.8  150.55    4469  148.03  4499.2  147.72  4520.3  145.77
  4571.6  144.37  4598.6  142.16  4628.8  141.74  4634.8  140.42  4716.3  135.79
  4722.3  134.61  4903.2  125.34  4905.7  124.41  4950.5  121.76  4990.5  119.11
  5007.5  118.97  5010.2  118.47  5013.5  118.97  5090.5  120.71  5100.5  121.88
  5120.5  121.97  5145.2  123.44  5220.9  128.45  5270.5  130.88  5400.5  132.64
  5470.5  134.79  5610.5  140.73  5630.5  142.34  5700.5  144.58  5875.5  153.76
#Mann= 5 ,-1 , 0
  4337.1      .1       0  5007.5     .07       0  5013.5      .1       0
  5145.2     .16       0  5220.9      .1       0
Bank Sta=4950.5,5100.5
XS Rating Curve= 0 ,0
Exp/Cntr=0.3,0.1

Type RM Length L Ch R = 1 ,9210    ,287,287,287
BEGIN DESCRIPTION:
GILDEN CREEK 79.0
END DESCRIPTION:
XS GIS Cut Line= 3
      2276415.62     13280578.13      2277162.13     13280039.95
      2277748.04     13279818.61
#Sta/Elev= 30
  4276.5  148.98    4301  147.16  4321.8  148.36    4458  145.69  4529.2  140.12
  4722.9  128.67  4759.9  127.68  4887.5  120.17  4931.7  120.17  4991.3   117.3
    4994   116.8  4997.3   117.3  5002.8  117.62    5009  120.61  5038.4  119.87
  5103.5  122.13  5166.7  127.45  5256.2  132.17  5389.7  134.63  5414.5  136.68
  5474.9  138.34  5529.9  143.53  5590.2  146.96  5694.5  156.84  5725.1  162.78
  5747.9  164.81  5760.6  168.31  5785.5  170.86  5810.3  177.66  5823.1  178.09
#Mann= 3 ,-1 , 0
  4276.5      .1       0  4991.3     .07       0  4997.3      .1       0
Bank Sta=4931.7,5009
XS Rating Curve= 0 ,0
Exp/Cntr=0.3,0.1

Type RM Length L Ch R = 1 ,8923    ,81,81,81
BEGIN DESCRIPTION:
GILDEN CREEK 81.0
END DESCRIPTION:
XS GIS Cut Line= 4
      2276233.29     13280925.38      2277162.13     13280361.13
      2277327.06     13280222.24        2277691.      13279871.3
#Sta/Elev= 30
  3781.1  156.78  4096.2  143.39  4117.5  139.35  4154.4  141.74    4228  138.96
  4270.6  139.35  4301.1  138.15  4429.8  139.85  4524.5  139.18  4803.6  123.13
  4830.7  117.79  4867.2  114.36  4957.1  113.44  4959.8  112.94  4963.1  113.44
  5017.3   115.1  5083.5  119.78  5087.7  121.21  5101.9   121.1  5109.1  123.33
  5179.8  126.85  5208.1  130.42  5215.1  132.93  5236.4  133.42  5278.9  138.21
  5441.5   148.8  5462.6  151.49  5561.6  159.11    5583  165.12  5589.1  165.13
#Mann= 3 ,-1 , 0
  3781.1      .1       0  4957.1     .07       0  4963.1      .1       0
Bank Sta=4803.6,5109.1
XS Rating Curve= 0 ,0
Exp/Cntr=0.3,0.1

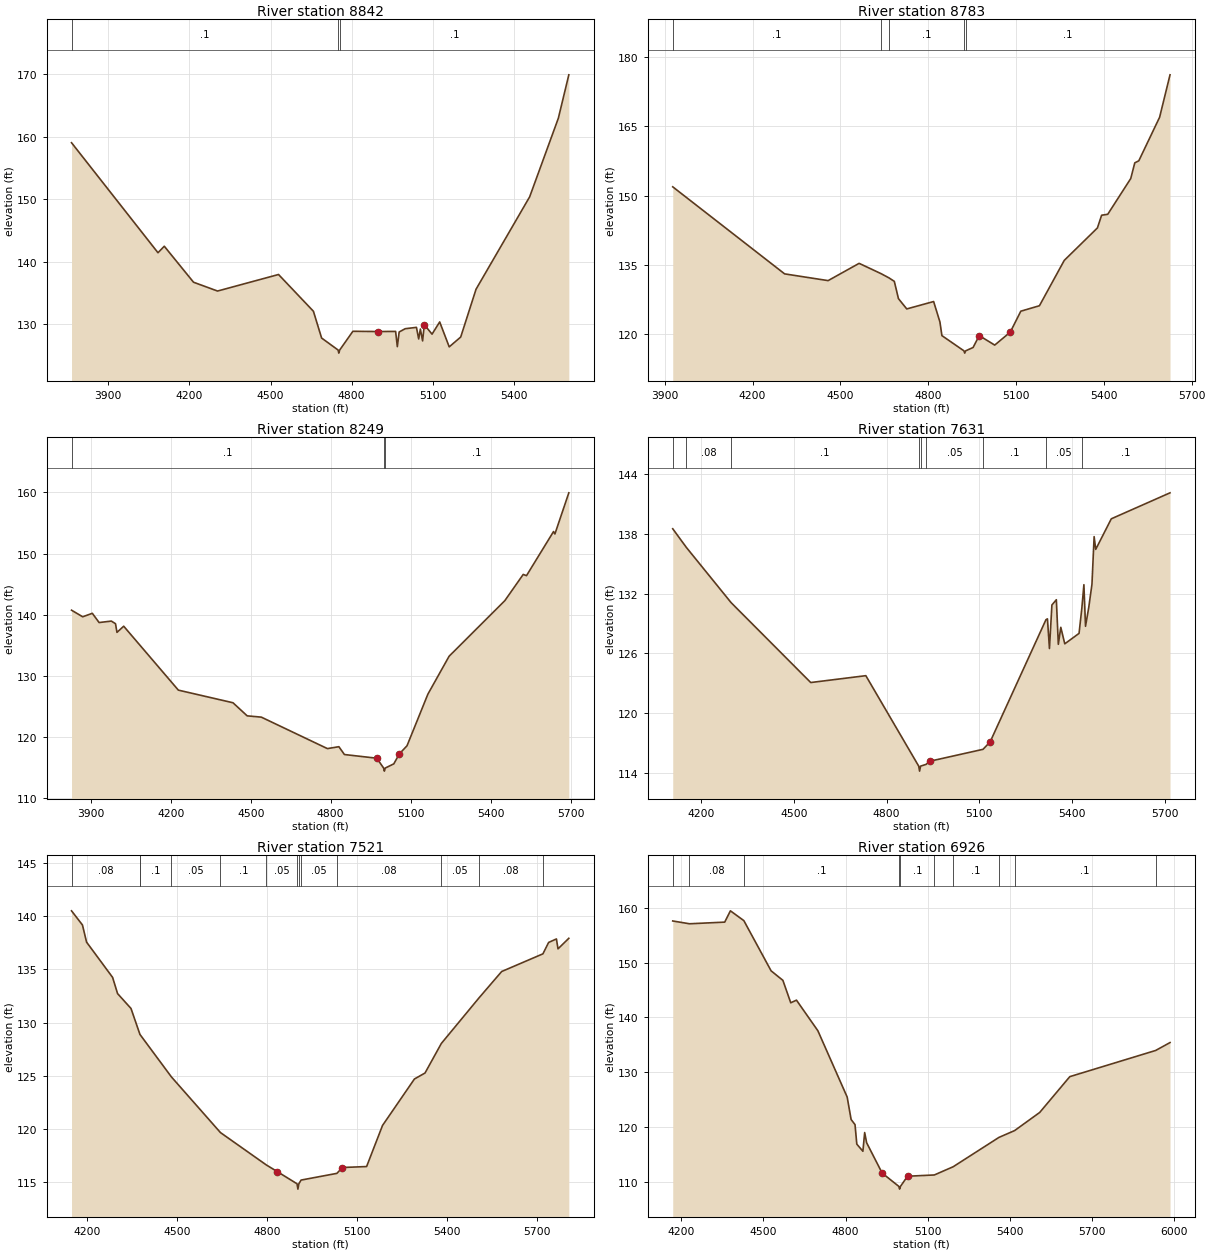
Type RM Length L Ch R = 1 ,8842    ,59,59,59
BEGIN DESCRIPTION:
GILDEN CREEK 80.0
END DESCRIPTION:
XS GIS Cut Line= 4
      2276285.36     13280986.15      2277162.13     13280447.94
       2277396.5     13280269.99      2277748.08     13279892.37
#Sta/Elev= 30
    3764  159.06  4083.7  141.43    4107  142.47  4215.2   136.7    4304  135.29
  4529.5  137.94  4658.5  132.05  4688.8  127.76  4749.7  125.84  4752.4  125.34
  4755.7  125.84  4804.5  128.84    4898   128.8  4962.5  128.82  4968.8  126.38
  4975.6  128.73  4997.9  129.25  5039.5  129.47  5047.8  127.61    5054   129.2
  5062.3   127.3  5068.6   129.9  5097.2  128.38  5125.5  130.34  5160.7  126.34
  5203.2  127.92  5259.9  135.58  5458.2  150.39  5564.3  162.99    5603  169.94
#Mann= 3 ,-1 , 0
    3764      .1       0  4749.7     .07       0  4755.7      .1       0
Bank Sta=4898,5068.6
XS Rating Curve= 0 ,0
Exp/Cntr=0.3,0.1

Type RM Length L Ch R = 1 ,8783    ,534,534,534
BEGIN DESCRIPTION:
GILDEN CREEK 8.0
END DESCRIPTION:
XS GIS Cut Line= 3
      2276587.71     13281096.86      2277387.72     13280346.85
      2277787.74     13279896.84
#Sta/Elev= 30
  3927.4   151.9  4309.6  133.05  4458.1  131.59  4564.1  135.33  4639.3  133.09
  4665.9  132.19  4684.3  131.43  4698.4  127.69  4726.8  125.46  4818.6  127.06
  4840.1  122.64  4846.9  119.68  4922.1  116.39  4924.8  115.89  4928.1  116.39
  4953.4  117.11  4974.4  119.69  5027.3  117.63  5080.4  120.44  5116.4  124.97
    5180  126.15  5264.8  135.97  5378.1     143  5392.4  145.75  5413.3  145.95
  5491.9  153.69  5505.7  157.09  5519.5  157.54  5590.5  166.96  5626.1  176.15
#Mann= 5 ,-1 , 0
  3927.4      .1       0  4639.3     .16       0  4665.9      .1       0
  4922.1     .07       0  4928.1      .1       0
Bank Sta=4974.4,5080.4
XS Rating Curve= 0 ,0
Exp/Cntr=0.3,0.1

Type RM Length L Ch R = 1 ,8249    ,618,618,618
BEGIN DESCRIPTION:
GILDEN CREEK 7.0
END DESCRIPTION:
XS GIS Cut Line= 4
      2276767.16     13281307.32      2277496.33      13281046.9
      2277895.64     13280556.45      2278017.16     13280113.75
#Sta/Elev= 30
  3827.7  140.76  3869.6  139.68  3905.7  140.25  3931.2  138.74    3977  138.98
  3992.7  138.55  3998.2  137.14  4023.5  138.14  4228.5   127.7  4433.4  125.64
  4486.7   123.5  4539.7  123.29  4787.7  118.15  4830.8  118.46  4851.6  117.18
    4973  116.58  4998.7  114.97  5001.5  114.47  5004.7  114.97  5036.9  115.66
  5057.7  117.29  5086.4  118.61  5164.7  127.04  5244.4  133.24  5453.5  142.32
  5522.4   146.6  5534.7   146.4  5636.1   153.6  5641.3  153.21  5693.5  159.93
#Mann= 3 ,-1 , 0
  3827.7      .1       0  4998.7     .07       0  5004.7      .1       0
Bank Sta=4973,5057.7
XS Rating Curve= 0 ,0
Exp/Cntr=0.3,0.1

Type RM Length L Ch R = 1 ,7631    ,110,110,110
BEGIN DESCRIPTION:
GILDEN CREEK 6.0
END DESCRIPTION:
XS GIS Cut Line= 4
      2277261.93     13281493.95      2278164.73     13281207.49
      2278381.75     13280938.39      2278472.82     13280634.82
#Sta/Elev= 30
  4107.9  138.52  4151.9  136.65  4296.8   131.1  4554.6  123.07    4733  123.76
  4904.2  114.67    4907  114.17  4910.2  114.67  4928.1  114.85  4939.5  115.16
  5112.3  116.36  5135.4  117.11    5316  129.38  5320.9  129.47  5327.4  126.49
  5335.3  130.86  5349.7  131.39  5356.1  126.91  5364.1  128.62    5377  126.96
  5423.2  128.01  5432.3  130.56  5438.9   132.9  5444.1  128.72  5454.6  130.61
    5465  132.95    5472  137.73  5477.2  136.45  5527.6  139.52  5717.7  142.13
#Mann= 9 ,-1 , 0
  4107.9      .1       0  4151.9     .08       0  4296.8      .1       0
  4904.2    .035       0  4910.2      .1       0  4928.1     .05       0
  5112.3      .1       0    5316     .05       0  5432.3      .1       0
Bank Sta=4939.5,5135.4
XS Rating Curve= 0 ,0
Exp/Cntr=0.3,0.1

Type RM Length L Ch R = 1 ,7521    ,595,595,595
BEGIN DESCRIPTION:
GILDEN CREEK 5.0
END DESCRIPTION:
XS GIS Cut Line= 4
      2277383.51      13281598.1      2278368.73     13281242.21
      2278485.91     13280994.81      2278594.43     13280677.95
#Sta/Elev= 30
  4149.6  140.49    4186  139.16  4199.7  137.55  4286.4  134.24  4302.9  132.72
  4347.7  131.32  4376.8  128.94  4377.1   128.9  4482.4  124.89  4645.6  119.67
  4798.9  116.62  4834.6  116.01  4900.7  114.86  4903.5  114.36  4906.7  114.86
  4914.1  115.21  5033.4  115.84  5051.8  116.39  5132.3  116.48  5185.4  120.34
  5291.6   124.7  5326.8  125.26  5381.3  128.04  5506.5  132.31  5582.1  134.79
  5719.5  136.45  5738.5  137.52  5764.5  137.85  5769.8  136.92  5805.8  137.91
#Mann= 13 ,-1 , 0
  4149.6     .08       0  4376.8     .05       0  4377.1      .1       0
  4482.4     .05       0  4645.6      .1       0  4798.9     .05       0
  4900.7    .035       0  4906.7     .05       0  4914.1     .05       0
  5033.4     .08       0  5381.3     .05       0  5506.5     .08       0
  5719.5      .1       0
Bank Sta=4834.6,5051.8
XS Rating Curve= 0 ,0
Exp/Cntr=0.3,0.1

Type RM Length L Ch R = 1 ,6926    ,595,595,595
BEGIN DESCRIPTION:
GILDEN CREEK 4.0
END DESCRIPTION:
XS GIS Cut Line= 3
      2278118.75     13282314.23      2278712.48      13281590.3
      2278696.87       13280711.
#Sta/Elev= 30
  4168.8  157.57    4230  157.06  4358.6  157.36  4379.4  159.42  4428.5  157.63
    4528  148.48    4571  146.75  4599.7  142.66  4620.6  143.14  4698.8  137.56
  4805.7  125.48  4820.1  121.39  4834.4  120.45  4840.9   116.9  4863.1   115.6
  4869.6  119.01  4876.7  117.16  4933.5  111.62  4994.3   109.2  4997.1   108.7
  5000.3   109.2    5026  111.05  5123.8  111.28  5192.8  112.78  5359.6  118.12
  5417.1  119.37  5508.6  122.67  5618.6   129.2    5932  133.97  5984.5  135.41
#Mann= 10 ,-1 , 0
  4168.8     .05       0    4230     .08       0  4428.5      .1       0
  4994.3     .07       0  5000.3      .1       0  5123.8     .16       0
  5192.8      .1       0  5359.6     .16       0  5417.1      .1       0
    5932     .08       0
Bank Sta=4933.5,5026
XS Rating Curve= 0 ,0
Exp/Cntr=0.3,0.1