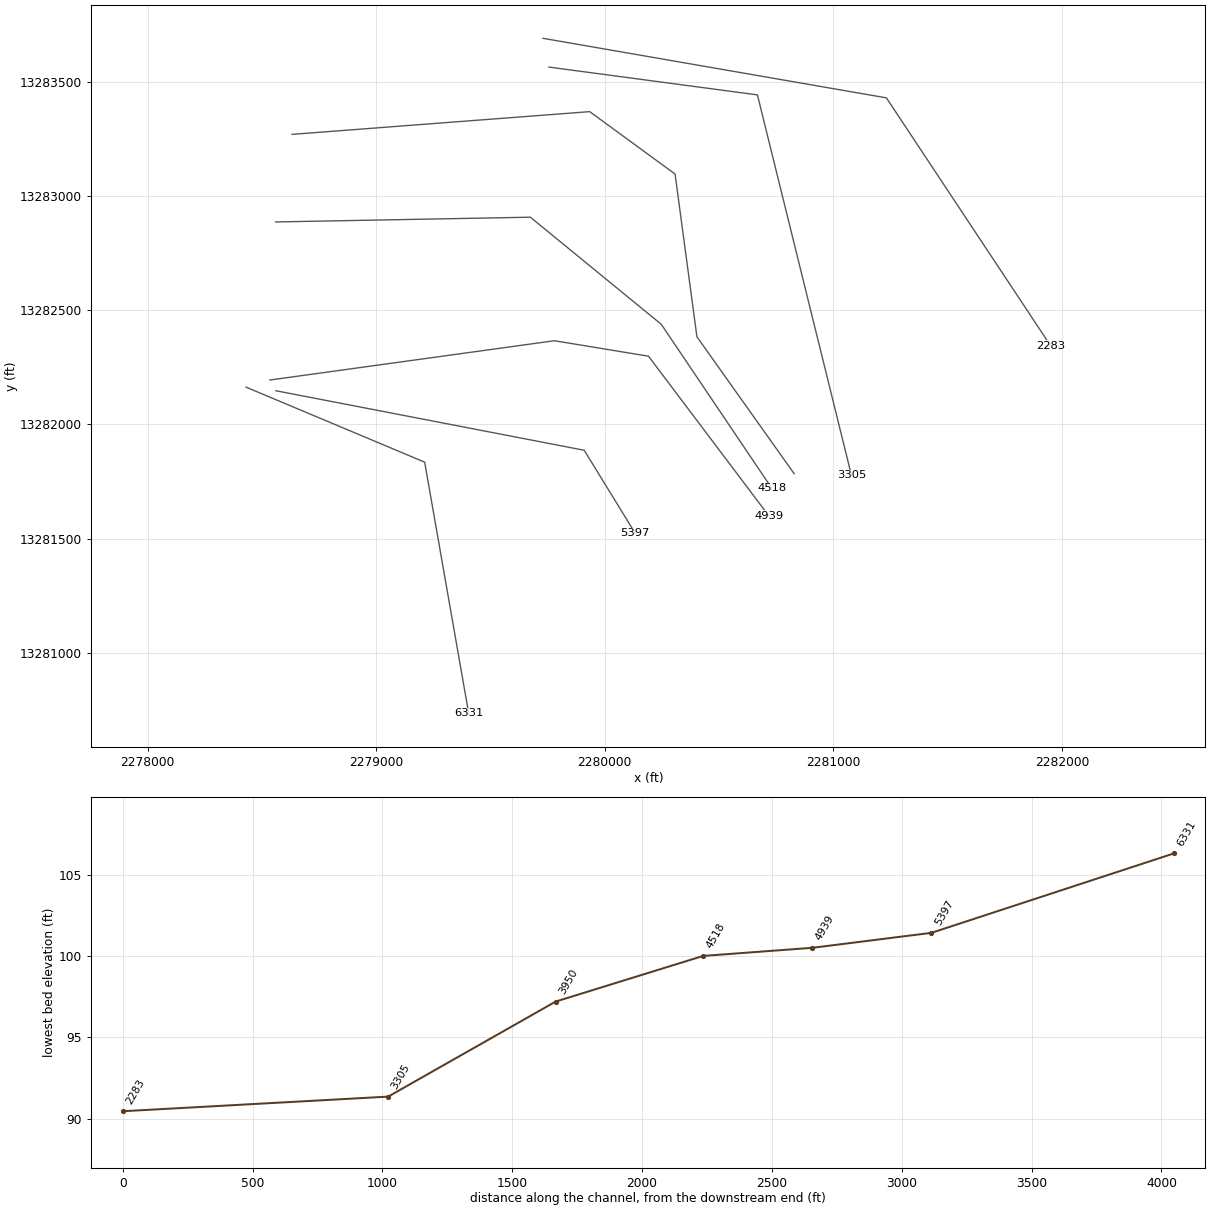
HEC-RAS study GILDEN CREEK.prj: GILDEN CREEK Base Level Engineering

--- GILDEN CREEK.g01 (geometry) --- (continued)

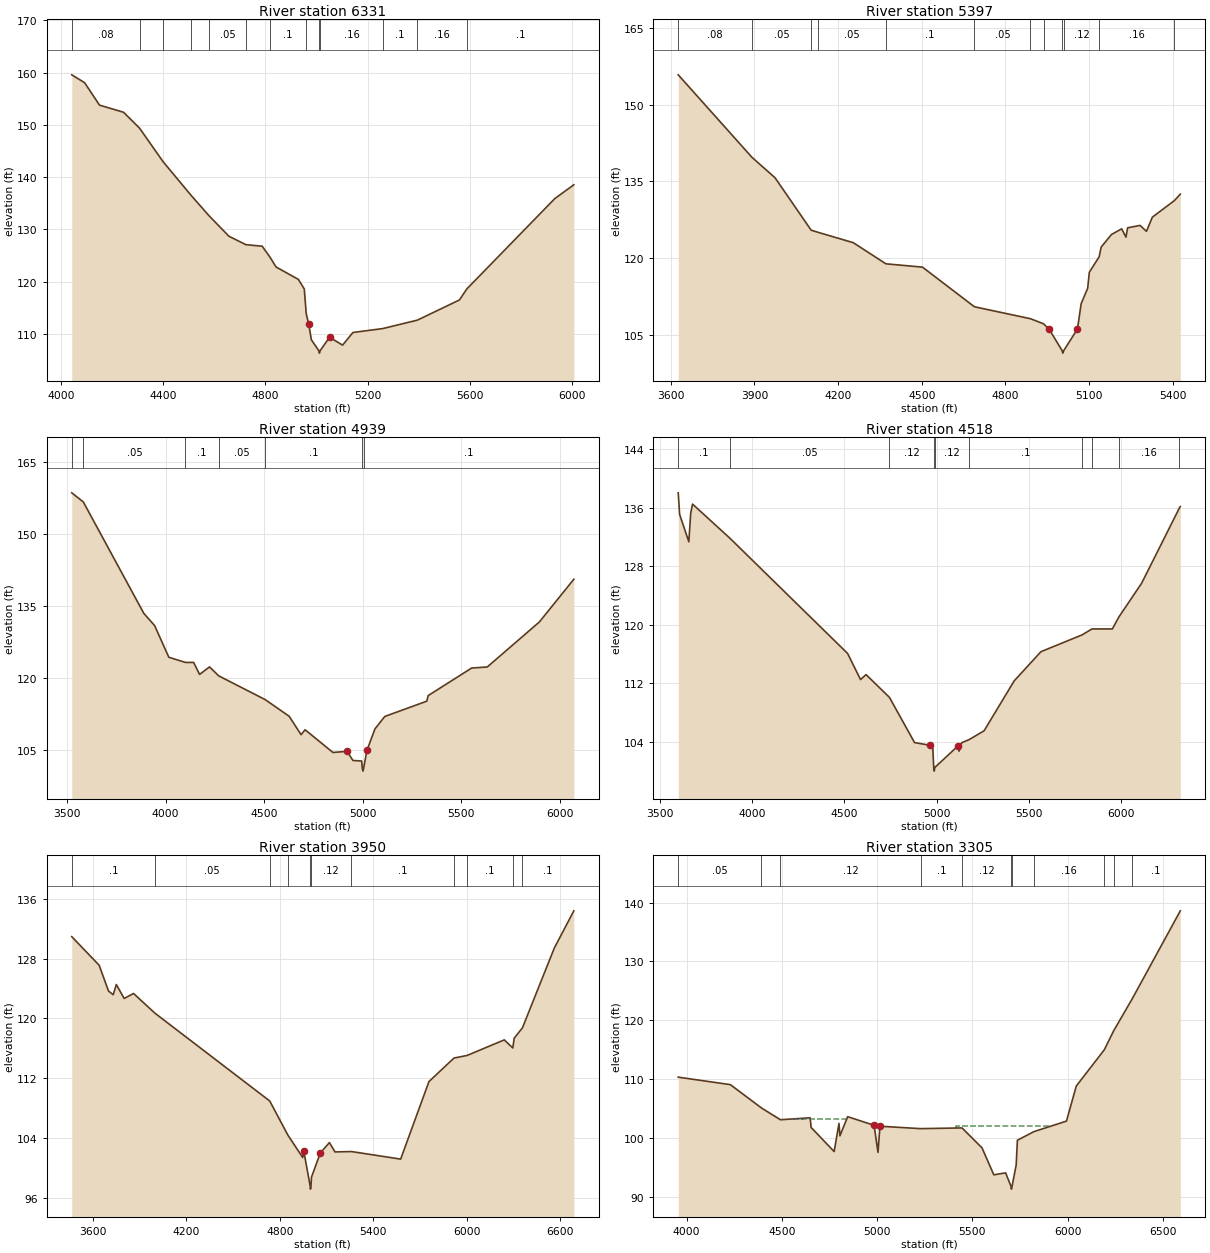
Type RM Length L Ch R = 1 ,6331    ,934,934,934
BEGIN DESCRIPTION:
GILDEN CREEK 82.0
END DESCRIPTION:
XS GIS Cut Line= 3
      2278431.22     13282163.22      2279212.48     13281835.09
      2279405.19     13280736.13
#Sta/Elev= 30
  4042.8  159.58  4092.9  158.08  4151.3  153.78  4245.1  152.42  4307.8  149.38
    4400  142.95  4507.9   136.6  4579.4  132.62  4657.2  128.69  4723.5  127.08
  4787.4  126.78  4817.5  124.71  4841.5  122.81    4929  120.42  4951.9   118.6
  4959.5  113.88  4969.6   111.8  4979.7  108.87  5008.3  106.82  5011.1  106.32
  5014.3  106.82  5050.8  109.36  5101.6  107.85  5142.2  110.27  5258.7  111.02
    5394  112.63  5558.4  116.49  5587.8  118.62  5931.4  135.89  6005.9  138.54
#Mann= 13 ,-1 , 0
  4042.8     .08       0  4307.8      .1       0    4400     .05       0
  4507.9     .08       0  4579.4     .05       0  4723.5     .08       0
  4817.5      .1       0  4959.5     .16       0  5008.3     .07       0
  5014.3     .16       0  5258.7      .1       0    5394     .16       0
  5587.8      .1       0
Bank Sta=4969.6,5050.8
XS Rating Curve= 0 ,0
Exp/Cntr=0.3,0.1

Type RM Length L Ch R = 1 ,5397    ,458,458,458
BEGIN DESCRIPTION:
GILDEN CREEK 3.0
END DESCRIPTION:
XS GIS Cut Line= 3
      2278561.48     13282147.58      2279910.39     13281887.18
      2280133.52     13281523.95
#Sta/Elev= 30
  3626.7  155.86    3891  139.73  3973.8  135.73  4103.2  125.48  4128.6  125.05
  4254.3  123.03  4371.2   118.9  4502.4  118.25  4688.5   110.5  4889.5  108.16
  4936.4  107.17  4957.1  106.07  5002.9  101.93  5005.6  101.43  5008.9  101.93
    5058  106.14  5071.3   111.1  5094.7  114.13  5100.6  117.24  5135.9  120.28
  5143.1  122.17  5179.9  124.63  5216.6  125.74    5232  124.12  5237.9  125.94
  5282.6  126.41  5305.4  125.25  5326.7  128.03  5405.5  131.26  5426.8  132.52
#Mann= 12 ,-1 , 0
  3626.7     .08       0    3891     .05       0  4103.2     .08       0
  4128.6     .05       0  4371.2      .1       0  4688.5     .05       0
  4889.5      .1       0  4936.4     .12       0  5002.9     .07       0
  5008.9     .12       0  5135.9     .16       0  5405.5      .1       0
Bank Sta=4957.1,5058
XS Rating Curve= 0 ,0
Exp/Cntr=0.3,0.1

Type RM Length L Ch R = 1 ,4939    ,421,421,421
BEGIN DESCRIPTION:
GILDEN CREEK 2.0
END DESCRIPTION:
XS GIS Cut Line= 4
       2278535.4     13282194.47      2279780.18     13282366.34
      2280191.64     13282298.63      2280717.24     13281601.31
#Sta/Elev= 30
  3523.7  158.55  3582.4  156.64  3889.5  133.39  3944.1  130.86    4016  124.26
  4100.3  123.18  4141.8  123.18  4172.1  120.68  4222.6  122.25    4269  120.38
  4504.7  115.43  4626.4  111.95  4686.9  108.11  4707.1  109.14  4848.7   104.4
  4919.7  104.64  4950.1  102.73  4994.2  102.62  4997.8  101.01  5000.5  100.51
  5003.8  101.01    5021  104.84  5061.6  109.31  5111.5  111.91  5324.7   115.1
  5331.5  116.26  5552.2  122.01  5631.3  122.23  5895.7  131.62  6070.5  140.53
#Mann= 7 ,-1 , 0
  3523.7     .08       0  3582.4     .05       0  4100.3      .1       0
    4269     .05       0  4504.7      .1       0  4997.8     .07       0
  5003.8      .1       0
Bank Sta=4919.7,5021
XS Rating Curve= 0 ,0
Exp/Cntr=0.3,0.1

Type RM Length L Ch R = 1 ,4518    ,568,568,568
BEGIN DESCRIPTION:
GILDEN CREEK 85.0
END DESCRIPTION:
XS GIS Cut Line= 4
      2278560.22     13282885.95      2279674.79     13282906.78
      2280247.71     13282438.03      2280731.22     13281720.56
#Sta/Elev= 30
  3599.3  138.04  3606.8   135.1  3656.8  131.35  3666.8  135.24  3676.8   136.5
    3880  131.82    4517  116.09    4587  112.52    4617   113.2  4743.9  110.08
  4879.6  103.91  4964.3  103.54  4978.6  103.15  4983.5  100.51  4986.3  100.01
  4989.5  100.51  5114.3  103.44  5120.7  102.74  5135.1  103.89  5174.7  104.31
  5256.4  105.52  5419.4  112.34  5564.3  116.33  5786.7  118.62    5841  119.44
  5951.3  119.44  5987.1  121.09  6110.2   125.7    6315  135.99  6319.5  136.16
#Mann= 10 ,-1 , 0
  3599.3      .1       0    3880     .05       0  4743.9     .12       0
  4983.5     .07       0  4989.5     .12       0  5174.7      .1       0
  5786.7     .16       0    5841      .1       0  5987.1     .16       0
    6315      .1       0
Bank Sta=4964.3,5114.3
XS Rating Curve= 0 ,0
Exp/Cntr=0.3,0.1

Type RM Length L Ch R = 1 ,3950    ,645,645,645
BEGIN DESCRIPTION:
GILDEN CREEK 83.0
END DESCRIPTION:
XS GIS Cut Line= 5
      2278632.61     13283269.12      2279934.34     13283368.58
      2280307.96     13283095.51      2280403.45      13282383.7
      2280828.79     13281784.75
#Sta/Elev= 30
  3465.2  130.93  3640.8  127.11    3701  123.67  3731.1  123.17  3751.1  124.53
  3801.3  122.67  3861.5  123.34  3997.9  120.72  4735.5  108.97  4850.8  104.45
  4946.9  101.42  4953.1  102.35  4994.1    97.7  4996.8    97.2  5000.1    97.7
  5003.3   98.81  5059.8  102.03  5118.3  103.42  5153.8  102.17  5259.6  102.22
  5575.2  101.21  5756.8  111.57  5917.4  114.71  6001.8  115.06    6240  117.14
  6294.6  116.06  6303.5  117.36  6356.6  118.75  6561.1  129.41  6686.3  134.38
#Mann= 11 ,-1 , 0
  3465.2      .1       0  3997.9     .05       0  4735.5      .1       0
  4850.8     .12       0  4994.1     .07       0  5000.1     .12       0
  5259.6      .1       0  5917.4     .12       0  6001.8      .1       0
  6294.6     .16       0  6356.6      .1       0
#XS Ineff= 1 ,-1
 5118.06 5654.31  103.41
Permanent Ineff=
       F
Bank Sta=4953.1,5059.8
XS Rating Curve= 0 ,0
Exp/Cntr=0.3,0.1

Type RM Length L Ch R = 1 ,3305    ,1022,1022,1022
BEGIN DESCRIPTION:
GILDEN CREEK 84.0
END DESCRIPTION:
XS GIS Cut Line= 3
      2279756.67     13283563.35      2280668.17     13283441.82
      2281079.63     13281776.88
#Sta/Elev= 30
  3956.5  110.36    4230  109.09  4393.3  105.13  4492.8  103.13  4648.7  103.46
  4653.8  101.82  4774.7   97.73    4800  102.51  4805.1   100.4  4845.4  103.65
  4984.2  102.19  5004.8   97.59    5015  102.03  5227.9  101.62  5445.7  101.74
  5550.7   98.35  5612.5   93.78  5674.4   94.11  5702.3   91.85    5705   91.35
  5708.3   91.85  5729.8   95.43  5736.2   99.65  5822.8  101.11  5993.7   102.9
  6045.2  108.85  6192.5  115.02  6241.9  118.26  6338.2  123.63  6591.1   138.6
#Mann= 11 ,-1 , 0
  3956.5     .05       0  4393.3      .1       0  4492.8     .12       0
  5227.9      .1       0  5445.7     .12       0  5702.3     .07       0
  5708.3     .12       0  5822.8     .16       0  6192.5      .1       0
  6241.9     .16       0  6338.2      .1       0
#XS Ineff= 2 ,-1
 4561.22 4844.87   103.3 5416.55 5905.79  102.07
Permanent Ineff=
       F       F
Bank Sta=4984.2,5015
XS Rating Curve= 0 ,0
Exp/Cntr=0.3,0.1

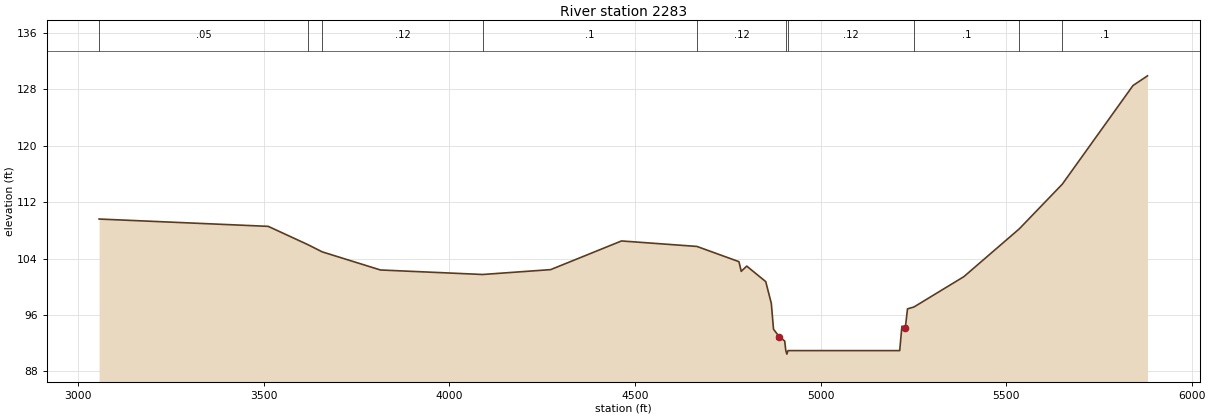
Type RM Length L Ch R = 1 ,2283    ,0,0,0
BEGIN DESCRIPTION:
GILDEN CREEK 1.0
END DESCRIPTION:
XS GIS Cut Line= 3
      2279730.64     13283689.22      2281232.41      13283428.8
      2281950.85     13282344.25
#Sta/Elev= 30
  3055.9  109.62  3511.7  108.58  3618.8  105.98  3657.2  104.96  3814.1  102.39
  4089.7  101.75  4272.7  102.44  4463.7  106.51  4666.9  105.73  4780.1  103.57
  4786.3   102.2  4801.1  102.94  4852.3  100.74  4867.3   97.66  4873.3   93.98
  4888.4   92.94  4903.4   92.31  4906.4   90.95  4909.2   90.45  4912.4   90.95
  5213.3   90.95  5219.3   94.42  5228.3   94.13  5234.3   96.87  5251.7   97.14
  5386.1  101.44  5535.4  108.22  5651.5  114.57  5841.9  128.56    5881  129.94
#Mann= 10 ,-1 , 0
  3055.9     .05       0  3618.8      .1       0  3657.2     .12       0
  4089.7      .1       0  4666.9     .12       0  4906.4     .07       0
  4912.4     .12       0  5251.7      .1       0  5535.4     .12       0
  5651.5      .1       0
Bank Sta=4888.4,5228.3
XS Rating Curve= 0 ,0
Exp/Cntr=0.3,0.1

Chan Stop Cuts=-1
Use User Specified Reach Order=0
Composite Channel Slope=5