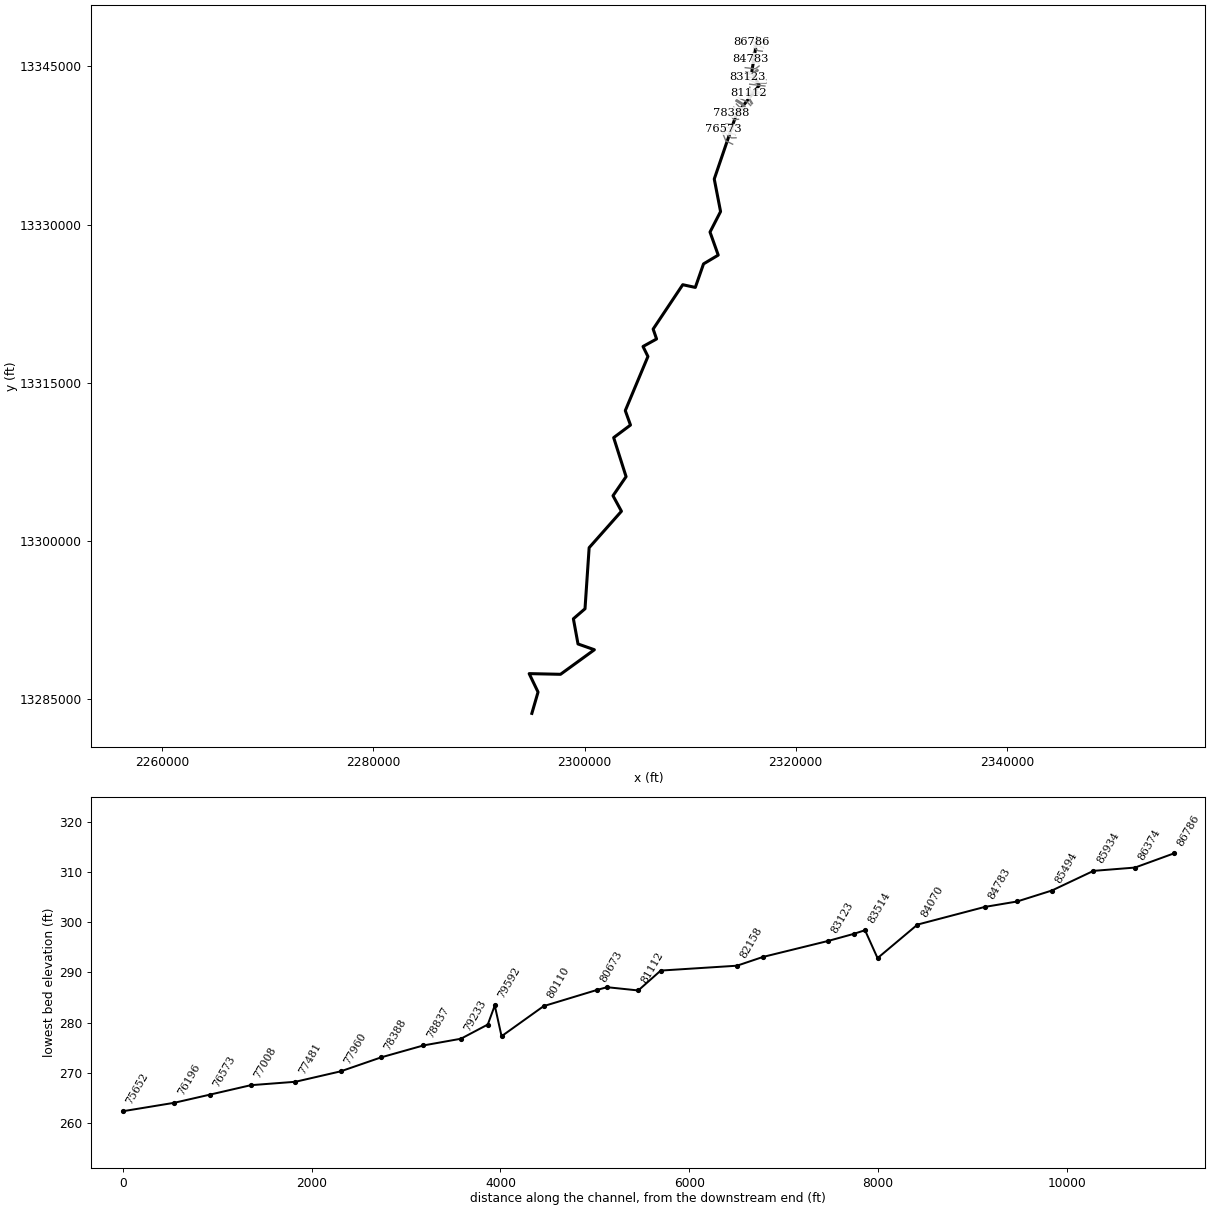
--- LA PARA CREEK.prj (project) ---

Proj Title=LA PARA CREEK Base Level Engineering
Current Plan=p01
Default Exp/Contr=0.3,0.1
English Units
Geom File=g01
Flow File=f01
Plan File=p01
Y Axis Title=Elevation
X Axis Title(PF)=Main Channel Distance
X Axis Title(XS)=Station
BEGIN DESCRIPTION:
LA PARA CREEK
END DESCRIPTION:
DSS Export Rating Curves= 0
DSS Export Rating Curve Sorted= 0
DSS Export Volume Flow Curves= 0
DXF OffsetX= 0
DXF OffsetY= 0
DXF ScaleX= 1
DXF ScaleY= 10

--- LA PARA CREEK.p01 (plan) ---

Plan Title=Multiple Run
Short Identifier=Multiple
Geom File=g01
Flow File=f01
Subcritical Flow
K Sum by GR= 0
Std Step Tol= 0.01
Critical Tol= 0.01
Num of Std Step Trials= 20
Max Error Tol= 0.3
Flow Tol Ratio= 0.001
Split Flow NTrial= 30
Split Flow Tol= 0.02
Split Flow Ratio= 0.02
Log Output Level= 0
Friction Slope Method= 1
Unsteady Friction Slope Method= 2
Unsteady Bridges Friction Slope Method= 1
Parabolic Critical Depth
Global Vel Dist=  1 , 1 , 1
Global Log Level= 0
CheckData=True
Encroach Param= -1, 0, 0, 0
BEGIN DESCRIPTION:
Multiple Run
END DESCRIPTION:

--- LA PARA CREEK.f01 (steady flow) ---

Flow Title=Multiple
Program Version=4.10
Number of Profiles= 7
Profile Names=10-year,25-year,50-year,1pct_min,100-year,1pct_plu,500-year
River Rch & RM=LA PARA CREEK,Reach-1         ,86786
     763    1090    1367    1251    1692    2288    2603
River Rch & RM=LA PARA CREEK,Reach-1         ,83123
    1101    1604    2037    1886    2551    3450    4018
River Rch & RM=LA PARA CREEK,Reach-1         ,82432
    1101    1604    2037    1886    2551    3450    4018
River Rch & RM=LA PARA CREEK,Reach-1         ,81350
    1351    1984    2534    2357    3188    4311    5070
River Rch & RM=LA PARA CREEK,Reach-1         ,77481
    1778    2638    3394    3176    4295    5808    6914
River Rch & RM=LA PARA CREEK,Reach-1         ,77008
    1778    2638    3394    3176    4295    5808    6914
River Rch & RM=LA PARA CREEK,Reach-1         ,71500
    2096    3129    4041    3794    5131    6939    8317
River Rch & RM=LA PARA CREEK,Reach-1         ,70807
    2096    3129    4041    3794    5131    6939    8317
River Rch & RM=LA PARA CREEK,Reach-1         ,69755
    2847    4302    5601    5298    7165    9690   11783
River Rch & RM=LA PARA CREEK,Reach-1         ,68629
    2847    4302    5601    5298    7165    9690   11783
River Rch & RM=LA PARA CREEK,Reach-1         ,66070
    3051    4611    6002    5675    7675   10380   12613
River Rch & RM=LA PARA CREEK,Reach-1         ,62617
    3069    4636    6033    5703    7713   10431   12666
River Rch & RM=LA PARA CREEK,Reach-1         ,60718
    3461    5241    6831    6464    8742   11823   14388
River Rch & RM=LA PARA CREEK,Reach-1         ,60199
    3461    5241    6831    6464    8742   11823   14388
River Rch & RM=LA PARA CREEK,Reach-1         ,59649
    3461    5241    6831    6464    8742   11823   14388
River Rch & RM=LA PARA CREEK,Reach-1         ,54993
    3486    5274    6871    6498    8788   11884   14444
River Rch & RM=LA PARA CREEK,Reach-1         ,51630
    3621    5472    7124    6730    9102   12309   14933
River Rch & RM=LA PARA CREEK,Reach-1         ,44130
    4553    6939    9086    8630   11671   15783   19348
River Rch & RM=LA PARA CREEK,Reach-1         ,43705
    4553    6939    9086    8630   11671   15783   19348
River Rch & RM=LA PARA CREEK,Reach-1         ,42721
    4553    6939    9086    8630   11671   15783   19348
River Rch & RM=LA PARA CREEK,Reach-1         ,40744
    4574    6962    9108    8643   11688   15807   19339
River Rch & RM=LA PARA CREEK,Reach-1         ,33893
    5165    7880   10324    9808   13264   17938   21995
River Rch & RM=LA PARA CREEK,Reach-1         ,27530
    5516    8420   11038   10489   14185   19183   23537
River Rch & RM=LA PARA CREEK,Reach-1         ,26799
    5516    8420   11038   10489   14185   19183   23537
River Rch & RM=LA PARA CREEK,Reach-1         ,17780
    5516    8419   11033   10483   14177   19173   23514
River Rch & RM=LA PARA CREEK,Reach-1         ,13575
    5605    8531   11158   10579   14306   19348   23625
Boundary for River Rch & Prof#=LA PARA CREEK,Reach-1         , 1
Up Type= 0
Dn Type= 3
Dn Slope=0.005
Boundary for River Rch & Prof#=LA PARA CREEK,Reach-1         , 2
Up Type= 0
Dn Type= 3
Dn Slope=0.005
Boundary for River Rch & Prof#=LA PARA CREEK,Reach-1         , 3
Up Type= 0
Dn Type= 3
Dn Slope=0.005
Boundary for River Rch & Prof#=LA PARA CREEK,Reach-1         , 4
Up Type= 0
Dn Type= 3
Dn Slope=0.005
Boundary for River Rch & Prof#=LA PARA CREEK,Reach-1         , 5
Up Type= 0
Dn Type= 3
Dn Slope=0.005
Boundary for River Rch & Prof#=LA PARA CREEK,Reach-1         , 6
Up Type= 0
Dn Type= 3
Dn Slope=0.005
Boundary for River Rch & Prof#=LA PARA CREEK,Reach-1         , 7
Up Type= 0
Dn Type= 3
Dn Slope=0.005
DSS Import GetInterval= 0
DSS Import GetPeak= 0
DSS Import FillOption= 0

--- LA PARA CREEK.g01 (geometry) ---

Geom Title=Existing Conditions
Program Version=4.10

River Reach=LA PARA CREEK   ,Reach-1
Reach XY= 30
      2316360.56     13347667.99       2315852.1     13344540.44
      2316547.78     13343206.94      2314380.32      13340462.3
      2312289.76     13334331.27       2312887.3     13331247.04
      2311888.08     13329302.21      2312665.42     13327117.81
      2311273.16     13326285.98      2310495.31     13324054.22
      2309305.49     13324312.21      2306501.11     13320105.99
      2306825.37     13319167.76      2305540.43     13318455.77
       2306006.7     13317506.81      2303860.95     13312375.52
      2304354.62     13311008.15      2302761.33     13309815.36
      2303936.62     13306116.92      2302697.72     13304306.85
      2303497.72     13302836.86      2300437.92     13299381.87
      2300045.69     13293592.64      2298945.01     13292641.25
      2299383.38      13290254.4      2300934.19     13289708.32
      2297726.65     13287379.09      2294755.68      13287443.5
      2295597.62     13285695.61      2295011.48     13283675.25

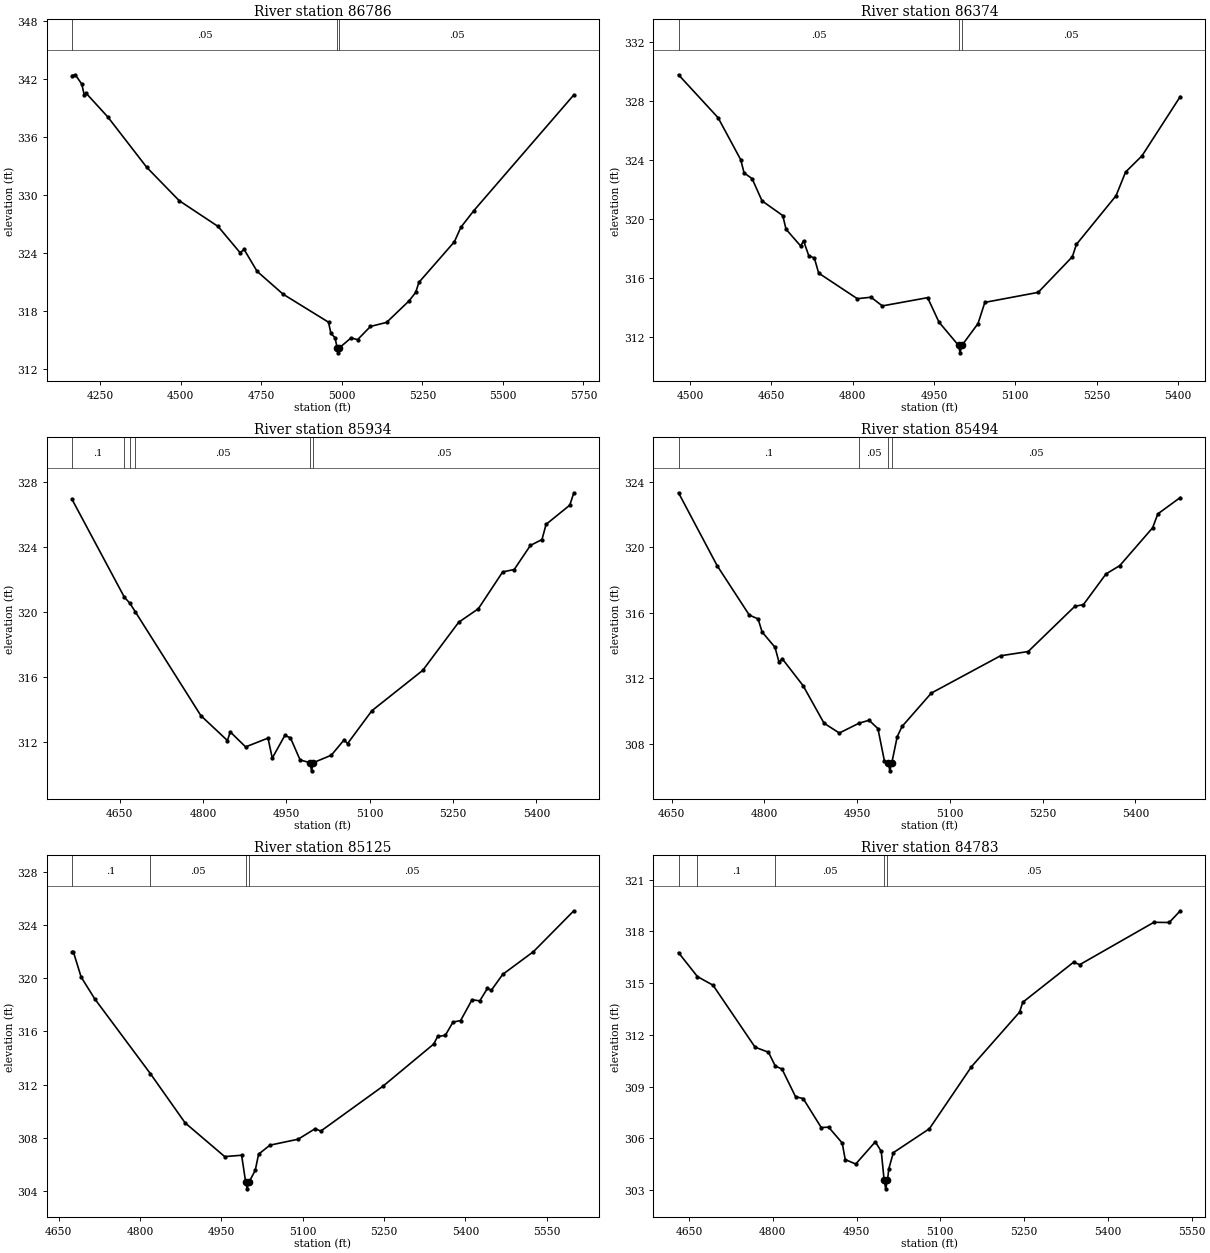
Type RM Length L Ch R = 1 ,86786   ,412,412,412
BEGIN DESCRIPTION:
LA PARA CREEK 157.0
END DESCRIPTION:
XS GIS Cut Line= 3
      2317337.76     13347246.85      2316537.72     13347346.85
      2315787.75     13347296.86
#Sta/Elev= 30
  4162.3   342.4  4172.4  342.48  4192.6  341.51  4200.1  340.37  4205.2   340.6
  4273.2  338.12  4394.1  332.91  4494.9  329.46  4615.8  326.79  4683.9  324.08
  4696.5  324.41  4736.8  322.15  4817.4  319.79  4958.5  316.89    4966  315.73
  4978.6  315.29  4985.6  314.22  4988.4  313.72  4991.6  314.22  5028.7  315.27
  5048.7  315.08  5088.8  316.45  5138.9  316.87  5209.1  319.11  5229.1  319.97
  5239.2  321.01  5349.4  325.21  5369.5  326.71  5409.5  328.42  5720.2   340.4
#Mann= 3 ,-1 , 0
  4162.3     .05       0  4985.6     .03       0  4991.6     .05       0
Bank Sta=4985.6,4991.6
XS Rating Curve= 0 ,0
Exp/Cntr=0.3,0.1

Type RM Length L Ch R = 1 ,86374   ,440,440,440
BEGIN DESCRIPTION:
LA PARA CREEK 156.0
END DESCRIPTION:
XS GIS Cut Line= 3
      2316937.69     13346796.87      2316437.72     13346946.85
      2316037.71     13346996.86
#Sta/Elev= 30
    4479   329.8    4552  326.88  4593.8  324.02  4599.9  323.13  4614.7  322.74
    4633  321.23  4671.2  320.23  4677.3   319.3  4704.3  318.16  4709.5  318.52
  4719.1  317.51  4729.5  317.34  4737.4  316.32  4808.7  314.58  4833.9  314.68
  4854.8  314.09  4938.3  314.65  4959.2  312.99  4995.4   311.4  4998.1   310.9
  5001.4   311.4  5031.2  312.89  5043.8  314.33  5142.1  315.01  5205.1  317.43
  5212.6  318.27  5285.7  321.58  5303.3  323.19  5333.5  324.29  5404.1  328.32
#Mann= 3 ,-1 , 0
    4479     .05       0  4995.4     .03       0  5001.4     .05       0
Bank Sta=4995.4,5001.4
XS Rating Curve= 0 ,0
Exp/Cntr=0.3,0.1

Type RM Length L Ch R = 1 ,85934   ,440,440,440
BEGIN DESCRIPTION:
LA PARA CREEK 155.0
END DESCRIPTION:
XS GIS Cut Line= 3
      2316837.71     13346446.86      2316437.72     13346496.85
      2316037.72     13346796.85
#Sta/Elev= 30
  4564.3   326.9  4658.4   320.9  4668.1  320.54  4678.2     320  4796.1  313.63
  4843.9   312.1    4849  312.63  4876.7  311.71    4917  312.25  4924.6  311.02
  4947.2  312.41  4957.3  312.27  4974.7  310.91  4992.5  310.74  4995.3  310.24
  4998.5  310.74  5030.9   311.2  5053.9  312.14  5060.1  311.91  5103.9  313.93
  5195.5  316.41  5260.1  319.36  5295.5  320.19  5339.3  322.45  5360.1   322.6
  5389.3  324.08  5410.1  324.44  5417.4  325.37  5460.1  326.55  5467.4  327.31
#Mann= 6 ,-1 , 0
  4564.3      .1       0  4658.4     .05       0  4668.1      .1       0
  4678.2     .05       0  4992.5     .03       0  4998.5     .05       0
Bank Sta=4992.5,4998.5
XS Rating Curve= 0 ,0
Exp/Cntr=0.3,0.1

Type RM Length L Ch R = 1 ,85494   ,369,369,369
BEGIN DESCRIPTION:
LA PARA CREEK 154.0
END DESCRIPTION:
XS GIS Cut Line= 3
      2316737.74     13345996.85      2316387.72     13346096.85
      2315987.76     13346296.84
#Sta/Elev= 30
  4661.2  323.32  4723.6  318.87  4775.6  315.85  4789.9  315.61  4796.4  314.81
  4817.2  313.88  4823.7  312.97  4828.9  313.18  4862.7  311.53  4896.5  309.24
  4921.2  308.64    4953  309.24  4969.3  309.42  4983.6  308.91    4994  306.95
  5000.1  306.83  5002.9  306.33  5006.1  306.83  5014.8  308.42  5022.6  309.04
  5069.9  311.08  5181.8  313.36  5226.5  313.62  5301.9  316.38  5315.9  316.49
  5352.3  318.36  5374.6  318.87  5427.7  321.18  5436.1  322.03  5472.4  323.03
#Mann= 4 ,-1 , 0
  4661.2      .1       0    4953     .05       0  5000.1     .03       0
  5006.1     .05       0
Bank Sta=5000.1,5006.1
XS Rating Curve= 0 ,0
Exp/Cntr=0.3,0.1

Type RM Length L Ch R = 1 ,85125   ,342,342,342
BEGIN DESCRIPTION:
LA PARA CREEK 153.0
END DESCRIPTION:
XS GIS Cut Line= 3
      2316637.75     13345646.85      2316008.62     13345831.88
       2315821.9     13346026.38
#Sta/Elev= 30
  4674.5  321.97  4677.1  321.97  4691.2   320.1  4716.2  318.46  4819.1  312.81
    4883  309.11    4956  306.57  4987.2  306.67  4994.7  304.64  4997.4  304.14
  5000.7  304.64  5012.3  305.53  5018.5  306.75  5039.4  307.43  5091.5  307.88
  5122.8  308.67  5133.2  308.49  5247.8  311.87  5341.5  315.05  5348.7  315.62
  5362.8   315.7    5377   316.7  5391.1  316.82  5412.2  318.39  5426.4   318.3
  5440.5  319.24  5447.7   319.1  5468.8   320.3  5525.4  322.01  5599.9  325.09
#Mann= 4 ,-1 , 0
  4674.5      .1       0  4819.1     .05       0  4994.7     .03       0
  5000.7     .05       0
Bank Sta=4994.7,5000.7
XS Rating Curve= 0 ,0
Exp/Cntr=0.3,0.1

Type RM Length L Ch R = 1 ,84783   ,713,713,713
BEGIN DESCRIPTION:
LA PARA CREEK 152.0
END DESCRIPTION:
XS GIS Cut Line= 3
      2316505.11     13345303.25      2315817.65     13345577.54
      2315741.97     13345716.85
#Sta/Elev= 30
    4631  316.77  4664.9  315.38  4692.8  314.88  4768.2  311.28  4792.1  310.99
  4804.3  310.19  4816.4  310.01  4840.6  308.41  4854.3   308.3  4886.6  306.62
  4899.9  306.64  4924.2  305.72  4929.6  304.76  4948.4   304.5  4983.5  305.79
  4994.2  305.23  4999.3  303.56  5002.1  303.06  5005.3  303.56  5007.7  304.23
  5015.8  305.16  5080.4  306.55  5155.7  310.15  5241.9  313.32  5247.6  313.89
  5338.8  316.22  5349.5  316.07  5482.4  318.53  5509.9  318.52  5529.7   319.2
#Mann= 5 ,-1 , 0
    4631     .05       0  4664.9      .1       0  4804.3     .05       0
  4999.3     .03       0  5005.3     .05       0
Bank Sta=4999.3,5005.3
XS Rating Curve= 0 ,0
Exp/Cntr=0.3,0.1

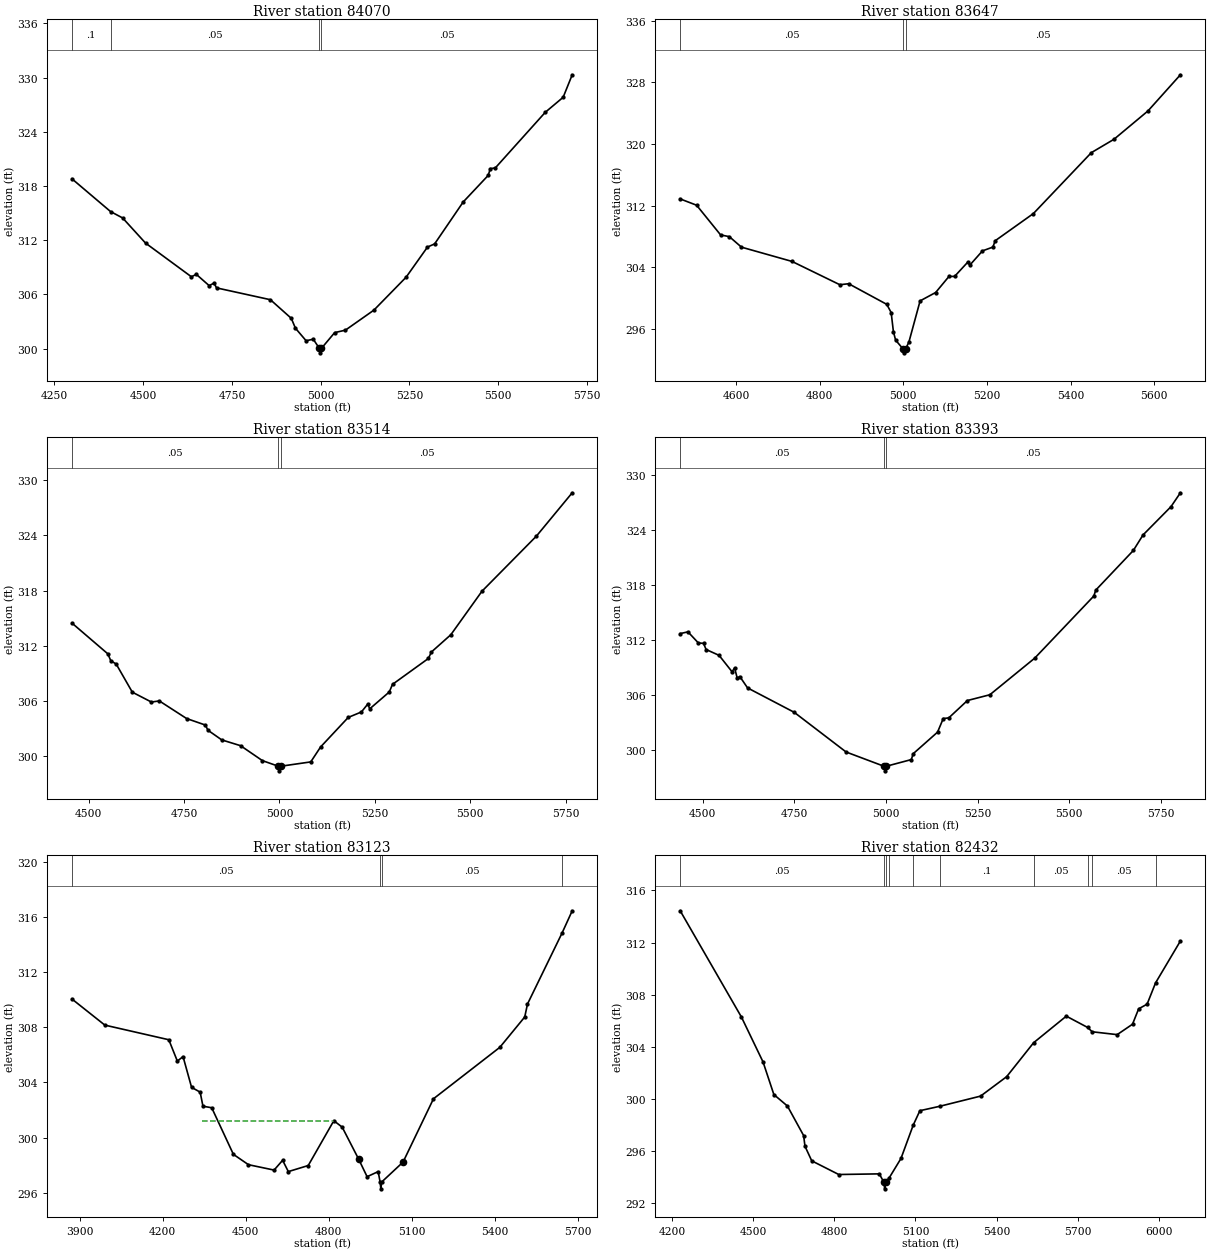
Type RM Length L Ch R = 1 ,84070   ,423,423,423
BEGIN DESCRIPTION:
LA PARA CREEK 151.0
END DESCRIPTION:
XS GIS Cut Line= 3
      2316537.72     13345046.85       2316185.7      13344782.4
       2315222.4     13344886.54
#Sta/Elev= 30
  4299.4   318.8    4408  315.18  4442.1  314.47  4506.6  311.69  4635.8  307.96
  4649.6  308.23  4685.8  306.98  4699.6  307.26  4706.6  306.73  4858.4  305.42
  4917.2  303.36  4928.8  302.27  4958.9  300.88  4979.1  301.05  4996.2  300.04
  4998.9  299.54  5002.2  300.04  5039.4  301.78  5069.6  302.05    5150  304.27
  5240.6  307.91  5300.9  311.25    5321   311.6  5401.5  316.24  5471.9  319.18
  5477.9  319.93    5492  320.01  5632.8  326.17  5683.1  327.83  5708.6  330.32
#Mann= 4 ,-1 , 0
  4299.4      .1       0    4408     .05       0  4996.2     .03       0
  5002.2     .05       0
Bank Sta=4996.2,5002.2
XS Rating Curve= 0 ,0
Exp/Cntr=0.3,0.1

Type RM Length L Ch R = 1 ,83647   ,133,133,133
BEGIN DESCRIPTION:
LA PARA CREEK 150.0
END DESCRIPTION:
XS GIS Cut Line= 4
      2316369.06     13344720.75      2316013.16     13344451.65
      2315813.51     13344386.54       2315281.2     13344477.43
#Sta/Elev= 30
  4466.4  312.86  4505.7  312.04  4563.1  308.18  4583.9  307.96    4613  306.59
  4733.7  304.74  4848.2  301.71  4869.3  301.84  4960.4  299.16  4970.9   298.1
  4976.3  295.61  4981.6  294.51  4999.5  293.36  5002.2  292.86  5005.5  293.36
  5013.5  294.29  5040.1  299.61  5077.3   300.7  5109.2  302.79  5122.6  302.79
    5154  304.64  5159.1  304.26  5189.3  306.11  5214.1   306.6  5219.8  307.43
  5311.1  310.96  5449.6  318.87  5503.8  320.61    5585  324.29  5662.6  328.99
#Mann= 3 ,-1 , 0
  4466.4     .05       0  4999.5     .03       0  5005.5     .05       0
Bank Sta=4999.5,5005.5
XS Rating Curve= 0 ,0
Exp/Cntr=0.3,0.1

Type RM Length L Ch R = 1 ,83514   ,121,121,121
BEGIN DESCRIPTION:
Mapping XS 1461fbab
END DESCRIPTION:
XS GIS Cut Line= 4
      2316427.64     13344659.96      2316041.37     13344327.95
      2315902.48     13344297.57      2315255.76     13344425.61
#Sta/Elev= 30
  4456.3  314.46  4550.3  311.12  4557.9  310.38  4572.2  310.01  4614.4  306.96
  4664.4  305.89  4685.2  306.01  4756.6   304.1  4805.9  303.39  4812.5  302.83
  4848.7  301.78  4898.1  301.15  4955.2  299.53  4997.1  298.92  4999.8  298.42
  5003.1  298.92    5082  299.39  5107.7  301.01  5180.2  304.22  5214.6  304.81
  5231.4  305.67  5236.5  305.15  5287.7  306.98  5296.2  307.81  5390.2  310.62
  5398.1  311.32  5449.1   313.2  5530.6  317.92  5673.4  323.91  5767.1  328.61
#Mann= 3 ,-1 , 0
  4456.3     .05       0  4997.1     .03       0  5003.1     .05       0
Bank Sta=4997.1,5003.1
XS Rating Curve= 0 ,0
Exp/Cntr=0.3,0.1

Type RM Length L Ch R = 1 ,83393   ,270,270,270
BEGIN DESCRIPTION:
LA PARA CREEK 149.0
END DESCRIPTION:
XS GIS Cut Line= 4
      2316437.74     13344596.88      2316093.46     13344247.65
      2315939.38     13344208.59      2315237.72     13344346.85
#Sta/Elev= 30
  4438.8  312.69    4460  312.88  4488.3  311.67  4502.5  311.62  4509.5  310.95
  4544.9  310.31  4580.2  308.52  4587.3  308.93  4594.4  307.81  4601.5  307.99
  4622.6  306.75  4749.9  304.08  4891.4  299.74  4994.8  298.18  4997.6  297.68
  5000.8  298.18  5069.2  298.91  5074.6  299.56  5140.8  301.91  5156.4   303.4
  5171.4  303.47  5222.3  305.37  5283.5     306  5405.8     310  5567.2   316.8
  5572.3  317.44  5674.9  321.78  5701.4  323.48  5777.6  326.57  5803.3  328.09
#Mann= 3 ,-1 , 0
  4438.8     .05       0  4994.8     .03       0  5000.8     .05       0
Bank Sta=4994.8,5000.8
XS Rating Curve= 0 ,0
Exp/Cntr=0.3,0.1

Type RM Length L Ch R = 1 ,83123   ,691,691,691
BEGIN DESCRIPTION:
LA PARA CREEK 148.0
END DESCRIPTION:
XS GIS Cut Line= 3
      2317187.96     13343743.78      2316259.42     13343969.01
      2315406.09     13343981.63
#Sta/Elev= 30
  3871.9  310.04  3990.7  308.15    4222  307.09  4252.9  305.54  4273.5  305.87
  4304.3  303.64  4335.4  303.29  4345.5  302.27  4377.2  302.16  4455.6  298.78
  4510.1  298.03  4602.7  297.64  4633.6  298.35  4654.2  297.53  4726.2  297.97
  4818.8  301.22  4849.1  300.75  4909.1  298.41  4939.1  297.16  4979.1  297.53
  4986.1  296.78  4988.8  296.28  4992.1  296.78  5069.1  298.22  5179.1  302.81
  5419.1  306.54  5509.1  308.74  5519.1  309.68  5644.4  314.84  5680.8  316.44
#Mann= 4 ,-1 , 0
  3871.9     .05       0  4986.1     .03       0  4992.1     .05       0
  5644.4     .08       0
#XS Ineff= 1 ,-1
 4343.75 4816.41  301.22
Permanent Ineff=
       F
Bank Sta=4909.1,5069.1
XS Rating Curve= 0 ,0
Exp/Cntr=0.3,0.1

Type RM Length L Ch R = 1 ,82432   ,274,274,274
BEGIN DESCRIPTION:
LA PARA CREEK 147.0
END DESCRIPTION:
XS GIS Cut Line= 3
      2317194.28     13343421.74      2316197.53     13343443.59
       2315426.4     13343809.66
#Sta/Elev= 30
  4229.6  314.44  4456.2  306.28  4536.2  302.83  4576.2  300.33  4626.3  299.45
  4686.3  297.18  4691.3  296.36  4716.3  295.24  4816.3  294.19  4966.3  294.24
  4983.3  293.59  4986.1  293.09  4989.3  293.59  5001.9   293.9  5046.4  295.42
  5091.9  297.99  5116.4  299.09  5190.2  299.43  5340.9  300.21  5437.3   301.7
  5537.2  304.31  5658.1  306.35  5737.1  305.48  5753.8  305.15  5846.3  304.93
    5903  305.73  5925.7  306.91    5957  307.27  5988.2   308.9  6080.2  312.12
#Mann= 10 ,-1 , 0
  4229.6     .05       0  4983.3     .03       0  4989.3     .05       0
  5001.9     .12       0  5091.9     .05       0  5190.2      .1       0
  5537.2     .05       0  5737.1      .1       0  5753.8     .05       0
  5988.2     .08       0
Bank Sta=4983.3,4989.3
XS Rating Curve= 0 ,0
Exp/Cntr=0.3,0.1

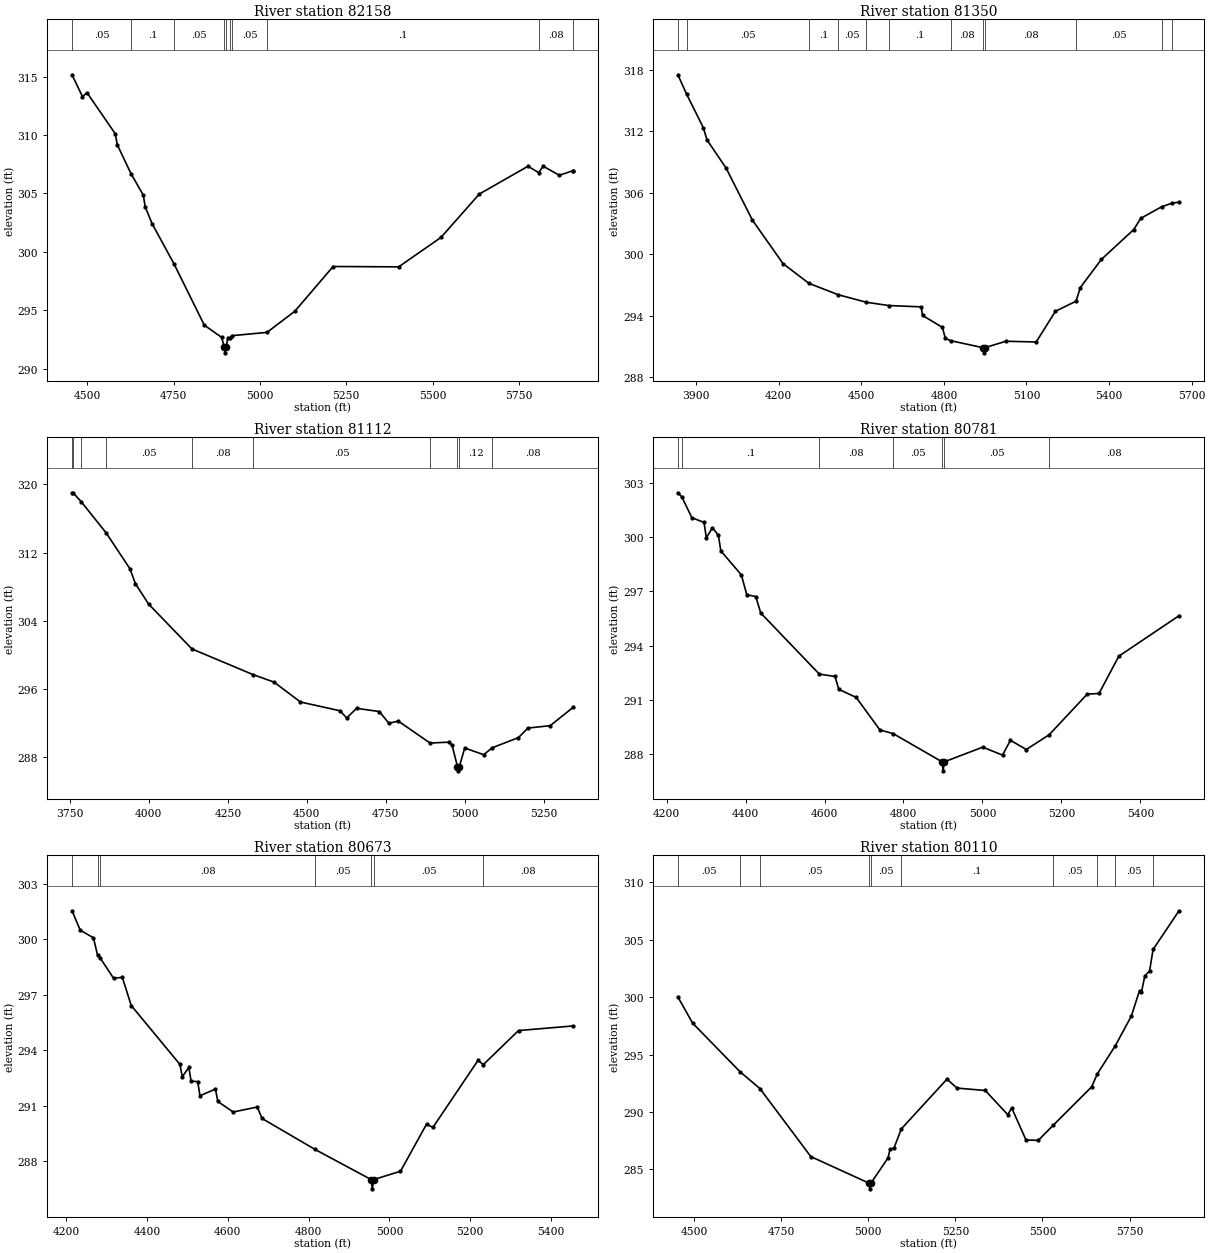
Type RM Length L Ch R = 1 ,82158   ,808,808,808
BEGIN DESCRIPTION:
LA PARA CREEK 146.0
END DESCRIPTION:
XS GIS Cut Line= 2
      2317087.72     13343146.85      2315647.81     13343322.65
#Sta/Elev= 30
  4456.3  315.15  4486.5  313.28  4499.6  313.62  4581.2  310.11  4587.3  309.16
  4626.7   306.7  4662.7  304.84  4667.9  303.86    4688  302.41  4751.7  298.95
  4839.1  293.72  4889.5  292.67  4896.6  291.85  4899.3  291.35  4902.6  291.85
  4907.4  292.66  4913.5  292.58  4919.1  292.82  5020.5   293.1  5101.1  294.91
  5211.9  298.74  5401.7  298.71  5524.2  301.23    5635  304.94    5776  307.32
  5807.3  306.77  5819.6  307.33  5866.7  306.55  5906.6  306.94  5906.9  306.94
#Mann= 10 ,-1 , 0
  4456.3     .05       0  4626.7      .1       0  4751.7     .05       0
  4896.6     .03       0  4902.6     .05       0  4913.5     .12       0
  4919.1     .05       0  5020.5      .1       0  5807.3     .08       0
  5906.6      .1       0
Bank Sta=4896.6,4902.6
XS Rating Curve= 0 ,0
Exp/Cntr=0.3,0.1

Type RM Length L Ch R = 1 ,81350   ,238,238,238
BEGIN DESCRIPTION:
LA PARA CREEK 145.0
END DESCRIPTION:
XS GIS Cut Line= 4
      2317120.52     13342419.13      2316156.97     13342657.85
      2315705.58     13342666.53       2315653.5     13343039.76
#Sta/Elev= 30
  3833.2  317.53  3865.4  315.62  3925.7  312.37  3939.1  311.17  4008.5  308.42
  4103.9  303.35  4215.5  299.09  4309.1  297.17  4416.3  296.05  4518.2  295.32
  4598.9     295  4717.4  294.87  4722.5  294.03  4794.2  292.87  4805.3  291.79
    4824  291.57  4942.2  290.88  4944.9  290.38  4948.2  290.88  5025.2  291.51
  5135.2  291.44  5205.2  294.44    5280  295.42  5295.4  296.75    5372   299.5
  5489.7  302.42    5515  303.51  5590.8  304.64  5627.4  304.98  5654.2   305.1
#Mann= 12 ,-1 , 0
  3833.2     .08       0  3865.4     .05       0  4309.1      .1       0
  4416.3     .05       0  4518.2     .08       0  4598.9      .1       0
    4824     .08       0  4942.2     .07       0  4948.2     .08       0
    5280     .05       0  5590.8      .1       0  5627.4     .05       0
Bank Sta=4942.2,4948.2
XS Rating Curve= 0 ,0
Exp/Cntr=0.3,0.1

Type RM Length L Ch R = 1 ,81112   ,331,331,331
BEGIN DESCRIPTION:
LA PARA CREEK 144.0
END DESCRIPTION:
XS GIS Cut Line= 3
      2317059.74     13342219.48      2316152.63     13342492.92
      2315514.63     13342471.22
#Sta/Elev= 30
  3757.1  319.02  3761.5  318.97  3785.8  317.99    3865  314.32  3940.3  310.11
  3957.7  308.36  3999.4  305.97  4136.5  300.71  4329.4  297.71  4396.3  296.82
  4479.9  294.49  4605.2  293.46  4626.1  292.61  4657.4  293.75  4729.5  293.37
  4759.5     292  4789.5  292.25  4889.9  289.68  4949.6  289.78  4959.6  289.42
  4976.6  286.92  4979.3  286.42  4982.6  286.92  4999.6   289.1  5059.6  288.31
  5086.3  289.12  5169.7  290.32  5199.7  291.44  5269.8  291.71  5342.9  293.87
#Mann= 10 ,-1 , 0
  3757.1     .08       0  3761.5     .05       0  3785.8     .08       0
    3865     .05       0  4136.5     .08       0  4329.4     .05       0
  4889.9     .12       0  4976.6     .07       0  4982.6     .12       0
  5086.3     .08       0
Bank Sta=4976.6,4982.6
XS Rating Curve= 0 ,0
Exp/Cntr=0.3,0.1

Type RM Length L Ch R = 1 ,80781   ,108,108,108
BEGIN DESCRIPTION:
LA PARA CREEK 143.0
END DESCRIPTION:
XS GIS Cut Line= 4
       2315909.6      13341508.5      2315687.35     13341866.18
      2315652.63     13342446.04      2315385.23     13342435.62
#Sta/Elev= 30
  4228.4  302.45  4238.4  302.23    4264  301.07  4294.7  300.81  4300.6  299.96
    4316  300.52  4331.3  300.09  4337.2  299.24  4389.2  297.91  4403.1  296.81
  4425.8  296.71  4438.4   295.8  4586.8  292.42  4626.7  292.29    4636  291.58
  4680.2  291.13  4740.3  289.33  4773.9  289.13  4897.6  287.57  4900.4  287.07
  4903.6  287.57  5000.8  288.38  5050.9  287.94  5070.9  288.76    5111  288.25
  5168.8  289.06  5265.3  291.31  5295.4  291.35  5345.4  293.41    5498  295.65
#Mann= 7 ,-1 , 0
  4228.4     .05       0  4238.4      .1       0  4586.8     .08       0
  4773.9     .05       0  4897.6     .04       0  4903.6     .05       0
  5168.8     .08       0
Bank Sta=4897.6,4903.6
XS Rating Curve= 0 ,0
Exp/Cntr=0.3,0.1

Type RM Length L Ch R = 1 ,80673   ,563,563,563
BEGIN DESCRIPTION:
Mapping XS cfc1e7a0
END DESCRIPTION:
XS GIS Cut Line= 4
      2315829.71     13341439.09      2315628.32     13341817.57
      2315544.99     13342380.07      2315302.35       13342387.
#Sta/Elev= 30
  4214.8  301.53  4235.1  300.48  4267.8  300.07  4278.1  299.12  4284.1  298.99
  4317.4  297.89  4339.3  297.93  4361.3  296.41  4481.8  293.23  4487.5  292.56
  4503.8  293.07  4509.4  292.33  4525.7   292.3  4531.4  291.54  4569.7   291.9
  4575.4  291.23  4613.6  290.66  4673.1  290.93    4685  290.31  4815.9  288.64
    4955  287.01  4957.7  286.51    4961  287.01  5027.5  287.46  5091.9     290
  5107.8  289.83  5219.4  293.45  5232.5  293.22  5319.5  295.06  5454.9  295.31
#Mann= 7 ,-1 , 0
  4214.8     .08       0  4278.1      .1       0  4284.1     .08       0
  4815.9     .05       0    4955     .03       0    4961     .05       0
  5232.5     .08       0
Bank Sta=4955,4961
XS Rating Curve= 0 ,0
Exp/Cntr=0.3,0.1

Type RM Length L Ch R = 1 ,80110   ,446,446,446
BEGIN DESCRIPTION:
LA PARA CREEK 142.0
END DESCRIPTION:
XS GIS Cut Line= 3
      2315737.72     13341296.86      2315337.72     13341696.85
      2314537.72     13342046.86
#Sta/Elev= 30
  4453.2  300.03  4495.6  297.74  4631.9   293.5  4688.7  292.04    4835  286.11
  5001.7   283.8  5004.5   283.3  5007.7   283.8  5056.7     286  5062.5  286.77
  5073.5  286.83  5094.7  288.52  5225.9  292.86  5254.7  292.08  5335.8  291.87
  5400.5  289.76  5411.8  290.35  5452.8  287.55  5488.2  287.53  5530.5  288.83
    5641  292.18    5658  293.34    5709  295.76  5755.3  298.36  5778.7  300.58
  5784.1  300.41  5793.9  301.86  5807.5  302.28  5817.6  304.16  5892.1  307.53
#Mann= 10 ,-1 , 0
  4453.2     .05       0  4631.9      .1       0  4688.7     .05       0
  5001.7     .03       0  5007.7     .05       0  5094.7      .1       0
  5530.5     .05       0    5658      .1       0    5709     .05       0
  5817.6      .1       0
Bank Sta=5001.7,5007.7
XS Rating Curve= 0 ,0
Exp/Cntr=0.3,0.1

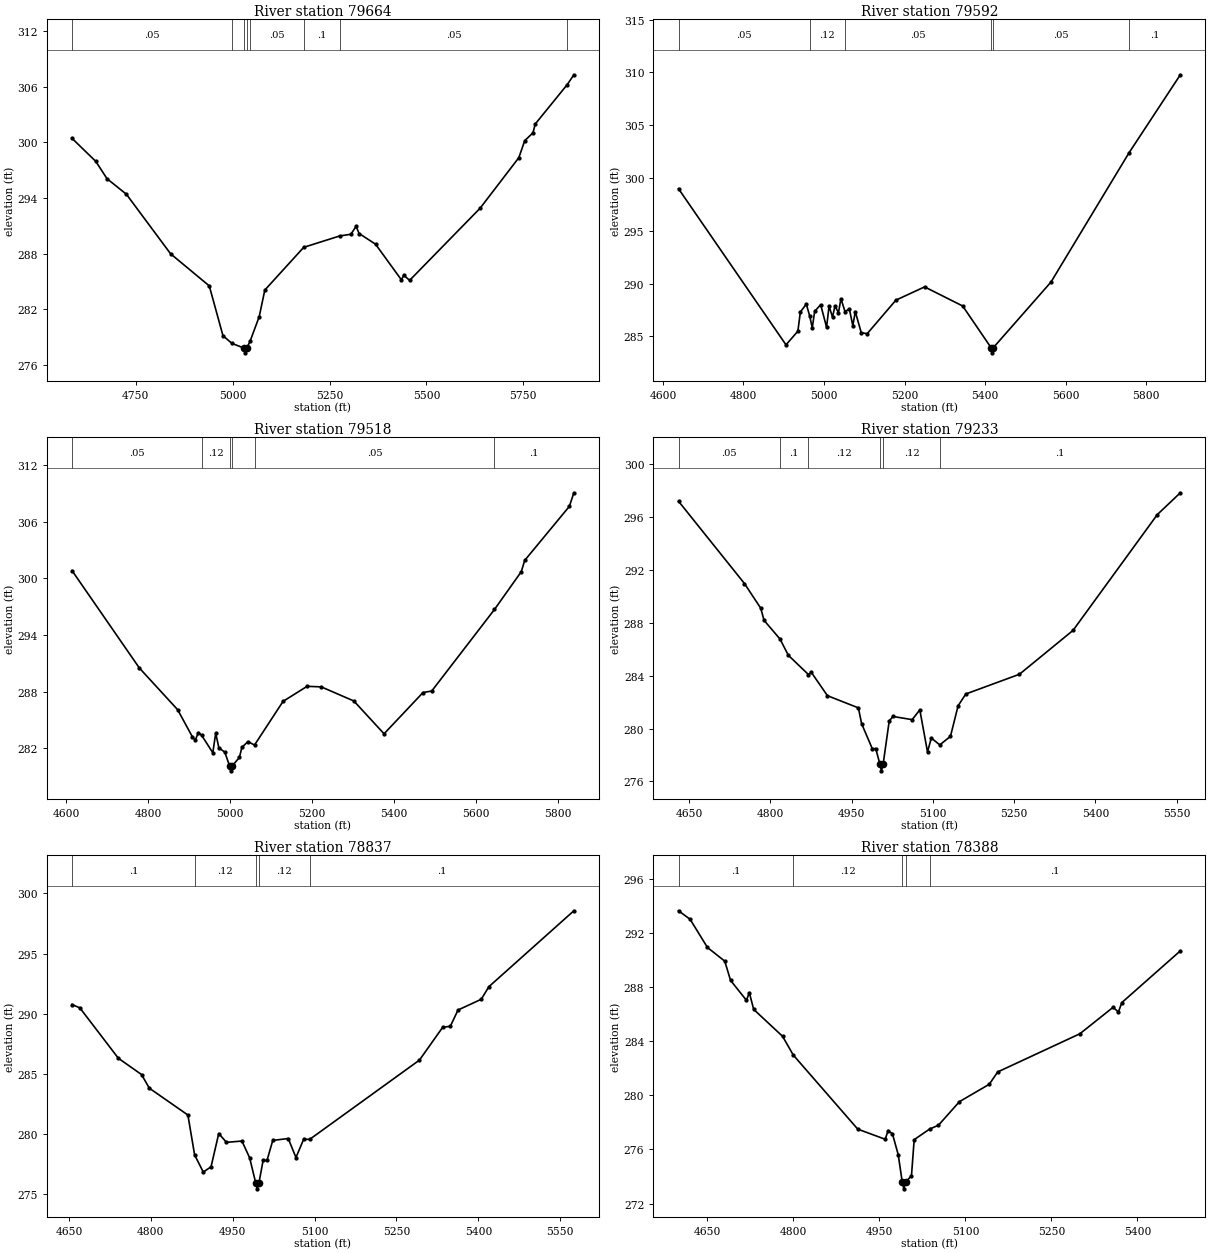
Type RM Length L Ch R = 1 ,79664   ,72,72,72
BEGIN DESCRIPTION:
Mapping XS 90b0dfe2
END DESCRIPTION:
XS GIS Cut Line= 3
      2315367.93     13340980.74      2314961.66     13341512.01
      2314433.88     13341848.82
#Sta/Elev= 30
  4585.4  300.43  4646.6  297.95  4675.6  296.08  4725.5  294.41  4839.7  287.98
  4939.5  284.52  4974.8  279.15  4997.8  278.32  5029.9   277.8  5032.7   277.3
  5035.9   277.8  5044.6  278.53  5068.3   281.2  5082.8  284.07  5183.2  288.68
  5276.4  289.91    5305  290.09  5318.2  290.94  5326.2  290.17  5368.5  289.02
  5435.3  285.17  5441.3  285.67  5456.5  285.12  5638.4   292.9  5738.3  298.35
  5753.5  300.18  5774.7  301.03  5780.8  301.99  5863.4  306.24  5880.3  307.29
#Mann= 8 ,-1 , 0
  4585.4     .05       0  4997.8     .12       0  5029.9     .07       0
  5035.9     .12       0  5044.6     .05       0  5183.2      .1       0
  5276.4     .05       0  5863.4      .1       0
Bank Sta=5029.9,5035.9
XS Rating Curve= 0 ,0
Exp/Cntr=0.3,0.1

Type RM Length L Ch R = 1 ,79592   ,74,74,74
BEGIN DESCRIPTION:
LA PARA CREEK 141.0
END DESCRIPTION:
XS GIS Cut Line= 3
      2315267.24     13340973.79      2314926.93     13341449.51
      2314364.48     13341796.71
#Sta/Elev= 30
  4638.7  298.98  4905.5  284.19    4935  285.48  4941.2   287.3  4955.9  288.05
  4964.4  286.92  4970.7   285.8  4976.8  287.37  4991.6  287.99  5006.3  285.85
  5012.4  287.85    5021  286.82  5027.2  287.87  5035.8  287.23  5041.9  288.56
  5052.1  287.34  5062.8  287.59  5071.4  286.01  5077.6  287.33  5092.3  285.35
    5107  285.24  5178.3  288.42  5249.6  289.68  5344.2  287.87  5414.5  283.93
  5417.3  283.43  5420.5  283.93  5563.5  290.14  5757.3  302.39  5884.6  309.78
#Mann= 6 ,-1 , 0
  4638.7     .05       0  4964.4     .12       0  5052.1     .05       0
  5414.5     .07       0  5420.5     .05       0  5757.3      .1       0
Bank Sta=5414.5,5420.5
XS Rating Curve= 0 ,0
Exp/Cntr=0.3,0.1

Type RM Length L Ch R = 1 ,79518   ,285,285,285
BEGIN DESCRIPTION:
Mapping XS 33328b81
END DESCRIPTION:
XS GIS Cut Line= 3
      2315225.56     13340914.77      2314867.91      13341400.9
       2314338.3     13341722.82
#Sta/Elev= 30
  4614.5   300.8  4778.5  290.51    4872  286.09  4907.5  283.25    4915  282.86
  4922.1  283.68  4930.5  283.38  4957.6  281.54  4964.7  283.62  4972.3  282.07
  4986.9   281.6  4998.6  280.13  5001.3  279.63  5004.6  280.13  5022.4  281.05
  5028.6  282.12  5043.3  282.72  5059.3  282.36  5128.9  286.98  5187.5  288.57
    5222  288.51  5301.4  287.02  5375.1  283.55    5470  287.91  5491.3  288.07
  5644.3   296.7  5709.7   300.7    5718  301.89  5826.8   307.6  5837.8  309.04
#Mann= 6 ,-1 , 0
  4614.5     .05       0  4930.5     .12       0  4998.6     .07       0
  5004.6     .12       0  5059.3     .05       0  5644.3      .1       0
Bank Sta=4998.6,5004.6
XS Rating Curve= 0 ,0
Exp/Cntr=0.3,0.1

Type RM Length L Ch R = 1 ,79233   ,396,396,396
BEGIN DESCRIPTION:
LA PARA CREEK 140.0
END DESCRIPTION:
XS GIS Cut Line= 3
      2315087.74     13340846.84      2314787.72     13341046.85
       2314387.7     13341446.88
#Sta/Elev= 30
  4630.3  297.18    4752  290.96  4782.1  289.09  4788.1  288.18  4817.5  286.77
  4833.1  285.53  4870.1  284.08  4875.2  284.26  4905.2  282.48  4962.3  281.56
  4968.3  280.36  4987.9  278.48  4994.4  278.48    5002   277.3  5004.8   276.8
    5008   277.3  5019.2  280.57  5026.2  280.91  5061.6  280.67  5075.7  281.41
  5089.9  278.23  5096.9  279.28  5112.6  278.76  5132.3  279.41  5146.4  281.72
  5160.6  282.61  5259.6   284.1  5358.6  287.42  5514.1  296.17  5556.6  297.82
#Mann= 6 ,-1 , 0
  4630.3     .05       0  4817.5      .1       0  4870.1     .12       0
    5002     .07       0    5008     .12       0  5112.6      .1       0
Bank Sta=5002,5008
XS Rating Curve= 0 ,0
Exp/Cntr=0.3,0.1

Type RM Length L Ch R = 1 ,78837   ,449,449,449
BEGIN DESCRIPTION:
LA PARA CREEK 139.0
END DESCRIPTION:
XS GIS Cut Line= 3
      2314787.74     13340496.83      2314537.72     13340746.85
       2314137.7     13341146.88
#Sta/Elev= 30
  4655.7  290.77  4669.9   290.5  4740.6  286.31    4783  284.96  4797.2  283.83
  4867.9   281.6  4880.2  278.29  4896.1  276.86  4910.3   277.3  4924.4  280.06
  4938.6  279.33  4966.9  279.44    4981  278.05  4992.1  275.97  4994.9  275.47
  4998.1  275.97  5005.7  277.83  5012.8  277.83  5023.4  279.49  5051.7  279.65
  5065.9  278.07    5080  279.59  5091.1  279.58  5292.1  286.16  5334.6  288.88
  5348.7  288.97  5362.8  290.32  5405.3  291.21  5419.4  292.26    5575  298.56
#Mann= 5 ,-1 , 0
  4655.7      .1       0  4880.2     .12       0  4992.1     .07       0
  4998.1     .12       0  5091.1      .1       0
Bank Sta=4992.1,4998.1
XS Rating Curve= 0 ,0
Exp/Cntr=0.3,0.1

Type RM Length L Ch R = 1 ,78388   ,428,428,428
BEGIN DESCRIPTION:
LA PARA CREEK 138.0
END DESCRIPTION:
XS GIS Cut Line= 3
      2314737.72     13340296.86      2314337.72     13340346.85
      2313937.73     13340596.85
#Sta/Elev= 30
  4599.9  293.62  4620.1  292.99  4650.3  290.91  4680.5   289.9  4690.6  288.48
  4718.3  287.01  4723.3  287.58  4730.9  286.34  4781.3  284.35  4799.9  282.97
  4912.3   277.5  4960.2  276.75  4965.2  277.39  4972.8  277.16  4982.9  275.61
  4989.9  273.59  4992.7  273.09  4995.9  273.59    5006  274.06  5010.7  276.72
  5037.5   277.5  5053.1  277.79  5089.7  279.53  5141.6  280.81  5156.3  281.72
  5299.6  284.54  5357.4  286.49  5366.8  286.15  5372.7  286.84  5474.7  290.66
#Mann= 5 ,-1 , 0
  4599.9      .1       0  4799.9     .12       0  4989.9     .07       0
  4995.9     .12       0  5037.5      .1       0
Bank Sta=4989.9,4995.9
XS Rating Curve= 0 ,0
Exp/Cntr=0.3,0.1

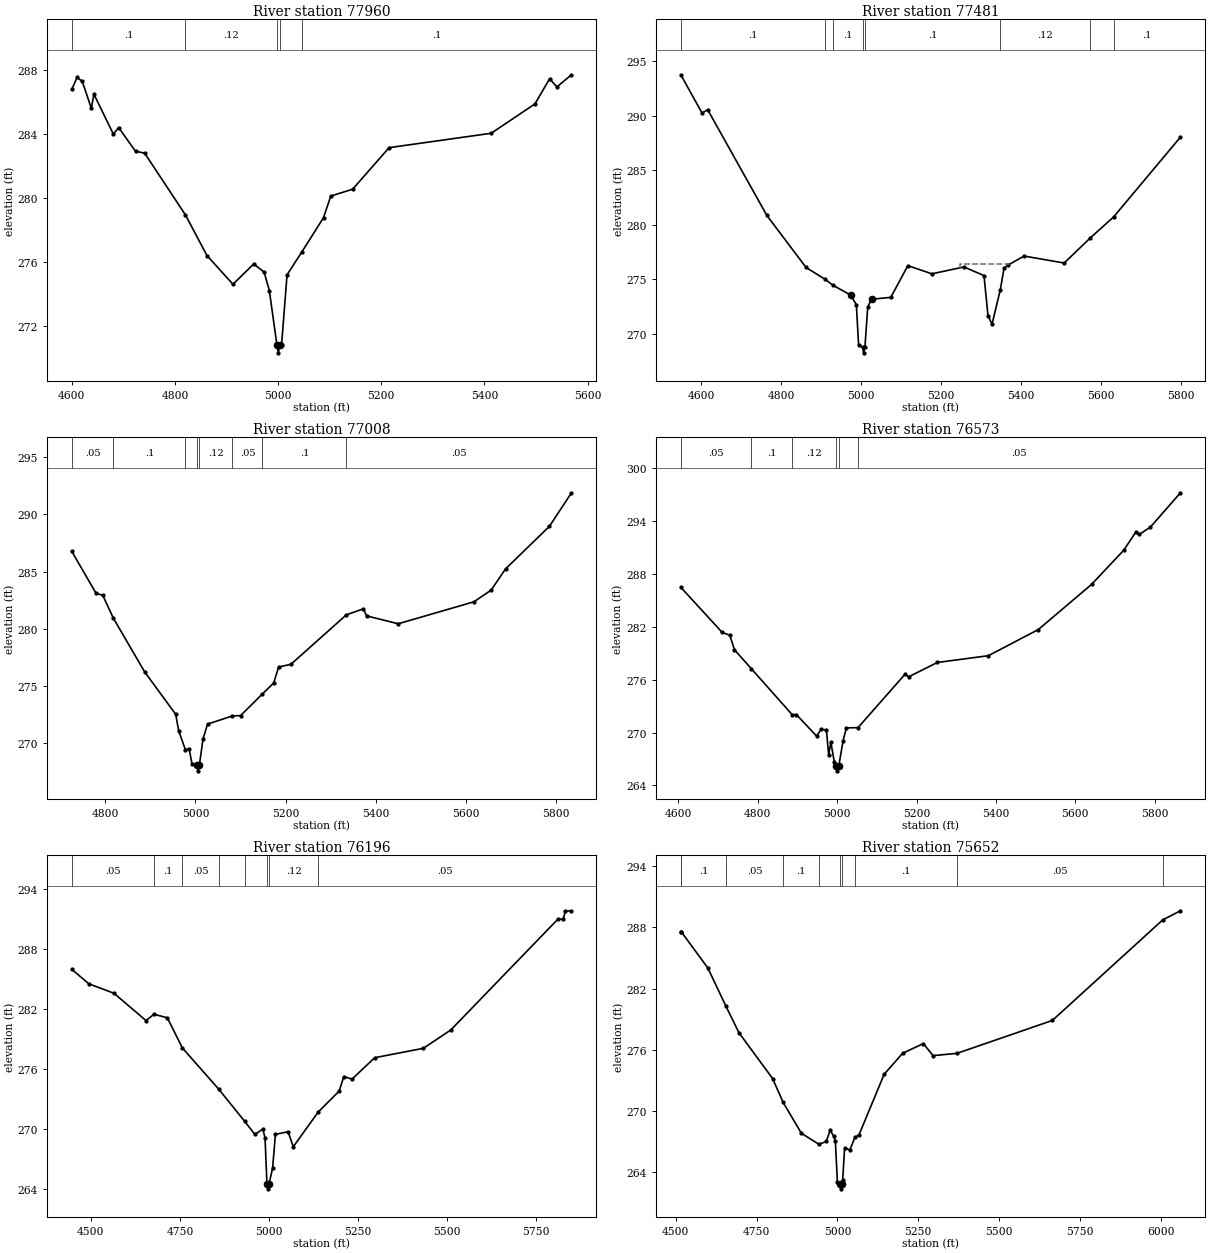
Type RM Length L Ch R = 1 ,77960   ,479,479,479
BEGIN DESCRIPTION:
LA PARA CREEK 137.0
END DESCRIPTION:
XS GIS Cut Line= 3
      2314587.72     13339996.86      2314187.72     13339946.85
      2313787.72     13340346.85
#Sta/Elev= 30
    4600   286.8  4610.1  287.54  4620.2   287.3  4637.8  285.61  4642.8   286.5
  4680.6  283.99  4690.7  284.41  4723.5  282.92  4741.1  282.81  4820.3  278.94
    4862   276.4  4912.4   274.6  4952.7  275.87  4972.9  275.36    4983   274.2
  4997.6  270.81  5000.3  270.31  5003.6  270.81  5006.7  270.81  5017.3  275.19
  5046.3  276.64    5088  278.77  5102.1  280.12  5144.5  280.55  5215.2  283.15
  5413.2  284.05  5498.1  285.89  5526.4  287.46  5540.5  286.95  5568.8  287.71
#Mann= 5 ,-1 , 0
    4600      .1       0  4820.3     .12       0  4997.6     .07       0
  5003.6     .12       0  5046.3      .1       0
Bank Sta=4997.6,5003.6
XS Rating Curve= 0 ,0
Exp/Cntr=0.3,0.1

Type RM Length L Ch R = 1 ,77481   ,473,473,473
BEGIN DESCRIPTION:
LA PARA CREEK 136.0
END DESCRIPTION:
XS GIS Cut Line= 3
      2314587.73     13339296.85      2314187.72     13339496.85
      2313387.71     13339546.86
#Sta/Elev= 30
    4549  293.74  4602.1  290.23  4616.1  290.54  4764.2  280.83  4862.1  276.06
  4909.6  274.98  4929.3  274.43  4973.9  273.52  4987.8  272.64  4993.4  268.94
  5003.2  268.73    5006  268.23  5009.2  268.73  5016.3  272.47  5026.3  273.15
  5073.9  273.32  5116.5  276.23  5176.6  275.48  5256.7  276.11  5306.8  275.32
  5316.9  271.62  5326.9  270.86  5347.6  274.02  5356.9     276    5367  276.28
    5407  277.11  5507.2  276.47    5573  278.79  5630.6  280.69  5797.8  288.02
#Mann= 8 ,-1 , 0
    4549      .1       0  4909.6     .12       0  4929.3      .1       0
  5003.2     .07       0  5009.2      .1       0  5347.6     .12       0
    5573     .05       0  5630.6      .1       0
#XS Ineff= 1 ,-1
 5246.56 5371.25  276.34
Permanent Ineff=
       F
Bank Sta=4973.9,5026.3
XS Rating Curve= 0 ,0
Exp/Cntr=0.3,0.1

Type RM Length L Ch R = 1 ,77008   ,435,435,435
BEGIN DESCRIPTION:
LA PARA CREEK 135.0
END DESCRIPTION:
XS GIS Cut Line= 3
       2314337.7     13338946.86      2314087.72     13339046.85
      2313287.71     13339296.86
#Sta/Elev= 30
  4726.1  286.76  4779.9  283.09  4794.7  282.92  4818.1  280.92  4887.6  276.21
  4956.3   272.5    4963  271.04  4977.8   269.4  4985.9   269.5  4992.6  268.15
  5002.8  268.05  5005.6  267.55  5008.8  268.05  5016.8  270.32  5026.8  271.64
  5082.1  272.36  5100.1  272.39  5148.5  274.28  5173.4  275.24  5184.4  276.64
  5211.7  276.88  5334.5  281.21  5372.5  281.74  5379.3  281.12  5449.5  280.43
  5617.1  282.35  5655.4  283.37  5687.3  285.23  5784.8  288.97  5833.5   291.9
#Mann= 8 ,-1 , 0
  4726.1     .05       0  4818.1      .1       0  4977.8     .12       0
  5002.8     .07       0  5008.8     .12       0  5082.1     .05       0
  5148.5      .1       0  5334.5     .05       0
Bank Sta=5002.8,5008.8
XS Rating Curve= 0 ,0
Exp/Cntr=0.3,0.1

Type RM Length L Ch R = 1 ,76573   ,377,377,377
BEGIN DESCRIPTION:
LA PARA CREEK 134.0
END DESCRIPTION:
XS GIS Cut Line= 3
      2314287.75     13338546.85      2313937.72     13338646.85
      2313137.69     13339046.87
#Sta/Elev= 30
  4606.2  286.49  4710.2  281.38  4729.7  281.05  4741.4   279.4  4783.7  277.26
  4886.7  272.04  4897.4  272.04  4948.1  269.61  4959.8  270.38    4973   270.3
  4978.6  267.47  4984.2  268.91  4992.6  266.72    4998  266.16  5000.7  265.66
    5004  266.16    5015   269.1  5023.3  270.54  5052.5  270.56  5171.5  276.65
  5179.9  276.33  5252.5  277.96  5381.1  278.73  5506.9   281.7  5641.1  286.83
  5722.1  290.71  5752.9   292.8  5761.2  292.49  5789.2  293.33  5864.7  297.22
#Mann= 6 ,-1 , 0
  4606.2     .05       0  4783.7      .1       0  4886.7     .12       0
    4998     .07       0    5004     .12       0  5052.5     .05       0
Bank Sta=4998,5004
XS Rating Curve= 0 ,0
Exp/Cntr=0.3,0.1

Type RM Length L Ch R = 1 ,76196   ,544,544,544
BEGIN DESCRIPTION:
LA PARA CREEK 133.0
END DESCRIPTION:
XS GIS Cut Line= 3
      2314355.78     13338239.62      2313921.73      13338229.2
      2313143.91     13338805.62
#Sta/Elev= 30
  4446.7  285.95  4494.8   284.5  4564.8  283.57  4654.8  280.84  4677.4  281.47
  4714.8  281.11  4756.9  278.11  4859.7  273.96  4931.8  270.78  4960.5  269.47
  4982.7  270.01  4988.9  269.15  4994.3  264.54    4997  264.04  5000.3  264.54
  5010.3  266.14  5018.1  269.48  5053.6  269.74  5068.2  268.24  5138.2  271.71
    5197   273.8  5210.1  275.25  5233.1  274.99  5296.6  277.13  5433.4  278.07
  5510.6  279.91  5811.1  290.97  5825.7  290.95    5832  291.77    5849   291.8
#Mann= 8 ,-1 , 0
  4446.7     .05       0  4677.4      .1       0  4756.9     .05       0
  4859.7      .1       0  4931.8     .12       0  4994.3     .07       0
  5000.3     .12       0  5138.2     .05       0
Bank Sta=4994.3,5000.3
XS Rating Curve= 0 ,0
Exp/Cntr=0.3,0.1

Type RM Length L Ch R = 1 ,75652   ,371,371,371
BEGIN DESCRIPTION:
LA PARA CREEK 132.0
END DESCRIPTION:
XS GIS Cut Line= 3
      2314032.81     13337631.99        2313387.     13337947.95
      2313075.23     13338713.54
#Sta/Elev= 30
  4515.6   287.6  4517.1  287.58  4599.2  284.03  4655.2  280.28  4695.6  277.67
  4799.6  273.18  4832.2  270.84  4888.6  267.81  4943.1  266.73  4965.7  267.01
  4977.7  268.14  4988.2  267.52  4993.8  267.05    5000  262.99  5007.7  262.86
  5010.5  262.36  5013.7  262.86  5016.3  263.19  5022.2  266.32  5038.8  266.19
  5054.1  267.41  5066.9  267.66  5144.7   273.6  5201.9  275.66  5265.8  276.61
  5295.9  275.43  5369.7  275.65    5665  278.88  6006.2  288.74  6061.2  289.64
#Mann= 10 ,-1 , 0
  4515.6     .05       0  4517.1      .1       0  4655.2     .05       0
  4832.2      .1       0  4943.1     .05       0  5007.7     .03       0
  5013.7     .05       0  5054.1      .1       0  5369.7     .05       0
  6006.2      .1       0
Bank Sta=5007.7,5013.7
XS Rating Curve= 0 ,0
Exp/Cntr=0.3,0.1