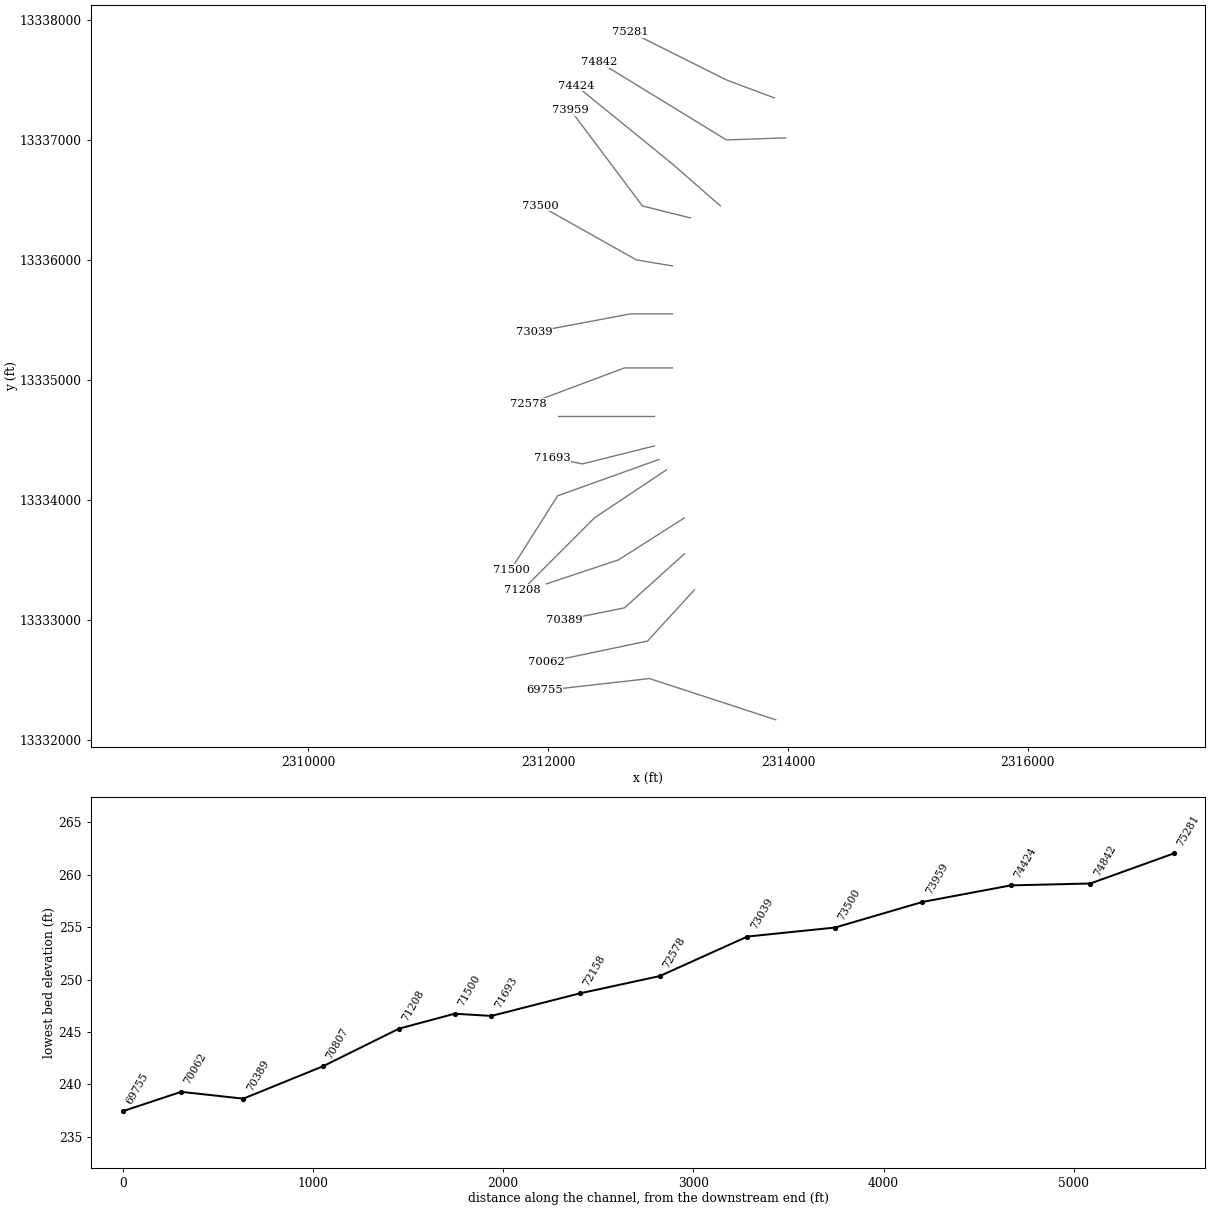
HEC-RAS study LA PARA CREEK.prj: LA PARA CREEK Base Level Engineering

--- LA PARA CREEK.g01 (geometry) --- (continued)

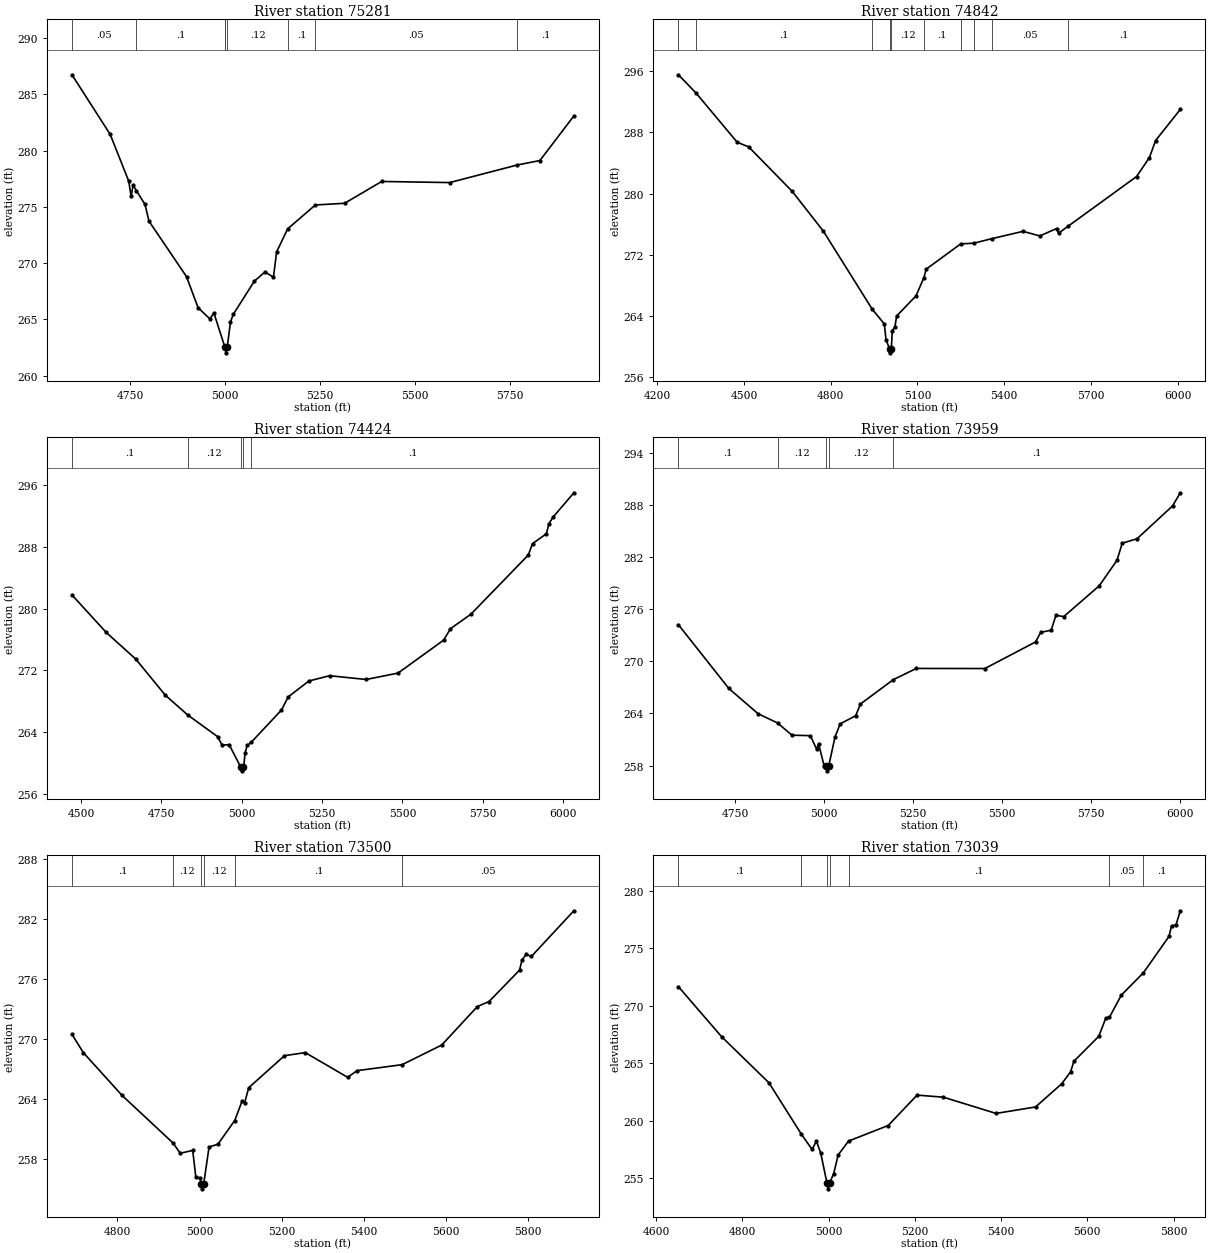
Type RM Length L Ch R = 1 ,75281   ,439,439,439
BEGIN DESCRIPTION:
LA PARA CREEK 131.0
END DESCRIPTION:
XS GIS Cut Line= 3
      2313887.74     13337346.85      2313487.72     13337496.85
      2312687.76     13337896.83
#Sta/Elev= 30
  4596.1  286.74  4696.7  281.45  4745.6  277.29  4751.9  275.93  4757.2  276.93
  4765.8  276.44  4788.4  275.22    4799  273.73  4897.8   268.8  4928.1  266.05
  4959.2  265.05  4969.9  265.57  4998.6  262.56    4999  262.53  5001.7  262.03
    5005  262.53  5013.5  264.76  5020.7  265.44  5076.4   268.4  5104.4  269.22
  5126.7  268.75  5135.1  271.01  5164.2  273.05    5237  275.17    5314  275.32
  5411.8  277.26  5590.7  277.16  5768.2  278.72  5828.3  279.12  5917.7  283.08
#Mann= 8 ,-1 , 0
  4596.1     .05       0  4765.8      .1       0  4998.6     .12       0
    4999     .07       0    5005     .12       0  5164.2      .1       0
    5237     .05       0  5768.2      .1       0
Bank Sta=4999,5005
XS Rating Curve= 0 ,0
Exp/Cntr=0.3,0.1

Type RM Length L Ch R = 1 ,74842   ,418,418,418
BEGIN DESCRIPTION:
LA PARA CREEK 130.0
END DESCRIPTION:
XS GIS Cut Line= 3
      2313980.76     13337013.92      2313487.72     13336996.85
       2312428.7     13337645.85
#Sta/Elev= 30
  4273.6  295.53  4334.3  293.15  4476.8  286.71  4516.8  286.09  4666.9  280.29
  4774.7  275.08  4943.8  264.86  4985.5  262.94  4991.3   260.9  5003.8  259.66
  5006.5  259.16  5009.8  259.66  5013.2  262.07  5022.2  262.56  5028.1  263.98
  5095.3  266.62  5122.4  269.01  5130.5  270.11  5249.6  273.41    5295   273.5
  5356.6  274.09  5465.1  275.05  5523.2  274.45  5581.2  275.42  5587.9  274.81
    5621  275.72  5857.7  282.22  5902.2   284.7  5923.5  286.93    6009     291
#Mann= 10 ,-1 , 0
  4273.6     .05       0  4334.3      .1       0  4943.8     .12       0
  5003.8     .07       0  5009.8     .12       0  5122.4      .1       0
  5249.6     .05       0    5295      .1       0  5356.6     .05       0
    5621      .1       0
Bank Sta=5003.8,5009.8
XS Rating Curve= 0 ,0
Exp/Cntr=0.3,0.1

Type RM Length L Ch R = 1 ,74424   ,465,465,465
BEGIN DESCRIPTION:
LA PARA CREEK 129.0
END DESCRIPTION:
XS GIS Cut Line= 3
      2313437.74     13336446.84      2313037.72     13336796.85
      2312237.72     13337446.85
#Sta/Elev= 30
  4471.4   281.8  4577.7  276.95  4670.3  273.46  4762.3  268.78    4832  266.22
  4924.6  263.42  4938.9  262.31  4960.7  262.38  4996.6  259.48  4999.4  258.98
  5002.6  259.48  5006.1  259.48  5010.1  261.23  5016.6  262.27  5028.9  262.66
  5123.6  266.87  5144.7  268.58  5209.1  270.64  5273.5  271.32  5387.2  270.83
  5486.4  271.66  5628.6  275.94  5649.4  277.41  5713.3   279.3    5892  286.98
  5905.1  288.46  5948.2  289.73  5956.1  291.04  5969.3  291.91  6033.7  295.05
#Mann= 5 ,-1 , 0
  4471.4      .1       0    4832     .12       0  4996.6     .07       0
  5002.6     .12       0  5028.9      .1       0
Bank Sta=4996.6,5002.6
XS Rating Curve= 0 ,0
Exp/Cntr=0.3,0.1

Type RM Length L Ch R = 1 ,73959   ,459,459,459
BEGIN DESCRIPTION:
LA PARA CREEK 128.0
END DESCRIPTION:
XS GIS Cut Line= 3
      2313187.75     13336346.85      2312787.72     13336446.85
      2312187.74     13337246.82
#Sta/Elev= 30
  4589.6  274.21  4731.4  266.88  4813.8  263.97  4868.5  262.91  4909.2   261.5
  4960.7  261.45  4978.7  259.88  4983.9  260.53  4999.4  258.01  5006.2   257.9
    5009   257.4  5012.2   257.9  5030.1  261.27  5044.6   262.8  5088.4  263.74
  5101.9  265.09  5194.2  267.89  5259.2  269.18  5451.9  269.17  5594.6  272.23
  5609.2  273.34  5638.4  273.57  5651.9   275.3  5673.8  275.14  5773.8  278.69
  5823.8  281.63  5838.4  283.59  5880.1   284.1  5980.1  287.88  6001.9  289.39
#Mann= 5 ,-1 , 0
  4589.6      .1       0  4868.5     .12       0  5006.2     .07       0
  5012.2     .12       0  5194.2      .1       0
Bank Sta=5006.2,5012.2
XS Rating Curve= 0 ,0
Exp/Cntr=0.3,0.1

Type RM Length L Ch R = 1 ,73500   ,461,461,461
BEGIN DESCRIPTION:
LA PARA CREEK 127.0
END DESCRIPTION:
XS GIS Cut Line= 3
      2313037.73     13335946.85      2312737.72     13335996.85
      2311937.74     13336446.84
#Sta/Elev= 30
  4689.3  270.45  4717.2  268.61    4811  264.34  4935.6  259.55  4952.9  258.53
  4983.3  258.81  4990.9  256.14  5001.4  256.07  5004.1  255.46  5006.9  254.96
  5010.1  255.46  5023.1  259.15  5044.8  259.44  5085.6  261.81    5104  263.81
  5109.8   263.6  5119.7   265.1  5206.7  268.31  5257.3  268.62  5360.6  266.14
  5383.5  266.81  5493.2  267.41  5589.7  269.38  5676.4  273.24  5704.8  273.74
  5779.1  276.89  5785.1  277.91    5795  278.46  5808.1  278.27  5911.3  282.84
#Mann= 6 ,-1 , 0
  4689.3      .1       0  4935.6     .12       0  5004.1     .07       0
  5010.1     .12       0  5085.6      .1       0  5493.2     .05       0
Bank Sta=5004.1,5010.1
XS Rating Curve= 0 ,0
Exp/Cntr=0.3,0.1

Type RM Length L Ch R = 1 ,73039   ,461,461,461
BEGIN DESCRIPTION:
LA PARA CREEK 126.0
END DESCRIPTION:
XS GIS Cut Line= 3
      2313037.75     13335546.85      2312687.72     13335546.85
      2311887.69     13335396.85
#Sta/Elev= 30
  4651.6  271.66  4751.6  267.32  4861.6  263.31  4936.3  258.87  4961.6  257.52
  4971.6  258.25  4981.6  257.22  4996.1   254.6  4998.9   254.1  5002.1   254.6
  5011.8  255.43    5022  257.04  5046.2  258.25  5138.1   259.6  5205.1  262.24
  5266.2  262.06  5388.2  260.65  5479.8  261.21  5540.9  263.24  5561.2  264.27
  5568.8  265.18  5626.5  267.35  5642.6  268.91  5651.2     269  5679.1  270.94
  5730.1  272.87  5789.3  276.02  5795.2  276.94  5805.4  277.01  5815.6  278.25
#Mann= 7 ,-1 , 0
  4651.6      .1       0  4936.3     .12       0  4996.1     .07       0
  5002.1     .12       0  5046.2      .1       0  5651.2     .05       0
  5730.1      .1       0
Bank Sta=4996.1,5002.1
XS Rating Curve= 0 ,0
Exp/Cntr=0.3,0.1

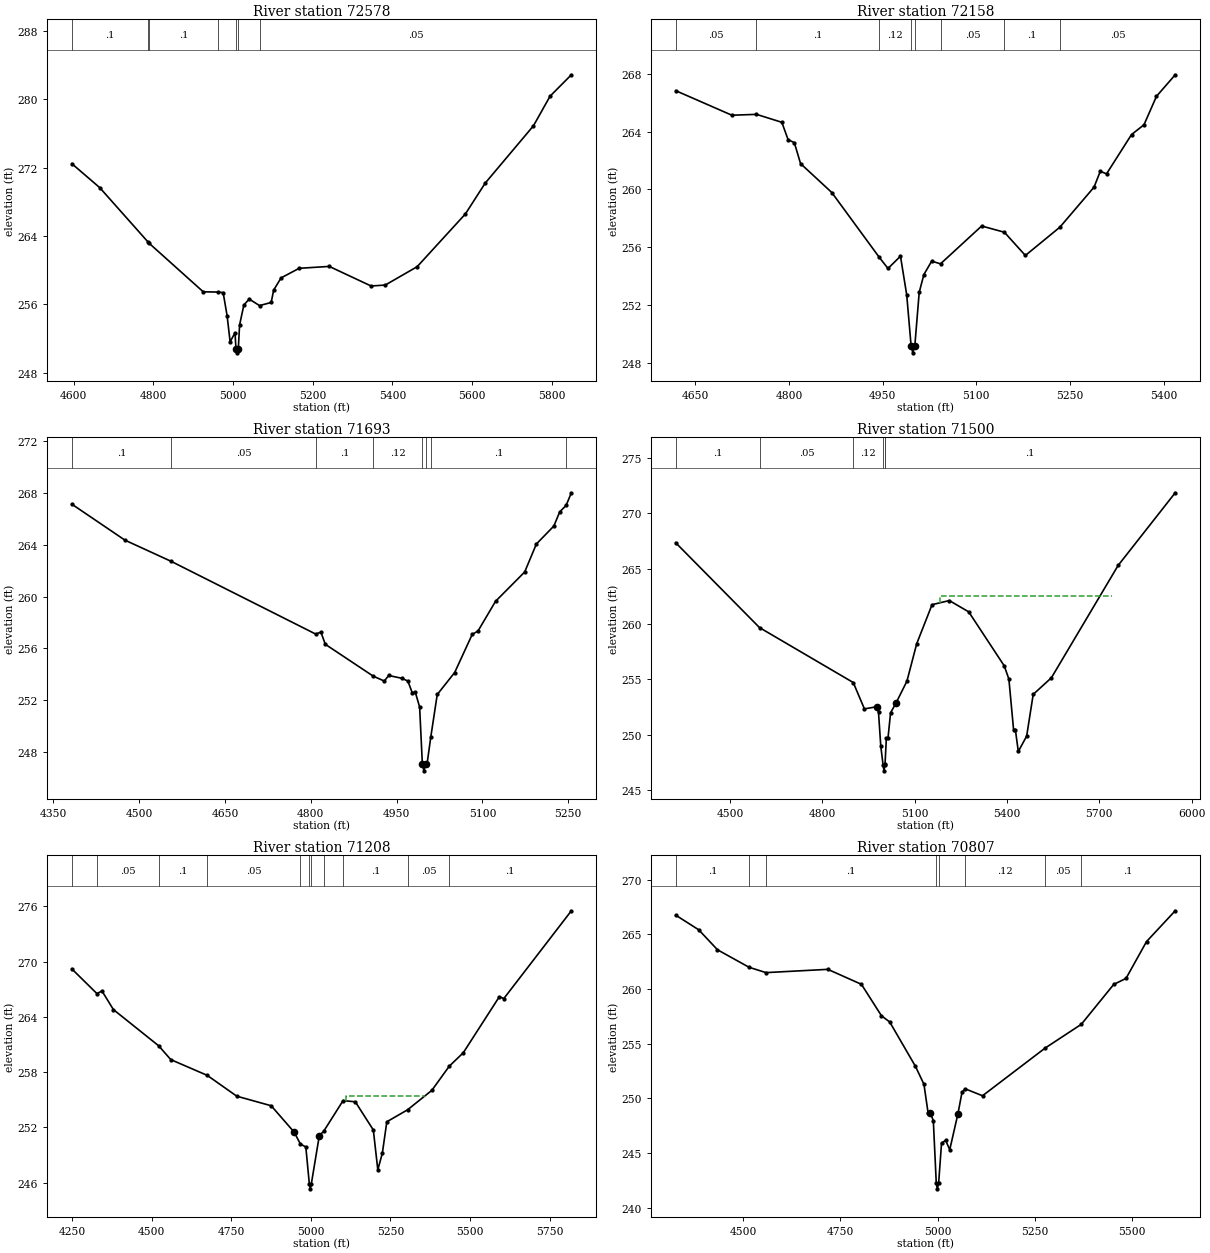
Type RM Length L Ch R = 1 ,72578   ,420,420,420
BEGIN DESCRIPTION:
LA PARA CREEK 125.0
END DESCRIPTION:
XS GIS Cut Line= 3
       2313037.7     13335096.85      2312637.72     13335096.85
      2311837.71     13334796.85
#Sta/Elev= 30
  4595.2  272.46  4665.2  269.66  4786.1  263.32  4788.1   263.2  4925.2  257.47
  4963.4  257.44  4975.2  257.37  4985.2  254.65  4992.7  251.62    5005  252.68
  5007.3  250.83  5010.1  250.33  5013.3  250.83  5016.5   253.6  5027.2  255.93
  5040.6  256.62  5066.5  255.86  5095.8  256.22    5102  257.67  5120.7   259.1
  5166.1  260.22  5241.7  260.44  5346.7  258.15  5382.3  258.26  5462.4  260.41
  5583.5  266.58  5633.3  270.19  5754.4  276.89  5796.2  280.36  5849.6  282.86
#Mann= 7 ,-1 , 0
  4595.2      .1       0  4786.1     .05       0  4788.1      .1       0
  4963.4     .12       0  5007.3     .07       0  5013.3     .12       0
  5066.5     .05       0
Bank Sta=5007.3,5013.3
XS Rating Curve= 0 ,0
Exp/Cntr=0.3,0.1

Type RM Length L Ch R = 1 ,72158   ,465,465,465
BEGIN DESCRIPTION:
LA PARA CREEK 124.0
END DESCRIPTION:
XS GIS Cut Line= 3
      2312887.71     13334696.85      2312487.72     13334696.85
      2312087.71     13334696.85
#Sta/Elev= 30
  4618.5  266.83  4708.5  265.13  4747.9  265.19  4788.5  264.64  4798.5  263.44
  4808.5  263.23  4818.5  261.78  4868.5  259.78  4944.4   255.3  4958.5  254.52
  4978.5  255.37  4988.5  252.69  4995.5  249.18  4998.2  248.68  5001.5  249.18
  5008.5  252.87    5016   254.1  5028.5  255.03  5042.6  254.84  5108.5  257.46
  5144.9  257.03  5178.5  255.42  5233.8  257.38  5288.5  260.15  5298.5  261.25
  5308.5  261.07  5348.5  263.79  5368.5  264.47  5388.5  266.44  5418.5  267.93
#Mann= 8 ,-1 , 0
  4618.5     .05       0  4747.9      .1       0  4944.4     .12       0
  4995.5     .07       0  5001.5     .12       0  5042.6     .05       0
  5144.9      .1       0  5233.8     .05       0
Bank Sta=4995.5,5001.5
XS Rating Curve= 0 ,0
Exp/Cntr=0.3,0.1

Type RM Length L Ch R = 1 ,71693   ,193,193,193
BEGIN DESCRIPTION:
LA PARA CREEK 123.0
END DESCRIPTION:
XS GIS Cut Line= 3
      2312887.71     13334446.85      2312287.72     13334296.85
      2312037.73     13334346.85
#Sta/Elev= 30
  4382.1  267.14  4474.9  264.36  4555.8  262.72  4808.5   257.1  4817.6  257.25
  4825.3  256.31    4909  253.85  4928.4  253.47  4936.1   253.9  4959.3  253.68
  4969.6  253.47  4977.4  252.55  4982.5  252.63  4990.2  251.46    4995  247.03
  4997.7  246.53    5001  247.03  5003.1  247.03  5009.6  249.11    5021  252.43
  5051.5  254.13  5082.1  257.07  5092.3  257.34  5122.9  259.63  5173.9   261.9
  5194.3  264.06  5224.9  265.45  5235.1  266.54  5246.4  267.05  5255.5  268.02
#Mann= 8 ,-1 , 0
  4382.1      .1       0  4555.8     .05       0  4808.5      .1       0
    4909     .12       0    4995     .07       0    5001     .12       0
  5009.6      .1       0  5246.4     .05       0
Bank Sta=4995,5001
XS Rating Curve= 0 ,0
Exp/Cntr=0.3,0.1

Type RM Length L Ch R = 1 ,71500   ,292,292,292
BEGIN DESCRIPTION:
Mapping XS 6548581d
END DESCRIPTION:
XS GIS Cut Line= 3
      2312925.17     13334333.36      2312081.45     13334031.28
      2311692.64     13333416.83
#Sta/Elev= 30
  4323.3  267.33  4595.7  259.67  4900.4  254.71  4936.6  252.33  4977.1  252.53
  4982.4  252.02  4989.8  248.96  4997.4  247.24  5000.1  246.74  5003.4  247.24
  5003.7   247.4  5007.9   249.7  5013.2  249.69  5021.6  251.98  5038.7  252.83
  5074.7  254.83  5106.6  258.22  5156.4  261.74  5212.6  262.11  5275.6  261.09
  5390.9  256.22  5406.1  255.02  5421.4  250.43  5427.3  250.42  5436.7  248.49
  5463.8  249.87  5485.1  253.64  5544.2  255.14  5761.3  265.29  5946.6  271.84
#Mann= 6 ,-1 , 0
  4323.3      .1       0  4595.7     .05       0  4900.4     .12       0
  4997.4     .07       0  5003.4     .12       0  5003.7      .1       0
#XS Ineff= 1 ,-1
 5181.56 5739.84  262.54
Permanent Ineff=
       F
Bank Sta=4977.1,5038.7
XS Rating Curve= 0 ,0
Exp/Cntr=0.3,0.1

Type RM Length L Ch R = 1 ,71208   ,401,401,401
BEGIN DESCRIPTION:
LA PARA CREEK 122.0
END DESCRIPTION:
XS GIS Cut Line= 3
      2312987.73     13334246.86      2312387.72     13333846.85
      2311787.69     13333246.82
#Sta/Elev= 30
  4248.9   269.2  4327.7  266.52  4343.6   266.8  4379.6  264.78  4521.8  260.85
  4559.9  259.35  4674.4  257.64  4767.2  255.38  4875.4  254.34  4947.5  251.48
  4966.9   250.2  4984.2  249.86  4995.3  245.82  4998.1  245.32  5001.3  245.82
  5026.6   251.1  5040.5  251.58  5101.3   254.9  5139.7  254.77  5196.3  251.71
  5210.4  247.39  5224.6  249.18  5238.7   252.6  5303.8   253.9  5380.1  256.01
  5434.8  258.63  5479.1   260.1  5592.3  266.18  5606.4  265.98  5818.6  275.51
#Mann= 11 ,-1 , 0
  4248.9      .1       0  4327.7     .05       0  4521.8      .1       0
  4674.4     .05       0  4966.9     .12       0  4995.3     .07       0
  5001.3     .12       0  5040.5     .05       0  5101.3      .1       0
  5303.8     .05       0  5434.8      .1       0
#XS Ineff= 1 ,-1
 5111.49 5359.53  255.41
Permanent Ineff=
       F
Bank Sta=4947.5,5026.6
XS Rating Curve= 0 ,0
Exp/Cntr=0.3,0.1

Type RM Length L Ch R = 1 ,70807   ,418,418,418
BEGIN DESCRIPTION:
LA PARA CREEK 121.0
END DESCRIPTION:
XS GIS Cut Line= 3
      2313137.69     13333846.83      2312587.72     13333496.85
      2311987.75     13333296.87
#Sta/Elev= 30
  4326.8  266.77    4386  265.43  4434.3   263.6  4515.4     262  4558.9  261.51
  4717.9  261.81  4804.3  260.44  4855.9  257.56  4877.1  256.99  4943.1  252.94
  4965.1  251.29  4975.7  248.68  4981.3  248.68  4989.2  247.96  4996.8  242.22
  4999.5  241.72  5002.8  242.22  5010.3   245.9  5020.8  246.16  5031.4   245.3
  5052.5   248.6    5063  250.57  5071.4  250.87  5115.7  250.24  5276.5   254.6
  5369.7  256.78    5453  260.43  5484.6  260.98  5537.3  264.35  5611.1  267.17
#Mann= 8 ,-1 , 0
  4326.8      .1       0  4515.4     .05       0  4558.9      .1       0
  4996.8     .07       0  5002.8      .1       0  5071.4     .12       0
  5276.5     .05       0  5369.7      .1       0
Bank Sta=4981.3,5052.5
XS Rating Curve= 0 ,0
Exp/Cntr=0.3,0.1

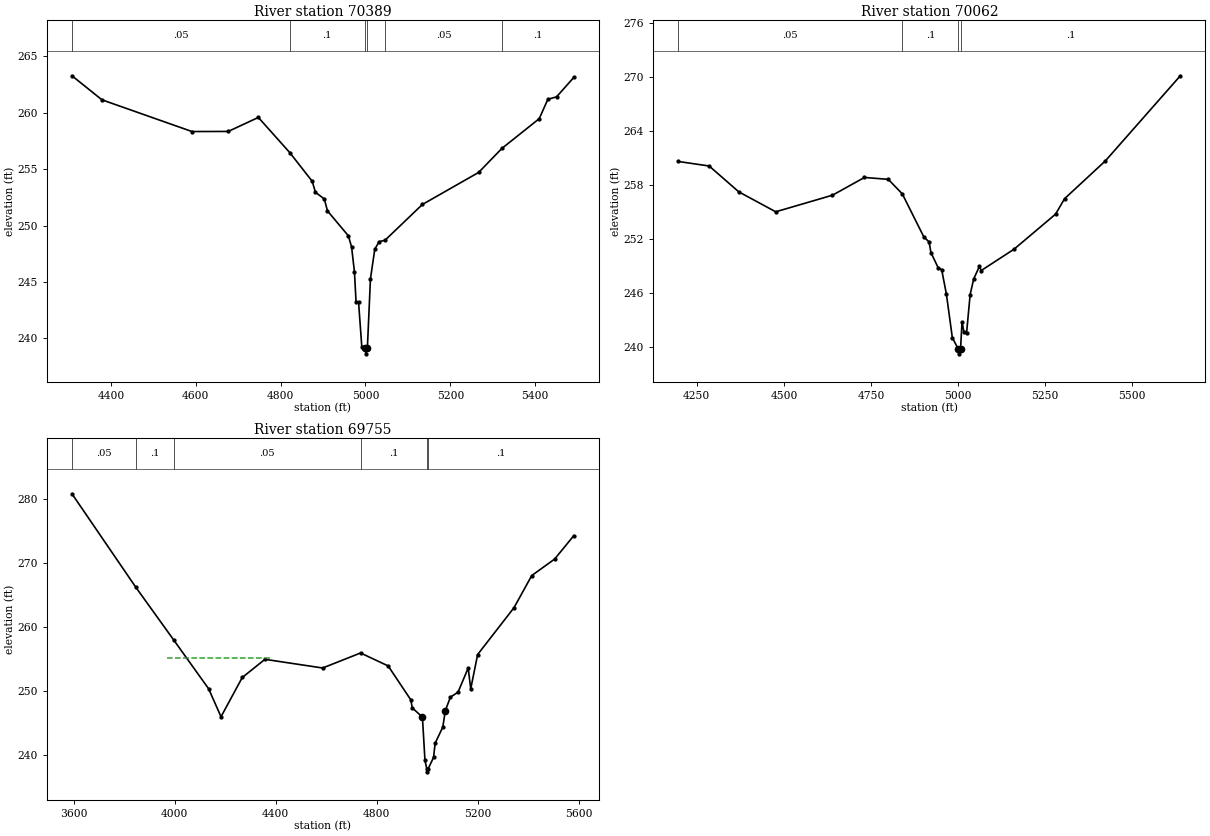
Type RM Length L Ch R = 1 ,70389   ,327,327,327
BEGIN DESCRIPTION:
LA PARA CREEK 120.0
END DESCRIPTION:
XS GIS Cut Line= 3
      2313137.76     13333546.89      2312637.72     13333096.85
      2312137.75     13332996.86
#Sta/Elev= 30
  4308.4  263.27  4379.1  261.14  4591.3  258.33  4676.6  258.34  4747.6  259.58
  4821.5  256.47  4874.6  253.92  4882.1  252.95    4903  252.36  4910.5   251.3
  4959.8  249.09  4967.3   248.1    4974  245.91  4977.8  243.24  4983.7  243.24
  4991.3  239.29  4998.5  239.14  5001.3  238.64  5004.5  239.14  5011.7  245.27
  5021.9   247.9  5032.1  248.58    5046   248.7  5134.1  251.87  5266.7  254.71
  5321.6  256.84  5409.4  259.47  5429.8  261.19  5450.2   261.4    5491  263.13
#Mann= 6 ,-1 , 0
  4308.4     .05       0  4821.5      .1       0  4998.5     .07       0
  5004.5      .1       0    5046     .05       0  5321.6      .1       0
Bank Sta=4998.5,5004.5
XS Rating Curve= 0 ,0
Exp/Cntr=0.3,0.1

Type RM Length L Ch R = 1 ,70062   ,307,307,307
BEGIN DESCRIPTION:
LA PARA CREEK 119.0
END DESCRIPTION:
XS GIS Cut Line= 3
      2313221.57     13333247.79      2312830.93     13332820.69
      2311987.21     13332643.62
#Sta/Elev= 30
  4197.2  260.63  4285.5  260.13  4370.6  257.26  4476.6  255.05  4639.5  256.89
  4731.3  258.86  4799.7  258.65  4839.9  257.04  4901.9  252.25  4916.8  251.71
  4922.3  250.51  4942.8  248.85    4953  248.63  4966.7  245.88  4983.6  241.08
  5001.1  239.79  5003.8  239.29  5007.1  239.79  5011.5  242.84  5016.6  241.76
  5024.5  241.62  5034.7  245.86  5044.9   247.6  5061.4     249  5066.5  248.53
  5161.1  250.91    5280  254.79  5305.7   256.5    5423   260.7  5638.1  270.14
#Mann= 4 ,-1 , 0
  4197.2     .05       0  4839.9      .1       0  5001.1     .07       0
  5007.1      .1       0
Bank Sta=5001.1,5007.1
XS Rating Curve= 0 ,0
Exp/Cntr=0.3,0.1

Type RM Length L Ch R = 1 ,69755   ,246,246,246
BEGIN DESCRIPTION:
Mapping XS ebb26458
END DESCRIPTION:
XS GIS Cut Line= 3
       2313898.6     13332164.46      2312846.55     13332508.19
       2311972.1      13332409.3
#Sta/Elev= 30
  3593.5  280.79  3846.4  266.21  3995.5  258.04  4134.4   250.4  4183.6  246.03
  4267.7  252.15  4357.5  254.98  4585.9  253.63    4736  255.97  4845.3  253.95
  4935.1  248.65  4940.6  247.42  4980.9  245.97  4990.9  239.21    4998  237.94
  5000.8  237.44    5004  237.94  5024.9  239.69  5031.2   241.9  5061.4  244.41
  5071.5  246.98  5091.6  249.08  5121.8  249.86    5162  253.63  5172.1  250.38
  5199.4  255.73  5343.2  263.02  5413.6  268.04  5504.2  270.61  5580.3  274.27
#Mann= 6 ,-1 , 0
  3593.5     .05       0  3846.4      .1       0  3995.5     .05       0
    4736      .1       0    4998     .07       0    5004      .1       0
#XS Ineff= 1 ,-1
 3968.75 4380.86   255.2
Permanent Ineff=
       F
Bank Sta=4980.9,5071.5
XS Rating Curve= 0 ,0
Exp/Cntr=0.3,0.1