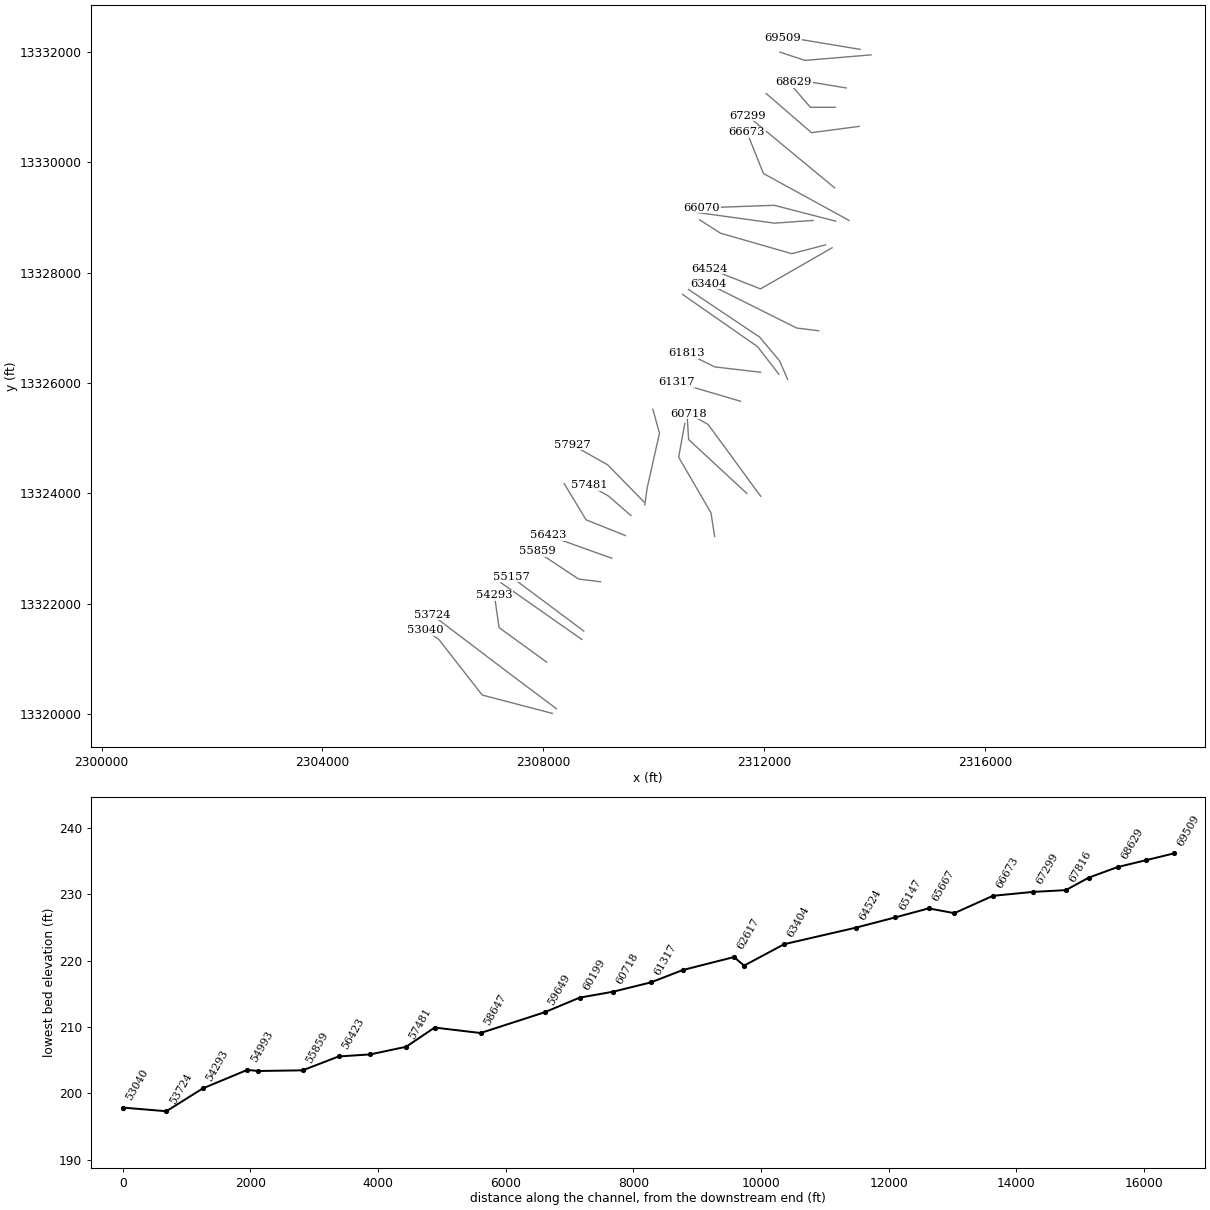
HEC-RAS study LA PARA CREEK.prj: LA PARA CREEK Base Level Engineering

--- LA PARA CREEK.g01 (geometry) --- (continued)

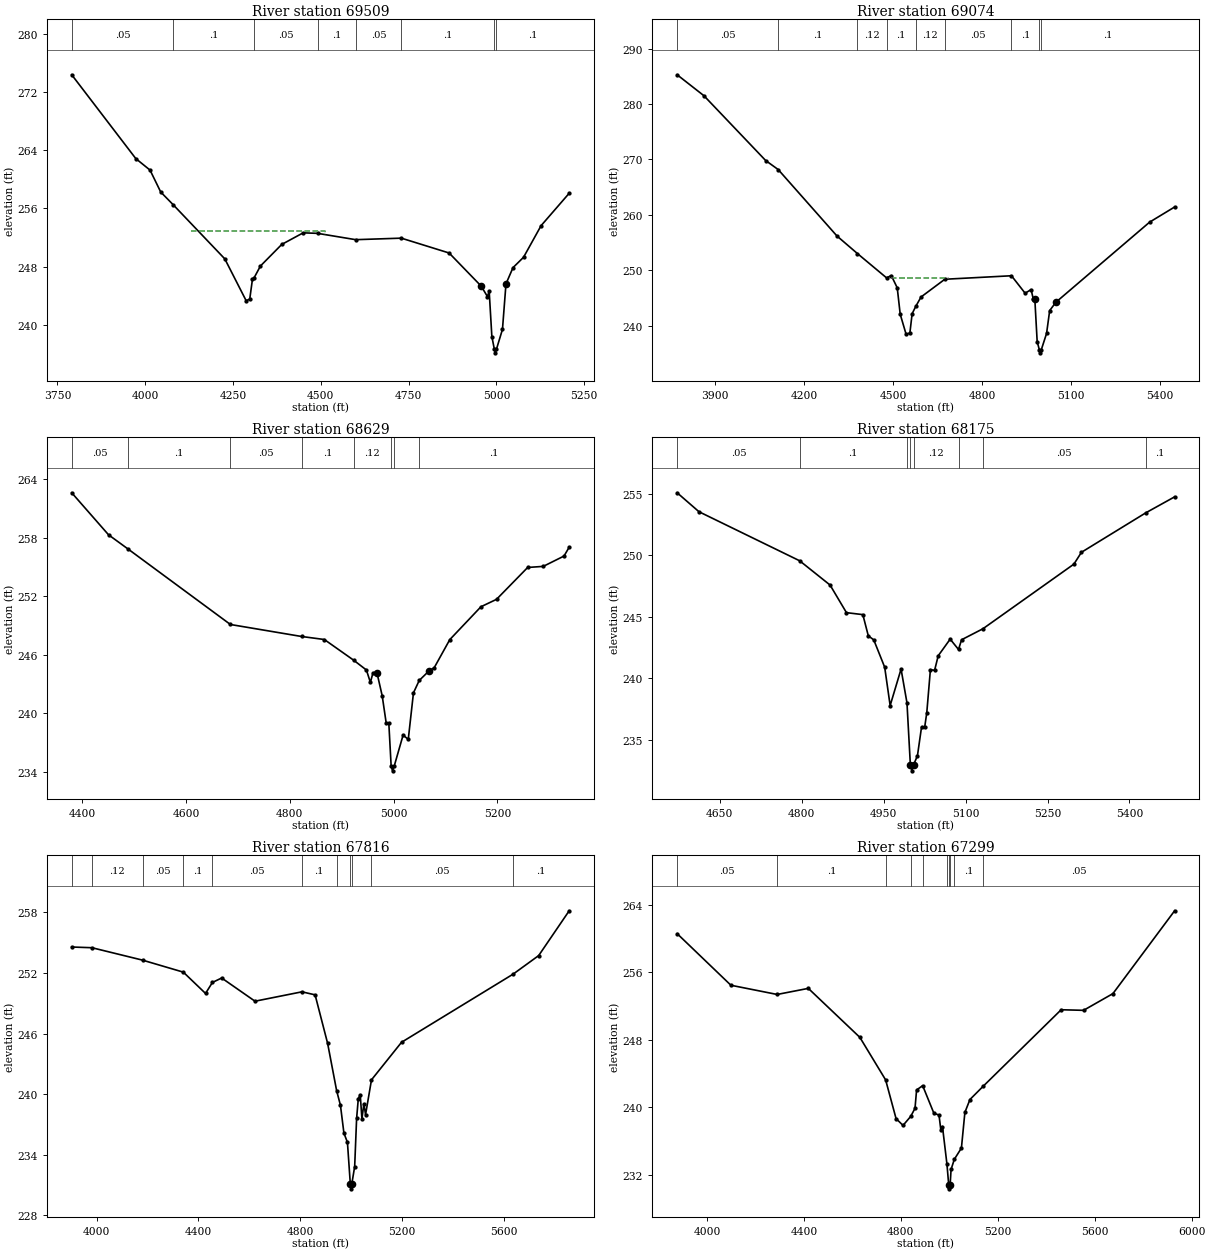
Type RM Length L Ch R = 1 ,69509   ,435,435,435
BEGIN DESCRIPTION:
LA PARA CREEK 118.0
END DESCRIPTION:
XS GIS Cut Line= 3
      2313737.71     13332046.86      2312537.72     13332246.85
      2312337.76     13332246.85
#Sta/Elev= 30
  3790.8  274.36  3973.3  262.84  4013.8  261.26  4044.2  258.25  4079.5  256.51
  4226.7  249.06  4287.5  243.31  4297.7  243.54  4305.3  246.23  4309.1  246.37
  4328.1  248.08  4388.9  251.05  4449.8  252.64  4490.7  252.57  4599.4   251.7
  4729.3  251.91  4865.4  249.87  4956.7  245.32  4974.4  243.89  4979.5  244.61
  4987.1  238.38  4994.2  236.65    4997  236.15  5000.2  236.65  5017.3  239.38
  5027.3  245.63  5047.3  247.86  5077.3  249.28  5127.3  253.63  5207.3  258.08
#Mann= 8 ,-1 , 0
  3790.8     .05       0  4079.5      .1       0  4309.1     .05       0
  4490.7      .1       0  4599.4     .05       0  4729.3      .1       0
  4994.2     .07       0  5000.2      .1       0
#XS Ineff= 1 ,-1
 4131.25 4510.57  252.86
Permanent Ineff=
       F
Bank Sta=4956.7,5027.3
XS Rating Curve= 0 ,0
Exp/Cntr=0.3,0.1

Type RM Length L Ch R = 1 ,69074   ,445,445,445
BEGIN DESCRIPTION:
LA PARA CREEK 117.0
END DESCRIPTION:
XS GIS Cut Line= 3
      2313937.77     13331946.86      2312737.72     13331846.85
      2312287.77     13331996.84
#Sta/Elev= 30
  3771.4  285.27  3861.8  281.49    4070  269.81  4112.3  268.18  4310.8  256.19
  4379.7  253.03    4478  248.65  4493.9  249.07    4514  246.85    4524  242.09
  4544.1  238.44  4556.7  238.74  4564.2  242.18  4576.3  243.49  4594.3   245.2
  4674.6   248.4  4899.4  249.03  4945.5  245.88  4965.6  246.54  4973.1  244.82
  4978.2  244.82  4986.1  237.17  4993.7  235.63  4996.4  235.13  4999.7  235.63
  5017.8  238.62  5028.3  242.75  5049.4  244.26  5365.6   258.7  5449.9  261.43
#Mann= 9 ,-1 , 0
  3771.4     .05       0  4112.3      .1       0  4379.7     .12       0
    4478      .1       0  4576.3     .12       0  4674.6     .05       0
  4899.4      .1       0  4993.7     .07       0  4999.7      .1       0
#XS Ineff= 1 ,-1
 4493.75 4684.47  248.66
Permanent Ineff=
       F
Bank Sta=4978.2,5049.4
XS Rating Curve= 0 ,0
Exp/Cntr=0.3,0.1

Type RM Length L Ch R = 1 ,68629   ,454,454,454
BEGIN DESCRIPTION:
LA PARA CREEK 116.0
END DESCRIPTION:
XS GIS Cut Line= 3
       2313487.7     13331346.86      2312887.72     13331446.85
      2312537.67     13331446.85
#Sta/Elev= 30
  4380.1  262.62    4451  258.31  4488.4  256.86  4685.8  249.11  4822.9  247.88
  4866.7  247.57  4922.9  245.46  4947.8  244.44  4955.4  243.17  4960.5  244.16
  4968.1  244.16  4978.2  241.79  4985.8  239.03  4990.9  239.03  4995.4   234.6
  4998.1   234.1  5001.4   234.6  5018.4  237.76  5028.4  237.33  5038.4   242.1
  5049.5  243.37  5068.4  244.35  5078.4  244.68  5108.4  247.56  5168.4  250.93
  5198.4  251.69  5258.4  254.96  5288.4  255.07  5328.4  256.13  5338.4  257.04
#Mann= 8 ,-1 , 0
  4380.1     .05       0  4488.4      .1       0  4685.8     .05       0
  4822.9      .1       0  4922.9     .12       0  4995.4     .07       0
  5001.4     .12       0  5049.5      .1       0
Bank Sta=4968.1,5068.4
XS Rating Curve= 0 ,0
Exp/Cntr=0.3,0.1

Type RM Length L Ch R = 1 ,68175   ,359,359,359
BEGIN DESCRIPTION:
LA PARA CREEK 115.0
END DESCRIPTION:
XS GIS Cut Line= 3
      2313287.68     13330996.85      2312837.72     13330996.85
      2312537.75     13331346.82
#Sta/Elev= 30
  4571.8  255.07  4611.8  253.53  4796.1  249.55  4851.8  247.58  4881.8  245.34
  4911.8  245.18  4921.8  243.46  4931.8  243.13  4951.8  240.91  4961.8   237.8
  4981.8  240.76  4992.6  238.02  4998.8     233  5001.5   232.5  5004.8     233
  5011.8  233.73  5019.3  236.06  5025.1  236.06  5028.9  237.23  5035.5  240.71
  5043.2  240.66  5049.8  241.84  5071.7  243.19    5087  242.35  5092.6  243.14
  5131.6  244.03  5298.3  249.28  5312.1  250.24  5429.8  253.44  5482.7  254.74
#Mann= 8 ,-1 , 0
  4571.8     .05       0  4796.1      .1       0  4992.6     .12       0
  4998.8     .07       0  5004.8     .12       0    5087      .1       0
  5131.6     .05       0  5429.8      .1       0
Bank Sta=4998.8,5004.8
XS Rating Curve= 0 ,0
Exp/Cntr=0.3,0.1

Type RM Length L Ch R = 1 ,67816   ,517,517,517
BEGIN DESCRIPTION:
LA PARA CREEK 114.0
END DESCRIPTION:
XS GIS Cut Line= 3
      2313722.51     13330651.25      2312857.96     13330536.74
      2312037.74     13331246.84
#Sta/Elev= 30
  3901.3  254.58  3980.8  254.51  4179.8  253.28  4340.3  252.09  4427.7  249.98
  4454.8  251.07  4491.2  251.51  4622.3  249.21    4807  250.14  4858.7  249.84
    4908  245.03  4943.4  240.35  4958.4   238.9  4972.1  236.14  4985.9  235.23
  4997.2  231.12  4999.9  230.62  5003.2  231.12  5014.4  232.83    5022  237.59
  5028.7  239.57  5036.3  239.94  5042.9  237.55  5050.6  239.05  5057.2  237.97
  5080.5  241.42  5198.7  245.14  5637.5  251.89  5738.2  253.73  5858.3  258.17
#Mann= 11 ,-1 , 0
  3901.3     .05       0  3980.8     .12       0  4179.8     .05       0
  4340.3      .1       0  4454.8     .05       0    4807      .1       0
  4943.4     .12       0  4997.2     .07       0  5003.2     .12       0
  5080.5     .05       0  5637.5      .1       0
Bank Sta=4997.2,5003.2
XS Rating Curve= 0 ,0
Exp/Cntr=0.3,0.1

Type RM Length L Ch R = 1 ,67299   ,626,626,626
BEGIN DESCRIPTION:
LA PARA CREEK 113.0
END DESCRIPTION:
XS GIS Cut Line= 2
      2313278.59     13329535.89      2311696.94     13330844.47
#Sta/Elev= 30
    3877  260.57  4098.8  254.46  4289.5  253.37  4418.2  254.09  4630.9  248.29
  4737.3  243.25  4780.3  238.67    4809  237.86  4840.8  238.93  4858.5  239.89
    4865  242.06  4890.1  242.57  4936.7  239.28  4957.5   239.1  4965.3  237.27
  4971.8  237.73  4990.3  233.27  4997.5  230.85  5000.2  230.35  5003.5  230.85
  5007.3  232.65  5020.8  233.85    5050  235.18  5064.3   239.4  5085.2  240.93
  5139.8   242.5  5461.6  251.56    5554  251.49  5675.2  253.47  5929.8  263.28
#Mann= 10 ,-1 , 0
    3877     .05       0  4289.5      .1       0  4737.3     .05       0
  4840.8     .12       0  4890.1      .1       0  4990.3     .12       0
  4997.5     .07       0  5003.5     .12       0  5020.8      .1       0
  5139.8     .05       0
Bank Sta=4997.5,5003.5
XS Rating Curve= 0 ,0
Exp/Cntr=0.3,0.1

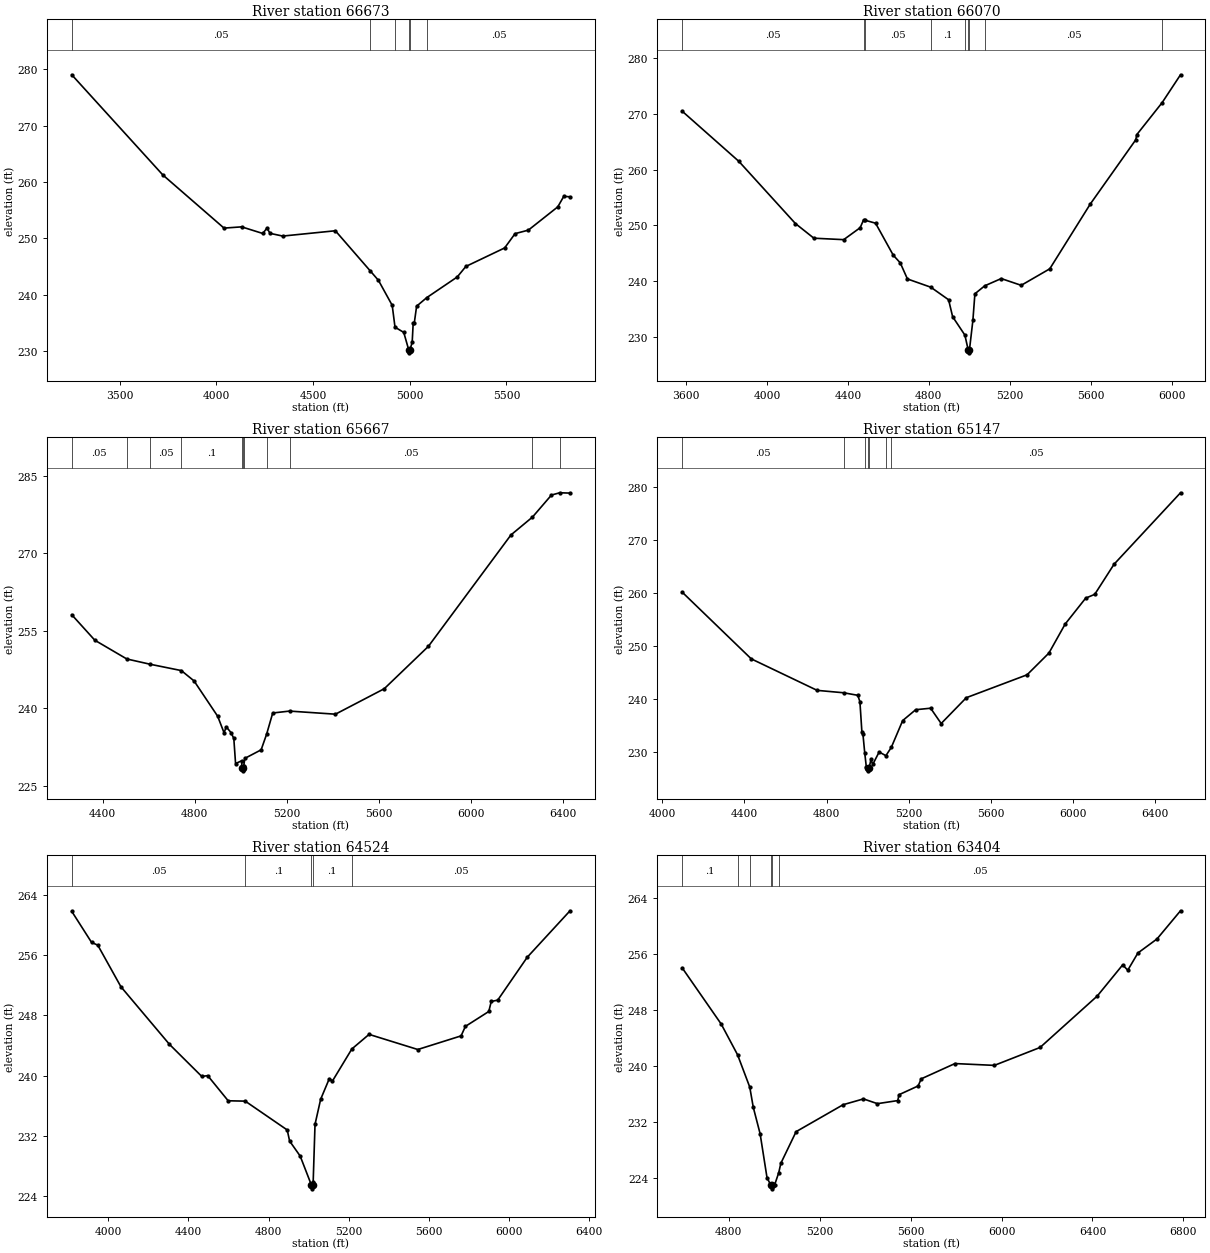
Type RM Length L Ch R = 1 ,66673   ,603,603,603
BEGIN DESCRIPTION:
LA PARA CREEK 112.0
END DESCRIPTION:
XS GIS Cut Line= 3
      2313537.75     13328946.84      2311987.72     13329796.85
      2311687.71     13330546.88
#Sta/Elev= 30
  3252.8  278.98  3723.5  261.25  4039.8  251.84    4131  252.06    4240  250.89
  4261.8  251.83  4277.9  250.91  4343.3  250.43  4615.4  251.37  4795.3  244.28
  4838.1  242.59  4909.2  238.17  4923.7   234.3  4968.9  233.38  4994.8  230.26
  4997.5  229.76  5000.8  230.26  5012.5  231.63  5017.7  235.03  5023.3  235.03
  5035.4  238.02  5088.1  239.54  5245.4  243.19  5289.9  245.05  5490.5  248.33
  5544.3  250.86    5613  251.48  5765.1   255.6  5796.1  257.46  5828.4  257.38
#Mann= 6 ,-1 , 0
  3252.8     .05       0  4795.3      .1       0  4923.7     .12       0
  4994.8     .07       0  5000.8     .12       0  5088.1     .05       0
Bank Sta=4994.8,5000.8
XS Rating Curve= 0 ,0
Exp/Cntr=0.3,0.1

Type RM Length L Ch R = 1 ,66070   ,403,403,403
BEGIN DESCRIPTION:
LA PARA CREEK 111.0
END DESCRIPTION:
XS GIS Cut Line= 3
      2313297.88     13328932.94      2312183.06     13329220.64
      2310871.83     13329173.98
#Sta/Elev= 30
  3580.9  270.48  3860.9  261.49  4140.4  250.34  4231.7  247.71  4379.2  247.45
  4460.5  249.59  4477.3  250.98  4483.1  250.95  4536.7   250.4  4624.2  244.66
  4658.7  243.29  4694.2   240.4  4809.9  238.92  4897.7  236.67  4917.7  233.63
  4978.3  230.33  4994.8  227.65  4997.5  227.15  5000.8  227.65  5017.8  232.96
  5027.8  237.74  5076.4  239.17  5157.9  240.47  5256.7  239.26    5398  242.22
  5598.1  253.83  5823.1  265.36  5828.3  266.29  5953.4  272.02  6044.3  277.02
#Mann= 9 ,-1 , 0
  3580.9     .05       0  4477.3      .1       0  4483.1     .05       0
  4809.9      .1       0  4978.3     .12       0  4994.8     .07       0
  5000.8     .12       0  5076.4     .05       0  5953.4     .08       0
Bank Sta=4994.8,5000.8
XS Rating Curve= 0 ,0
Exp/Cntr=0.3,0.1

Type RM Length L Ch R = 1 ,65667   ,520,520,520
BEGIN DESCRIPTION:
LA PARA CREEK 110.0
END DESCRIPTION:
XS GIS Cut Line= 3
      2312887.75     13328946.86      2312187.72     13328896.85
      2310737.77     13329096.85
#Sta/Elev= 30
  4265.3  258.12  4365.6  253.18  4504.5  249.55  4606.8  248.52  4741.5   247.3
  4796.7   245.3  4899.4  238.45    4927  235.26    4937  236.38  4957.1   235.3
  4969.6  234.14  4977.2  229.28  5003.1  229.81  5005.1  228.37  5007.9  227.87
  5011.1  228.37  5012.6  228.81  5017.6  230.29  5088.3  231.94  5112.1  234.97
  5138.7  239.08  5211.7  239.45  5411.3  238.85  5623.3  243.78  5815.1  251.99
  6174.1  273.59  6267.6  277.05  6350.1  281.32    6386  281.76  6430.8   281.7
#Mann= 11 ,-1 , 0
  4265.3     .05       0  4504.5      .1       0  4606.8     .05       0
  4741.5      .1       0  5005.1     .07       0  5011.1      .1       0
  5012.6     .12       0  5112.1      .1       0  5211.7     .05       0
  6267.6     .08       0    6386      .1       0
Bank Sta=5005.1,5011.1
XS Rating Curve= 0 ,0
Exp/Cntr=0.3,0.1

Type RM Length L Ch R = 1 ,65147   ,623,623,623
BEGIN DESCRIPTION:
LA PARA CREEK 109.0
END DESCRIPTION:
XS GIS Cut Line= 4
      2313112.68      13328503.3      2312501.54     13328343.57
      2311209.87      13328715.1      2310832.08     13328957.72
#Sta/Elev= 30
  4097.4  260.15  4433.3   247.6  4753.9  241.67  4882.3  241.22  4951.6  240.74
    4962  239.54  4971.6  233.86  4976.8   233.4  4985.3  229.95  4993.2  227.25
  5000.6  227.02  5003.3  226.52  5006.6  227.02  5015.7  228.67  5024.4  227.72
  5055.6  230.07  5088.4  229.37  5114.7  230.93  5170.1  235.98  5233.5  238.03
  5306.1  238.31  5357.4  235.43  5479.8  240.29  5775.4   244.6  5881.7  248.69
  5960.9  254.16  6060.6  259.03  6104.8  259.75  6198.6  265.41  6522.1  278.87
#Mann= 7 ,-1 , 0
  4097.4     .05       0  4882.3     .12       0  4985.3     .05       0
  5000.6     .03       0  5006.6     .05       0  5088.4      .1       0
  5114.7     .05       0
Bank Sta=5000.6,5006.6
XS Rating Curve= 0 ,0
Exp/Cntr=0.3,0.1

Type RM Length L Ch R = 1 ,64524   ,1120,1120,1120
BEGIN DESCRIPTION:
LA PARA CREEK 108.0
END DESCRIPTION:
XS GIS Cut Line= 3
      2313230.31     13328449.98      2311933.45      13327705.2
      2311012.19     13328069.54
#Sta/Elev= 30
  3817.8  261.82  3916.6   257.7  3947.6  257.33    4063  251.81  4305.1  244.16
  4466.6  239.89  4496.1     240  4598.2  236.66  4683.4  236.61  4892.9  232.78
  4904.8  231.31  4957.6  229.31  5013.6  225.46  5016.3  224.96  5019.6  225.46
  5022.3  225.81  5031.6  233.53  5059.7  236.86  5102.9   239.6  5118.7  239.29
  5215.3  243.54  5301.3  245.48  5544.4  243.47  5760.4  245.28  5781.9  246.54
  5898.6  248.52  5910.9  249.85  5943.2  250.03  6090.6  255.73    6304   261.9
#Mann= 5 ,-1 , 0
  3817.8     .05       0  4683.4      .1       0  5013.6     .07       0
  5019.6      .1       0  5215.3     .05       0
Bank Sta=5013.6,5019.6
XS Rating Curve= 0 ,0
Exp/Cntr=0.3,0.1

Type RM Length L Ch R = 1 ,63404   ,629,629,629
BEGIN DESCRIPTION:
LA PARA CREEK 107.0
END DESCRIPTION:
XS GIS Cut Line= 3
      2312987.71     13326946.86      2312587.72     13326996.85
      2310987.68     13327796.88
#Sta/Elev= 30
  4595.3  254.04  4766.6  246.03  4838.6  241.64  4892.3  237.02  4907.7  234.14
  4937.9  230.35  4968.2  224.08  4985.3  222.98  4988.1  222.48  4991.3  222.98
  5001.2  222.99  5019.9   224.8  5029.1  226.13  5096.2  230.65  5303.1   234.5
  5392.5  235.33    5454  234.65  5543.4  235.09    5549  235.93  5632.9  237.18
  5646.9   238.2    5795  240.38  5968.3  240.12  6169.5  242.68  6421.1  250.03
  6532.9  254.48  6555.3  253.72    6600  256.18  6683.8  258.18  6787.3  262.21
#Mann= 6 ,-1 , 0
  4595.3      .1       0  4838.6     .05       0  4892.3      .1       0
  4985.3     .07       0  4991.3      .1       0  5019.9     .05       0
Bank Sta=4985.3,4991.3
XS Rating Curve= 0 ,0
Exp/Cntr=0.3,0.1

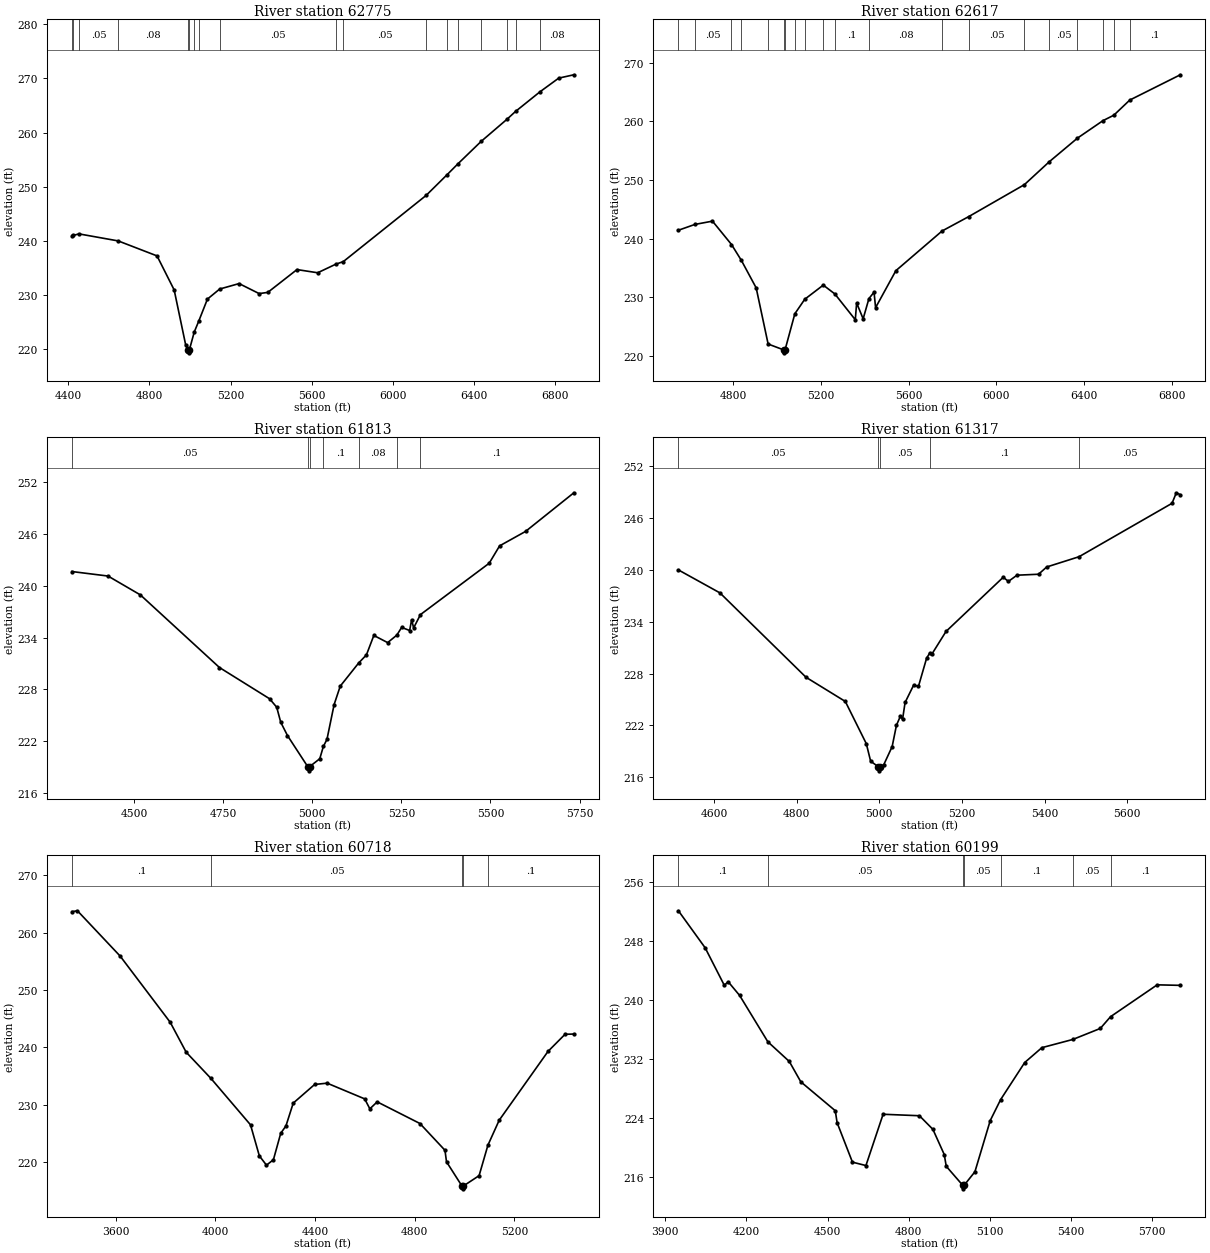
Type RM Length L Ch R = 1 ,62775   ,158,158,158
BEGIN DESCRIPTION:
LA PARA CREEK 106.0
END DESCRIPTION:
XS GIS Cut Line= 4
       2312424.5     13326067.05       2312282.4     13326397.91
      2311918.85     13326832.12        2310632.     13327694.35
#Sta/Elev= 30
  4417.9  240.91  4423.6  240.96  4452.6  241.25  4646.1  239.95  4837.5  237.18
  4922.1  230.88  4979.4  220.61  4990.7  219.75  4993.4  219.25  4996.7  219.75
  5020.9  223.08  5043.3  225.12  5086.1  229.19  5146.5  231.05  5242.2  232.06
  5341.1  230.21  5383.8  230.43  5527.8  234.65  5629.9  234.06  5718.3  235.63
  5756.4  236.13  6164.8  248.37    6266  252.12  6321.3   254.2  6435.8  258.35
  6562.5  262.42  6605.7   263.9  6726.5  267.54  6818.6  270.06  6893.3  270.68
#Mann= 18 ,-1 , 0
  4417.9     .05       0  4423.6     .08       0  4452.6     .05       0
  4646.1     .08       0  4990.7     .07       0  4996.7     .08       0
  5020.9     .05       0  5043.3     .08       0  5146.5     .05       0
  5718.3     .08       0  5756.4     .05       0  6164.8     .08       0
    6266      .1       0  6321.3     .05       0  6435.8      .1       0
  6562.5     .08       0  6605.7     .05       0  6726.5     .08       0
Bank Sta=4990.7,4996.7
XS Rating Curve= 0 ,0
Exp/Cntr=0.3,0.1

Type RM Length L Ch R = 1 ,62617   ,804,804,804
BEGIN DESCRIPTION:
LA PARA CREEK 105.0
END DESCRIPTION:
XS GIS Cut Line= 3
      2312267.43      13326158.7      2311881.36     13326658.32
      2310522.35     13327605.99
#Sta/Elev= 30
    4550  241.43  4625.1  242.42  4705.3  242.98    4792     239  4836.9   236.3
  4904.5  231.61    4959  222.04  5030.1  221.04  5032.9  220.54  5036.1  221.04
  5080.8   227.2    5126  229.67  5210.4  232.08  5263.1  230.58  5356.4  226.18
  5362.5  229.03  5392.2  226.34  5418.5  229.78  5441.9  230.88  5448.9  228.24
  5541.4  234.54    5752   241.3  5874.3  243.77  6127.4   249.2    6241  253.11
  6369.4  257.13  6485.4   260.1    6535  261.03  6607.7  263.61  6838.2  267.92
#Mann= 20 ,-1 , 0
    4550     .08       0  4625.1     .05       0    4792      .1       0
  4836.9     .05       0    4959     .05       0  5030.1    .035       0
  5036.1     .05       0  5080.8     .08       0    5126     .05       0
  5210.4     .08       0  5263.1      .1       0  5418.5     .08       0
    5752     .05       0  5874.3     .05       0  6127.4     .08       0
    6241     .05       0  6369.4     .05       0  6485.4      .1       0
    6535     .05       0  6607.7      .1       0
Bank Sta=5030.1,5036.1
XS Rating Curve= 0 ,0
Exp/Cntr=0.3,0.1

Type RM Length L Ch R = 1 ,61813   ,496,496,496
BEGIN DESCRIPTION:
LA PARA CREEK 104.0
END DESCRIPTION:
XS GIS Cut Line= 3
      2311938.28      13326194.5      2311103.98     13326291.72
       2310594.9     13326543.74
#Sta/Elev= 30
    4326  241.63  4427.2  241.11  4517.9  238.93  4739.8  230.53  4880.3  226.92
  4900.4  225.94  4911.7   224.2  4930.6  222.66  4987.2  219.08  4989.9  218.58
  4993.2  219.08  5021.2  219.98  5031.3   221.4  5041.4  222.22  5061.5  226.25
  5078.7  228.38  5130.5  231.06  5152.1  231.99  5172.9  234.24  5211.7  233.41
  5237.5  234.28  5250.9  235.17  5273.4  234.81  5278.9  236.06  5284.5  235.11
  5303.7  236.65  5496.5  242.59  5525.7   244.6  5598.5  246.27    5734  250.74
#Mann= 7 ,-1 , 0
    4326     .05       0  4987.2     .03       0  4993.2     .05       0
  5031.3      .1       0  5130.5     .08       0  5237.5     .05       0
  5303.7      .1       0
Bank Sta=4987.2,4993.2
XS Rating Curve= 0 ,0
Exp/Cntr=0.3,0.1

Type RM Length L Ch R = 1 ,61317   ,599,599,599
BEGIN DESCRIPTION:
Mapping XS 8ea213fe
END DESCRIPTION:
XS GIS Cut Line= 2
      2311574.11     13325668.73      2310408.46     13326012.18
#Sta/Elev= 30
  4513.6  240.01  4614.1  237.35  4822.6  227.57  4917.7  224.77  4968.5  219.88
    4979  217.85  4996.8  217.23  4999.6  216.73  5002.8  217.23  5010.2  217.38
  5031.1  219.54  5041.5  222.01  5051.1  223.07  5056.3   222.7  5062.4  224.65
  5083.2  226.67  5094.8  226.52  5114.5  229.78  5122.2  230.39  5128.1  230.32
  5161.5  232.88    5300  239.16  5312.6  238.68  5333.3   239.4  5385.5  239.51
  5405.2  240.35  5483.6  241.54  5708.7  247.73  5719.1  248.95  5728.8  248.73
#Mann= 5 ,-1 , 0
  4513.6     .05       0  4996.8     .03       0  5002.8     .05       0
  5122.2      .1       0  5483.6     .05       0
Bank Sta=4996.8,5002.8
XS Rating Curve= 0 ,0
Exp/Cntr=0.3,0.1

Type RM Length L Ch R = 1 ,60718   ,519,519,519
BEGIN DESCRIPTION:
LA PARA CREEK 103.0
END DESCRIPTION:
XS GIS Cut Line= 3
       2311937.7     13323946.89      2310987.72     13325246.85
      2310637.72     13325446.86
#Sta/Elev= 30
  3425.3  263.68  3447.3  263.83  3618.7  255.92  3819.5  244.37  3883.5  239.15
  3982.7  234.58  4141.5  226.48    4177  221.06  4205.6  219.44  4233.4  220.39
  4262.8  225.01  4283.6  226.28  4312.9  230.27  4398.7  233.52  4448.9  233.75
  4599.4  231.01  4620.3  229.27  4649.6  230.49  4821.1  226.71  4921.5  222.04
  4927.7  220.03  4989.5  215.81  4992.3  215.31  4995.5  215.81  5058.4  217.61
  5093.9  222.94    5139  227.28  5334.8  239.29  5403.2  242.28  5438.5  242.32
#Mann= 5 ,-1 , 0
  3425.3      .1       0  3982.7     .05       0  4989.5     .03       0
  4995.5     .05       0  5093.9      .1       0
Bank Sta=4989.5,4995.5
XS Rating Curve= 0 ,0
Exp/Cntr=0.3,0.1

Type RM Length L Ch R = 1 ,60199   ,550,550,550
BEGIN DESCRIPTION:
LA PARA CREEK 102.0
END DESCRIPTION:
XS GIS Cut Line= 3
      2311687.71     13323996.87      2310632.33     13324976.64
      2310606.62     13325392.29
#Sta/Elev= 30
  3948.3  252.05  4047.2  247.04  4118.1  241.96  4132.2  242.46  4174.8  240.59
    4279  234.33  4358.5  231.66    4401  228.91  4528.5     225  4535.3  223.38
    4592  218.04  4641.9  217.58  4705.4  224.52  4839.8  224.32  4889.6  222.48
  4931.6  219.07    4939  217.48  4999.5  214.93  5002.2  214.43  5005.5  214.93
    5045  216.74  5101.7  223.67  5140.1   226.5  5229.2  231.52  5292.7  233.53
  5407.1  234.64  5508.8  236.13  5546.7  237.72  5719.2  242.03  5804.8  241.96
#Mann= 7 ,-1 , 0
  3948.3      .1       0    4279     .05       0  4999.5     .03       0
  5005.5     .05       0  5140.1      .1       0  5407.1     .05       0
  5546.7      .1       0
Bank Sta=4999.5,5005.5
XS Rating Curve= 0 ,0
Exp/Cntr=0.3,0.1

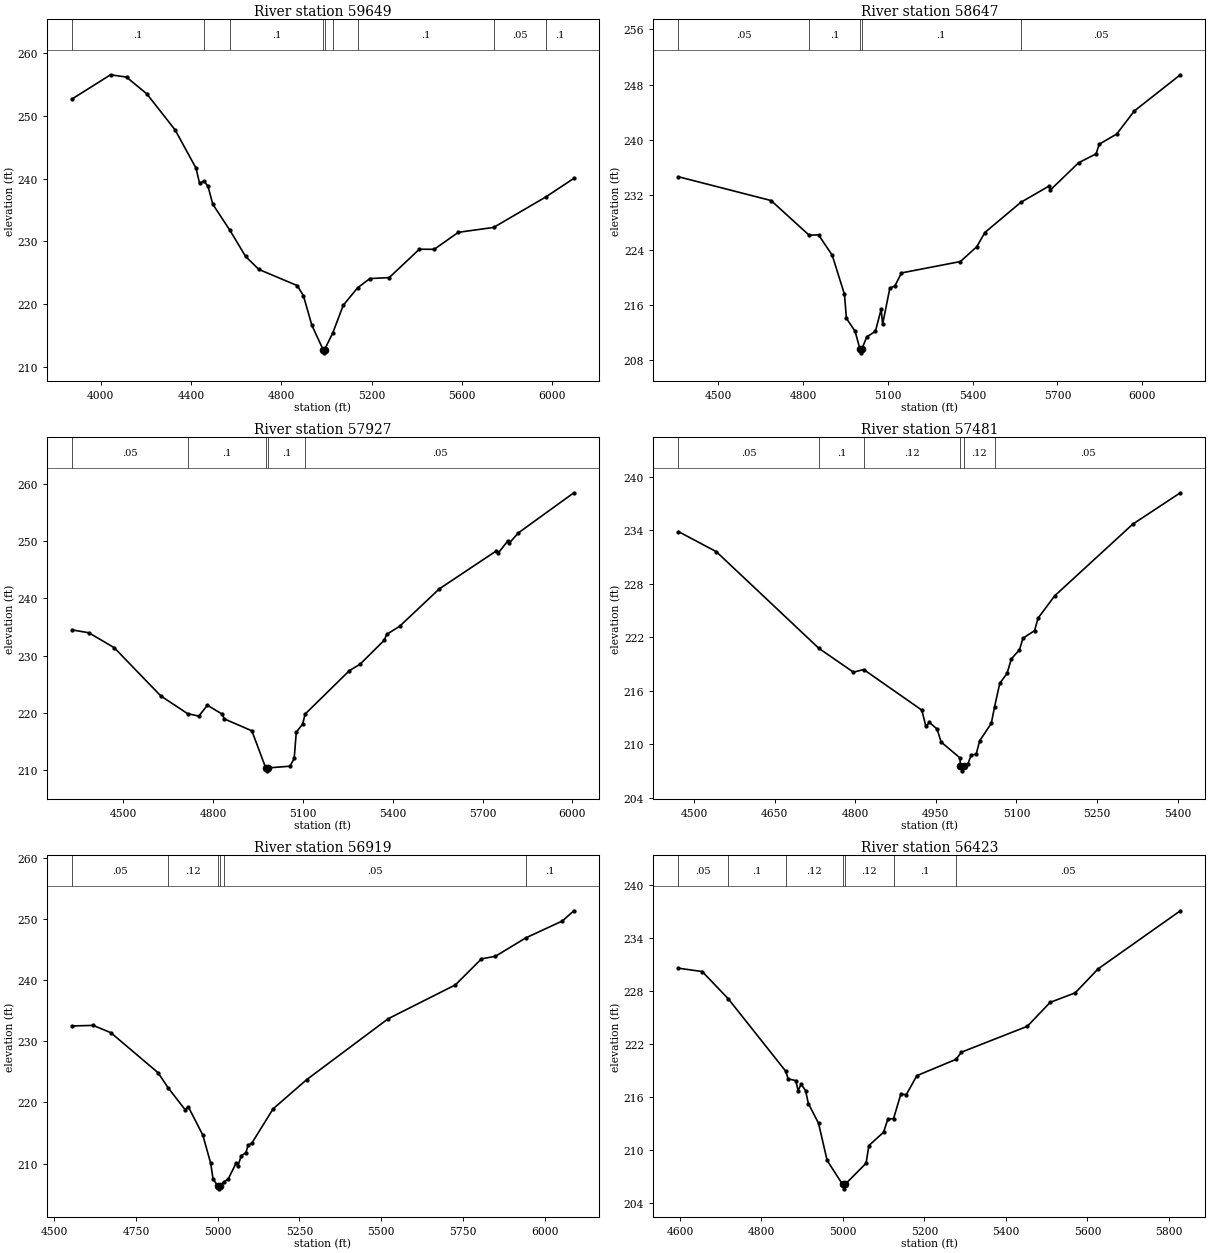
Type RM Length L Ch R = 1 ,59649   ,1002,1002,1002
BEGIN DESCRIPTION:
LA PARA CREEK 101.0
END DESCRIPTION:
XS GIS Cut Line= 4
      2311104.16     13323218.02      2311037.72     13323646.85
      2310452.18     13324654.94      2310563.71     13325268.33
#Sta/Elev= 30
    3872  252.69  4042.9  256.56  4113.7  256.19  4203.8  253.51  4329.1  247.76
  4421.6  241.67  4437.2  239.25    4456   239.6  4474.4  238.82  4495.9  235.91
  4571.9  231.75  4641.3  227.59  4699.6  225.53  4870.1  222.94  4897.4  221.33
  4934.7  216.61  4984.7  212.72  4987.4  212.22  4990.7  212.72  5027.3  215.39
  5073.7   219.8  5137.1  222.58  5191.3  224.06  5277.4  224.22  5410.7  228.74
  5476.8  228.73  5583.5  231.44    5740  232.22  5970.6  237.07  6095.2  240.04
#Mann= 9 ,-1 , 0
    3872      .1       0    4456     .05       0  4571.9      .1       0
  4984.7     .07       0  4990.7      .1       0  5027.3     .05       0
  5137.1      .1       0    5740     .05       0  5970.6      .1       0
Bank Sta=4984.7,4990.7
XS Rating Curve= 0 ,0
Exp/Cntr=0.3,0.1

Type RM Length L Ch R = 1 ,58647   ,720,720,720
BEGIN DESCRIPTION:
LA PARA CREEK 100.0
END DESCRIPTION:
XS GIS Cut Line= 4
       2309838.8     13323792.76       2309881.7     13324097.32
      2310104.74     13325088.16      2309985.17     13325523.75
#Sta/Elev= 30
  4359.6  234.64  4687.2  231.19  4821.7  226.17  4855.1  226.21  4903.5  223.26
  4946.8  217.58  4953.7  214.11  4984.4  212.22  5001.9   209.6  5004.7   209.1
  5007.9   209.6  5025.4   211.4  5056.2  212.22  5076.6  215.42  5081.7  213.24
  5107.4  218.51    5125  218.79  5148.4  220.69  5356.7  222.34    5415   224.5
  5443.2  226.55  5570.2  230.92  5669.8  233.28    5675  232.72  5774.8  236.67
  5836.7  237.96  5847.4  239.35  5909.6  240.84  5971.8  244.18  6134.5  249.43
#Mann= 5 ,-1 , 0
  4359.6     .05       0  4821.7      .1       0  5001.9     .07       0
  5007.9      .1       0  5570.2     .05       0
Bank Sta=5001.9,5007.9
XS Rating Curve= 0 ,0
Exp/Cntr=0.3,0.1

Type RM Length L Ch R = 1 ,57927   ,446,446,446
BEGIN DESCRIPTION:
LA PARA CREEK 99.0
END DESCRIPTION:
XS GIS Cut Line= 3
       2309824.5     13323844.24      2309164.81     13324517.82
       2308526.3     13324877.97
#Sta/Elev= 30
  4329.1  234.49  4385.3  233.99  4470.2  231.39  4625.7  222.98  4715.2  219.89
  4752.9  219.46  4781.2  221.36  4830.8  219.81  4837.8  218.97  4929.8   216.9
  4976.2  210.42    4979  209.92  4982.2  210.42  5057.1  210.73  5071.2  212.09
  5078.2  216.66  5099.5  218.09  5107.6  219.81  5255.1  227.37  5291.5  228.52
  5371.9  232.69  5379.8   233.7  5423.1  235.11  5555.6  241.63  5746.7  248.28
  5752.4  247.88  5784.2  249.98    5790  249.65  5819.7   251.4    6005  258.39
#Mann= 5 ,-1 , 0
  4329.1     .05       0  4715.2      .1       0  4976.2     .07       0
  4982.2      .1       0  5107.6     .05       0
Bank Sta=4976.2,4982.2
XS Rating Curve= 0 ,0
Exp/Cntr=0.3,0.1

Type RM Length L Ch R = 1 ,57481   ,562,562,562
BEGIN DESCRIPTION:
LA PARA CREEK 98.0
END DESCRIPTION:
XS GIS Cut Line= 3
      2309587.69     13323596.89      2309187.72     13323946.85
       2308837.7     13324146.87
#Sta/Elev= 30
  4470.6  233.86  4541.3   231.6  4732.3  220.76  4796.6  218.09  4815.6  218.39
  4923.8  213.84  4931.4  212.02    4938  212.46  4952.2  211.72  4959.8  210.26
  4994.9  208.48  4995.7  207.53  4998.5  207.03  5001.7  207.53    5010  207.85
  5015.7   208.8  5025.1   208.9  5031.6   210.4  5053.2  212.35  5059.2  214.18
    5069  216.84  5082.7  217.98  5090.6  219.59  5105.7   220.6  5112.2   221.9
  5133.8  222.75  5140.3  224.15  5171.2  226.65  5316.6  234.69  5405.2  238.21
#Mann= 6 ,-1 , 0
  4470.6     .05       0  4732.3      .1       0  4815.6     .12       0
  4995.7     .07       0  5001.7     .12       0  5059.2     .05       0
Bank Sta=4995.7,5001.7
XS Rating Curve= 0 ,0
Exp/Cntr=0.3,0.1

Type RM Length L Ch R = 1 ,56919   ,496,496,496
BEGIN DESCRIPTION:
LA PARA CREEK 97.0
END DESCRIPTION:
XS GIS Cut Line= 3
      2309488.07     13323234.33      2308774.55     13323520.77
      2308378.69     13324177.06
#Sta/Elev= 30
  4554.1  232.51  4619.1   232.6    4673  231.41  4817.2  224.88  4848.5  222.39
  4900.5   218.8  4910.1  219.29  4954.3  214.68  4978.5  210.06  4985.5  207.55
  4999.7  206.38  5002.5  205.88  5005.7  206.38  5019.4  207.01  5032.3  207.51
  5056.5  210.11  5061.9  209.61  5071.7  211.26  5086.1   211.8  5093.3  213.04
    5104  213.32  5169.5  218.96  5271.6  223.71  5521.4  233.69  5727.1  239.23
  5806.8  243.48  5849.5   243.9  5941.8  246.89  6054.1  249.67  6089.4  251.34
#Mann= 6 ,-1 , 0
  4554.1     .05       0  4848.5     .12       0  4999.7     .07       0
  5005.7     .12       0  5019.4     .05       0  5941.8      .1       0
Bank Sta=4999.7,5005.7
XS Rating Curve= 0 ,0
Exp/Cntr=0.3,0.1

Type RM Length L Ch R = 1 ,56423   ,564,564,564
BEGIN DESCRIPTION:
LA PARA CREEK 96.0
END DESCRIPTION:
XS GIS Cut Line= 2
      2309241.24     13322823.36      2308082.08     13323239.82
#Sta/Elev= 30
  4596.3  230.55  4654.7  230.17  4718.4   227.1  4859.1  218.92  4865.7  218.02
  4884.6  217.82  4889.9   216.7  4897.6  217.42  4908.2   216.7  4915.3  215.22
  4940.1     213  4961.3  208.78  4999.2  206.07    5002  205.57  5005.2  206.07
  5056.9  208.47  5063.7  210.47  5099.7  211.98  5110.1  213.44  5124.3  213.53
    5142  216.27  5155.8  216.25  5181.3  218.38  5277.6  220.23  5290.7  221.04
  5452.5  223.97  5508.6  226.68  5570.1  227.76  5626.2  230.47    5828  237.05
#Mann= 7 ,-1 , 0
  4596.3     .05       0  4718.4      .1       0  4859.1     .12       0
  4999.2     .07       0  5005.2     .12       0  5124.3      .1       0
  5277.6     .05       0
Bank Sta=4999.2,5005.2
XS Rating Curve= 0 ,0
Exp/Cntr=0.3,0.1

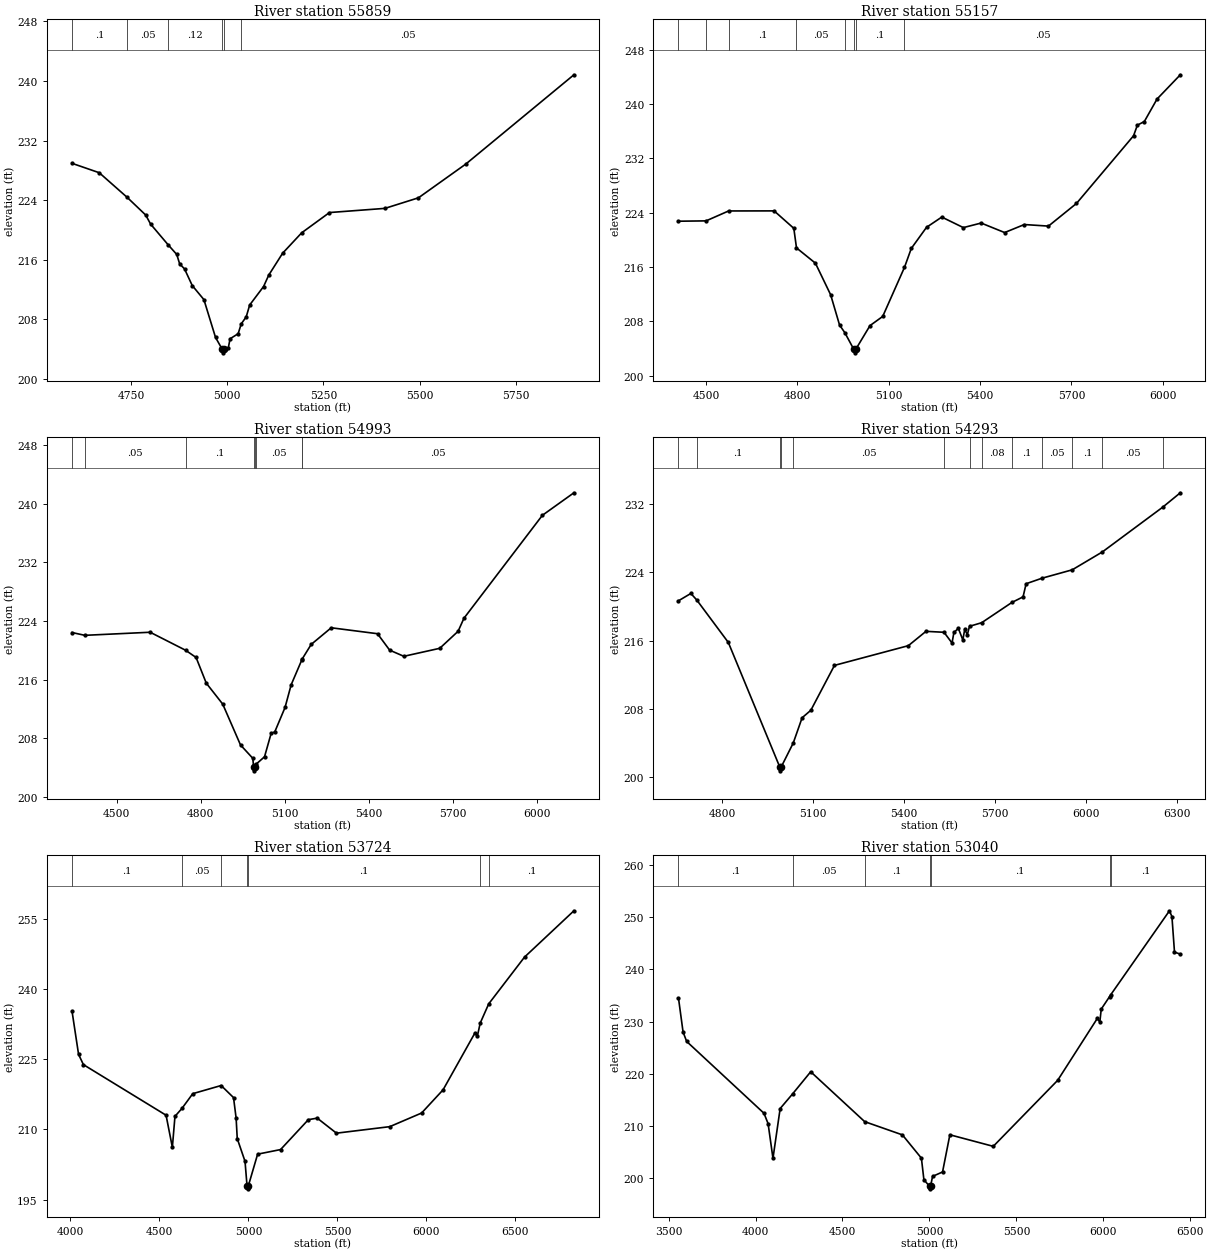
Type RM Length L Ch R = 1 ,55859   ,702,702,702
BEGIN DESCRIPTION:
LA PARA CREEK 95.0
END DESCRIPTION:
XS GIS Cut Line= 3
      2309037.76     13322396.85      2308637.72     13322446.85
      2307887.75     13322946.83
#Sta/Elev= 30
  4596.6  228.94  4667.2  227.68  4739.6  224.38  4788.1  221.99  4800.7  220.78
  4846.4  217.99  4868.7   216.7  4876.3  215.43  4888.9  214.76    4909  212.52
  4939.3  210.63  4969.5  205.55  4986.7  203.98  4989.4  203.48  4992.7  203.98
  5002.8  204.17  5007.3  205.37  5028.3  206.05  5036.3  207.37  5049.3  208.32
  5058.3  209.91  5094.4  212.39  5107.9  213.93    5144  216.87  5193.5  219.61
  5265.7  222.33  5409.9  222.89    5497  224.31  5620.2  228.85  5901.1  240.84
#Mann= 6 ,-1 , 0
  4596.6      .1       0  4739.6     .05       0  4846.4     .12       0
  4986.7     .07       0  4992.7     .12       0  5036.3     .05       0
Bank Sta=4986.7,4992.7
XS Rating Curve= 0 ,0
Exp/Cntr=0.3,0.1

Type RM Length L Ch R = 1 ,55157   ,164,164,164
BEGIN DESCRIPTION:
LA PARA CREEK 94.0
END DESCRIPTION:
XS GIS Cut Line= 2
      2308734.28     13321503.91      2307414.77     13322490.07
#Sta/Elev= 30
    4410  222.76  4500.6  222.81  4574.6  224.27    4724  224.28  4788.6  221.71
  4797.4  218.83  4859.5  216.58  4909.5  211.93  4938.7  207.48    4956  206.35
  4985.7  203.88  4988.5  203.38  4991.7  203.88  5038.7  207.39  5080.4  208.74
  5151.9  215.97  5174.2  218.75  5224.2  221.86  5274.3  223.37  5345.1  221.82
  5403.5  222.49  5480.6  221.09  5545.2  222.27  5624.4  222.04  5716.5  225.38
  5903.8  235.34  5916.3   236.9  5939.2  237.44  5980.9  240.75  6057.3  244.32
#Mann= 8 ,-1 , 0
    4410      .1       0  4500.6     .05       0  4574.6      .1       0
  4797.4     .05       0    4956      .1       0  4985.7     .07       0
  4991.7      .1       0  5151.9     .05       0
Bank Sta=4985.7,4991.7
XS Rating Curve= 0 ,0
Exp/Cntr=0.3,0.1

Type RM Length L Ch R = 1 ,54993   ,700,700,700
BEGIN DESCRIPTION:
LA PARA CREEK 93.0
END DESCRIPTION:
XS GIS Cut Line= 2
      2308699.54     13321351.15      2307234.25     13322378.93
#Sta/Elev= 30
  4341.4  222.41  4386.9  222.03  4619.9  222.45    4746     220  4783.7  219.01
    4820  215.51  4878.7  212.65  4942.1  207.08  4985.9  205.26    4989  204.05
  4991.8  203.55    4995  204.05  4997.8  204.46  5027.8  205.47  5051.3  208.65
  5064.3  208.86  5100.9  212.19  5122.8  215.29    5160  218.61  5162.7  218.84
  5194.2  220.79  5265.7  223.06  5430.7  222.25    5474  220.01  5524.6  219.17
  5652.7  220.26  5718.1  222.58    5739  224.36  6018.8   238.4  6131.2  241.47
#Mann= 8 ,-1 , 0
  4341.4      .1       0  4386.9     .05       0    4746      .1       0
    4989     .04       0    4995      .1       0  4997.8     .05       0
    5160      .1       0  5162.7     .05       0
Bank Sta=4989,4995
XS Rating Curve= 0 ,0
Exp/Cntr=0.3,0.1

Type RM Length L Ch R = 1 ,54293   ,569,569,569
BEGIN DESCRIPTION:
LA PARA CREEK 92.0
END DESCRIPTION:
XS GIS Cut Line= 3
      2308060.64     13320941.43      2307199.53     13321566.43
       2307116.2     13322149.79
#Sta/Elev= 30
  4656.8  220.68  4697.6  221.54  4716.9  220.78    4821   215.8  4989.9  201.25
  4992.7  200.75  4995.9  201.25    5035  204.02  5064.1  206.97  5092.9  207.85
  5170.7  213.11  5414.1  215.42  5472.2   217.1  5531.6  216.99    5558  215.73
  5564.2  216.97  5578.9  217.45  5593.6  216.09  5599.8  217.33  5608.3  216.71
  5615.6  217.69  5655.6  218.11  5755.4  220.49    5792  221.14  5802.1  222.68
  5854.7  223.33    5954  224.31  6053.4  226.41    6252  231.65  6310.1  233.34
#Mann= 13 ,-1 , 0
  4656.8     .05       0  4716.9      .1       0  4989.9     .07       0
  4995.9      .1       0    5035     .05       0  5531.6      .1       0
  5615.6     .05       0  5655.6     .08       0  5755.4      .1       0
  5854.7     .05       0    5954      .1       0  6053.4     .05       0
    6252      .1       0
Bank Sta=4989.9,4995.9
XS Rating Curve= 0 ,0
Exp/Cntr=0.3,0.1

Type RM Length L Ch R = 1 ,53724   ,684,684,684
BEGIN DESCRIPTION:
LA PARA CREEK 91.0
END DESCRIPTION:
XS GIS Cut Line= 3
      2308237.75     13320096.83      2307437.72     13320696.85
      2305987.69     13321796.87
#Sta/Elev= 30
  4008.9  235.17  4045.4  226.02  4072.5  223.83  4537.1  213.03  4572.5  206.18
  4587.1  212.79  4626.3  214.48  4687.1  217.63  4846.6  219.37  4916.2  216.79
  4930.8   212.4  4937.1  208.04  4980.8  203.19  4992.4  197.82  4995.1  197.32
  4998.4  197.82  5051.6  204.72  5180.5   205.7  5336.6  212.08  5386.5  212.41
  5494.6   209.2  5794.1  210.59    5973   213.5  6093.7  218.45  6272.5  230.57
  6287.1  230.04  6302.5   232.7  6350.3   236.8  6551.3  246.77    6829  256.66
#Mann= 7 ,-1 , 0
  4008.9      .1       0  4626.3     .05       0  4846.6      .1       0
  4992.4     .07       0  4998.4      .1       0  6302.5     .08       0
  6350.3      .1       0
Bank Sta=4992.4,4998.4
XS Rating Curve= 0 ,0
Exp/Cntr=0.3,0.1

Type RM Length L Ch R = 1 ,53040   ,749,749,749
BEGIN DESCRIPTION:
LA PARA CREEK 90.0
END DESCRIPTION:
XS GIS Cut Line= 4
      2308163.27     13320011.88      2306893.98      13320344.2
      2306109.26     13321351.15      2305866.71     13321522.06
#Sta/Elev= 30
    3557  234.52  3583.4  227.98  3604.1  226.17  4048.6  212.38  4072.3  210.39
  4100.3  203.73  4141.6  213.29  4214.4  216.15  4317.3  220.35  4627.7  210.77
  4844.5  208.23  4953.7  203.76  4968.1  199.62  5000.4  198.37  5003.2  197.87
  5006.4  198.37  5017.9  200.26  5075.3  201.11  5117.4  208.25  5366.9  206.03
  5737.1   218.7  5965.1  230.59  5979.6  229.88  5987.7  232.38  6035.2  234.76
  6042.2  235.13    6380  251.26  6394.2  250.13  6408.9  243.32  6442.4  242.94
#Mann= 7 ,-1 , 0
    3557      .1       0  4214.4     .05       0  4627.7      .1       0
  5000.4     .07       0  5006.4      .1       0  6035.2     .08       0
  6042.2      .1       0
Bank Sta=5000.4,5006.4
XS Rating Curve= 0 ,0
Exp/Cntr=0.3,0.1