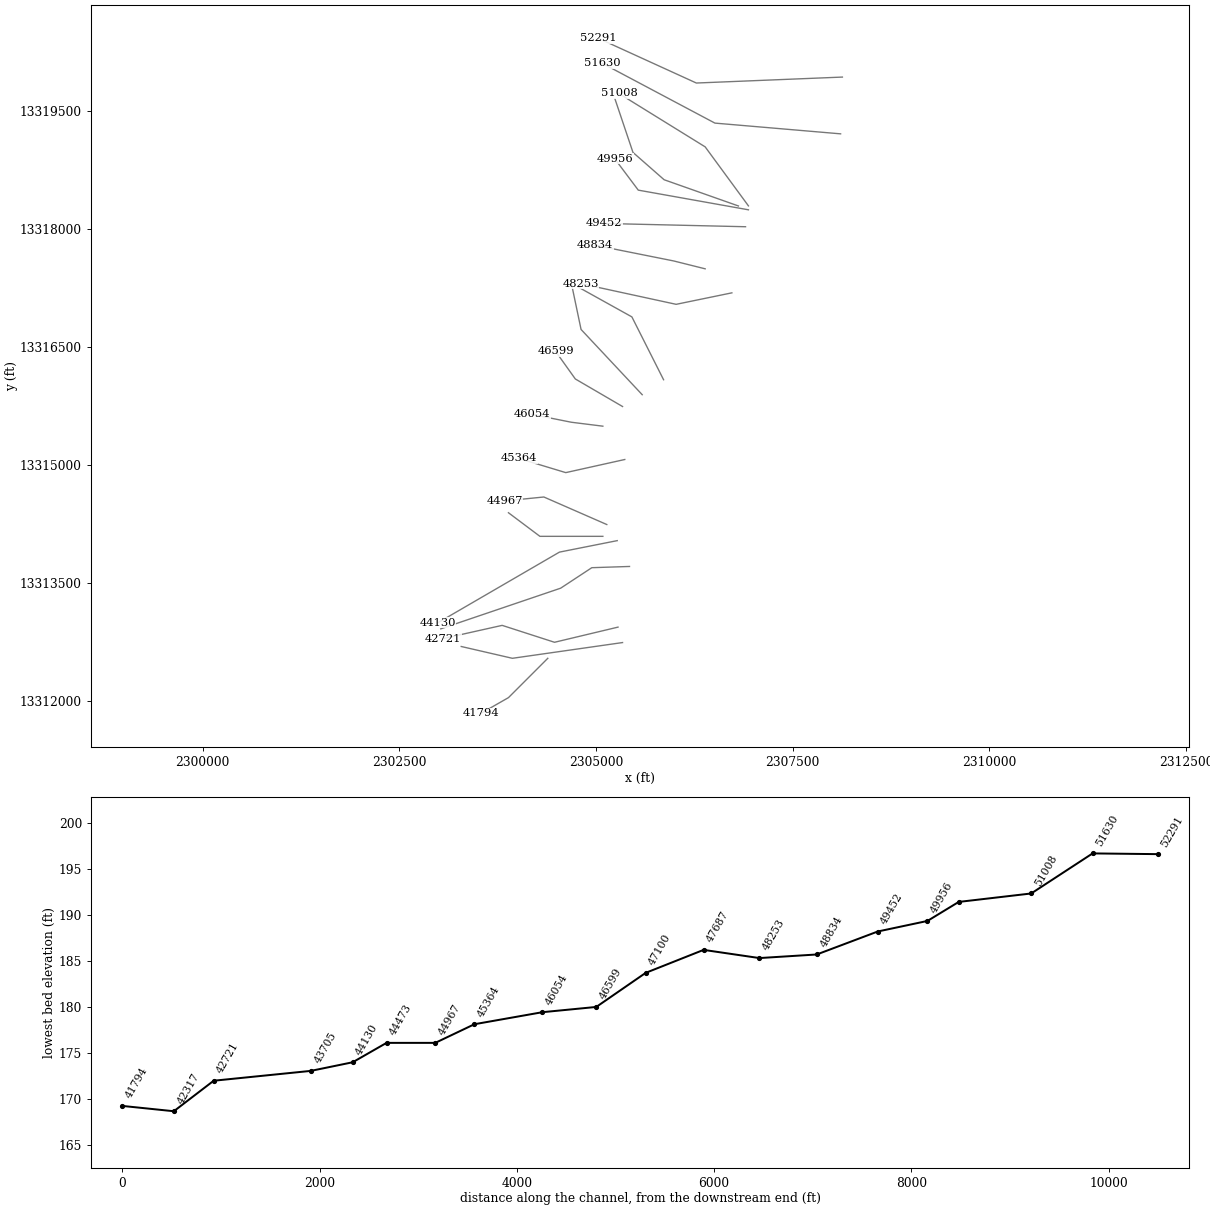
HEC-RAS study LA PARA CREEK.prj: LA PARA CREEK Base Level Engineering

--- LA PARA CREEK.g01 (geometry) --- (continued)

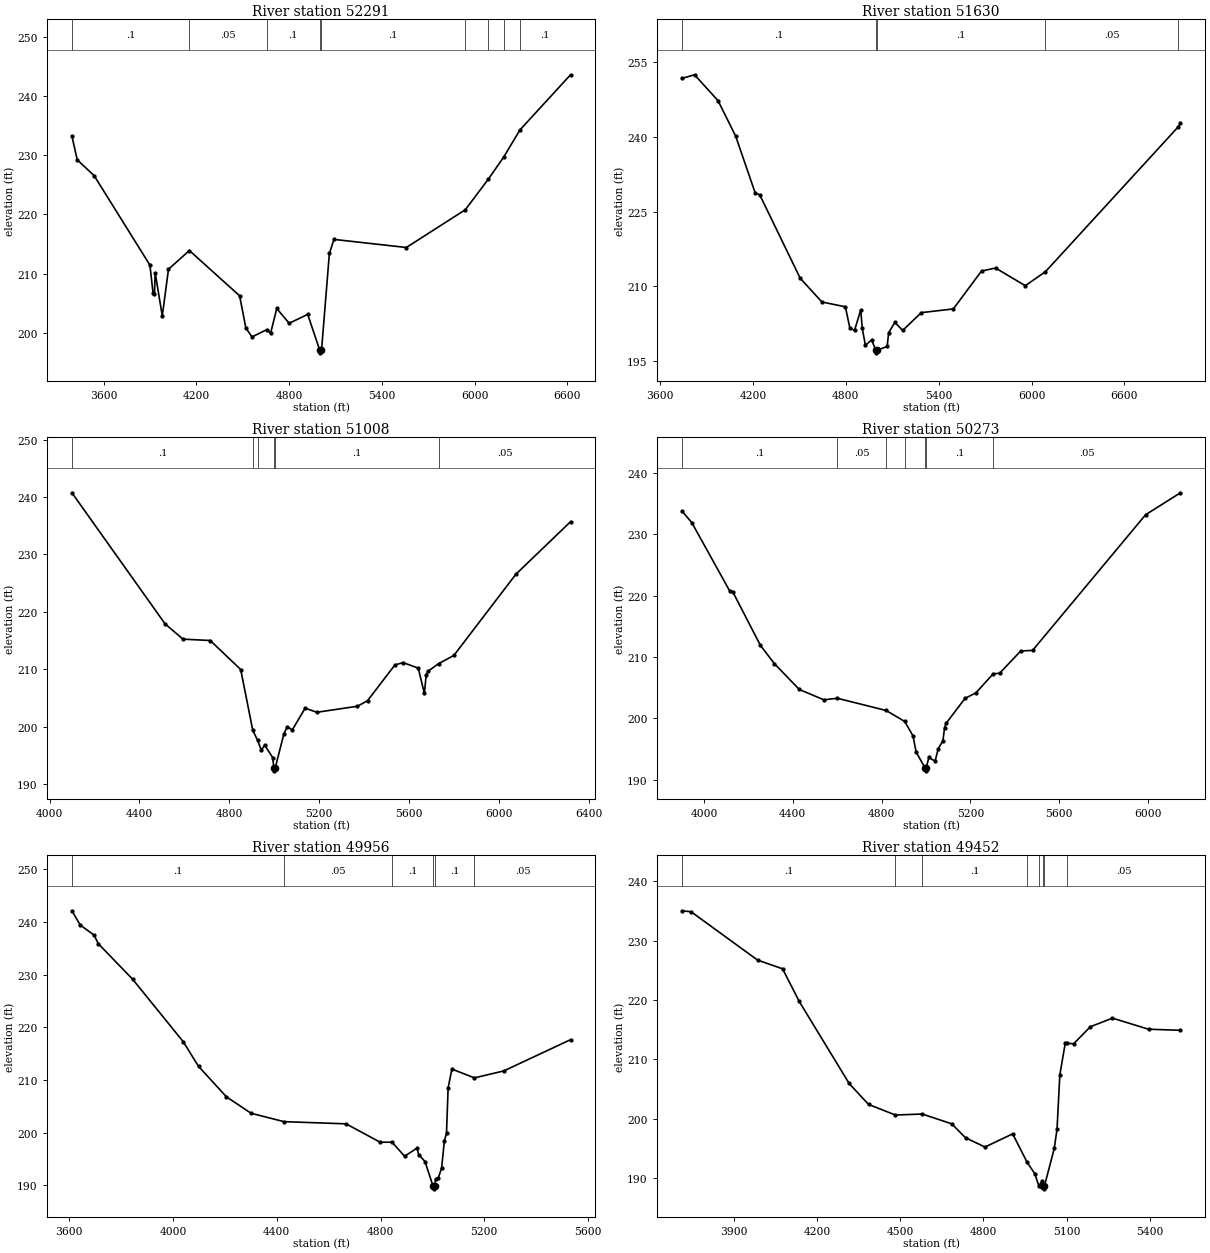
Type RM Length L Ch R = 1 ,52291   ,661,661,661
BEGIN DESCRIPTION:
LA PARA CREEK 89.0
END DESCRIPTION:
XS GIS Cut Line= 3
      2308131.96     13319933.77      2306275.92     13319858.09
      2305031.17     13320426.09
#Sta/Elev= 30
  3394.7  233.23    3429  229.23  3539.1  226.52  3899.4  211.43  3919.4  206.78
  3928.5  206.54  3933.5  210.13  3979.4  202.85  4019.5  210.74  4154.6   213.9
  4479.8  206.25  4519.9  200.82  4559.9  199.31  4655.4  200.54    4680  199.92
    4720  204.11  4800.1  201.61  4920.2  203.12  4997.3  197.12    5000  196.62
  5003.3  197.12  5010.3  197.26  5060.3   213.4  5090.3  215.78  5558.1  214.41
  5939.9  220.79  6087.3   225.9  6188.7   229.7  6292.8  234.25  6620.5  243.58
#Mann= 9 ,-1 , 0
  3394.7      .1       0  4154.6     .05       0  4655.4      .1       0
  4997.3     .07       0  5003.3      .1       0  5939.9     .05       0
  6087.3      .1       0  6188.7     .05       0  6292.8      .1       0
Bank Sta=4997.3,5003.3
XS Rating Curve= 0 ,0
Exp/Cntr=0.3,0.1

Type RM Length L Ch R = 1 ,51630   ,622,622,622
BEGIN DESCRIPTION:
LA PARA CREEK 88.0
END DESCRIPTION:
XS GIS Cut Line= 3
      2308109.25     13319212.26      2306511.71     13319348.73
      2305082.08     13320107.77
#Sta/Elev= 30
  3740.4  251.67  3822.2   252.4  3974.2  247.21  4088.1  240.11  4213.6  228.78
  4243.8  228.34  4504.7  211.66  4645.2  206.89  4796.9  205.92  4825.9  201.68
    4856  201.18  4896.1  205.28  4905.8  201.69  4926.2   198.2  4966.4   199.3
  4993.5   197.2  4996.2   196.7  4999.5   197.2  5066.7  197.97  5076.8  200.74
  5116.9   202.8  5167.1  201.19  5287.5  204.75  5494.7   205.5  5676.6  213.09
  5767.2  213.69  5959.7  210.15  6089.7  212.95  6948.4  241.99  6962.4   242.7
#Mann= 5 ,-1 , 0
  3740.4      .1       0  4993.5     .07       0  4999.5      .1       0
  6089.7     .05       0  6948.4      .1       0
Bank Sta=4993.5,4999.5
XS Rating Curve= 0 ,0
Exp/Cntr=0.3,0.1

Type RM Length L Ch R = 1 ,51008   ,735,735,735
BEGIN DESCRIPTION:
LA PARA CREEK 87.0
END DESCRIPTION:
XS GIS Cut Line= 3
      2306937.74     13318296.82      2306387.72     13319046.85
      2305291.31     13319725.22
#Sta/Elev= 30
  4099.5  240.73  4514.4  217.91  4593.9  215.26  4715.1  215.02  4850.9  209.97
  4904.5  199.39  4925.6  197.68  4942.8  195.92  4957.4  196.82    4993  194.66
  4998.4  192.84  5001.2  192.34  5004.4  192.84  5043.2   198.8  5058.5  200.05
  5079.8  199.43  5137.7  203.25  5189.7  202.53  5370.6  203.58  5415.5  204.55
  5537.2  210.77  5573.8  211.18  5641.1  210.21  5668.4  205.81  5676.4  209.01
  5683.8  209.65  5732.1     211  5799.6  212.42  6076.2  226.58  6318.9  235.69
#Mann= 6 ,-1 , 0
  4099.5      .1       0  4904.5     .16       0  4925.6      .1       0
  4998.4     .07       0  5004.4      .1       0  5732.1     .05       0
Bank Sta=4998.4,5004.4
XS Rating Curve= 0 ,0
Exp/Cntr=0.3,0.1

Type RM Length L Ch R = 1 ,50273   ,317,317,317
BEGIN DESCRIPTION:
LA PARA CREEK 86.0
END DESCRIPTION:
XS GIS Cut Line= 4
      2306810.65     13318295.59       2305866.2     13318628.93
      2305470.37     13318976.15       2305241.2      13319656.7
#Sta/Elev= 30
  3900.5  233.79    3945   231.9  4115.7  220.76  4130.6  220.55  4254.3  211.87
  4317.2   208.9  4429.3  204.69  4539.9     203  4601.1  203.25  4820.5  201.26
  4904.5  199.47  4941.7  197.12  4955.9  194.48  4995.6  191.92  4998.4  191.42
  5001.6  191.92  5012.9   193.6  5041.3     193  5055.6  195.05  5076.5  196.32
    5084  198.46  5090.7  199.16  5176.1  203.23  5225.4  204.14  5303.2  207.25
  5331.7  207.32    5427  210.96  5480.4  211.05  5989.6  233.17  6146.7  236.75
#Mann= 7 ,-1 , 0
  3900.5      .1       0  4601.1     .05       0  4820.5     .16       0
  4904.5      .1       0  4995.6     .07       0  5001.6      .1       0
  5303.2     .05       0
Bank Sta=4995.6,5001.6
XS Rating Curve= 0 ,0
Exp/Cntr=0.3,0.1

Type RM Length L Ch R = 1 ,49956   ,504,504,504
BEGIN DESCRIPTION:
LA PARA CREEK 85.0
END DESCRIPTION:
XS GIS Cut Line= 3
      2306937.75     13318246.85      2305537.72     13318496.85
      2305237.71     13318896.87
#Sta/Elev= 30
  3610.2  242.15  3642.2  239.45  3696.1  237.51  3711.8   235.9  3843.9  229.17
  4039.4  217.29  4098.3  212.61    4206  206.82    4301   203.7  4427.5  202.11
  4667.2  201.69  4798.7   198.2  4844.3  198.21  4892.7  195.54    4941  197.09
  4946.5  195.87  4971.4  194.54  5002.5  189.85  5005.2  189.35  5008.5  189.85
  5012.1  191.19  5022.2  191.37  5035.5  193.28  5045.9   198.4  5054.3  199.93
  5060.5   208.5  5075.1  212.09    5162  210.42  5275.1  211.74  5532.4  217.67
#Mann= 6 ,-1 , 0
  3610.2      .1       0  4427.5     .05       0  4844.3      .1       0
  5002.5     .07       0  5008.5      .1       0    5162     .05       0
Bank Sta=5002.5,5008.5
XS Rating Curve= 0 ,0
Exp/Cntr=0.3,0.1

Type RM Length L Ch R = 1 ,49452   ,618,618,618
BEGIN DESCRIPTION:
LA PARA CREEK 84.0
END DESCRIPTION:
XS GIS Cut Line= 2
      2306900.95      13318031.7      2305102.53     13318073.37
#Sta/Elev= 30
  3711.9  235.03  3745.1  234.87  3985.2  226.72  4075.2  225.26  4135.2  219.77
  4315.3  205.95  4385.3  202.42  4482.3  200.63    4579   200.8  4685.4  199.15
  4735.4   196.8  4805.4  195.24  4905.4  197.46  4957.2  192.69  4985.5  190.73
  4999.2  188.76  5012.1  189.45  5014.1   188.7  5016.9   188.2  5020.1   188.7
  5055.5  195.02  5065.5  198.32  5075.5   207.4  5095.5  212.84  5100.8  212.71
  5125.5  212.64  5185.5   215.5  5265.5  216.95  5395.6  215.08  5510.8   214.9
#Mann= 8 ,-1 , 0
  3711.9      .1       0  4482.3     .05       0    4579      .1       0
  4957.2     .16       0  4999.2      .1       0  5014.1     .07       0
  5020.1      .1       0  5100.8     .05       0
Bank Sta=5014.1,5020.1
XS Rating Curve= 0 ,0
Exp/Cntr=0.3,0.1

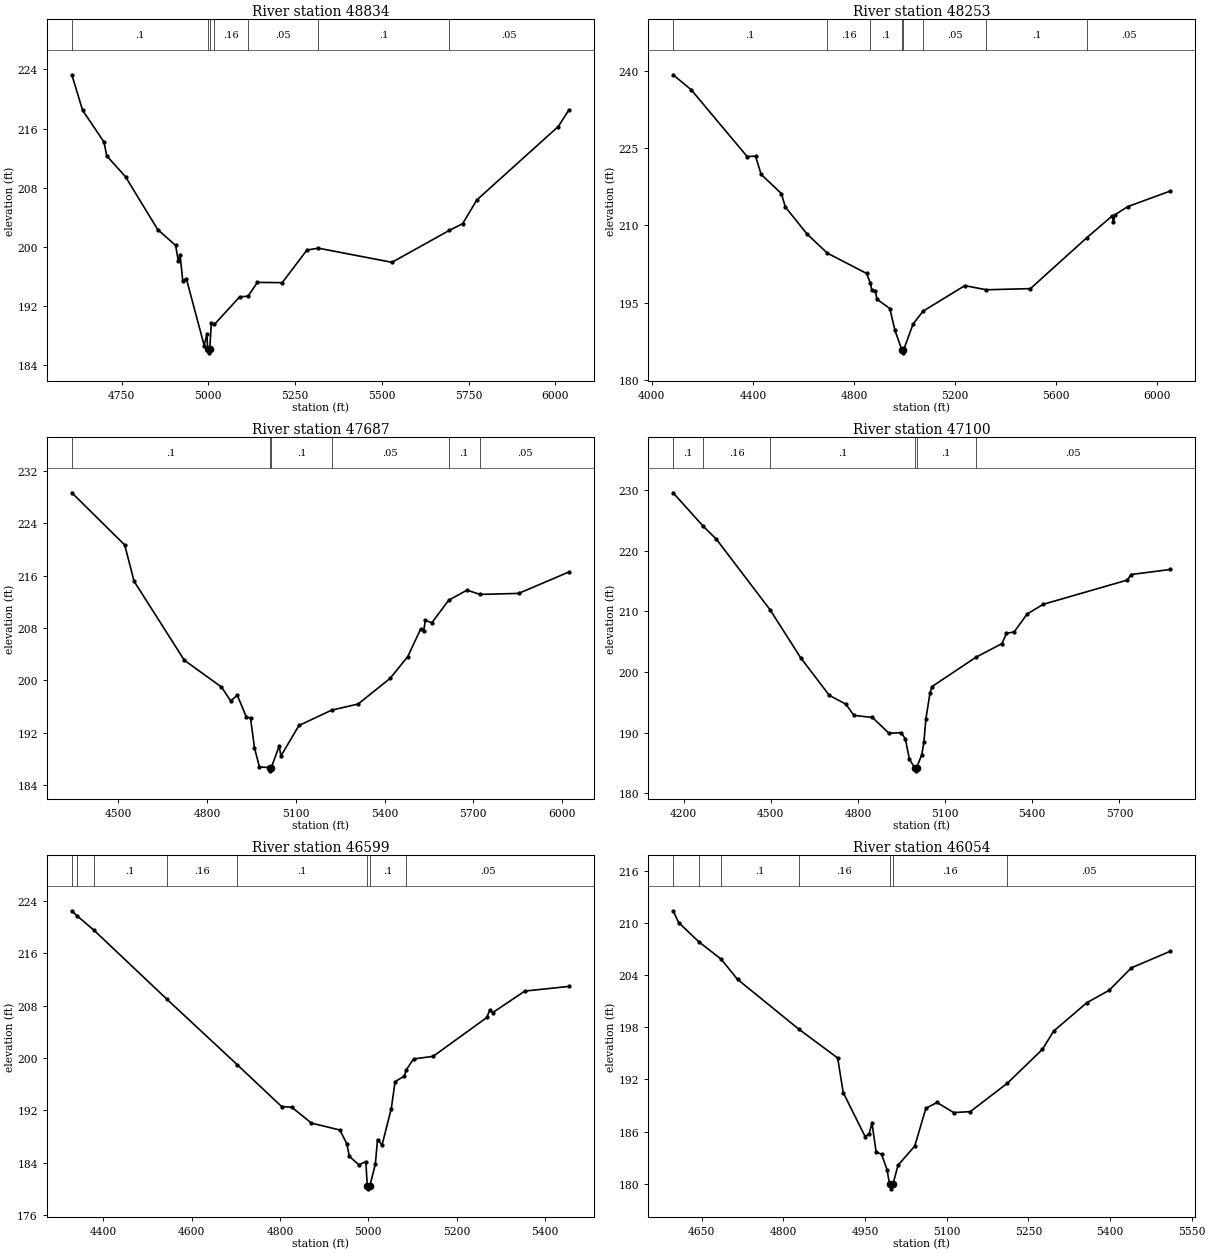
Type RM Length L Ch R = 1 ,48834   ,581,581,581
BEGIN DESCRIPTION:
LA PARA CREEK 83.0
END DESCRIPTION:
XS GIS Cut Line= 3
      2306387.76     13317496.84      2305987.72     13317596.85
      2304987.68     13317796.86
#Sta/Elev= 30
  4606.6  223.27  4637.6  218.47  4699.4  214.18  4707.1  212.32  4761.3  209.49
    4854  202.36  4905.6  200.21  4913.3  198.13  4918.5  198.96  4926.2  195.42
  4936.5  195.72    4988  186.69  4995.8  188.24  4997.9   186.2  5000.7   185.7
  5003.9   186.2  5008.6  189.74  5017.6  189.55  5090.3  193.27  5114.3  193.35
  5141.3  195.22  5212.7  195.18  5284.1  199.59  5317.1  199.84  5528.9  197.93
  5694.5  202.25  5732.8  203.16  5773.6  206.36  6008.2  216.28  6038.8  218.52
#Mann= 7 ,-1 , 0
  4606.6      .1       0  4997.9     .07       0  5003.9      .1       0
  5017.6     .16       0  5114.3     .05       0  5317.1      .1       0
  5694.5     .05       0
Bank Sta=4997.9,5003.9
XS Rating Curve= 0 ,0
Exp/Cntr=0.3,0.1

Type RM Length L Ch R = 1 ,48253   ,566,566,566
BEGIN DESCRIPTION:
LA PARA CREEK 82.0
END DESCRIPTION:
XS GIS Cut Line= 3
      2306727.27     13317191.42      2306018.98     13317045.59
      2304803.74     13317309.47
#Sta/Elev= 30
    4084  239.22    4155  236.35  4376.9  223.37  4410.2  223.44  4432.4   219.9
  4512.3   216.2  4527.9   213.6  4614.4  208.32  4694.3  204.64  4849.4  200.71
  4864.6  198.84  4869.8  197.51  4884.5  197.37  4890.3  195.71  4941.5   193.9
  4961.9  189.65  4989.6  185.81  4992.4  185.31  4995.6  185.81  5033.6  190.91
    5073  193.39  5238.2  198.34    5323  197.54  5497.8  197.76  5720.4  207.61
  5821.3  211.85  5826.5  210.65  5831.7  212.05  5882.9  213.66  6050.7  216.67
#Mann= 8 ,-1 , 0
    4084      .1       0  4694.3     .16       0  4864.6      .1       0
  4989.6     .07       0  4995.6      .1       0    5073     .05       0
    5323      .1       0  5720.4     .05       0
Bank Sta=4989.6,4995.6
XS Rating Curve= 0 ,0
Exp/Cntr=0.3,0.1

Type RM Length L Ch R = 1 ,47687   ,587,587,587
BEGIN DESCRIPTION:
LA PARA CREEK 81.0
END DESCRIPTION:
XS GIS Cut Line= 3
      2305859.27     13316087.23      2305456.48     13316885.87
      2304769.01      13317267.8
#Sta/Elev= 30
  4342.4  228.67  4521.2   220.7    4553  215.15  4722.8  203.09  4848.5     199
  4879.6  196.88    4902  197.75  4932.1  194.47  4946.8  194.21    4960  189.74
  4976.7  186.79    5011   186.7  5013.7   186.2    5017   186.7  5043.7  190.01
  5049.3  188.46  5110.6  193.13  5220.9  195.47  5310.4   196.4  5419.1  200.34
  5478.5  203.66    5522  207.86  5532.3  207.63    5538  209.19  5559.8  208.81
  5616.5  212.25  5678.7   213.8  5722.6  213.15  5853.2   213.3  6023.3  216.57
#Mann= 6 ,-1 , 0
  4342.4      .1       0    5011     .07       0    5017      .1       0
  5220.9     .05       0  5616.5      .1       0  5722.6     .05       0
Bank Sta=5011,5017
XS Rating Curve= 0 ,0
Exp/Cntr=0.3,0.1

Type RM Length L Ch R = 1 ,47100   ,501,501,501
BEGIN DESCRIPTION:
LA PARA CREEK 80.0
END DESCRIPTION:
XS GIS Cut Line= 3
      2305587.75     13315896.83      2304810.64     13316726.15
      2304692.66     13317288.29
#Sta/Elev= 30
  4163.9  229.59  4267.1  224.09  4312.7  221.94  4497.4   210.3  4602.5   202.4
  4701.5  196.16  4758.2  194.71  4786.5  192.85    4850  192.51  4906.7  189.91
  4949.1  189.99  4963.3  188.98  4977.5  185.58    4996   184.2  4998.7   183.7
    5002   184.2    5020  186.38  5027.3  188.53  5034.1  192.31  5048.3  196.57
  5055.2  197.61  5205.8  202.43    5296  204.71  5311.4  206.39  5337.9  206.63
  5382.7  209.59  5437.7  211.18  5726.8  215.18  5740.5   216.1  5874.8  216.93
#Mann= 6 ,-1 , 0
  4163.9      .1       0  4267.1     .16       0  4497.4      .1       0
    4996     .07       0    5002      .1       0  5205.8     .05       0
Bank Sta=4996,5002
XS Rating Curve= 0 ,0
Exp/Cntr=0.3,0.1

Type RM Length L Ch R = 1 ,46599   ,545,545,545
BEGIN DESCRIPTION:
LA PARA CREEK 79.0
END DESCRIPTION:
XS GIS Cut Line= 3
      2305337.75     13315746.84      2304737.72     13316096.85
      2304487.71     13316446.88
#Sta/Elev= 30
  4329.2  222.49  4341.4   221.7  4379.4  219.51  4543.6  209.02  4703.8  198.94
  4803.9  192.57    4827  192.46  4871.3  190.04  4935.8  188.98  4951.5  186.87
  4957.3  184.94  4978.8  183.66  4994.5  184.16  4997.7  180.49  5000.5  179.99
  5003.7  180.49    5016  183.76    5021  187.53  5031.2  186.69  5052.1  192.26
  5060.7  196.37  5081.6  197.23  5086.1  198.18  5102.5  199.84  5146.7  200.24
  5268.4  206.18  5274.6  207.26  5281.9  206.94  5354.4  210.22    5454  210.93
#Mann= 8 ,-1 , 0
  4329.2      .1       0  4341.4     .16       0  4379.4      .1       0
  4543.6     .16       0  4703.8      .1       0  4997.7     .07       0
  5003.7      .1       0  5086.1     .05       0
Bank Sta=4997.7,5003.7
XS Rating Curve= 0 ,0
Exp/Cntr=0.3,0.1

Type RM Length L Ch R = 1 ,46054   ,690,690,690
BEGIN DESCRIPTION:
LA PARA CREEK 78.0
END DESCRIPTION:
XS GIS Cut Line= 3
      2305087.71     13315496.86      2304687.72     13315546.85
      2304187.73     13315646.85
#Sta/Elev= 30
  4597.5   211.4  4607.6  210.05  4644.5  207.85  4685.7  205.84  4715.9  203.51
  4828.3  197.79  4899.8  194.47  4909.9   190.5  4950.2  185.43  4957.8  185.78
  4962.8     187  4970.4  183.66  4980.4   183.4  4990.5  181.62  4995.1  179.92
  4997.8  179.42  5001.1  179.92  5010.8  182.15  5041.4  184.34  5061.8  188.68
  5082.2  189.35  5112.8  188.19  5143.4   188.3  5211.7  191.58    5276  195.47
  5296.3  197.55  5357.5  200.83  5398.3  202.25  5439.1  204.83  5510.5  206.74
#Mann= 7 ,-1 , 0
  4597.5      .1       0  4644.5     .16       0  4685.7      .1       0
  4828.3     .16       0  4995.1     .07       0  5001.1     .16       0
  5211.7     .05       0
Bank Sta=4995.1,5001.1
XS Rating Curve= 0 ,0
Exp/Cntr=0.3,0.1

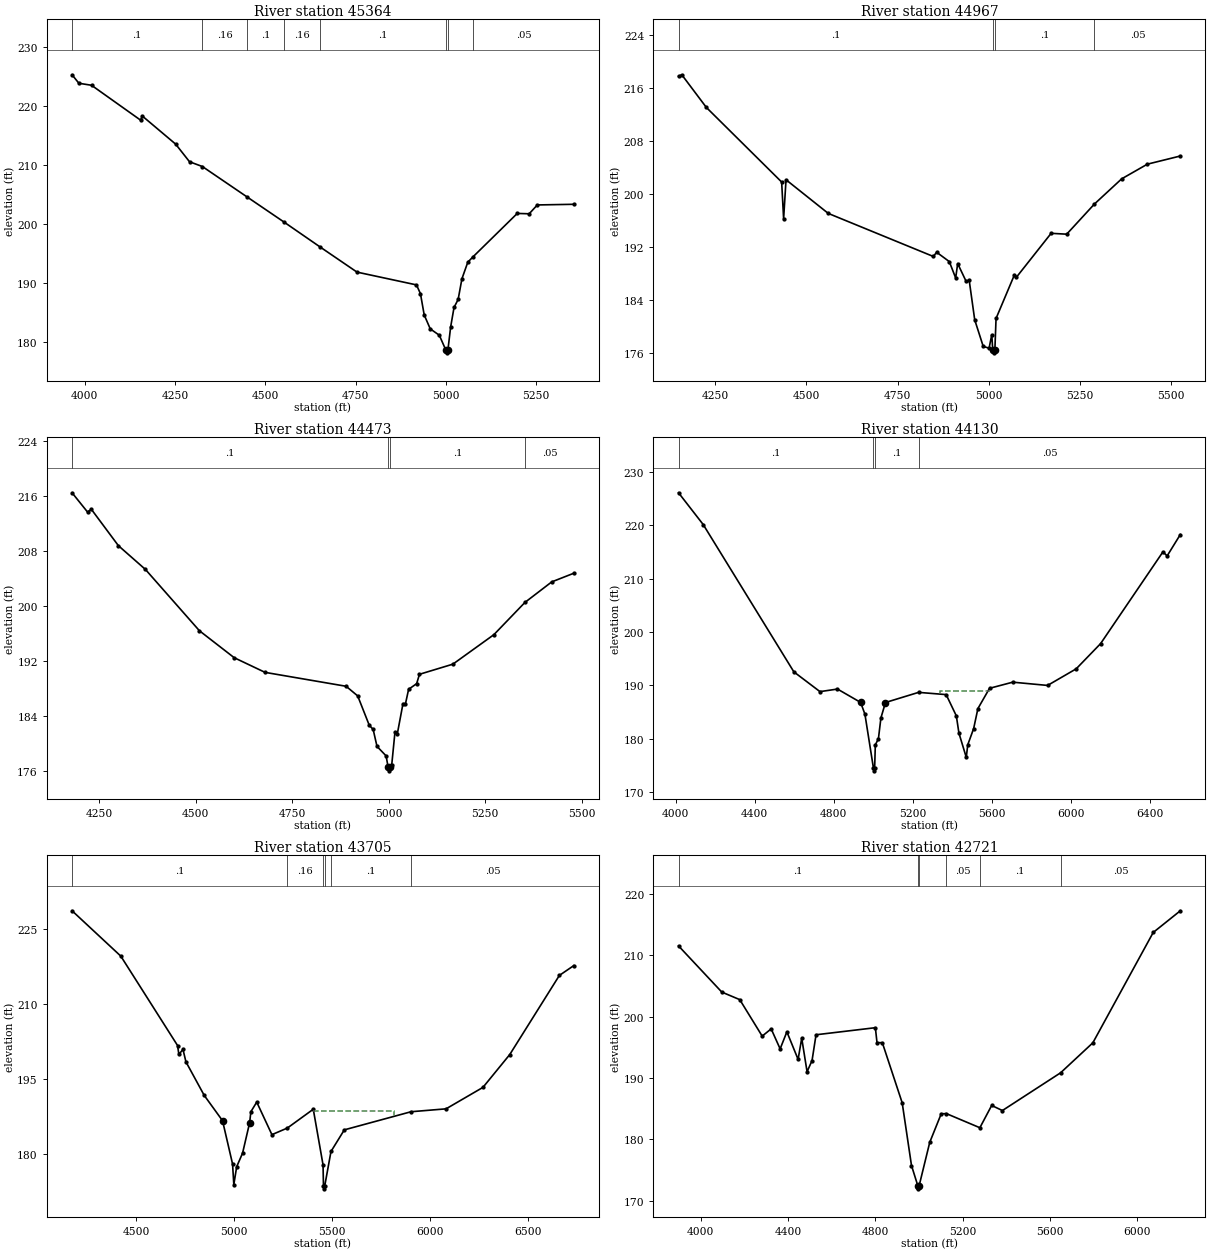
Type RM Length L Ch R = 1 ,45364   ,397,397,397
BEGIN DESCRIPTION:
LA PARA CREEK 77.0
END DESCRIPTION:
XS GIS Cut Line= 3
      2305366.18     13315073.37       2304616.2      13314906.7
      2304020.88     13315086.68
#Sta/Elev= 30
  3964.6   225.3  3983.5  223.86  4018.5  223.52  4154.2  217.61  4159.4  218.29
  4251.6  213.53    4290  210.54  4325.6  209.73  4450.6  204.52  4550.5  200.36
  4650.5  196.13    4754  191.81  4918.8  189.64  4929.8  188.15  4940.2  184.54
  4956.9  182.18    4982   181.1  4999.9  178.61  5002.7  178.11  5005.9  178.61
  5013.4  182.49  5022.8  185.81  5034.2  187.17  5044.7  190.68    5061   193.5
    5076  194.44    5198  201.77    5231  201.71  5253.6  203.21  5354.8  203.32
#Mann= 8 ,-1 , 0
  3964.6      .1       0  4325.6     .16       0  4450.6      .1       0
  4550.5     .16       0  4650.5      .1       0  4999.9     .07       0
  5005.9      .1       0    5076     .05       0
Bank Sta=4999.9,5005.9
XS Rating Curve= 0 ,0
Exp/Cntr=0.3,0.1

Type RM Length L Ch R = 1 ,44967   ,494,494,494
BEGIN DESCRIPTION:
LA PARA CREEK 76.0
END DESCRIPTION:
XS GIS Cut Line= 3
      2305137.74     13314246.84      2304337.72     13314596.85
      2303837.75     13314546.86
#Sta/Elev= 30
  4149.4  217.75  4158.4  217.98  4225.8  213.05  4432.1  201.82  4437.5  196.29
  4444.1  202.16  4559.9  197.09    4848   190.6    4857  191.24  4891.7  189.83
  4909.2  187.36  4914.7  189.53    4938  186.83  4946.2  187.04  4961.4  181.05
  4984.8  177.04  5000.8  176.79  5008.2  178.81  5010.7  176.58  5013.4  176.08
  5016.7  176.58  5019.9  181.26  5070.4  187.85  5075.4  187.45  5170.9  194.09
  5213.6  193.96  5289.7  198.51  5364.3   202.3  5434.7  204.51  5525.1  205.74
#Mann= 4 ,-1 , 0
  4149.4      .1       0  5010.7     .07       0  5016.7      .1       0
  5289.7     .05       0
Bank Sta=5010.7,5016.7
XS Rating Curve= 0 ,0
Exp/Cntr=0.3,0.1

Type RM Length L Ch R = 1 ,44473   ,343,343,343
BEGIN DESCRIPTION:
LA PARA CREEK 75.0
END DESCRIPTION:
XS GIS Cut Line= 3
      2305087.74     13314096.85      2304287.72     13314096.85
      2303887.73     13314396.84
#Sta/Elev= 30
  4179.7  216.46  4219.7  213.67  4229.7  214.06  4299.7  208.78  4369.7  205.33
  4509.7  196.42  4599.7  192.51  4679.7  190.38  4889.7  188.36  4919.7  186.96
  4949.7  182.69  4959.7   182.1  4969.7  179.63  4993.3  178.25  4998.6  176.58
  5001.3  176.08  5004.6  176.58  5007.8  176.92  5016.2  181.68  5022.4  181.47
    5037  185.84  5043.3  185.78  5051.6  187.92  5072.4  188.74  5079.7   190.1
  5166.2  191.57  5272.4  195.85    5353  200.54  5422.4  203.52  5479.7  204.78
#Mann= 4 ,-1 , 0
  4179.7      .1       0  4998.6     .07       0  5004.6      .1       0
    5353     .05       0
Bank Sta=4998.6,5004.6
XS Rating Curve= 0 ,0
Exp/Cntr=0.3,0.1

Type RM Length L Ch R = 1 ,44130   ,425,425,425
BEGIN DESCRIPTION:
LA PARA CREEK 74.0
END DESCRIPTION:
XS GIS Cut Line= 3
      2305270.14     13314042.16      2304535.73     13313896.32
      2302987.72     13312996.86
#Sta/Elev= 30
  4014.4  226.06  4139.2  220.11    4598  192.51  4730.1  188.81  4818.7  189.29
  4935.7  186.79  4957.5  184.59  5000.7  174.47  5003.5  173.97  5006.7  174.47
  5010.2  178.83  5025.9     180  5038.4  183.87  5061.5  186.77  5229.1  188.67
  5368.6  188.25  5420.1  184.27  5433.2  181.04  5470.4  176.49  5477.9  178.85
  5507.7  181.89  5529.2  185.63    5588  189.43  5705.5  190.58  5881.8  189.97
  6026.6  193.08    6150   197.8  6465.3  214.98  6486.9  214.24  6553.5  218.24
#Mann= 4 ,-1 , 0
  4014.4      .1       0  5000.7     .07       0  5006.7      .1       0
  5229.1     .05       0
#XS Ineff= 1 ,-1
 5335.94 5591.41   188.9
Permanent Ineff=
       F
Bank Sta=4935.7,5061.5
XS Rating Curve= 0 ,0
Exp/Cntr=0.3,0.1

Type RM Length L Ch R = 1 ,43705   ,984,984,984
BEGIN DESCRIPTION:
LA PARA CREEK 73.0
END DESCRIPTION:
XS GIS Cut Line= 4
      2305426.36     13313714.03      2304947.19      13313698.4
      2304551.36     13313437.98      2303027.75     13312921.21
#Sta/Elev= 30
  4171.6  228.71  4420.4  219.63  4710.2  201.73  4716.9  199.95  4737.9  200.95
    4753  198.46  4846.4  191.74  4939.8  186.68    4991  178.02  4997.5  173.88
  5012.1  177.46  5042.2  180.18  5078.4   186.3  5084.4  188.46  5114.5   190.4
    5192  183.88  5270.7   185.2  5403.2  188.97    5453  177.84  5455.3  173.53
    5458  173.03  5461.3  173.53  5493.6  180.51  5561.6  184.84  5902.4  188.47
  6081.1  189.05  6269.6  193.35  6406.4  199.92  6659.8  215.77  6733.7  217.74
#Mann= 6 ,-1 , 0
  4171.6      .1       0  5270.7     .16       0  5455.3     .07       0
  5461.3     .16       0  5493.6      .1       0  5902.4     .05       0
#XS Ineff= 1 ,-1
 5403.91 5816.41  188.71
Permanent Ineff=
       F
Bank Sta=4939.8,5078.4
XS Rating Curve= 0 ,0
Exp/Cntr=0.3,0.1

Type RM Length L Ch R = 1 ,42721   ,404,404,404
BEGIN DESCRIPTION:
LA PARA CREEK 72.0
END DESCRIPTION:
XS GIS Cut Line= 4
      2305280.51     13312943.19      2304473.23     13312750.48
      2303807.62     13312965.32      2303056.56     13312797.36
#Sta/Elev= 30
  3898.3  211.52  4096.5     204  4178.8  202.77  4281.6  196.83  4322.7  198.01
  4363.8  194.75  4394.7  197.53  4446.1  193.04  4462.7  196.49  4487.2  191.03
    4510  192.85  4528.3  197.05  4800.1   198.2  4807.6  195.78  4832.1  195.75
    4923  185.97  4965.6  175.76  4994.6  172.46  4997.3  171.96  5000.6  172.46
  5049.3  179.54  5101.8  184.18  5125.5  184.21  5278.9  181.91    5333  185.54
  5382.1  184.71  5648.9  190.86  5796.5  195.74  6073.1  213.71  6197.3  217.24
#Mann= 6 ,-1 , 0
  3898.3      .1       0  4994.6     .07       0  5000.6      .1       0
  5125.5     .05       0  5278.9      .1       0  5648.9     .05       0
Bank Sta=4994.6,5000.6
XS Rating Curve= 0 ,0
Exp/Cntr=0.3,0.1

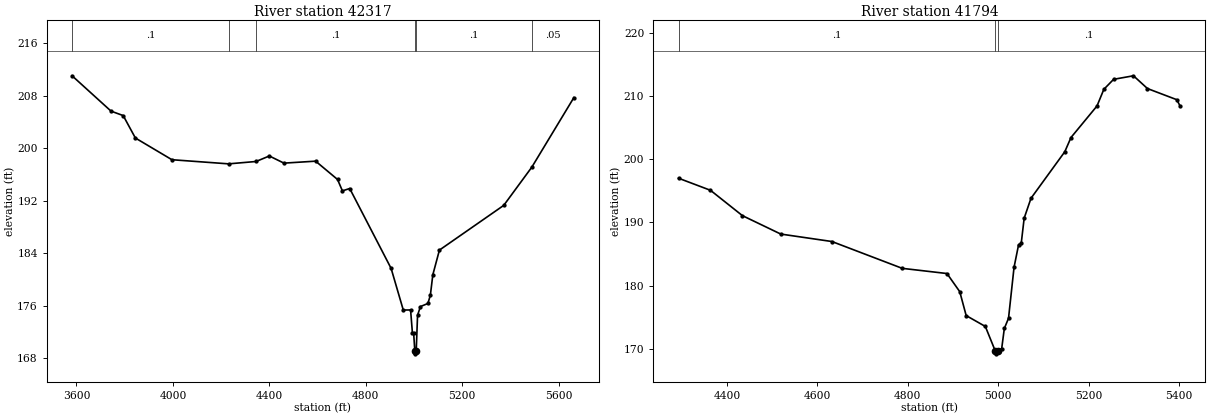
Type RM Length L Ch R = 1 ,42317   ,523,523,523
BEGIN DESCRIPTION:
LA PARA CREEK 71.0
END DESCRIPTION:
XS GIS Cut Line= 3
      2305337.73     13312746.86      2303937.72     13312546.85
      2303287.73     13312696.85
#Sta/Elev= 30
  3581.8  211.04  3743.4  205.65  3793.9  204.97  3844.4  201.55    3996  198.24
  4231.2  197.61  4344.8  197.97    4400  198.81  4460.6  197.72    4592  198.02
  4682.9  195.23  4703.1  193.49  4733.4  193.85  4905.1  181.67  4955.6  175.32
  4985.9  175.33  4993.5  171.81  4998.6  171.81  5003.3  169.14    5006  168.64
  5009.3  169.14  5014.8  174.52  5026.8  175.85  5057.6  176.32  5067.9  177.57
  5078.1  180.69  5105.5  184.46  5372.3  191.28  5488.8  197.11  5663.1  207.71
#Mann= 6 ,-1 , 0
  3581.8      .1       0  4231.2     .05       0  4344.8      .1       0
  5003.3     .07       0  5009.3      .1       0  5488.8     .05       0
Bank Sta=5003.3,5009.3
XS Rating Curve= 0 ,0
Exp/Cntr=0.3,0.1

Type RM Length L Ch R = 1 ,41794   ,510,510,510
BEGIN DESCRIPTION:
LA PARA CREEK 70.0
END DESCRIPTION:
XS GIS Cut Line= 3
       2304387.7     13312546.83      2303887.72     13312046.85
      2303537.71     13311846.85
#Sta/Elev= 30
  4292.8  196.99  4363.5  195.08  4434.2  191.07    4519  188.16  4632.2  186.98
  4787.7  182.74  4886.7  181.92    4915  179.05  4929.2  175.27  4971.6  173.55
  4993.3  169.72  4996.1  169.22  4999.3  169.72  5007.8  170.06  5013.6  173.23
  5022.9  174.85  5035.1   182.9  5045.2  186.49    5051  186.69  5057.5  190.67
  5072.6  193.82  5147.4  201.18  5161.1  203.43  5218.7  208.42  5233.8  211.05
  5255.4  212.63  5299.3  213.19  5330.3  211.17  5395.1  209.41    5403  208.34
#Mann= 3 ,-1 , 0
  4292.8      .1       0  4993.3     .07       0  4999.3      .1       0
Bank Sta=4993.3,4999.3
XS Rating Curve= 0 ,0
Exp/Cntr=0.3,0.1