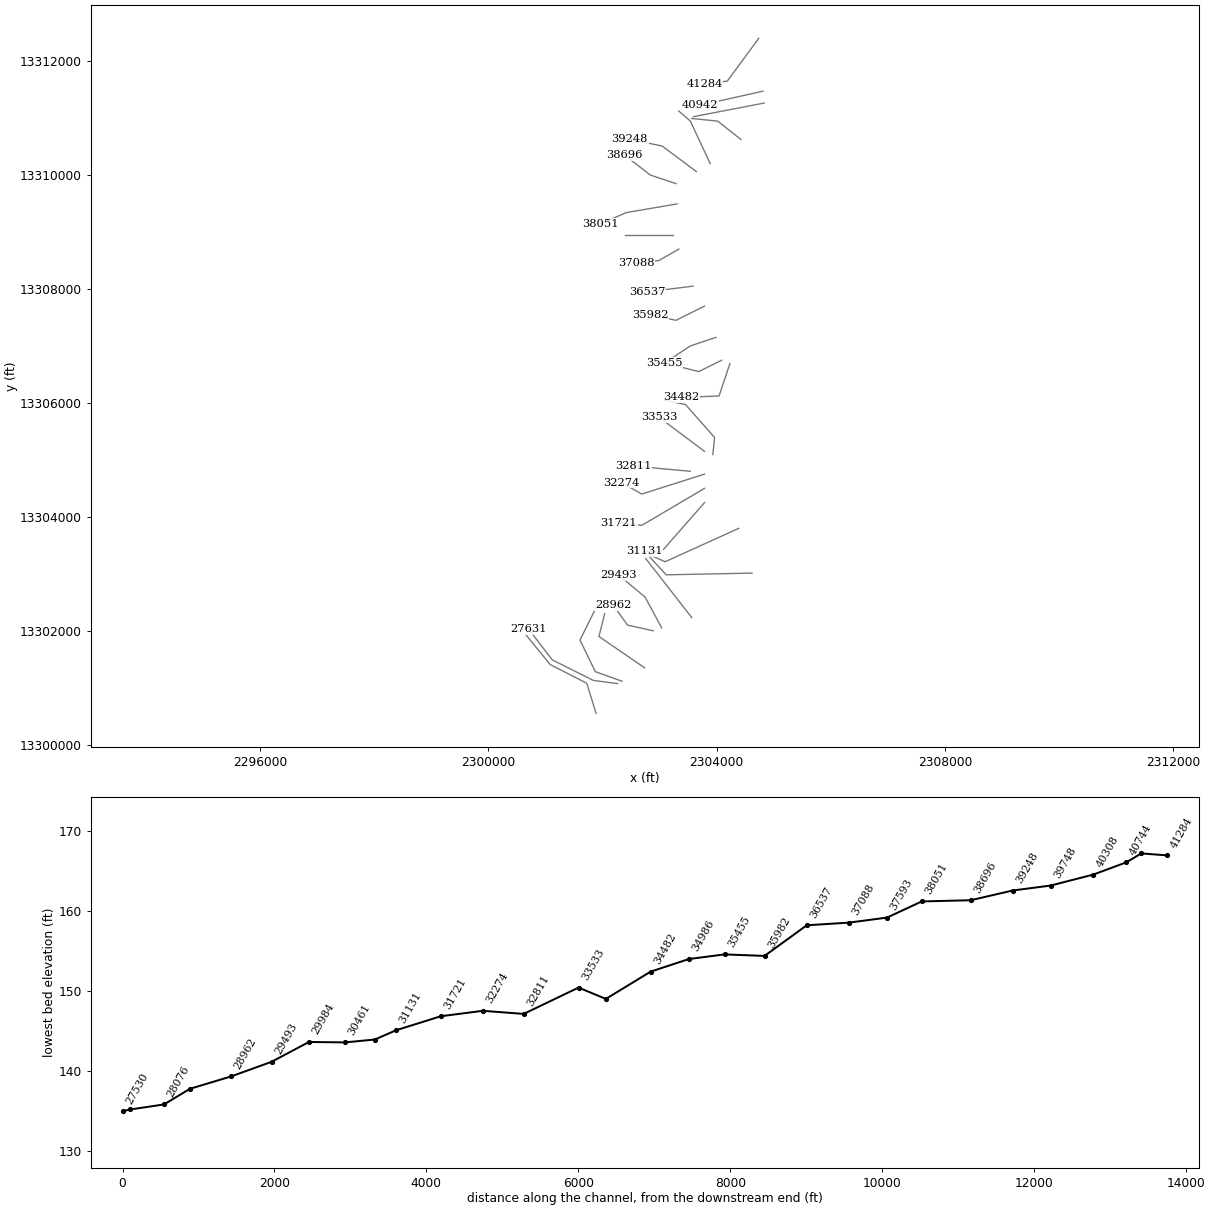
HEC-RAS study LA PARA CREEK.prj: LA PARA CREEK Base Level Engineering

--- LA PARA CREEK.g01 (geometry) --- (continued)

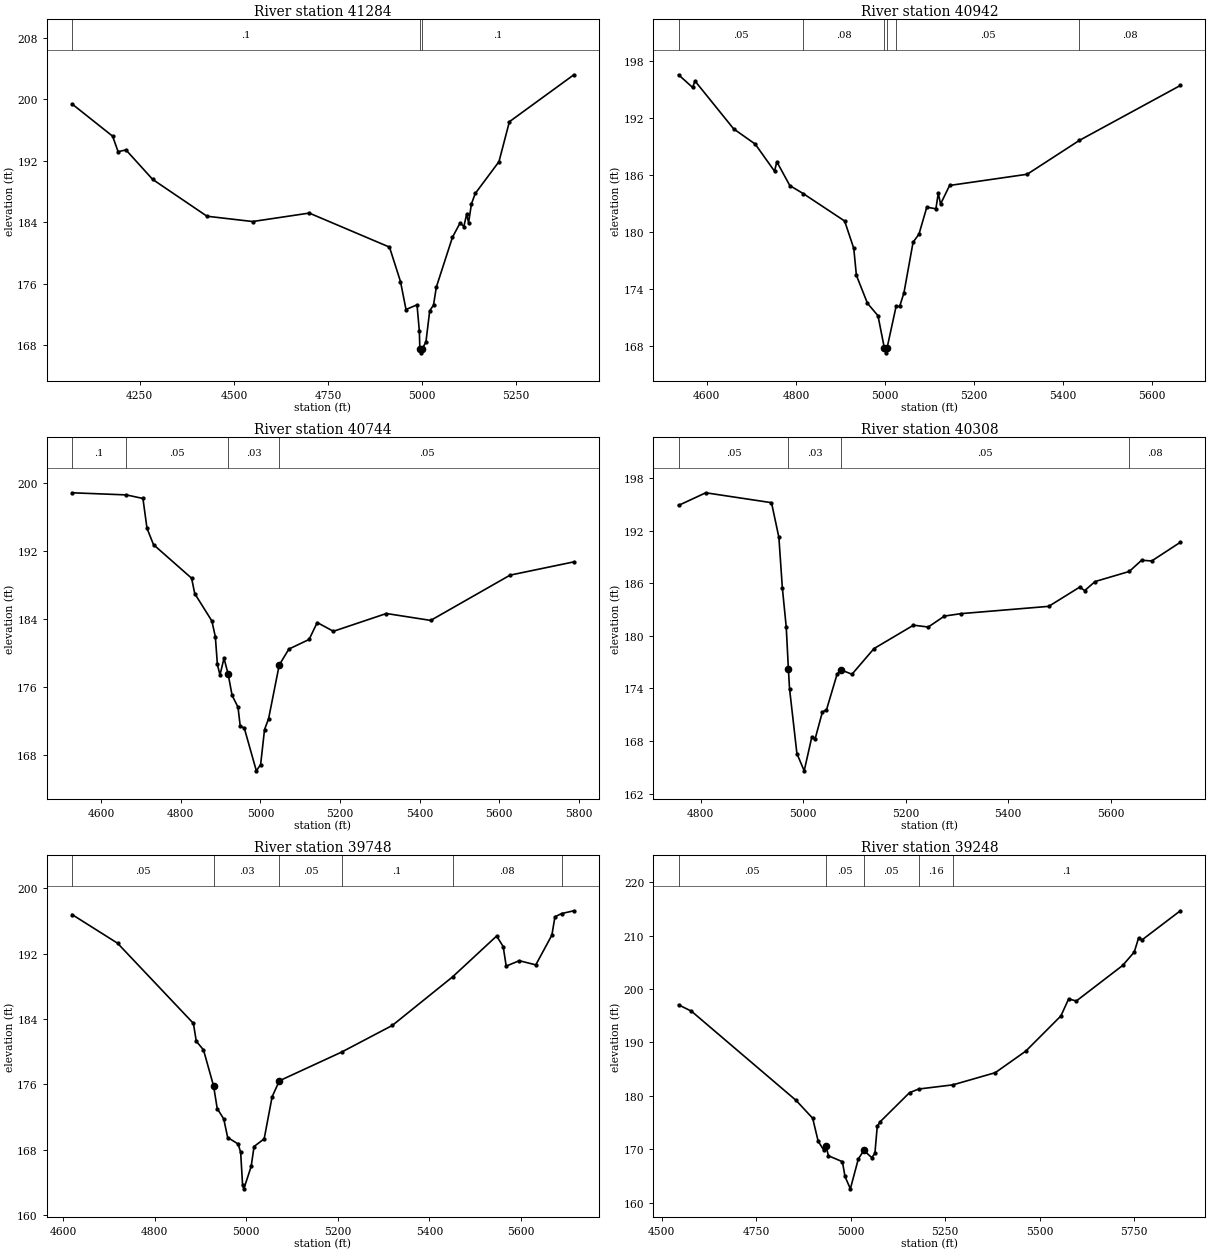
Type RM Length L Ch R = 1 ,41284   ,342,342,342
BEGIN DESCRIPTION:
LA PARA CREEK 69.0
END DESCRIPTION:
XS GIS Cut Line= 3
      2304737.73     13312396.87      2304187.72     13311646.85
      2303787.71     13311596.85
#Sta/Elev= 30
  4070.1  199.39  4177.8   195.2  4192.4  193.18  4213.3  193.41  4284.3  189.57
  4428.6  184.78  4549.8  184.09  4700.3  185.19  4913.4  180.76  4942.7  176.28
  4957.3  172.64  4986.6  173.25  4992.8  169.81  4994.1   167.5  4996.8     167
  5000.1   167.5  5010.3  168.41  5020.3  172.47  5030.4  173.22    5038  175.57
  5080.8  182.05    5101   183.9    5111  183.44  5118.6  185.06  5123.6  183.94
  5131.2  186.39  5141.3  187.74  5204.3  191.88    5232  197.08  5403.3  203.19
#Mann= 3 ,-1 , 0
  4070.1      .1       0  4994.1     .07       0  5000.1      .1       0
Bank Sta=4994.1,5000.1
XS Rating Curve= 0 ,0
Exp/Cntr=0.3,0.1

Type RM Length L Ch R = 1 ,40942   ,198,198,198
BEGIN DESCRIPTION:
LA PARA CREEK 68.0
END DESCRIPTION:
XS GIS Cut Line= 2
      2304811.73     13311469.22      2303712.11     13311223.24
#Sta/Elev= 30
  4536.4  196.57  4568.1  195.23  4573.3  195.92  4660.1  190.87  4708.6  189.26
    4752   186.4  4757.1   187.4  4786.4  184.88  4816.2  184.05  4909.4  181.15
  4929.9  178.26  4935.8  175.42  4960.6  172.48  4984.3  171.16  4998.6  167.75
  5001.4  167.25  5004.6  167.75    5025  172.16  5032.9  172.14  5042.6  173.58
  5063.1  178.92  5076.3  179.76  5093.9  182.61  5114.3  182.44  5119.7  184.08
  5124.8  182.94  5145.1   184.9  5319.3  186.08  5436.5  189.65  5663.2  195.44
#Mann= 6 ,-1 , 0
  4536.4     .05       0  4816.2     .08       0  4998.6     .07       0
  5004.6     .08       0    5025     .05       0  5436.5     .08       0
Bank Sta=4998.6,5004.6
XS Rating Curve= 0 ,0
Exp/Cntr=0.3,0.1

Type RM Length L Ch R = 1 ,40744   ,436,436,436
BEGIN DESCRIPTION:
LA PARA CREEK 67.0
END DESCRIPTION:
XS GIS Cut Line= 2
      2304832.62      13311260.9      2303594.44     13311021.59
#Sta/Elev= 30
  4526.7  198.81  4663.3  198.56  4704.8  198.14    4715  194.64  4731.4  192.71
  4827.1  188.77    4835  186.96    4878  183.75  4886.8  181.88  4891.9  178.64
  4898.4  177.39  4908.5  179.36  4918.7  177.55  4928.9     175  4943.7  173.62
  4949.3  171.39  4959.5  171.16  4989.8  166.13  5000.6  166.87  5010.4  170.98
  5020.6  172.26  5047.3  178.56  5071.5  180.44  5122.4  181.57  5142.8  183.56
  5183.5  182.53  5316.6  184.62    5428  183.81  5627.5  189.13  5787.8  190.69
#Mann= 4 ,-1 , 0
  4526.7      .1       0  4663.3     .05       0  4918.7     .03       0
  5047.3     .05       0
Bank Sta=4918.7,5047.3
XS Rating Curve= 0 ,0
Exp/Cntr=0.3,0.1

Type RM Length L Ch R = 1 ,40308   ,560,560,560
BEGIN DESCRIPTION:
Mapping XS 7972c9d3
END DESCRIPTION:
XS GIS Cut Line= 3
      2304426.33      13310620.3      2304020.11     13310943.19
      2303562.21     13310990.02
#Sta/Elev= 30
    4757  194.88  4810.2  196.32  4938.4  195.19  4952.8  191.24  4959.6  185.46
  4967.2  180.98 4971.37  176.22  4973.6  173.97    4988  166.56  5002.2  164.59
  5016.9   168.4  5023.5  168.23  5037.7   171.3  5045.7  171.55  5066.5  175.64
  5074.6   176.1  5095.4  175.61  5138.4  178.54  5215.5  181.21  5244.3     181
  5275.9  182.25  5308.5  182.53  5479.4  183.36  5539.7  185.55  5549.7  185.16
  5569.8  186.19  5636.5  187.34  5660.6  188.62  5680.4  188.54  5736.2  190.67
#Mann= 4 ,-1 , 0
    4757     .05       0 4971.37     .03       0  5074.6     .05       0
  5636.5     .08       0
Bank Sta=4971.37,5074.6
XS Rating Curve= 0 ,0
Exp/Cntr=0.3,0.1

Type RM Length L Ch R = 1 ,39748   ,500,500,500
BEGIN DESCRIPTION:
LA PARA CREEK 66.0
END DESCRIPTION:
XS GIS Cut Line= 3
      2303887.73     13310196.84      2303537.72     13310946.85
      2303335.25      13311122.2
#Sta/Elev= 30
  4619.9  196.79  4719.2  193.28  4884.8  183.47  4891.1  181.28  4906.8  180.23
  4928.9   175.8  4936.8  173.04    4951  171.78  4959.6   169.5  4982.5  168.71
    4988  167.67  4992.1  163.72  4994.9  163.22  5010.9  165.96  5017.2   168.4
  5039.3  169.34  5056.6  174.48  5072.4  176.44  5208.5  179.96  5319.1  183.22
  5450.6  189.16  5546.8  194.16  5561.1  192.87  5567.7  190.48  5596.2  191.14
  5632.3  190.63  5667.4  194.27  5674.1  196.51  5688.5  196.91  5715.4  197.25
#Mann= 6 ,-1 , 0
  4619.9     .05       0  4928.9     .03       0  5072.4     .05       0
  5208.5      .1       0  5450.6     .08       0  5688.5     .05       0
Bank Sta=4928.9,5072.4
XS Rating Curve= 0 ,0
Exp/Cntr=0.3,0.1

Type RM Length L Ch R = 1 ,39248   ,552,552,552
BEGIN DESCRIPTION:
LA PARA CREEK 65.0
END DESCRIPTION:
XS GIS Cut Line= 3
      2303645.09     13310057.78      2303046.15     13310505.69
      2302478.45     13310625.48
#Sta/Elev= 30
  4544.6  197.04  4578.7  195.85  4855.8  179.15  4899.6  175.81  4914.2  171.51
  4928.4  169.91  4935.1  170.57  4941.3  168.79  4978.4  167.68  4985.1  164.92
  4999.4   162.6  5020.5  168.21  5035.1  169.78  5055.9  168.45  5064.3  169.22
  5070.5  174.27  5078.3  175.16    5156   180.6  5180.3  181.28  5270.7  182.06
  5382.9  184.34  5463.6  188.37  5556.6  194.96  5577.1  198.14  5597.5  197.76
  5720.1  204.41  5750.8  206.92  5762.2  209.55  5771.2  209.18  5872.7  214.64
#Mann= 5 ,-1 , 0
  4544.6     .05       0  4935.1     .05       0  5035.1     .05       0
  5180.3     .16       0  5270.7      .1       0
Bank Sta=4935.1,5035.1
XS Rating Curve= 0 ,0
Exp/Cntr=0.3,0.1

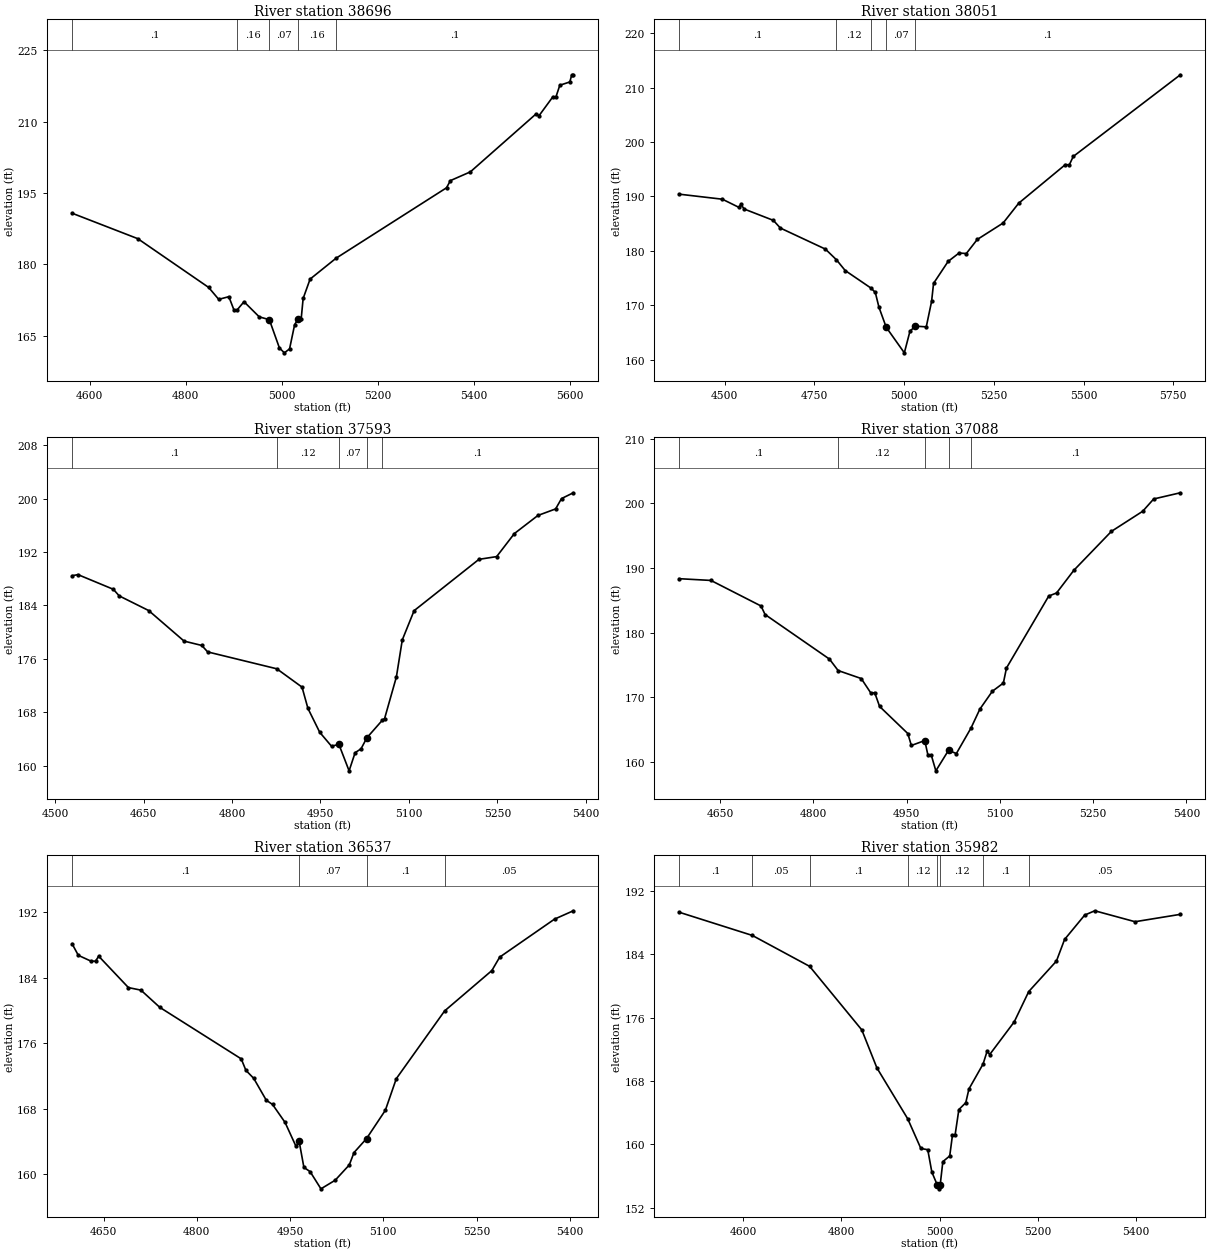
Type RM Length L Ch R = 1 ,38696   ,645,645,645
BEGIN DESCRIPTION:
LA PARA CREEK 64.0
END DESCRIPTION:
XS GIS Cut Line= 3
      2303287.68     13309846.87      2302837.72     13309996.85
      2302387.71     13310346.86
#Sta/Elev= 30
  4563.4  190.75  4700.4  185.39    4848  175.14    4869  172.63  4890.1  173.19
  4900.7  170.41  4907.7  170.45  4921.7  172.13  4953.4  168.95  4974.5  168.35
  4995.5   162.4  5005.8  161.38  5016.6  162.21  5027.2  167.31  5035.1   168.6
  5040.9   168.6  5044.9  172.81  5059.4  176.89  5113.5  181.28  5343.6  196.09
  5351.7   197.6  5393.3  199.44    5530  211.61  5536.3  211.24  5565.3  215.24
  5571.6   215.2  5579.7  217.66  5600.5  218.35  5604.6  219.86  5607.8  219.86
#Mann= 5 ,-1 , 0
  4563.4      .1       0  4907.7     .16       0  4974.5     .07       0
  5035.1     .16       0  5113.5      .1       0
Bank Sta=4974.5,5035.1
XS Rating Curve= 0 ,0
Exp/Cntr=0.3,0.1

Type RM Length L Ch R = 1 ,38051   ,458,458,458
BEGIN DESCRIPTION:
LA PARA CREEK 63.0
END DESCRIPTION:
XS GIS Cut Line= 3
      2303306.61     13309490.07      2302421.15     13309339.02
      2301963.63     13309141.46
#Sta/Elev= 30
  4373.2  190.42  4493.8  189.49  4540.2  187.98  4545.3  188.55  4554.7  187.68
  4635.8   185.6  4655.5  184.18  4780.9  180.31  4811.6  178.35    4836  176.37
  4908.1  173.13  4919.9  172.34    4930  169.63  4950.3  165.93  5000.8  161.23
  5016.5  165.22  5031.5  166.14  5061.9  166.01  5076.7  170.69  5082.2  174.01
  5122.8  178.05  5153.2  179.59  5173.5   179.5  5203.9  182.08    5276  185.11
  5319.5  188.76  5449.5  195.86  5460.4  195.81  5471.4  197.35  5769.8  212.38
#Mann= 5 ,-1 , 0
  4373.2      .1       0  4811.6     .12       0  4908.1      .1       0
  4950.3     .07       0  5031.5      .1       0
Bank Sta=4950.3,5031.5
XS Rating Curve= 0 ,0
Exp/Cntr=0.3,0.1

Type RM Length L Ch R = 1 ,37593   ,505,505,505
BEGIN DESCRIPTION:
LA PARA CREEK 62.0
END DESCRIPTION:
XS GIS Cut Line= 3
      2303237.73     13308946.85      2302787.72     13308946.85
      2302387.73     13308946.85
#Sta/Elev= 30
  4528.8  188.45  4538.8  188.62  4598.8  186.42  4608.8  185.43  4658.8  183.23
  4718.8  178.65  4748.8     178  4758.8  177.03    4876   174.5  4918.8  171.75
  4928.8  168.56  4948.8  164.98  4968.8  162.89  4981.3  163.17  4998.6   159.2
  5008.8  161.92  5018.8   162.5  5028.8  164.16  5054.6  166.75  5058.8  167.04
  5078.8  173.28  5088.8  178.83  5108.8  183.21  5218.8  190.91  5248.8  191.32
  5278.8  194.77  5318.8  197.49  5348.8  198.47  5358.8  200.02  5378.8  200.89
#Mann= 5 ,-1 , 0
  4528.8      .1       0    4876     .12       0  4981.3     .07       0
  5028.8     .12       0  5054.6      .1       0
Bank Sta=4981.3,5028.8
XS Rating Curve= 0 ,0
Exp/Cntr=0.3,0.1

Type RM Length L Ch R = 1 ,37088   ,551,551,551
BEGIN DESCRIPTION:
LA PARA CREEK 61.0
END DESCRIPTION:
XS GIS Cut Line= 3
      2303337.76     13308696.88      2302987.72     13308496.85
      2302587.69     13308446.85
#Sta/Elev= 30
    4584  188.34  4635.2  188.07  4715.8  184.11  4722.3  182.79  4825.9  175.88
  4839.8  174.11    4877  172.87  4892.9  170.56  4898.6   170.7  4906.5  168.55
  4951.9  164.35  4957.6   162.5  4979.2  163.26  4984.3  160.99  4989.7  160.99
    4997  158.57  5017.4  161.75    5030  161.25  5053.6  165.21  5067.8  168.13
  5087.9   170.9  5105.6  172.17  5110.6   174.5  5178.6  185.65  5191.2  186.13
  5218.9  189.63  5279.4  195.67  5329.8  198.79  5347.4  200.69  5390.3  201.65
#Mann= 5 ,-1 , 0
    4584      .1       0  4839.8     .12       0  4979.2     .07       0
  5017.4     .12       0  5053.6      .1       0
Bank Sta=4979.2,5017.4
XS Rating Curve= 0 ,0
Exp/Cntr=0.3,0.1

Type RM Length L Ch R = 1 ,36537   ,555,555,555
BEGIN DESCRIPTION:
LA PARA CREEK 60.0
END DESCRIPTION:
XS GIS Cut Line= 3
      2303587.69     13308046.85      2303187.72     13307996.85
      2302787.72     13307946.85
#Sta/Elev= 30
  4599.4  188.17  4609.5  186.75  4629.6  186.05  4637.2  186.03  4642.2  186.65
  4690.1  182.81  4710.2   182.5  4740.5   180.4  4871.5  174.11    4879  172.71
  4891.6  171.73  4911.8  169.06  4921.9  168.54    4942  166.35  4959.7  163.41
  4964.7  164.02  4972.3  160.86  4982.3  160.34  4999.7  158.24  5022.6  159.29
  5045.3  161.16  5052.9  162.67    5073  164.37  5103.3  167.83  5120.9  171.69
  5198.6  179.96  5274.6  184.89  5287.2  186.53  5375.4  191.17  5405.6  192.19
#Mann= 4 ,-1 , 0
  4599.4      .1       0  4964.7     .07       0    5073      .1       0
  5198.6     .05       0
Bank Sta=4964.7,5073
XS Rating Curve= 0 ,0
Exp/Cntr=0.3,0.1

Type RM Length L Ch R = 1 ,35982   ,527,527,527
BEGIN DESCRIPTION:
LA PARA CREEK 59.0
END DESCRIPTION:
XS GIS Cut Line= 3
      2303787.76     13307696.87      2303287.72     13307446.85
      2302837.76     13307546.85
#Sta/Elev= 30
  4469.8   189.3  4618.8  186.37  4735.4  182.47  4841.6  174.45  4872.3  169.66
    4935  163.24  4961.8  159.49  4975.8  159.34  4984.1  156.52  4995.1   154.9
  4997.9   154.4  5001.1   154.9  5006.5  157.83  5020.5  158.55  5026.1  161.18
  5031.4  161.18  5039.1   164.4  5053.2  165.27  5059.6     167  5088.4  170.15
  5096.7  171.78  5101.8  171.34  5151.8  175.47  5181.3  179.29  5237.6  183.13
  5254.2  185.86  5295.2  188.94  5315.7  189.48  5397.6   188.1  5489.8  189.03
#Mann= 8 ,-1 , 0
  4469.8      .1       0  4618.8     .05       0  4735.4      .1       0
    4935     .12       0  4995.1     .07       0  5001.1     .12       0
  5088.4      .1       0  5181.3     .05       0
Bank Sta=4995.1,5001.1
XS Rating Curve= 0 ,0
Exp/Cntr=0.3,0.1

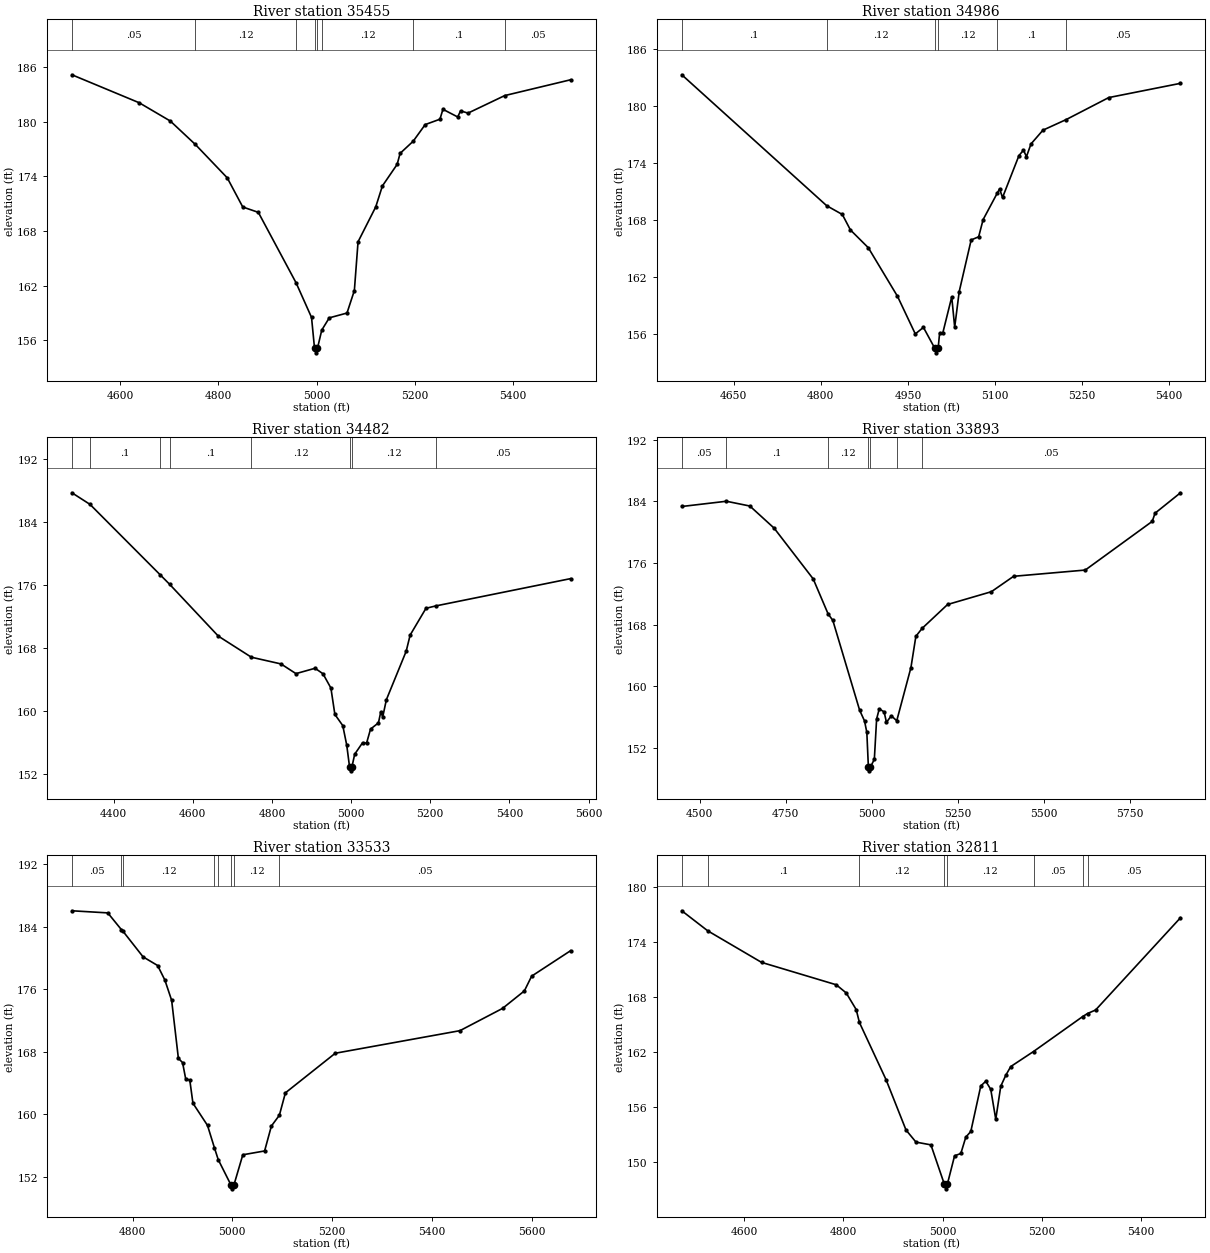
Type RM Length L Ch R = 1 ,35455   ,469,469,469
BEGIN DESCRIPTION:
LA PARA CREEK 58.0
END DESCRIPTION:
XS GIS Cut Line= 3
       2303987.7     13307146.85      2303537.72     13306996.85
      2303087.68     13306696.83
#Sta/Elev= 30
  4501.8  185.19  4638.8  182.11  4702.1   180.1  4753.1  177.52    4818  173.85
  4849.6  170.64  4881.3  170.05  4958.2  162.29  4989.6  158.49  4995.7  155.09
  4998.4  154.59  5001.7  155.09  5010.4  157.09  5025.7  158.44  5061.8  158.97
  5076.8  161.45  5084.3  166.81  5120.3  170.65  5133.9  172.96  5163.9  175.33
  5169.9  176.54  5196.6  177.88    5221  179.71    5251   180.3  5257.1  181.39
  5287.1  180.55  5293.1  181.22  5308.1  180.97  5382.9   182.9    5517  184.64
#Mann= 8 ,-1 , 0
  4501.8     .05       0  4753.1     .12       0  4958.2      .1       0
  4995.7     .07       0  5001.7      .1       0  5010.4     .12       0
  5196.6      .1       0  5382.9     .05       0
Bank Sta=4995.7,5001.7
XS Rating Curve= 0 ,0
Exp/Cntr=0.3,0.1

Type RM Length L Ch R = 1 ,34986   ,504,504,504
BEGIN DESCRIPTION:
LA PARA CREEK 57.0
END DESCRIPTION:
XS GIS Cut Line= 3
      2304087.74     13306746.87      2303687.72     13306546.85
      2303287.67     13306646.87
#Sta/Elev= 30
  4560.3  183.27  4810.1  169.49    4837  168.57    4851  166.94  4881.8  165.07
  4932.1  159.96  4962.8     156  4976.8  156.69  4996.2  154.51  4998.9  154.01
  5002.2  154.51  5004.7  156.08  5010.1  156.08  5025.6  159.89  5030.7  156.71
  5038.5  160.46  5059.1  165.89    5072  166.22  5079.7  168.03  5104.2  170.83
    5108  171.26  5113.2  170.36  5141.5  174.77  5149.3  175.34  5154.4  174.65
  5162.2  175.99  5182.8  177.44    5223  178.56  5296.2  180.87  5419.9  182.37
#Mann= 6 ,-1 , 0
  4560.3      .1       0  4810.1     .12       0  4996.2     .07       0
  5002.2     .12       0  5104.2      .1       0    5223     .05       0
Bank Sta=4996.2,5002.2
XS Rating Curve= 0 ,0
Exp/Cntr=0.3,0.1

Type RM Length L Ch R = 1 ,34482   ,589,589,589
BEGIN DESCRIPTION:
LA PARA CREEK 56.0
END DESCRIPTION:
XS GIS Cut Line= 3
      2304233.26      13306687.6      2304042.28       13306119.
      2303382.61     13306092.96
#Sta/Elev= 30
  4294.5  187.67  4340.2   186.2    4517   177.3  4541.6  176.06  4664.5   169.5
  4747.9  166.83  4822.7  165.98  4860.6  164.75  4908.9  165.43  4928.9  164.73
  4948.9  162.92  4958.9  159.58  4978.9  158.16  4988.9  155.68    4996  152.93
  4998.7  152.43    5002  152.93    5009  154.54    5029     156    5039  155.94
    5049  157.72    5069  158.51  5074.8  159.88  5079.8  159.26    5089  161.44
  5139.1  167.59  5149.1  169.64  5189.1  173.03  5213.8  173.33  5554.5  176.79
#Mann= 8 ,-1 , 0
  4294.5     .05       0  4340.2      .1       0    4517     .05       0
  4541.6      .1       0  4747.9     .12       0    4996     .07       0
    5002     .12       0  5213.8     .05       0
Bank Sta=4996,5002
XS Rating Curve= 0 ,0
Exp/Cntr=0.3,0.1

Type RM Length L Ch R = 1 ,33893   ,360,360,360
BEGIN DESCRIPTION:
LA PARA CREEK 55.0
END DESCRIPTION:
XS GIS Cut Line= 4
      2303933.77     13305090.36      2303964.15     13305389.83
      2303456.34     13305967.09      2303087.72     13306046.86
#Sta/Elev= 30
  4448.4  183.32  4577.8     184  4645.9  183.38  4716.3  180.51  4829.7  173.92
    4873  169.37  4886.6  168.54  4964.4  156.88  4978.6  155.49  4985.3     154
  4989.8  149.51  4992.6  149.01  4995.8  149.51  5007.1  150.51  5013.7  155.74
  5021.3  157.05  5035.5  156.66  5042.2  155.31  5056.4  156.15  5072.1  155.51
  5113.3  162.42  5127.6  166.47  5145.7   167.5  5219.6   170.6  5346.7  172.26
  5411.2  174.26  5619.1  175.07  5813.5  181.39  5821.6  182.45  5895.4   185.1
#Mann= 7 ,-1 , 0
  4448.4     .05       0  4577.8      .1       0    4873     .12       0
  4989.8     .07       0  4995.8     .12       0  5072.1      .1       0
  5145.7     .05       0
Bank Sta=4989.8,4995.8
XS Rating Curve= 0 ,0
Exp/Cntr=0.3,0.1

Type RM Length L Ch R = 1 ,33533   ,722,722,722
BEGIN DESCRIPTION:
LA PARA CREEK 54.0
END DESCRIPTION:
XS GIS Cut Line= 2
      2303787.71     13305146.86      2302987.71     13305746.86
#Sta/Elev= 30
  4678.4  186.03  4750.3  185.76  4777.7  183.61  4780.3  183.45  4821.1  180.13
  4850.3  179.02  4864.8  177.16  4878.4  174.56  4891.9  167.14  4900.3  166.59
  4906.5  164.53  4914.8  164.34  4921.1  161.39  4950.3  158.55  4964.1   155.7
  4971.8  154.17  4997.3  150.93    5000  150.43  5003.3  150.93  5021.1  154.79
  5064.8  155.28  5078.4  158.47  5094.4  159.85  5106.5  162.72  5206.5  167.79
  5456.5  170.68  5541.9  173.53  5585.7  175.77  5600.3  177.66  5678.4  180.92
#Mann= 8 ,-1 , 0
  4678.4     .05       0  4777.7      .1       0  4780.3     .12       0
  4964.1      .1       0  4971.8     .12       0  4997.3     .07       0
  5003.3     .12       0  5094.4     .05       0
Bank Sta=4997.3,5003.3
XS Rating Curve= 0 ,0
Exp/Cntr=0.3,0.1

Type RM Length L Ch R = 1 ,32811   ,537,537,537
BEGIN DESCRIPTION:
LA PARA CREEK 53.0
END DESCRIPTION:
XS GIS Cut Line= 3
      2303537.76     13304796.85      2302987.72     13304846.85
      2302537.69     13304896.86
#Sta/Elev= 30
  4474.3  177.42  4526.5  175.24    4635   171.8  4785.6  169.36  4805.7  168.47
  4825.8  166.66  4832.3  165.25    4886  159.02  4926.2  153.54  4946.3  152.22
  4976.4  151.92  5003.5  147.63  5006.3  147.13  5009.5  147.63  5024.1  150.73
  5036.7  150.98  5046.7  152.76  5056.8  153.38  5076.9  158.34    5087  158.85
    5097  157.97  5107.1  154.71  5117.2  158.31  5127.2  159.49  5137.3  160.45
  5183.2  162.09  5282.4   165.9  5292.1  166.23  5308.3  166.61  5479.4  176.66
#Mann= 8 ,-1 , 0
  4474.3     .05       0  4526.5      .1       0  4832.3     .12       0
  5003.5     .07       0  5009.5     .12       0  5183.2     .05       0
  5282.4      .1       0  5292.1     .05       0
Bank Sta=5003.5,5009.5
XS Rating Curve= 0 ,0
Exp/Cntr=0.3,0.1

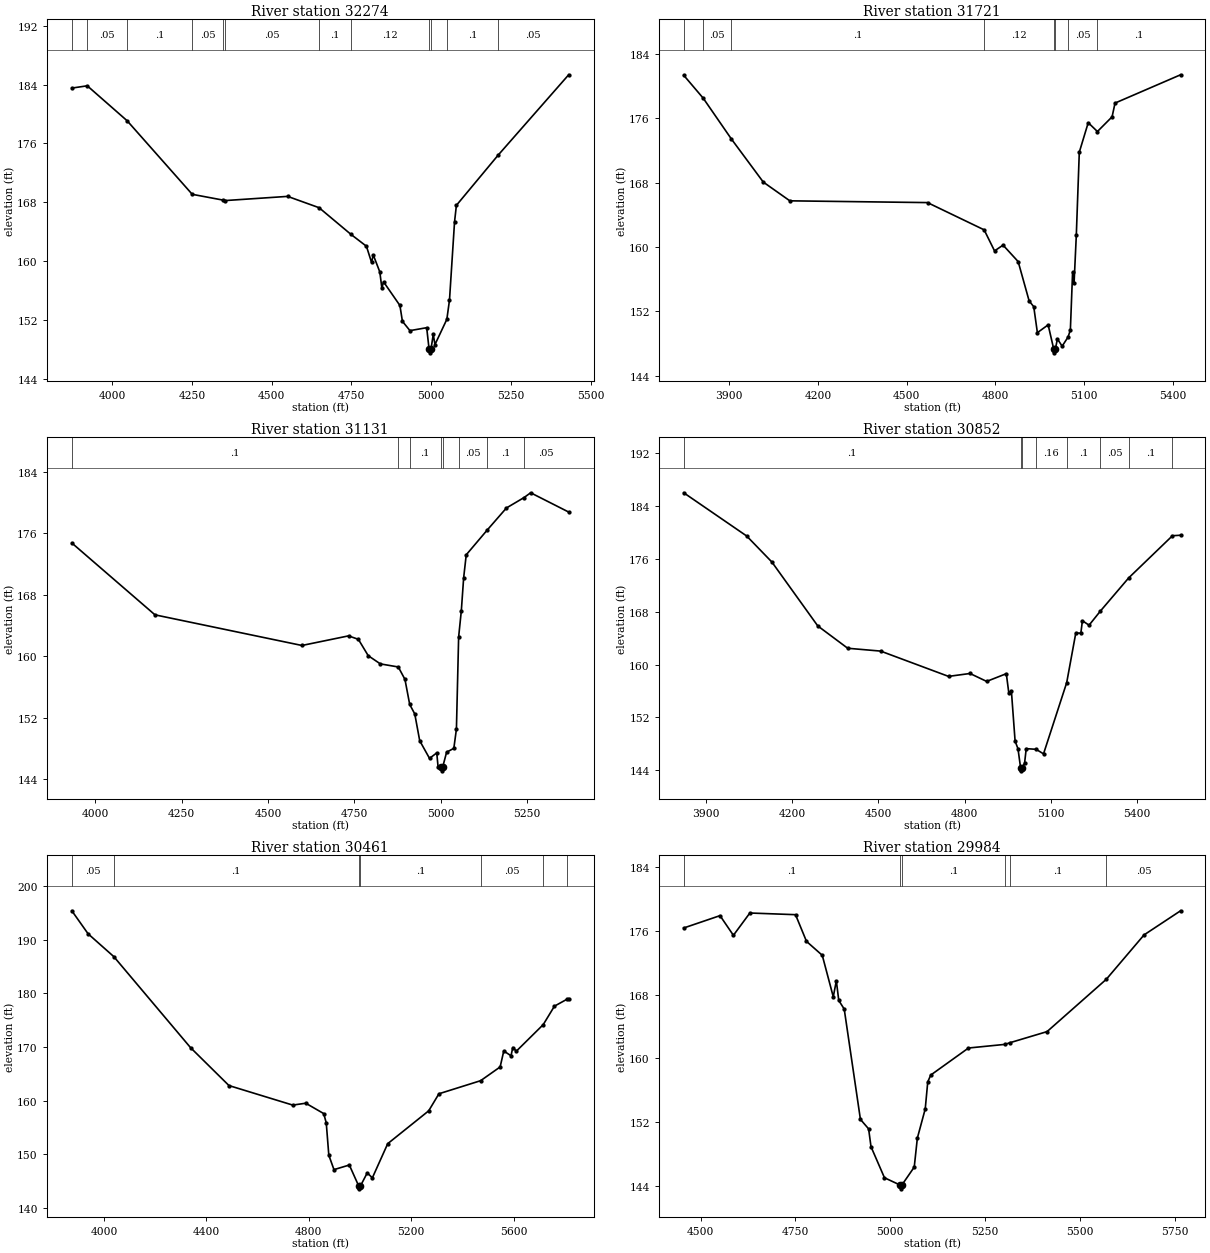
Type RM Length L Ch R = 1 ,32274   ,553,553,553
BEGIN DESCRIPTION:
LA PARA CREEK 52.0
END DESCRIPTION:
XS GIS Cut Line= 3
      2303787.77     13304746.87      2302687.72     13304396.85
      2302337.72     13304596.85
#Sta/Elev= 30
  3873.7  183.53  3922.1  183.84    4047  179.09  4251.2  169.08  4348.2  168.29
  4354.1  168.23  4550.2   168.8  4648.8  167.26  4748.2  163.65  4797.2  162.02
  4813.3  159.82  4818.6  160.84  4839.2  158.52  4845.6  156.31  4850.8  157.18
  4902.2  153.96    4910  151.81  4933.6  150.54  4986.1  150.94  4993.6  148.02
  4996.4  147.52  4999.6  148.02  5006.7  150.03    5012  148.64  5049.3  152.08
  5057.6   154.7  5073.4  165.32  5079.2  167.58  5209.7  174.39  5431.2  185.34
#Mann= 12 ,-1 , 0
  3873.7      .1       0  3922.1     .05       0    4047      .1       0
  4251.2     .05       0  4348.2      .1       0  4354.1     .05       0
  4648.8      .1       0  4748.2     .12       0  4993.6     .07       0
  4999.6     .12       0  5049.3      .1       0  5209.7     .05       0
Bank Sta=4993.6,4999.6
XS Rating Curve= 0 ,0
Exp/Cntr=0.3,0.1

Type RM Length L Ch R = 1 ,31721   ,590,590,590
BEGIN DESCRIPTION:
LA PARA CREEK 51.0
END DESCRIPTION:
XS GIS Cut Line= 3
      2303787.75     13304496.87      2302687.72     13303846.85
      2302287.76     13303896.85
#Sta/Elev= 30
  3746.2  181.37  3812.3  178.51  3907.5  173.44  4015.4  168.08  4105.2  165.75
  4570.9  165.53  4762.5  162.14  4797.7  159.52  4826.5  160.24  4877.6  158.19
  4914.7   153.3  4930.3  152.58  4942.6  149.35    4979  150.32  4997.7  147.34
  5000.4  146.84  5003.7  147.34  5010.3  148.57  5026.4  147.67  5046.3   148.8
  5054.2  149.68  5061.7  156.87  5066.8  155.56  5074.3  161.47  5084.4   171.8
  5114.6  175.47  5145.7  174.37  5195.3   176.2  5205.3  177.91    5427  181.43
#Mann= 8 ,-1 , 0
  3746.2      .1       0  3812.3     .05       0  3907.5      .1       0
  4762.5     .12       0  4997.7     .07       0  5003.7     .12       0
  5046.3     .05       0  5145.7      .1       0
Bank Sta=4997.7,5003.7
XS Rating Curve= 0 ,0
Exp/Cntr=0.3,0.1

Type RM Length L Ch R = 1 ,31131   ,279,279,279
BEGIN DESCRIPTION:
LA PARA CREEK 50.0
END DESCRIPTION:
XS GIS Cut Line= 4
      2303787.74     13304246.87      2303087.72     13303446.86
      2303015.51     13303382.61      2302737.74     13303391.29
#Sta/Elev= 30
  3932.5  174.76  4173.1   165.4  4598.3  161.41  4733.1  162.66  4761.6  162.21
  4790.1  160.08  4825.2  159.01  4877.1  158.61  4896.4  156.99  4910.1  153.73
  4924.8  152.49  4939.1     149  4967.5   146.7  4988.4  147.42  4992.2  145.59
  4999.6  145.58  5002.4  145.08  5005.6  145.58  5016.9  147.51  5037.8  148.01
  5045.3  150.52  5051.7  162.51  5059.5  165.94  5066.2  170.22  5073.7  173.22
  5133.9  176.42    5190  179.32  5240.7  180.67  5260.1   181.3  5370.1  178.79
#Mann= 8 ,-1 , 0
  3932.5      .1       0  4877.1     .16       0  4910.1      .1       0
  4999.6     .07       0  5005.6      .1       0  5051.7     .05       0
  5133.9      .1       0  5240.7     .05       0
Bank Sta=4999.6,5005.6
XS Rating Curve= 0 ,0
Exp/Cntr=0.3,0.1

Type RM Length L Ch R = 1 ,30852   ,391,391,391
BEGIN DESCRIPTION:
Mapping XS 83062be5
END DESCRIPTION:
XS GIS Cut Line= 3
      2304387.02     13303794.93      2303097.97       13303209.
      2302812.11      13303334.6
#Sta/Elev= 30
    3823  186.02  4041.9  179.48  4129.8  175.53  4289.3  165.86  4393.4  162.48
  4507.9  162.05  4744.1  158.22  4818.8  158.66  4876.7  157.46  4945.1  158.63
  4953.6  155.76  4962.7  156.04  4975.6  148.43  4985.7  147.26  4994.6  144.42
  4997.3  143.92  5000.6  144.42  5008.6  145.07  5014.3  147.28  5048.7  147.18
  5074.5  146.49  5155.1  157.27  5186.8   164.8  5204.3  164.76  5209.8  166.65
  5232.9  165.97  5272.3  168.11  5370.7  173.13  5523.1  179.52  5551.2  179.59
#Mann= 8 ,-1 , 0
    3823      .1       0  4994.6     .07       0  5000.6      .1       0
  5048.7     .16       0  5155.1      .1       0  5272.3     .05       0
  5370.7      .1       0  5523.1     .05       0
Bank Sta=4994.6,5000.6
XS Rating Curve= 0 ,0
Exp/Cntr=0.3,0.1

Type RM Length L Ch R = 1 ,30461   ,477,477,477
BEGIN DESCRIPTION:
Mapping XS 83062be
END DESCRIPTION:
XS GIS Cut Line= 3
      2304621.36     13303009.34      2303115.33     13302978.96
      2302821.43      13303298.8
#Sta/Elev= 30
  3874.3  195.39    3938  191.09  4038.2  186.85    4338  169.88  4488.1  162.81
  4737.3  159.17  4788.1  159.52  4858.1  157.59  4868.1  155.86  4878.1  149.83
  4898.2  147.14  4958.2     148  4995.2  144.06  4997.9  143.56  5001.2  144.06
  5028.2  146.53  5048.2  145.61  5108.2  151.98  5268.2   158.1  5308.2  161.28
  5471.1  163.72  5547.3  166.28  5561.5  169.26  5589.8  168.36  5596.6   169.9
  5610.8  169.23  5715.6  174.17  5759.4  177.61  5809.9  178.94    5815     179
#Mann= 7 ,-1 , 0
  3874.3     .05       0  4038.2      .1       0  4995.2     .07       0
  5001.2      .1       0  5471.1     .05       0  5715.6      .1       0
  5809.9     .05       0
Bank Sta=4995.2,5001.2
XS Rating Curve= 0 ,0
Exp/Cntr=0.3,0.1

Type RM Length L Ch R = 1 ,29984   ,491,491,491
BEGIN DESCRIPTION:
LA PARA CREEK 49.0
END DESCRIPTION:
XS GIS Cut Line= 2
      2303563.74      13302229.2      2302758.99     13303262.88
#Sta/Elev= 30
  4455.7  176.36  4551.4  177.91  4586.7  175.44  4630.1  178.24  4750.5  178.03
  4779.4  174.68    4821  172.93    4850  167.72  4858.1  169.73  4864.5  167.26
  4878.9  166.18  4921.6  152.33  4943.2  151.14  4949.5   148.9    4985     145
  5025.2  144.11    5028  143.61  5031.2  144.11  5063.5  146.34  5071.7  149.98
  5092.5  153.65  5099.1  157.03  5106.9  157.89  5206.5  161.29  5303.3  161.75
  5314.7  161.94  5413.7  163.35  5569.9  169.92  5669.4  175.49  5765.7  178.52
#Mann= 6 ,-1 , 0
  4455.7      .1       0  5025.2     .07       0  5031.2      .1       0
  5303.3     .05       0  5314.7      .1       0  5569.9     .05       0
Bank Sta=5025.2,5031.2
XS Rating Curve= 0 ,0
Exp/Cntr=0.3,0.1

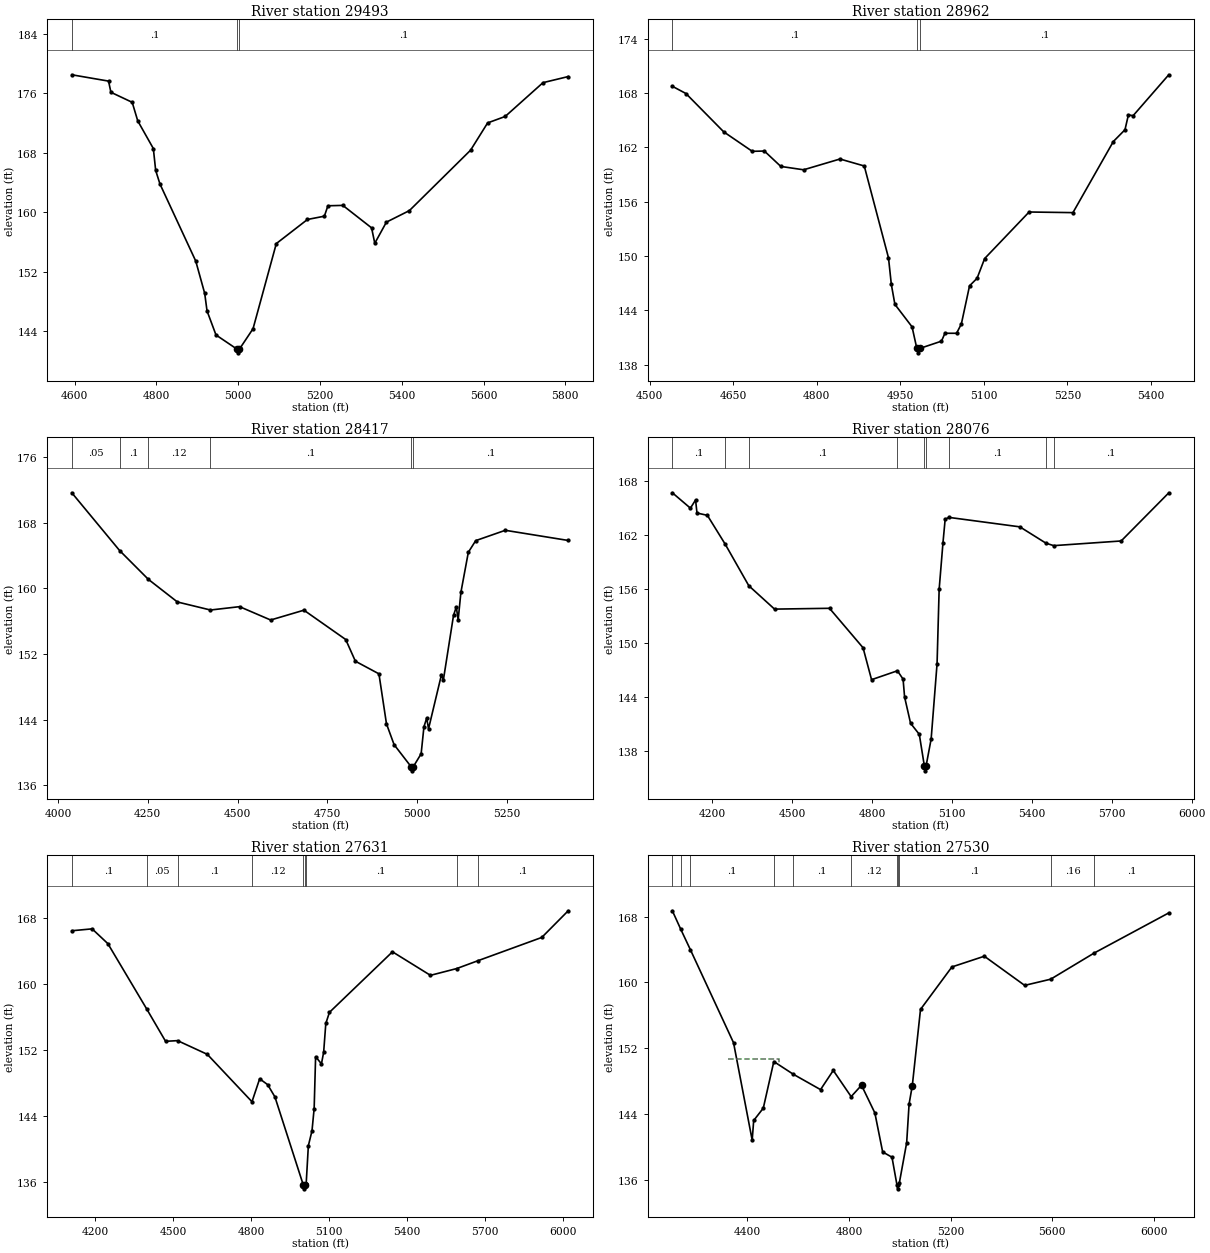
Type RM Length L Ch R = 1 ,29493   ,531,531,531
BEGIN DESCRIPTION:
LA PARA CREEK 48.0
END DESCRIPTION:
XS GIS Cut Line= 3
       2303037.7     13302046.89      2302744.28     13302590.33
      2302286.19     13302972.07
#Sta/Elev= 30
  4593.2  178.49  4683.1  177.64  4688.8  176.14  4740.9  174.79  4754.5  172.29
  4792.6  168.58  4798.3  165.64  4808.8  163.81  4896.3  153.46  4918.2  149.12
  4923.9  146.76  4945.8  143.53  4997.1  141.63  4999.8  141.13  5003.1  141.63
  5036.4  144.37  5093.3  155.81  5169.5  159.05  5210.8  159.49  5219.5  160.89
    5256  160.94  5326.3  157.92  5334.1  155.85  5362.5  158.69  5418.7  160.24
  5568.4  168.36    5610  172.02    5653  172.89  5745.4  177.43  5807.1  178.25
#Mann= 3 ,-1 , 0
  4593.2      .1       0  4997.1     .07       0  5003.1      .1       0
Bank Sta=4997.1,5003.1
XS Rating Curve= 0 ,0
Exp/Cntr=0.3,0.1

Type RM Length L Ch R = 1 ,28962   ,545,545,545
BEGIN DESCRIPTION:
LA PARA CREEK 47.0
END DESCRIPTION:
XS GIS Cut Line= 3
      2302887.75     13301996.85      2302437.72     13302096.85
      2302187.74     13302446.83
#Sta/Elev= 30
  4540.8  168.73  4565.2  167.93    4633   163.7  4684.2  161.55    4706  161.58
  4735.5  159.88  4776.4  159.51  4841.7   160.7  4885.3  159.93  4928.8  149.79
  4933.9  146.85  4940.3  144.65  4971.1  142.17  4979.6   139.8  4982.4   139.3
  4985.6   139.8  5023.9  140.59  5030.1  141.46    5051  141.46  5059.6  142.49
  5074.3   146.7  5087.8  147.53  5101.4  149.71  5181.2  154.85  5259.9  154.78
  5332.4  162.63  5353.3  163.93  5359.4  165.56    5368  165.49  5431.9     170
#Mann= 3 ,-1 , 0
  4540.8      .1       0  4979.6     .07       0  4985.6      .1       0
Bank Sta=4979.6,4985.6
XS Rating Curve= 0 ,0
Exp/Cntr=0.3,0.1

Type RM Length L Ch R = 1 ,28417   ,341,341,341
BEGIN DESCRIPTION:
LA PARA CREEK 46.0
END DESCRIPTION:
XS GIS Cut Line= 3
      2302737.74     13301346.84      2301937.72     13301896.85
      2302037.73     13302296.89
#Sta/Elev= 30
  4038.2  171.68  4171.4  164.63  4251.6  161.11  4332.5  158.35  4424.6  157.37
  4505.7  157.78  4592.3  156.15    4685  157.35  4801.4  153.77  4828.4  151.12
    4894  149.58    4915  143.48  4936.2  140.94  4983.7  138.24  4986.5  137.74
  4989.7  138.24  5011.6  139.82  5019.4  143.12  5027.1  144.18  5032.2  142.87
  5068.3  149.49  5073.5  148.81  5101.8  156.71  5109.6  157.75  5114.7  156.15
  5122.4  159.53  5143.1  164.42  5163.7  165.84  5246.1   167.1  5421.4  165.86
#Mann= 6 ,-1 , 0
  4038.2     .05       0  4171.4      .1       0  4251.6     .12       0
  4424.6      .1       0  4983.7     .07       0  4989.7      .1       0
Bank Sta=4983.7,4989.7
XS Rating Curve= 0 ,0
Exp/Cntr=0.3,0.1

Type RM Length L Ch R = 1 ,28076   ,445,445,445
BEGIN DESCRIPTION:
LA PARA CREEK 45.0
END DESCRIPTION:
XS GIS Cut Line= 4
      2302341.48     13301111.17      2301874.45     13301279.12
      2301605.39     13301833.38      2301938.72     13302506.99
#Sta/Elev= 30
    4050  166.71  4117.8     165  4137.2  165.91  4142.5  164.46  4181.5   164.2
  4248.3     161  4337.1  156.37  4433.7  153.77  4640.1  153.86  4766.1  149.47
    4798  145.92  4895.1  146.91  4916.4  145.98    4922     144  4944.5  141.07
  4977.3  139.84  4996.5  136.28  4999.3  135.78  5002.5  136.28  5021.8  139.33
    5044   147.7  5051.8  155.96  5066.2  161.16  5074.4  163.77  5089.1  163.97
  5354.9  162.92  5453.1   161.1    5482  160.83  5735.3  161.35    5914   166.7
#Mann= 9 ,-1 , 0
    4050      .1       0  4248.3     .05       0  4337.1      .1       0
  4895.1     .16       0  4996.5     .07       0  5002.5     .16       0
  5089.1      .1       0  5453.1     .16       0    5482      .1       0
Bank Sta=4996.5,5002.5
XS Rating Curve= 0 ,0
Exp/Cntr=0.3,0.1

Type RM Length L Ch R = 1 ,27631   ,101,101,101
BEGIN DESCRIPTION:
Mapping XS eb22ef98
END DESCRIPTION:
XS GIS Cut Line= 4
      2302265.16     13301069.49       2301841.5     13301125.05
      2301119.28     13301486.16      2300709.56     13302020.88
#Sta/Elev= 30
  4110.5  166.41  4188.6  166.64  4249.1  164.85    4398  156.96    4471  153.02
  4517.2   153.1  4631.5  151.44  4803.2   145.7  4832.7  148.48  4863.4  147.77
  4891.3  146.29  5000.1  135.65  5002.9  135.15  5006.1  135.65    5009  135.72
  5011.6  135.79  5019.9  140.37  5033.9  142.18  5042.2  144.88  5047.8  151.16
  5070.2  150.29  5078.7  151.69    5087  155.18    5101  156.53  5343.3  163.86
  5489.3  161.01  5590.1  161.83  5672.6  162.79  5917.2   165.6  6018.9  168.83
#Mann= 9 ,-1 , 0
  4110.5      .1       0    4398     .05       0  4517.2      .1       0
  4803.2     .12       0  5000.1     .07       0  5006.1     .12       0
    5009      .1       0  5590.1     .16       0  5672.6      .1       0
Bank Sta=5000.1,5006.1
XS Rating Curve= 0 ,0
Exp/Cntr=0.3,0.1

Type RM Length L Ch R = 1 ,27530   ,731,731,731
BEGIN DESCRIPTION:
LA PARA CREEK 44.0
END DESCRIPTION:
XS GIS Cut Line= 4
      2301887.71      13300546.9      2301723.45     13301076.44
      2301084.56     13301402.83      2300653.99     13301930.62
#Sta/Elev= 30
  4105.3   168.7  4138.3  166.46  4176.6  163.95  4346.1  152.67  4419.4  140.84
  4425.3  143.23  4463.1  144.73  4504.5  150.39    4581  148.85  4688.3  146.98
  4738.4  149.31  4808.7  146.13  4849.5  147.51    4902  144.15  4932.7  139.41
  4969.4  138.77  4988.8  135.43  4991.6  134.93  4994.8  135.43  4998.3  135.64
  5027.2  140.54  5036.7  145.23  5049.4  147.48  5081.6  156.72  5205.2  161.88
  5332.7  163.18  5491.4  159.64  5593.7  160.39    5765  163.57  6058.3  168.44
#Mann= 11 ,-1 , 0
  4105.3      .1       0  4138.3     .05       0  4176.6      .1       0
  4504.5     .05       0    4581      .1       0  4808.7     .12       0
  4988.8     .07       0  4994.8     .12       0  4998.3      .1       0
  5593.7     .16       0    5765      .1       0
#XS Ineff= 1 ,-1
 4326.17 4523.44  150.68
Permanent Ineff=
       F
Bank Sta=4849.5,5049.4
XS Rating Curve= 0 ,0
Exp/Cntr=0.3,0.1