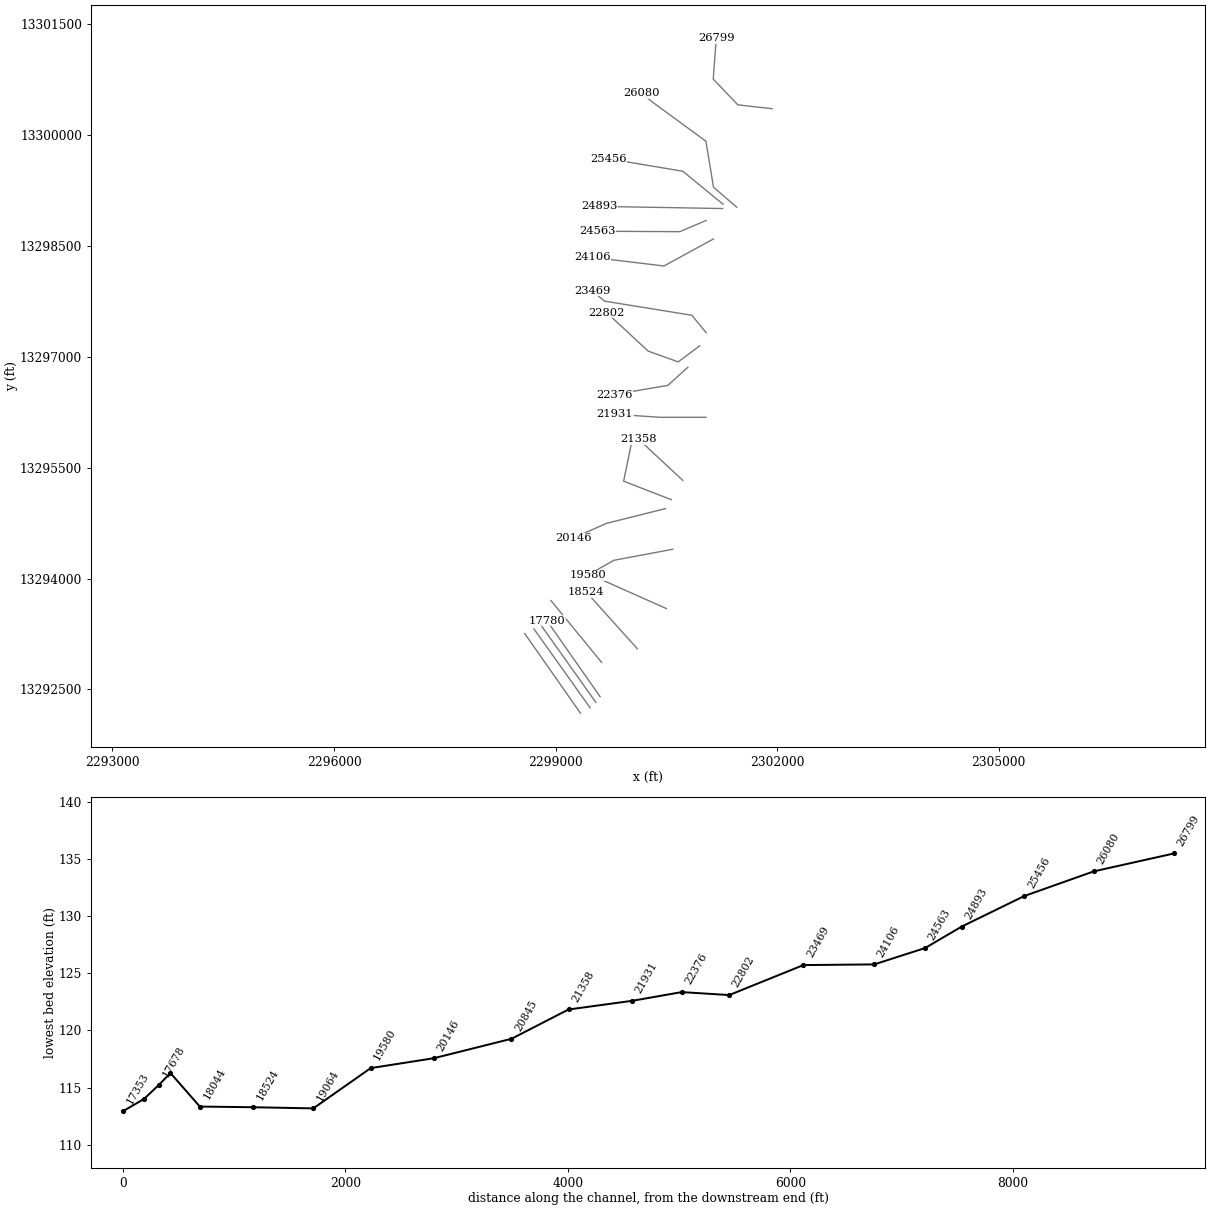
HEC-RAS study LA PARA CREEK.prj: LA PARA CREEK Base Level Engineering

--- LA PARA CREEK.g01 (geometry) --- (continued)

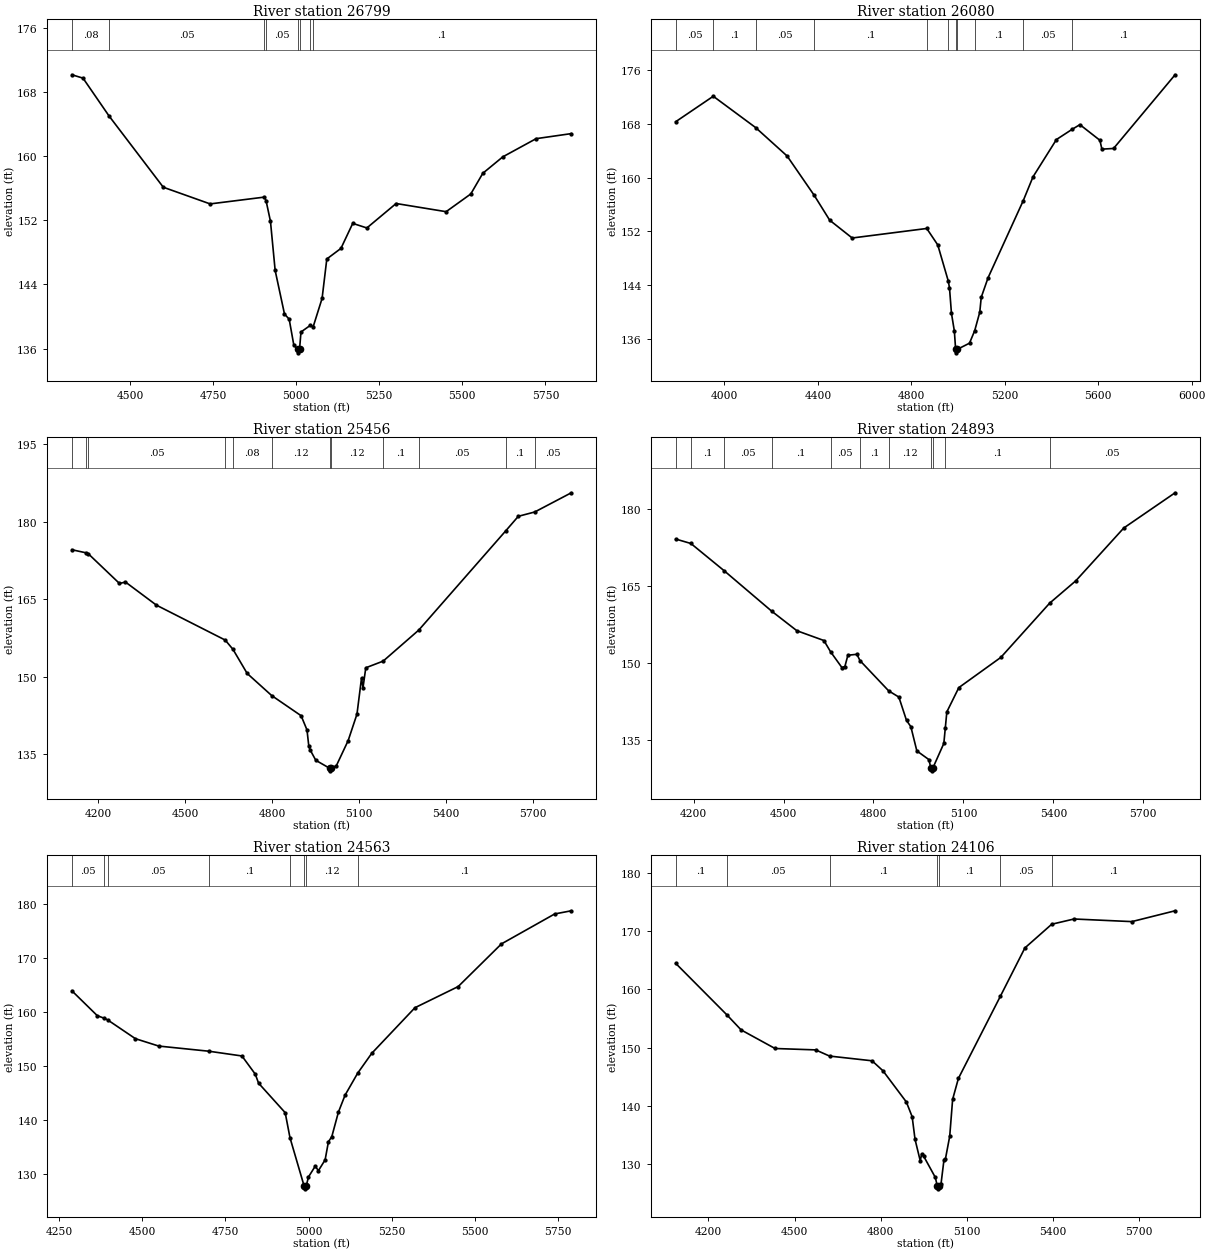
Type RM Length L Ch R = 1 ,26799   ,719,719,719
BEGIN DESCRIPTION:
LA PARA CREEK 43.0
END DESCRIPTION:
XS GIS Cut Line= 4
      2301930.85     13300359.74      2301467.26     13300411.83
      2301133.93     13300760.79      2301175.56     13301312.34
#Sta/Elev= 30
  4325.5  170.15  4358.8  169.73  4437.1  165.01  4600.3  156.12  4741.2  154.04
  4904.7  154.89  4909.5  154.43  4922.7  151.87  4936.8  145.74  4964.9   140.3
    4979  139.66  4993.1  136.39  5004.3  135.96    5007  135.46  5010.3  135.96
  5014.5  138.06  5042.3  138.88  5051.3  138.73    5078  142.25  5092.2  147.17
  5134.7  148.49  5170.2  151.61  5212.7  151.04  5300.7  154.09  5451.1  153.07
  5525.3  155.28  5561.5  157.86  5621.6  159.91  5721.9  162.18  5827.7  162.81
#Mann= 8 ,-1 , 0
  4325.5     .08       0  4437.1     .05       0  4904.7      .1       0
  4909.5     .05       0  5004.3     .04       0  5010.3     .05       0
  5042.3     .16       0  5051.3      .1       0
Bank Sta=5004.3,5010.3
XS Rating Curve= 0 ,0
Exp/Cntr=0.3,0.1

Type RM Length L Ch R = 1 ,26080   ,624,624,624
BEGIN DESCRIPTION:
LA PARA CREEK 42.0
END DESCRIPTION:
XS GIS Cut Line= 5
       2301453.2     13299025.82      2301137.72     13299296.85
      2301035.46     13299919.28      2300321.87     13300441.42
      2300159.42     13300569.06
#Sta/Elev= 30
  3791.6  168.34  3952.3  172.13  4133.3  167.47  4268.3  163.23  4384.3  157.37
  4450.7  153.66  4546.9  151.01    4866  152.43  4913.2  149.98  4957.8  144.65
  4963.4   143.6  4971.8   139.8  4984.3  137.14  4989.7   134.4  4992.5   133.9
  4995.7   134.4  5049.1  135.34  5071.5  137.22  5093.1  139.97  5099.3  142.17
  5128.6  145.09  5279.2  156.58  5320.9  160.12  5421.2  165.68  5487.8  167.19
  5521.6   167.9  5607.3  165.57  5615.8  164.25  5665.7  164.35  5929.1  175.33
#Mann= 11 ,-1 , 0
  3791.6     .05       0  3952.3      .1       0  4133.3     .05       0
  4384.3      .1       0    4866     .08       0  4957.8     .05       0
  4989.7     .07       0  4995.7     .05       0  5071.5      .1       0
  5279.2     .05       0  5487.8      .1       0
Bank Sta=4989.7,4995.7
XS Rating Curve= 0 ,0
Exp/Cntr=0.3,0.1

Type RM Length L Ch R = 1 ,25456   ,563,563,563
BEGIN DESCRIPTION:
LA PARA CREEK 41.0
END DESCRIPTION:
XS GIS Cut Line= 3
      2301267.55     13299066.43      2300722.18     13299513.17
      2299718.47     13299681.43
#Sta/Elev= 30
  4109.7  174.59  4157.2  174.01  4166.5  173.79  4273.6  168.06  4294.4  168.33
  4401.3  163.85  4638.4  157.09  4665.1   155.3  4714.2  150.62  4798.7  146.34
  4900.3  142.43  4920.6  139.67  4926.7  136.59  4931.7  135.78    4951  133.79
  4998.7  132.25  5001.5  131.75  5004.7  132.25    5022  132.76  5062.6  137.61
    5093  142.74  5108.7  149.74  5113.7  147.83  5123.4  151.72  5183.3  153.01
  5306.1  159.02  5606.3  178.26  5649.6  181.07  5706.3  181.91  5832.4  185.63
#Mann= 12 ,-1 , 0
  4109.7     .05       0  4157.2      .1       0  4166.5     .05       0
  4638.4      .1       0  4665.1     .08       0  4798.7     .12       0
  4998.7     .07       0  5004.7     .12       0  5183.3      .1       0
  5306.1     .05       0  5606.3      .1       0  5706.3     .05       0
Bank Sta=4998.7,5004.7
XS Rating Curve= 0 ,0
Exp/Cntr=0.3,0.1

Type RM Length L Ch R = 1 ,24893   ,330,330,330
BEGIN DESCRIPTION:
LA PARA CREEK 40.0
END DESCRIPTION:
XS GIS Cut Line= 2
      2301261.71     13299008.44      2299596.66     13299037.45
#Sta/Elev= 30
  4140.6  174.11  4191.1  173.25    4302  167.96  4460.4  160.11  4544.6   156.3
  4634.7   154.4  4656.9  152.22  4694.7  149.15  4704.7  149.35  4714.7  151.54
  4744.7  151.72  4755.2  150.49  4850.7  144.62  4884.7  143.41  4910.2  138.88
  4924.7  137.66  4944.7  132.95  4984.7  131.27  4991.7  129.58  4994.5  129.08
  4997.7  129.58  5034.7  134.41  5039.6  137.41  5044.7  140.53  5084.7  145.25
  5224.8  151.12  5387.5  161.65  5474.8     166  5634.8  176.26  5805.9   183.1
#Mann= 11 ,-1 , 0
  4140.6     .05       0  4191.1      .1       0    4302     .05       0
  4460.4      .1       0  4656.9     .05       0  4755.2      .1       0
  4850.7     .12       0  4991.7     .07       0  4997.7     .12       0
  5039.6      .1       0  5387.5     .05       0
Bank Sta=4991.7,4997.7
XS Rating Curve= 0 ,0
Exp/Cntr=0.3,0.1

Type RM Length L Ch R = 1 ,24563   ,457,457,457
BEGIN DESCRIPTION:
LA PARA CREEK 39.0
END DESCRIPTION:
XS GIS Cut Line= 3
      2301037.72     13298846.85      2300681.57     13298695.16
      2299567.69     13298700.96
#Sta/Elev= 30
  4288.9  163.96    4365  159.36  4386.4  158.86  4395.9  158.58  4479.7  155.08
  4549.8  153.71  4700.8  152.75  4799.9  151.87  4839.9   148.5  4849.9  146.82
  4929.9  141.34  4944.3  136.69  4986.9   127.7  4989.6   127.2  4992.9   127.7
  4999.9  129.41  5019.9  131.38  5029.9  130.59  5049.9  132.58  5059.9  135.96
  5069.9  136.87  5089.9  141.45  5109.9   144.6  5147.7  148.67  5189.9  152.35
  5319.9  160.83  5449.9  164.76  5579.9  172.68  5739.9  178.24  5789.9  178.83
#Mann= 8 ,-1 , 0
  4288.9     .05       0  4386.4      .1       0  4395.9     .05       0
  4700.8      .1       0  4944.3     .12       0  4986.9     .07       0
  4992.9     .12       0  5147.7      .1       0
Bank Sta=4986.9,4992.9
XS Rating Curve= 0 ,0
Exp/Cntr=0.3,0.1

Type RM Length L Ch R = 1 ,24106   ,637,637,637
BEGIN DESCRIPTION:
LA PARA CREEK 38.0
END DESCRIPTION:
XS GIS Cut Line= 3
      2301137.72     13298596.85      2300466.91     13298231.04
       2299498.1     13298347.06
#Sta/Elev= 30
  4085.9  164.47    4264  155.64  4313.7  153.05  4431.9  149.86  4573.4  149.62
  4621.8  148.56  4769.9  147.75  4807.8  146.04  4889.4  140.68  4909.6  138.15
  4919.7  134.25  4937.8  130.58  4942.9  131.77  4949.9  131.36  4990.2  127.74
  4997.2  126.27    5000  125.77  5003.2  126.27  5010.3  126.66  5020.2  130.64
  5025.2  130.81  5040.5   134.8  5050.6  141.12  5070.7  144.72  5217.4  158.87
  5302.4  167.12  5395.9  171.19  5473.6  172.09    5675  171.64  5825.7   173.5
#Mann= 7 ,-1 , 0
  4085.9      .1       0    4264     .05       0  4621.8      .1       0
  4997.2     .07       0  5003.2      .1       0  5217.4     .05       0
  5395.9      .1       0
Bank Sta=4997.2,5003.2
XS Rating Curve= 0 ,0
Exp/Cntr=0.3,0.1

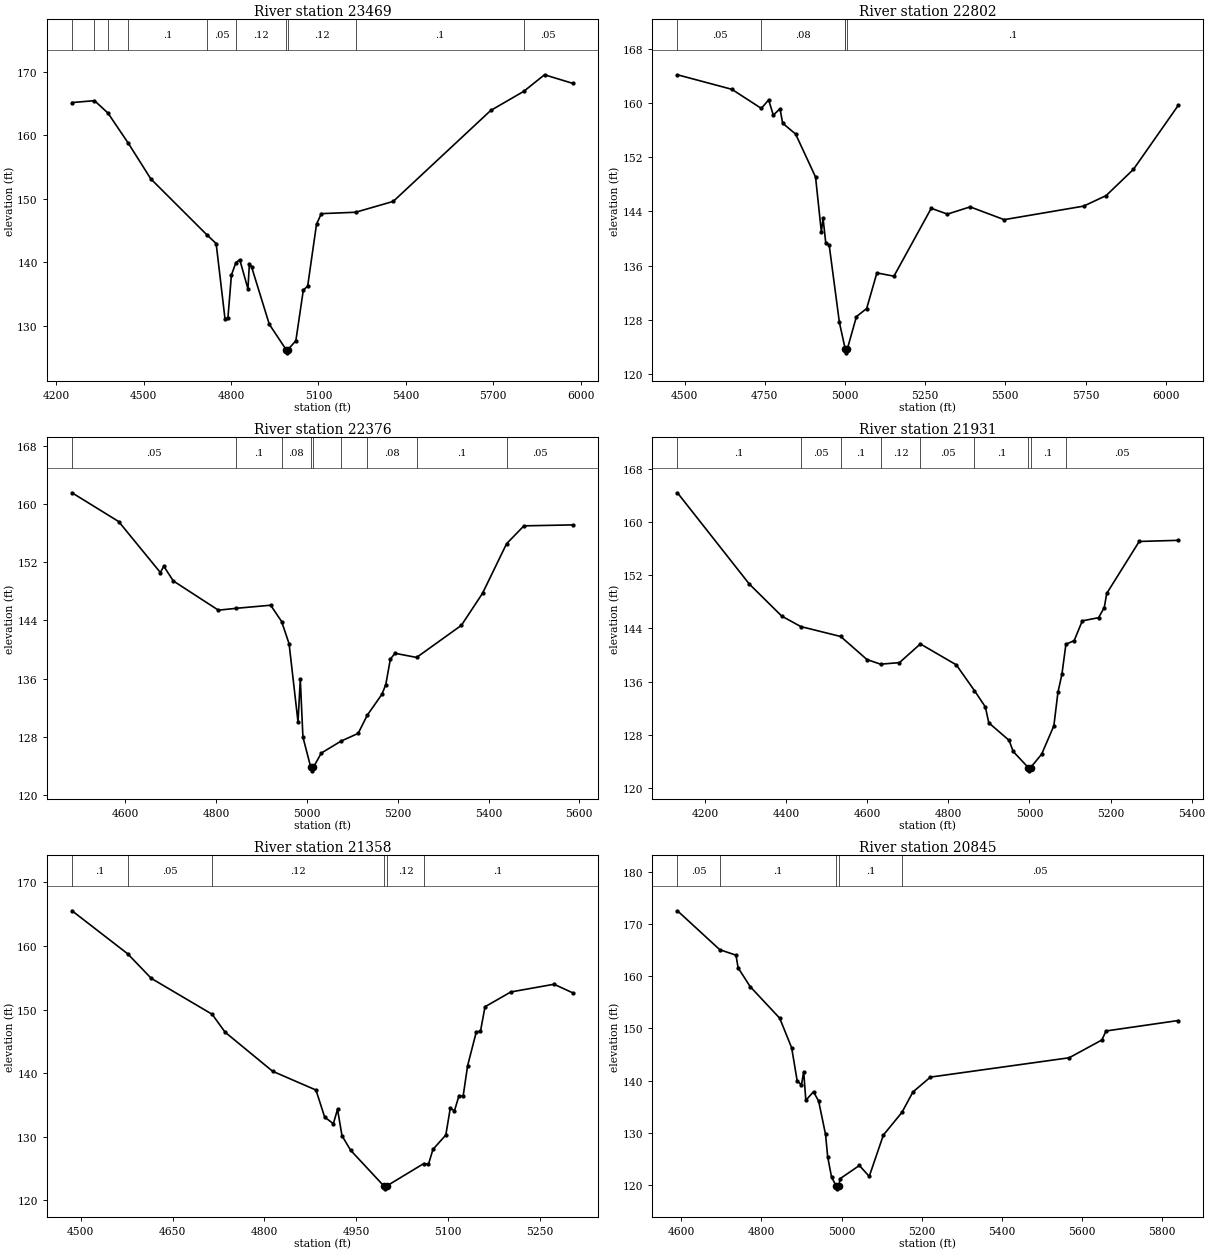
Type RM Length L Ch R = 1 ,23469   ,667,667,667
BEGIN DESCRIPTION:
LA PARA CREEK 37.0
END DESCRIPTION:
XS GIS Cut Line= 4
      2301038.93     13297328.16      2300844.01     13297563.87
       2299660.5     13297755.32      2299498.06     13297894.55
#Sta/Elev= 30
  4254.4  165.16  4331.4  165.46  4377.6  163.51  4446.6  158.82  4524.8  153.13
    4717  144.32    4749  142.94  4779.4  131.06  4789.5  131.27  4801.4  137.98
  4816.9  139.94    4830  140.39  4858.1   135.8  4863.1  139.78  4870.5  139.27
  4931.3  130.22  4989.1  126.21  4991.8  125.71  4995.1  126.21  5022.5  127.61
  5048.2  135.62    5063  136.21  5093.4  145.98  5109.9  147.65  5227.6  147.87
  5356.7  149.58  5691.1  163.91  5804.7  166.93  5875.8  169.54  5973.1  168.18
#Mann= 10 ,-1 , 0
  4254.4     .05       0  4331.4     .08       0  4377.6     .05       0
  4446.6      .1       0    4717     .05       0  4816.9     .12       0
  4989.1     .07       0  4995.1     .12       0  5227.6      .1       0
  5804.7     .05       0
Bank Sta=4989.1,4995.1
XS Rating Curve= 0 ,0
Exp/Cntr=0.3,0.1

Type RM Length L Ch R = 1 ,22802   ,426,426,426
BEGIN DESCRIPTION:
LA PARA CREEK 36.0
END DESCRIPTION:
XS GIS Cut Line= 4
      2300951.65     13297151.43      2300659.97     13296932.67
      2300253.72      13297078.5      2299691.98     13297598.63
#Sta/Elev= 30
  4477.4   164.2  4647.2  162.05    4739  159.23  4761.8  160.49  4776.4  158.23
  4797.2  159.18  4805.5  157.04  4845.9  155.44  4908.1  149.09  4926.2  140.96
  4931.5  142.99    4940  139.31  4950.6  139.02  4982.4   127.6  5000.6  123.66
  5000.8  123.59  5003.5  123.09  5006.8  123.59  5035.6  128.45  5067.5  129.64
  5099.4  134.91  5152.5  134.42  5268.9  144.46  5319.3   143.6  5390.2  144.67
  5496.2  142.78    5744  144.78  5814.3  146.34  5899.3  150.21  6039.2  159.68
#Mann= 5 ,-1 , 0
  4477.4     .05       0    4739     .08       0  5000.6      .1       0
  5000.8     .07       0  5006.8      .1       0
Bank Sta=5000.8,5006.8
XS Rating Curve= 0 ,0
Exp/Cntr=0.3,0.1

Type RM Length L Ch R = 1 ,22376   ,445,445,445
BEGIN DESCRIPTION:
LA PARA CREEK 35.0
END DESCRIPTION:
XS GIS Cut Line= 3
      2300790.17     13296859.74      2300519.92     13296615.18
      2299791.44     13296490.17
#Sta/Elev= 30
  4482.2  161.53    4585  157.58  4676.9  150.58  4684.4  151.45  4705.3  149.43
  4804.7  145.41  4844.5  145.67  4919.9  146.09  4944.1  143.85  4960.5   140.8
  4980.2  130.06  4985.2  135.93    4991  127.99  5008.2  123.85    5011  123.35
  5014.2  123.85  5031.5  125.79  5074.7  127.42  5112.7  128.49  5132.9     131
  5165.2  133.87  5173.6   135.2  5183.7   138.7  5193.9  139.49  5241.5  138.92
  5340.2  143.33  5386.7  147.72  5439.8  154.54    5478  156.99  5585.8  157.12
#Mann= 9 ,-1 , 0
  4482.2     .05       0  4844.5      .1       0  4944.1     .08       0
  5008.2     .07       0  5014.2     .08       0  5074.7      .1       0
  5132.9     .08       0  5241.5      .1       0  5439.8     .05       0
Bank Sta=5008.2,5014.2
XS Rating Curve= 0 ,0
Exp/Cntr=0.3,0.1

Type RM Length L Ch R = 1 ,21931   ,573,573,573
BEGIN DESCRIPTION:
LA PARA CREEK 34.0
END DESCRIPTION:
XS GIS Cut Line= 3
      2301034.98     13296182.67      2300415.18     13296182.67
      2299801.69     13296224.26
#Sta/Elev= 30
  4132.2   164.4  4309.5  150.67  4389.5  145.85  4436.5  144.28  4534.7  142.79
  4599.5  139.32  4632.9  138.63  4679.5  138.86  4731.1  141.67  4819.6  138.53
  4864.5  134.65  4891.3   132.2  4899.8  129.81  4949.9  127.17  4959.9   125.5
    4997  123.09  4999.8  122.59    5003  123.09  5030.1   125.1  5060.2  129.36
  5070.2  134.37  5080.2  137.17  5089.9  141.62  5110.3  142.17  5130.3  145.14
  5170.4  145.62  5184.5  147.15  5190.5  149.26  5270.6  157.08  5366.9  157.25
#Mann= 9 ,-1 , 0
  4132.2      .1       0  4436.5     .05       0  4534.7      .1       0
  4632.9     .12       0  4731.1     .05       0  4864.5      .1       0
    4997     .07       0    5003      .1       0  5089.9     .05       0
Bank Sta=4997,5003
XS Rating Curve= 0 ,0
Exp/Cntr=0.3,0.1

Type RM Length L Ch R = 1 ,21358   ,513,513,513
BEGIN DESCRIPTION:
LA PARA CREEK 33.0
END DESCRIPTION:
XS GIS Cut Line= 2
      2300722.46     13295328.51      2300123.52     13295885.78
#Sta/Elev= 30
  4485.8  165.54  4576.8  158.77  4615.2  154.92  4714.7  149.27  4735.8  146.46
  4813.5  140.31  4884.3  137.36  4898.5   133.1  4912.7  132.07  4919.5  134.34
  4926.8  130.18    4941  127.88  4994.7  122.33  4997.4  121.83  5000.7  122.33
  5060.3   125.8    5068  125.68  5075.4  128.03  5096.4  130.29  5103.7  134.53
  5110.5  134.08  5117.9  136.48  5124.7  136.42    5132  141.19  5146.2  146.51
    5153  146.59  5160.4  150.45  5202.6  152.78  5273.2  153.99  5303.9  152.63
#Mann= 6 ,-1 , 0
  4485.8      .1       0  4576.8     .05       0  4714.7     .12       0
  4994.7     .07       0  5000.7     .12       0  5060.3      .1       0
Bank Sta=4994.7,5000.7
XS Rating Curve= 0 ,0
Exp/Cntr=0.3,0.1

Type RM Length L Ch R = 1 ,20845   ,699,699,699
BEGIN DESCRIPTION:
LA PARA CREEK 32.0
END DESCRIPTION:
XS GIS Cut Line= 3
      2300566.24     13295068.08      2299920.39     13295318.08
      2300033.79     13295863.37
#Sta/Elev= 30
  4590.3   172.5  4695.9  165.05  4736.4     164  4741.7  161.58  4771.7  157.99
  4845.4  151.94  4875.3  146.26    4889  139.95  4899.7  139.16  4905.3  141.68
  4910.6  136.23  4929.8  137.85  4942.6  136.06  4959.8  129.69  4965.1  125.43
  4974.7  121.54  4986.7  119.77  4989.5  119.27  4992.7  119.77  4996.2  121.22
  5044.2  123.74  5068.8  121.65  5104.1  129.57  5150.3   133.9  5177.8  137.81
  5221.4  140.66  5567.6  144.36  5649.3  147.77  5659.5  149.49  5839.8  151.49
#Mann= 5 ,-1 , 0
  4590.3     .05       0  4695.9      .1       0  4986.7     .07       0
  4992.7      .1       0  5150.3     .05       0
Bank Sta=4986.7,4992.7
XS Rating Curve= 0 ,0
Exp/Cntr=0.3,0.1

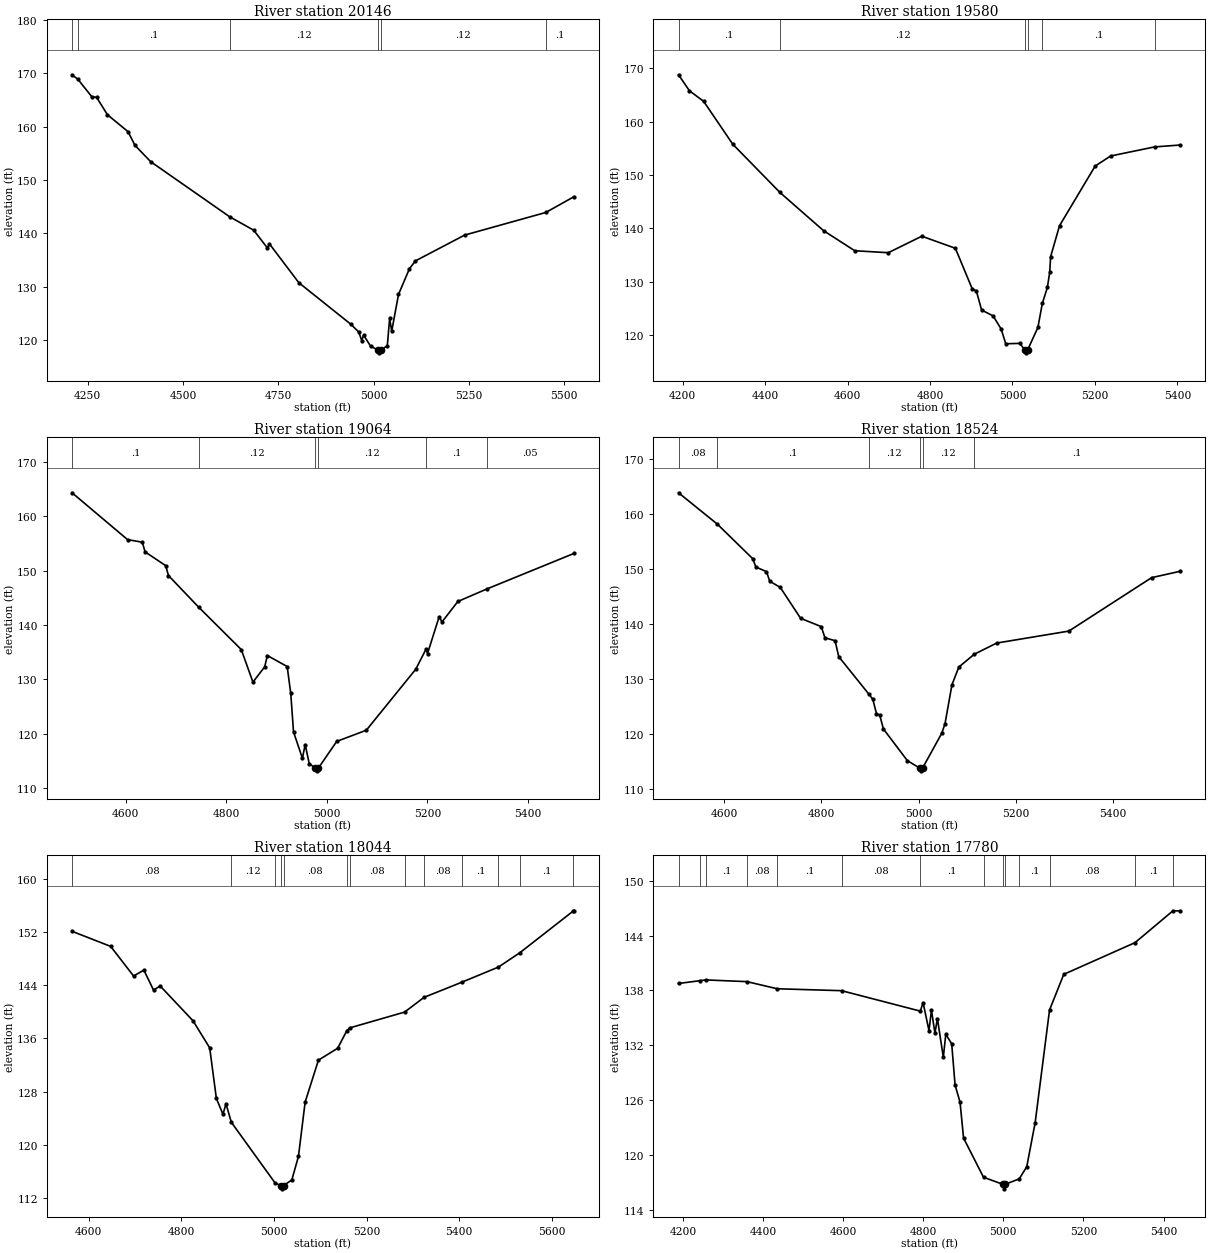
Type RM Length L Ch R = 1 ,20146   ,566,566,566
BEGIN DESCRIPTION:
LA PARA CREEK 31.0
END DESCRIPTION:
XS GIS Cut Line= 3
      2300487.76     13294946.87      2299687.72     13294746.85
      2299237.73     13294546.86
#Sta/Elev= 30
  4208.7  169.73  4224.3  168.86  4260.3  165.63  4273.2  165.49  4301.5  162.24
  4355.6  159.06  4373.7   156.5  4414.9  153.44    4622  143.11  4685.5  140.57
  4721.6  137.23  4726.7  138.02    4804  130.72  4940.6  122.92  4961.2  121.48
  4968.9  119.88  4974.1  120.89  4992.1  118.83  5012.3  118.07  5015.1  117.57
  5018.3  118.07  5036.1  118.88  5042.3  124.05  5047.7  121.63  5065.5  128.52
  5094.2  133.35    5110  134.82  5239.2  139.66  5452.1   143.9  5525.8  146.85
#Mann= 6 ,-1 , 0
  4208.7     .05       0  4224.3      .1       0    4622     .12       0
  5012.3     .07       0  5018.3     .12       0  5452.1      .1       0
Bank Sta=5012.3,5018.3
XS Rating Curve= 0 ,0
Exp/Cntr=0.3,0.1

Type RM Length L Ch R = 1 ,19580   ,516,516,516
BEGIN DESCRIPTION:
LA PARA CREEK 30.0
END DESCRIPTION:
XS GIS Cut Line= 3
      2300587.76     13294396.86      2299787.72     13294246.85
      2299437.71     13294046.85
#Sta/Elev= 30
    4190  168.78  4216.3   165.8  4251.1  163.79  4321.5  155.78    4436  146.74
  4541.9  139.58  4617.4  135.83  4698.8  135.46  4780.1  138.55  4861.5  136.29
  4902.2  128.72  4912.4   128.3  4925.1  124.73  4953.1  123.62  4972.6  121.16
  4983.6  118.41  5017.7  118.48  5030.5  117.21  5033.2  116.71  5036.5  117.21
  5061.6  121.46  5072.4  125.97  5084.6  128.95  5090.4  131.84  5092.5  134.72
  5114.1  140.52  5200.5  151.68  5237.9  153.57  5344.5  155.27  5407.1  155.63
#Mann= 6 ,-1 , 0
    4190      .1       0    4436     .12       0  5030.5     .07       0
  5036.5     .12       0  5072.4      .1       0  5344.5     .05       0
Bank Sta=5030.5,5036.5
XS Rating Curve= 0 ,0
Exp/Cntr=0.3,0.1

Type RM Length L Ch R = 1 ,19064   ,540,540,540
BEGIN DESCRIPTION:
LA PARA CREEK 29.0
END DESCRIPTION:
XS GIS Cut Line= 2
      2300498.48     13293594.14      2299587.02     13294000.39
#Sta/Elev= 30
  4493.5  164.32  4603.8  155.71  4633.2  155.23  4638.7  153.45  4679.7  150.92
  4685.2   149.1  4745.2  143.29    4830  135.49  4853.2   129.5  4876.5  132.31
  4881.9  134.39  4921.3  132.37  4928.4  127.43  4933.9  120.35  4951.6  115.49
  4957.1  118.03  4965.1  114.52  4977.3  113.69  4980.1  113.19  4983.3  113.69
  5019.8   118.6  5078.7  120.66  5177.1  131.89  5197.4  135.56  5200.4  134.76
  5223.6  141.55  5229.1  140.56  5260.7  144.33  5318.3  146.63  5491.4  153.16
#Mann= 6 ,-1 , 0
  4493.5      .1       0  4745.2     .12       0  4977.3     .07       0
  4983.3     .12       0  5197.4      .1       0  5318.3     .05       0
Bank Sta=4977.3,4983.3
XS Rating Curve= 0 ,0
Exp/Cntr=0.3,0.1

Type RM Length L Ch R = 1 ,18524   ,480,480,480
BEGIN DESCRIPTION:
LA PARA CREEK 28.0
END DESCRIPTION:
XS GIS Cut Line= 2
      2300106.54      13293050.2      2299415.15     13293818.11
#Sta/Elev= 30
  4505.7  163.93  4585.6  158.22  4658.4  151.93  4665.1   150.4  4686.8  149.57
  4693.5  147.83  4715.2  146.69  4757.1  141.07  4799.7  139.55  4807.1  137.52
  4828.1  136.99  4835.5   134.1  4897.5  127.27  4905.8  126.31  4913.3  123.72
    4920  123.44  4927.5  120.93  4976.8  115.16  5002.2  113.79    5005  113.29
  5008.2  113.79  5047.8  120.14  5054.5   121.9  5068.7  128.95  5082.9  132.19
  5114.5  134.51  5160.7  136.56  5309.4  138.74  5479.8  148.47    5539  149.64
#Mann= 6 ,-1 , 0
  4505.7     .08       0  4585.6      .1       0  4897.5     .12       0
  5002.2     .07       0  5008.2     .12       0  5114.5      .1       0
Bank Sta=5002.2,5008.2
XS Rating Curve= 0 ,0
Exp/Cntr=0.3,0.1

Type RM Length L Ch R = 1 ,18044   ,264,264,264
BEGIN DESCRIPTION:
LA PARA CREEK 27.0
END DESCRIPTION:
XS GIS Cut Line= 2
      2299623.48     13292864.99      2298936.71     13293702.65
#Sta/Elev= 30
  4564.1  152.11  4647.4  149.84  4696.9  145.38  4719.1  146.27  4739.9  143.27
  4754.3  143.88  4825.1  138.65  4861.2  134.57  4875.6  126.95  4889.8  124.58
  4896.4  126.14  4907.9  123.37  5002.6  114.21  5014.7  113.85  5017.4  113.35
  5020.7  113.85  5038.5  114.69  5052.8  118.24  5067.2   126.4  5095.9  132.72
  5137.5  134.51  5157.3  137.17  5163.3  137.57  5281.9  139.95  5323.9  142.17
  5406.6  144.48  5484.6  146.73  5531.2  148.91  5645.2  155.12  5647.3   155.2
#Mann= 13 ,-1 , 0
  4564.1     .08       0  4907.9     .12       0  5002.6     .08       0
  5014.7     .07       0  5020.7     .08       0  5157.3      .1       0
  5163.3     .08       0  5281.9     .12       0  5323.9     .08       0
  5406.6      .1       0  5484.6     .08       0  5531.2      .1       0
  5645.2     .08       0
Bank Sta=5014.7,5020.7
XS Rating Curve= 0 ,0
Exp/Cntr=0.3,0.1

Type RM Length L Ch R = 1 ,17780   ,102,102,102
BEGIN DESCRIPTION:
Mapping XS fd8dd649
END DESCRIPTION:
XS GIS Cut Line= 2
       2299602.7     13292401.39      2298883.91     13293427.48
#Sta/Elev= 30
  4189.1  138.77  4241.9  139.07  4256.9  139.16    4360  138.97  4435.5  138.19
  4596.2  137.98  4792.8  135.74  4799.6  136.68  4814.4  133.61  4820.5  135.84
  4829.3  133.33  4835.4  134.93  4850.2  130.68  4856.3   133.2  4871.1  132.17
  4879.5  127.66    4892  125.75  4900.7  121.84  4950.5  117.55  4998.6  116.78
  5001.3  116.28  5004.6  116.78  5039.7  117.37  5058.5   118.7  5079.5  123.54
  5115.4  135.87  5150.9  139.77  5328.8  143.24    5423  146.71  5441.9  146.73
#Mann= 14 ,-1 , 0
  4189.1      .1       0  4241.9     .08       0  4256.9      .1       0
    4360     .08       0  4435.5      .1       0  4596.2     .08       0
  4792.8      .1       0  4950.5     .08       0  4998.6     .07       0
  5004.6     .08       0  5039.7      .1       0  5115.4     .08       0
  5328.8      .1       0    5423     .08       0
Bank Sta=4998.6,5004.6
XS Rating Curve= 0 ,0
Exp/Cntr=0.3,0.1

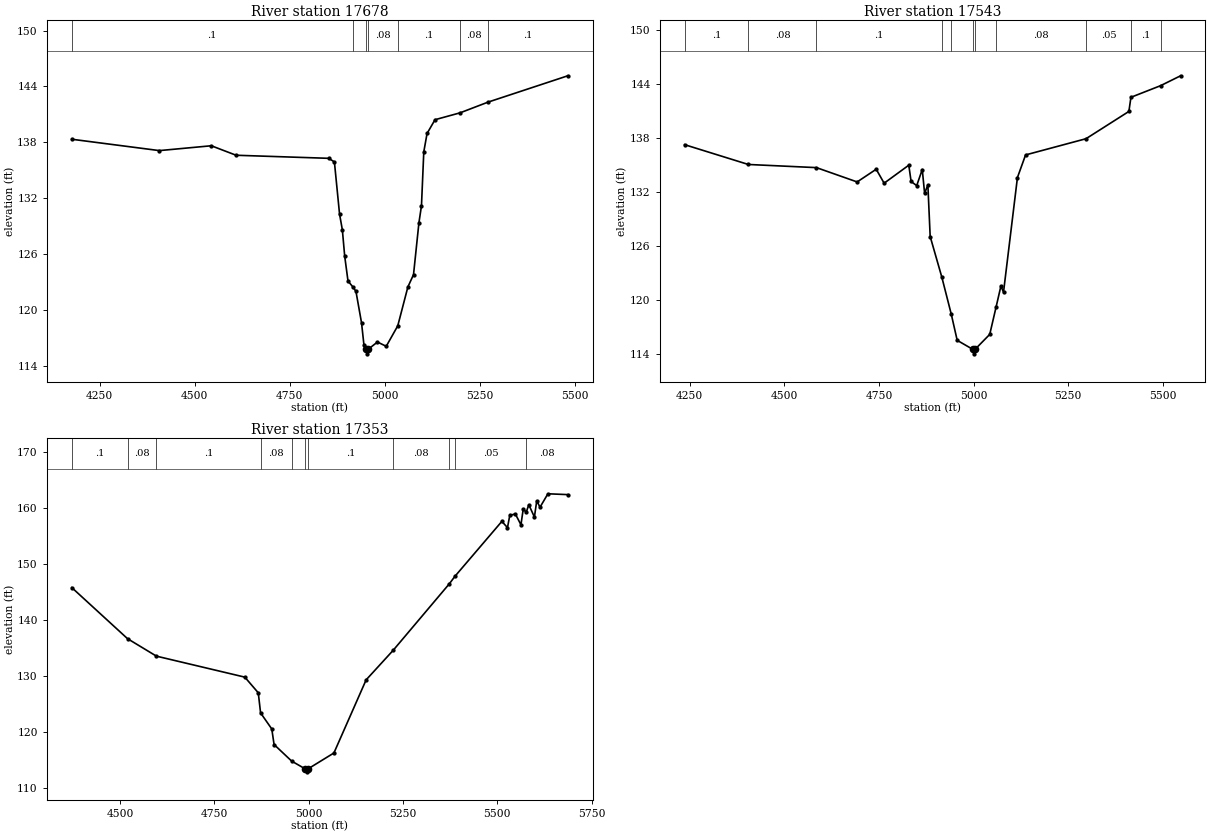
Type RM Length L Ch R = 1 ,17678   ,135,135,135
BEGIN DESCRIPTION:
Mapping XS 05c38c2c
END DESCRIPTION:
XS GIS Cut Line= 2
      2299545.41     13292323.26      2298790.18      13293385.8
#Sta/Elev= 30
    4177  138.32  4407.2   137.1  4543.7  137.62  4608.9   136.6  4852.4  136.27
  4867.2  135.88  4880.7  130.28  4888.1  128.58  4894.2  125.77  4902.9  123.09
  4915.1  122.48  4923.8  121.98  4938.5  118.59  4944.7  116.26  4950.3  115.76
    4953  115.26  4956.3  115.76  4980.3  116.53  5003.4  116.07  5033.7  118.27
  5060.3  122.45  5075.1  123.77  5089.3  129.34    5096  131.17  5102.1  136.97
  5110.7  138.94  5131.6  140.42  5197.6  141.16    5271  142.31  5480.6  145.14
#Mann= 7 ,-1 , 0
    4177      .1       0  4915.1     .08       0  4950.3     .07       0
  4956.3     .08       0  5033.7      .1       0  5197.6     .08       0
    5271      .1       0
Bank Sta=4950.3,4956.3
XS Rating Curve= 0 ,0
Exp/Cntr=0.3,0.1

Type RM Length L Ch R = 1 ,17543   ,190,190,190
BEGIN DESCRIPTION:
Mapping XS abcd98e7
END DESCRIPTION:
XS GIS Cut Line= 2
      2299467.25     13292250.39      2298706.84     13293318.09
#Sta/Elev= 30
  4236.4  137.25  4404.9  135.05  4584.9   134.7  4692.4  133.11  4742.8  134.52
  4763.7  132.97  4828.9  134.97    4835  133.16  4849.8   132.7  4864.5  134.49
  4870.7  131.84  4879.3  132.79  4885.4  127.05  4916.1  122.55    4941  118.45
  4956.8  115.52    4998  114.52  5000.8  114.02    5004  114.52  5042.8  116.18
  5059.8  119.26  5072.3  121.54  5079.2  120.87    5116   133.6  5137.5  136.11
  5297.2  137.91  5410.5  140.94  5415.9  142.51  5494.2   143.8  5547.2   144.9
#Mann= 11 ,-1 , 0
  4236.4      .1       0  4404.9     .08       0  4584.9      .1       0
  4916.1     .08       0    4941      .1       0    4998     .07       0
    5004      .1       0  5059.8     .08       0  5297.2     .05       0
  5415.9      .1       0  5494.2     .08       0
Bank Sta=4998,5004
XS Rating Curve= 0 ,0
Exp/Cntr=0.3,0.1

Type RM Length L Ch R = 1 ,17353   ,465,465,465
BEGIN DESCRIPTION:
LA PARA CREEK 26.0
END DESCRIPTION:
XS GIS Cut Line= 2
      2299337.04     13292177.48       2298582.3     13293254.93
#Sta/Elev= 30
  4371.6  145.86  4519.5  136.73  4596.1  133.61  4830.5  129.86  4866.2  127.06
  4872.3  123.47    4902   120.6  4908.1  117.82  4954.7  114.86  4991.4  113.44
  4994.1  112.94  4997.4  113.44  5066.8  116.31  5152.2  129.37  5223.9  134.65
  5373.3  146.57  5387.7  147.87  5512.2  157.69  5527.1  156.57  5533.2  158.77
    5548  159.01  5562.8  157.08  5568.9  159.91  5576.8  159.33  5583.7  160.66
  5598.5  158.46  5604.7  161.36  5613.4  160.22  5634.3  162.62  5687.1  162.47
#Mann= 11 ,-1 , 0
  4371.6      .1       0  4519.5     .08       0  4596.1      .1       0
  4872.3     .08       0  4954.7      .1       0  4991.4     .07       0
  4997.4      .1       0  5223.9     .08       0  5373.3      .1       0
  5387.7     .05       0  5576.8     .08       0
Bank Sta=4991.4,4997.4
XS Rating Curve= 0 ,0
Exp/Cntr=0.3,0.1