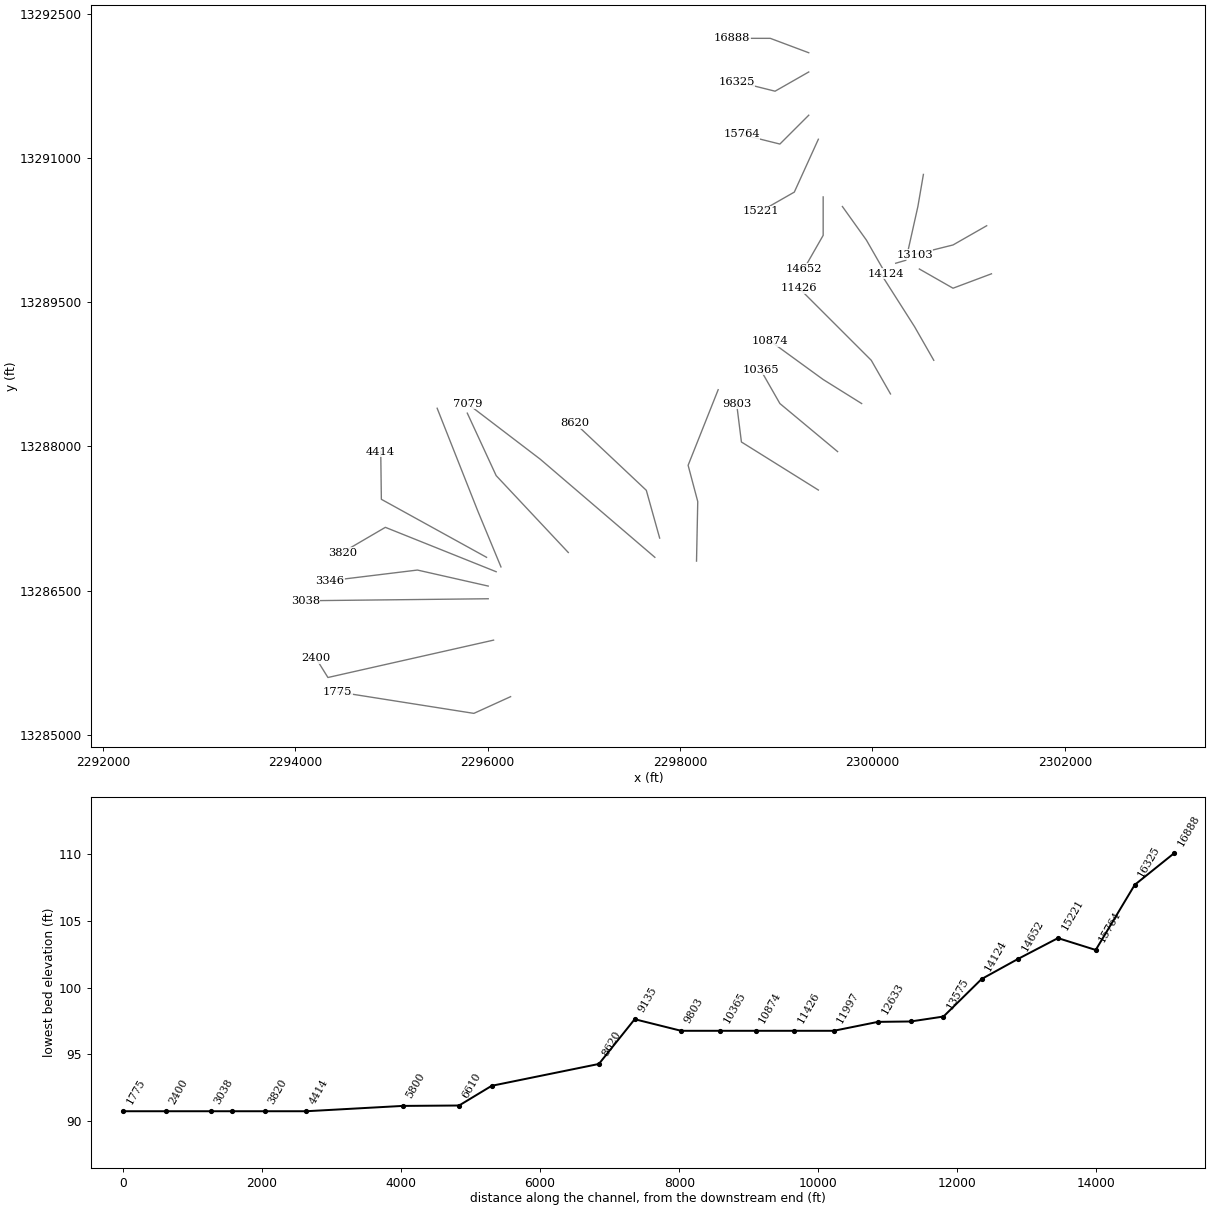
HEC-RAS study LA PARA CREEK.prj: LA PARA CREEK Base Level Engineering

--- LA PARA CREEK.g01 (geometry) --- (continued)

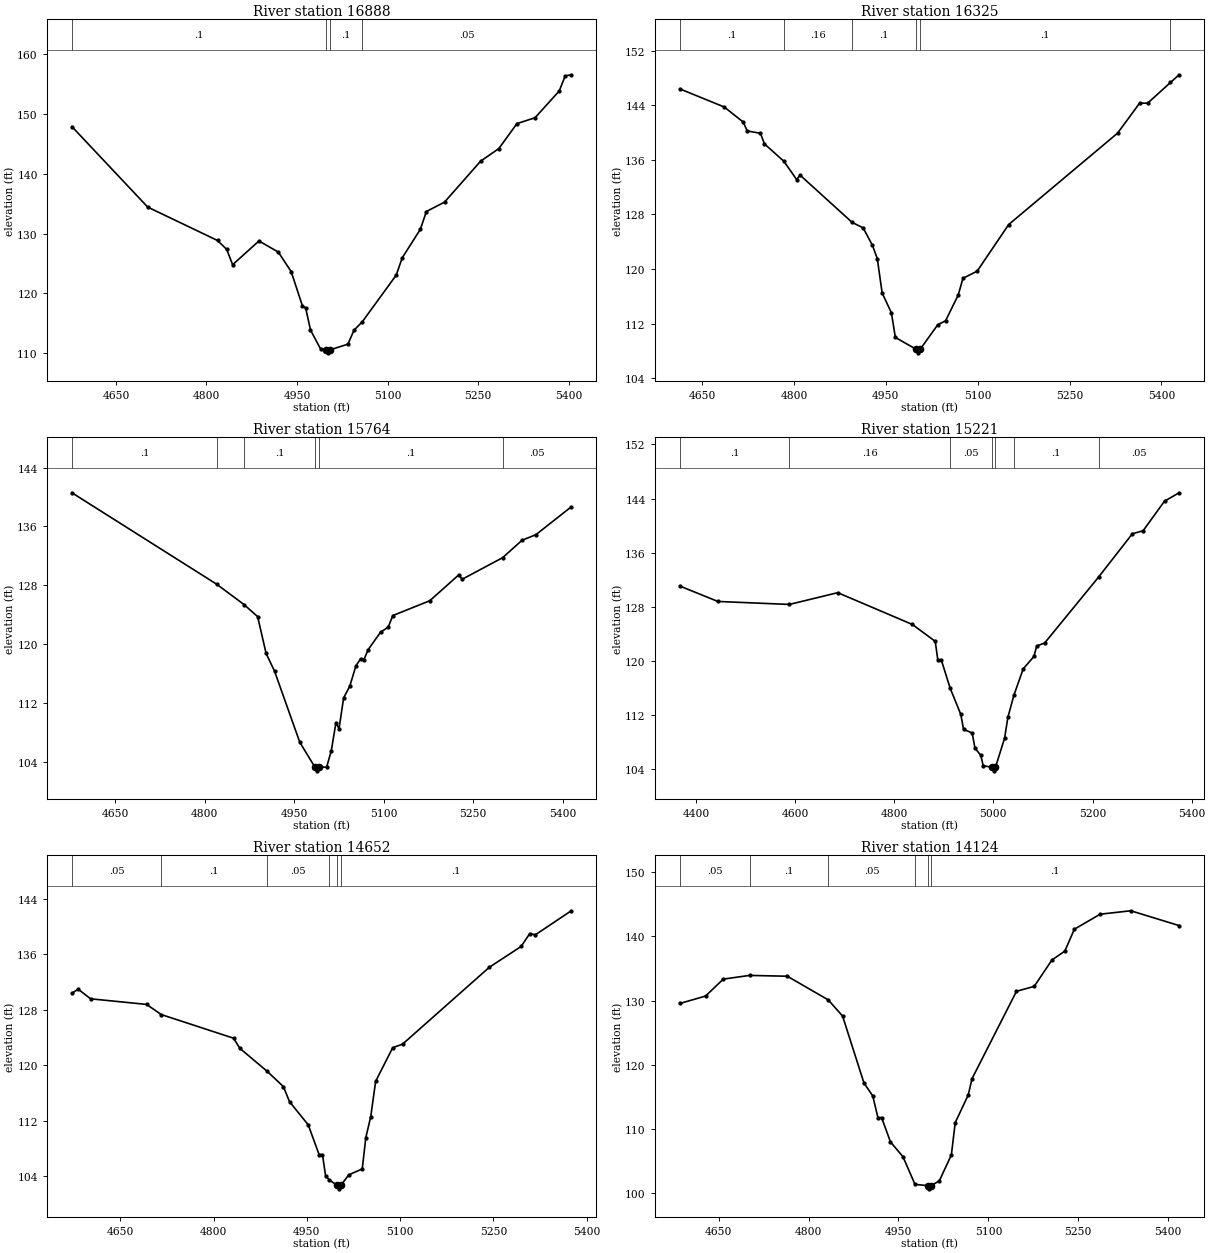
Type RM Length L Ch R = 1 ,16888   ,563,563,563
BEGIN DESCRIPTION:
LA PARA CREEK 25.0
END DESCRIPTION:
XS GIS Cut Line= 3
      2299337.76     13292096.84      2298937.72     13292246.85
      2298537.76     13292246.85
#Sta/Elev= 30
  4577.1  147.92  4702.6  134.46  4818.3  128.87  4833.5  127.38  4843.3  124.82
  4886.9  128.79  4918.9  126.94  4940.3  123.66    4959  117.91  4964.3  117.58
  4972.3  113.89  4989.2  110.68  4998.7  110.57  5001.4  110.07  5004.7  110.57
  5034.3  111.52  5044.3  113.84  5058.2  115.28  5114.3  123.07  5124.3  125.98
  5154.3  130.74  5164.3  133.72  5194.3  135.29  5254.3  142.16  5284.3  144.25
  5314.3  148.43  5344.3  149.41  5384.3  153.88  5394.3  156.41  5404.3   156.6
#Mann= 4 ,-1 , 0
  4577.1      .1       0  4998.7     .07       0  5004.7      .1       0
  5058.2     .05       0
Bank Sta=4998.7,5004.7
XS Rating Curve= 0 ,0
Exp/Cntr=0.3,0.1

Type RM Length L Ch R = 1 ,16325   ,561,561,561
BEGIN DESCRIPTION:
LA PARA CREEK 24.0
END DESCRIPTION:
XS GIS Cut Line= 3
      2299337.72     13291896.86      2298987.72     13291696.85
      2298587.75     13291796.85
#Sta/Elev= 30
  4613.6  146.42  4686.3  143.76  4717.3  141.54  4723.7  140.25  4745.3  139.91
  4751.8  138.36  4783.7  135.79  4804.4  133.12  4810.1  133.76  4894.9  126.85
  4913.1  126.03  4928.2  123.47  4936.1  121.53    4944  116.49  4959.1  113.59
  4965.6  109.97    5000  108.21  5002.8  107.71    5006  108.21  5034.8  111.83
  5047.6  112.41  5068.3   116.2    5076  118.64  5099.2  119.69  5150.7  126.53
  5328.5  139.93  5364.6  144.34  5377.5  144.32  5414.9  147.36    5429  148.49
#Mann= 6 ,-1 , 0
  4613.6      .1       0  4783.7     .16       0  4894.9      .1       0
    5000     .07       0    5006      .1       0  5414.9     .05       0
Bank Sta=5000,5006
XS Rating Curve= 0 ,0
Exp/Cntr=0.3,0.1

Type RM Length L Ch R = 1 ,15764   ,543,543,543
BEGIN DESCRIPTION:
LA PARA CREEK 23.0
END DESCRIPTION:
XS GIS Cut Line= 3
      2299337.72     13291446.85      2299037.72     13291146.85
      2298637.69     13291246.86
#Sta/Elev= 30
  4577.8  140.57  4820.4  128.15  4866.2  125.39  4888.9  123.76  4903.1  118.76
  4917.2  116.36  4959.6  106.69  4984.9  103.32  4987.7  102.82  4990.9  103.32
  5004.6  103.33  5012.4  105.58  5020.1  109.36  5025.3  108.54    5033  112.72
  5043.3  114.31  5053.6  117.08  5061.3  118.02  5066.5  117.82  5074.2  119.29
  5094.8  121.63  5107.7  122.33  5115.4   123.9  5177.3  125.91  5226.3  129.45
  5231.4  128.82  5299.4  131.76  5331.9  134.12  5355.1  134.88  5414.4  138.66
#Mann= 6 ,-1 , 0
  4577.8      .1       0  4820.4     .16       0  4866.2      .1       0
  4984.9     .07       0  4990.9      .1       0  5299.4     .05       0
Bank Sta=4984.9,4990.9
XS Rating Curve= 0 ,0
Exp/Cntr=0.3,0.1

Type RM Length L Ch R = 1 ,15221   ,569,569,569
BEGIN DESCRIPTION:
LA PARA CREEK 22.0
END DESCRIPTION:
XS GIS Cut Line= 3
      2299437.71     13291196.83      2299187.72     13290646.85
      2298837.76     13290446.87
#Sta/Elev= 30
  4367.5  131.05  4444.4  128.77  4588.5  128.33    4686  130.07  4836.5  125.37
  4882.7  122.87  4888.1  120.04  4894.7  120.18  4912.8  115.94  4934.3  112.06
  4939.8  109.85  4957.3  109.31  4962.8  107.08  4974.5  106.01  4979.5  104.48
  4998.1  104.21  5000.9  103.71  5004.1  104.21  5022.7  108.56  5029.2  111.61
  5041.4   114.9  5060.2   118.8  5081.8  120.63  5087.5  122.19  5103.4  122.62
  5212.1  132.37  5280.4  138.79    5302  139.23  5345.2  143.61  5374.7  144.85
#Mann= 7 ,-1 , 0
  4367.5      .1       0  4588.5     .16       0  4912.8     .05       0
  4998.1    .035       0  5004.1     .05       0  5041.4      .1       0
  5212.1     .05       0
Bank Sta=4998.1,5004.1
XS Rating Curve= 0 ,0
Exp/Cntr=0.3,0.1

Type RM Length L Ch R = 1 ,14652   ,528,528,528
BEGIN DESCRIPTION:
LA PARA CREEK 21.0
END DESCRIPTION:
XS GIS Cut Line= 3
      2299487.72     13290596.84      2299487.72     13290196.85
      2299287.72     13289846.86
#Sta/Elev= 30
  4572.2   130.4  4582.2  130.99  4602.2   129.6  4692.2  128.79    4716  127.32
  4832.2  123.91  4842.2  122.45  4886.1  119.14  4912.2  116.93  4922.2  114.74
  4952.2   111.4  4969.7  107.11  4975.1  107.11  4980.1  104.08  4985.6  103.49
  4998.7  102.66  5001.5  102.16  5004.7  102.66  5017.5  104.19  5039.1  105.03
  5044.9  109.57  5052.8   112.6  5060.7  117.69  5088.1  122.54  5103.9  123.05
  5243.6  134.16  5294.7  137.16  5308.4     139  5317.7  138.85  5375.3  142.31
#Mann= 6 ,-1 , 0
  4572.2     .05       0    4716      .1       0  4886.1     .05       0
  4985.6      .1       0  4998.7     .07       0  5004.7      .1       0
Bank Sta=4998.7,5004.7
XS Rating Curve= 0 ,0
Exp/Cntr=0.3,0.1

Type RM Length L Ch R = 1 ,14124   ,549,549,549
BEGIN DESCRIPTION:
LA PARA CREEK 20.0
END DESCRIPTION:
XS GIS Cut Line= 3
      2299687.72     13290496.85      2299937.72     13290146.85
      2300137.71     13289796.87
#Sta/Elev= 30
  4585.1  129.55  4628.1  130.71  4657.6  133.35  4701.4  133.93  4764.5   133.8
  4832.8  130.11  4856.7  127.59  4892.3  117.17  4907.1  115.13  4915.7  111.74
  4921.8  111.76  4936.6  107.96  4957.5  105.65  4977.5  101.34  4998.7  101.14
  5001.4  100.64  5004.7  101.14  5018.1  101.88  5038.2  105.92  5044.7  110.97
  5066.3  115.26  5072.8  117.84  5146.9  131.45  5176.5  132.22    5206  136.33
  5227.6  137.72  5243.4  141.13  5286.6  143.48  5337.7  144.01  5418.3   141.7
#Mann= 6 ,-1 , 0
  4585.1     .05       0  4701.4      .1       0  4832.8     .05       0
  4977.5      .1       0  4998.7     .07       0  5004.7      .1       0
Bank Sta=4998.7,5004.7
XS Rating Curve= 0 ,0
Exp/Cntr=0.3,0.1

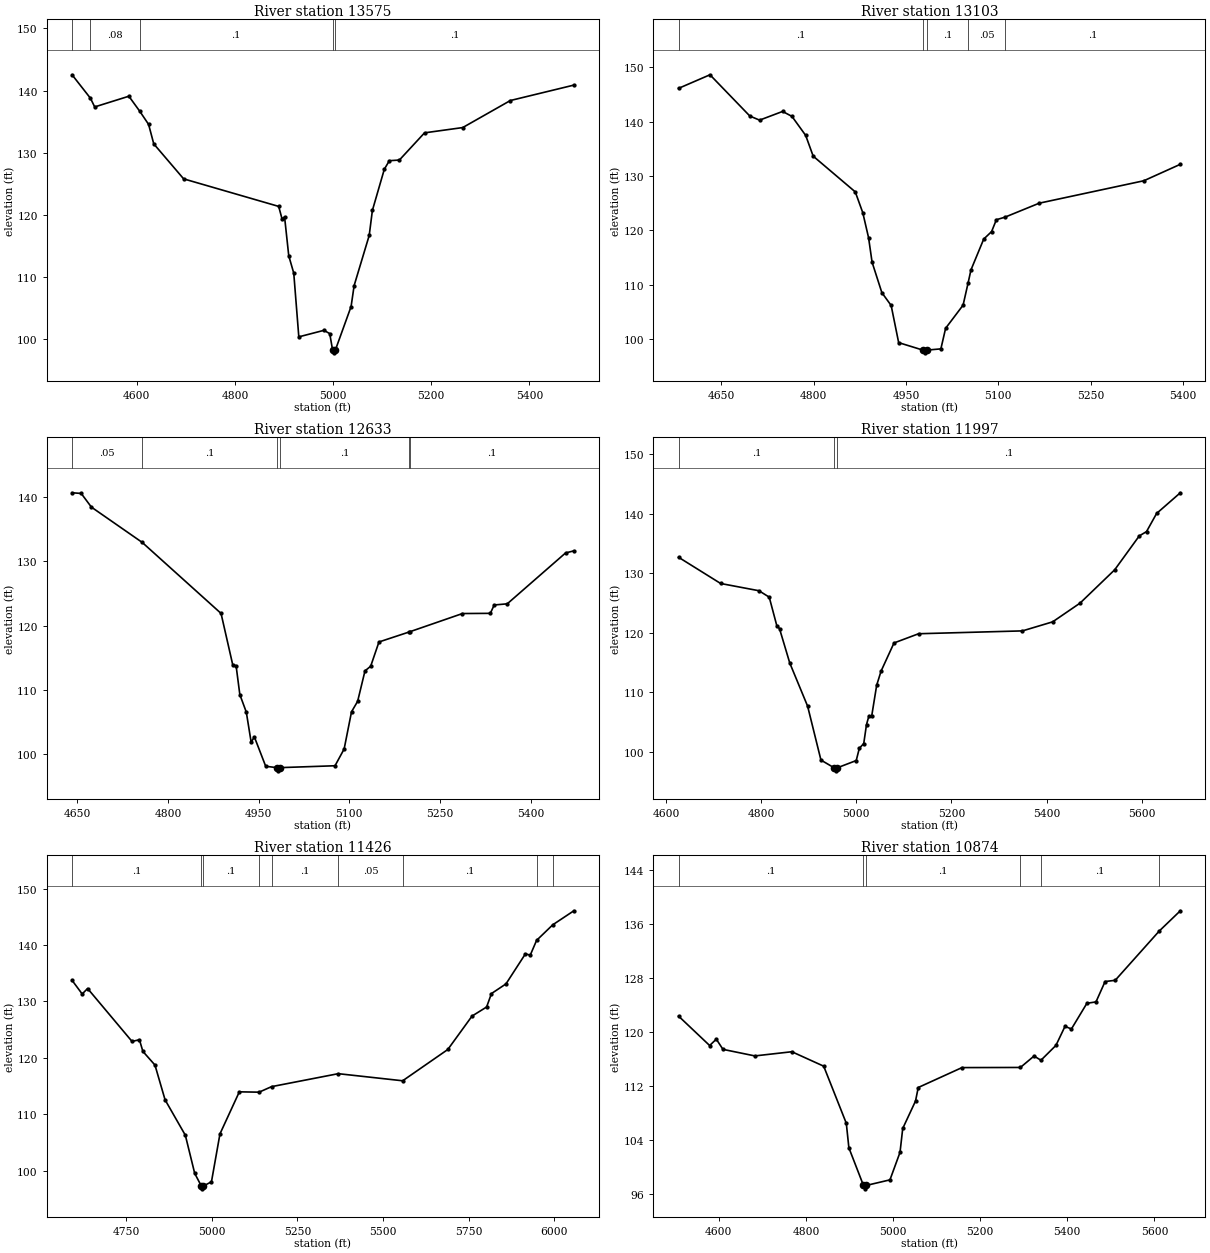
Type RM Length L Ch R = 1 ,13575   ,472,472,472
BEGIN DESCRIPTION:
LA PARA CREEK 19.0
END DESCRIPTION:
XS GIS Cut Line= 4
      2300529.92     13290830.89      2300472.63     13290497.56
      2300347.63     13289937.67      2300241.77     13289906.68
#Sta/Elev= 30
  4468.2  142.54  4505.6  138.77  4514.3  137.37  4583.9  139.09  4606.3  136.65
  4624.1  134.56  4634.6  131.43  4695.5   125.8  4889.1  121.37    4896  119.34
  4901.1  119.68  4909.6  113.43  4919.8  110.64  4930.1  100.39  4981.3  101.44
  4993.1  100.91  4998.8   98.32  5001.6   97.82  5004.8   98.32  5036.6  105.27
  5042.8  108.64  5073.5   116.7    5080  120.73  5104.3  127.35  5114.5  128.72
    5135  128.83  5186.2   133.2    5264  134.05  5361.1   138.4  5490.4  140.88
#Mann= 5 ,-1 , 0
  4468.2      .1       0  4505.6     .08       0  4606.3      .1       0
  4998.8     .07       0  5004.8      .1       0
Bank Sta=4998.8,5004.8
XS Rating Curve= 0 ,0
Exp/Cntr=0.3,0.1

Type RM Length L Ch R = 1 ,13103   ,470,470,470
BEGIN DESCRIPTION:
LA PARA CREEK 18.0
END DESCRIPTION:
XS GIS Cut Line= 3
       2301187.7     13290296.84      2300837.72     13290096.85
      2300437.72     13289996.85
#Sta/Elev= 30
  4580.3  146.14  4631.4  148.64  4696.2  141.04    4712  140.29  4749.4  141.89
  4764.6  140.98  4786.9  137.48  4799.1  133.66  4867.5  127.08  4879.7  123.25
  4889.1  118.65  4894.8  114.14  4910.7  108.53  4925.8  106.17    4938   99.33
  4977.5   97.95  4980.3   97.45  4983.5   97.95  5006.6   98.18  5014.3  101.97
  5042.7  106.23  5050.9  110.35  5055.5  112.72  5076.2  118.39    5089  119.77
  5096.8  121.96  5110.6  122.42  5166.4     125  5336.4  129.13  5395.7  132.16
#Mann= 5 ,-1 , 0
  4580.3      .1       0  4977.5     .07       0  4983.5      .1       0
  5050.9     .05       0  5110.6      .1       0
Bank Sta=4977.5,4983.5
XS Rating Curve= 0 ,0
Exp/Cntr=0.3,0.1

Type RM Length L Ch R = 1 ,12633   ,636,636,636
BEGIN DESCRIPTION:
LA PARA CREEK 17.0
END DESCRIPTION:
XS GIS Cut Line= 3
      2301237.68     13289796.84      2300837.72     13289646.85
      2300487.69     13289846.87
#Sta/Elev= 30
  4641.3  140.64  4656.4  140.54  4673.3  138.41  4757.3  132.93  4887.8  121.89
  4907.4   113.8  4912.7  113.76  4918.9  109.27  4929.6  106.55  4937.6  101.89
    4943  102.68  4961.7   98.13    4980   97.92  4982.8   97.42    4986   97.92
  5076.4   98.21  5091.5  100.82  5103.7   106.6  5113.8  108.22    5126  112.96
  5135.4  113.68  5149.1  117.45  5199.3  119.01  5201.1  119.07  5287.3  121.87
  5333.4   121.9  5339.8   123.2  5361.4  123.38  5457.9  131.29  5471.6  131.61
#Mann= 6 ,-1 , 0
  4641.3     .05       0  4757.3      .1       0    4980     .07       0
    4986      .1       0  5199.3     .05       0  5201.1      .1       0
Bank Sta=4980,4986
XS Rating Curve= 0 ,0
Exp/Cntr=0.3,0.1

Type RM Length L Ch R = 1 ,11997   ,571,571,571
BEGIN DESCRIPTION:
LA PARA CREEK 16.0
END DESCRIPTION:
XS GIS Cut Line= 3
      2300637.71     13288896.87      2300437.72     13289246.85
      2300087.73     13289796.85
#Sta/Elev= 30
  4626.3  132.66  4714.8  128.25  4795.4  127.03    4817  125.95  4832.9  121.16
  4838.6  120.66  4860.2  114.87  4897.7  107.62  4925.7   98.56  4953.7   97.25
  4956.4   96.75  4959.7   97.25  4999.9   98.48  5006.4  100.54  5015.7  101.34
  5021.5  104.54  5026.5  105.95  5032.4  105.95  5042.9  111.15  5052.2  113.53
  5079.3  118.25    5131   119.8  5349.4  120.28  5412.9   121.8  5470.5  124.95
  5543.3  130.55    5595  136.25  5610.2  136.97  5631.4  140.02  5681.3   143.5
#Mann= 3 ,-1 , 0
  4626.3      .1       0  4953.7     .07       0  4959.7      .1       0
Bank Sta=4953.7,4959.7
XS Rating Curve= 0 ,0
Exp/Cntr=0.3,0.1

Type RM Length L Ch R = 1 ,11426   ,552,552,552
BEGIN DESCRIPTION:
LA PARA CREEK 15.0
END DESCRIPTION:
XS GIS Cut Line= 3
       2300187.7     13288546.89      2299987.72     13288896.85
      2299237.74     13289646.83
#Sta/Elev= 30
  4592.9  133.74  4622.4  131.32  4638.2  132.29  4767.8   122.9  4789.4   123.2
  4799.5  121.13  4834.7  118.71  4864.2  112.54  4923.3  106.26  4950.6    99.5
  4969.9   97.25  4972.7   96.75  4975.9   97.25  4999.5      98  5024.3   106.5
  5080.8  113.96  5138.5   113.9  5174.8  114.88  5369.4  117.18  5557.2  115.92
  5688.9  121.47  5759.6   127.4  5802.1  129.01  5816.2  131.39  5858.6  133.11
  5915.2  138.43  5929.4  138.21  5947.9  140.83    5995  143.59  6056.6  146.08
#Mann= 9 ,-1 , 0
  4592.9      .1       0  4969.9     .07       0  4975.9      .1       0
  5138.5     .05       0  5174.8      .1       0  5369.4     .05       0
  5557.2      .1       0  5947.9     .05       0    5995      .1       0
Bank Sta=4969.9,4975.9
XS Rating Curve= 0 ,0
Exp/Cntr=0.3,0.1

Type RM Length L Ch R = 1 ,10874   ,509,509,509
BEGIN DESCRIPTION:
LA PARA CREEK 14.0
END DESCRIPTION:
XS GIS Cut Line= 3
      2299887.75     13288446.84      2299487.72     13288696.85
      2298937.73     13289096.85
#Sta/Elev= 30
  4507.7  122.34  4579.1  117.98  4594.4  118.92  4609.7  117.41  4682.9  116.44
  4767.8  117.06  4840.9  114.92  4892.8  106.46  4898.7  102.83  4932.2   97.25
    4935   96.75  4938.2   97.25    4993   98.08  5016.1  102.16  5022.3  105.69
  5051.7  109.76  5057.9  111.76  5158.3  114.71  5292.4  114.73  5323.7  116.42
  5339.6   115.8    5374     118  5394.8  120.82  5409.5  120.43  5445.1  124.24
  5465.9  124.44  5486.8  127.46    5510  127.64  5611.1  134.94  5659.5  137.94
#Mann= 6 ,-1 , 0
  4507.7      .1       0  4932.2     .07       0  4938.2      .1       0
  5292.4     .05       0  5339.6      .1       0  5611.1     .05       0
Bank Sta=4932.2,4938.2
XS Rating Curve= 0 ,0
Exp/Cntr=0.3,0.1

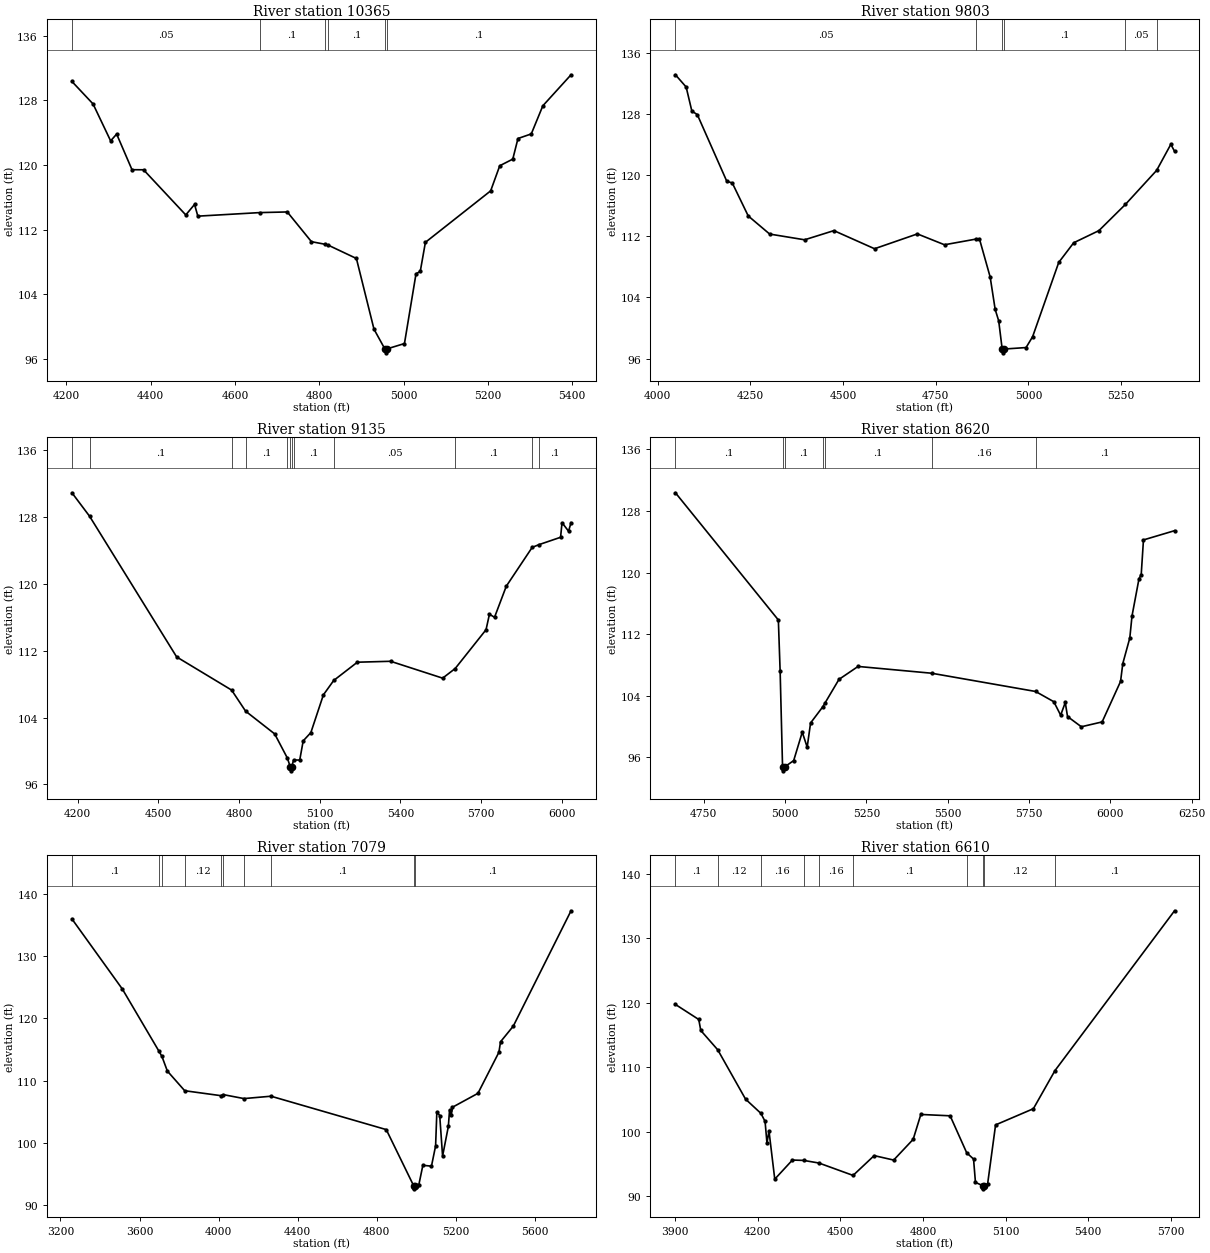
Type RM Length L Ch R = 1 ,10365   ,562,562,562
BEGIN DESCRIPTION:
LA PARA CREEK 13.0
END DESCRIPTION:
XS GIS Cut Line= 3
      2299637.72     13287946.85      2299037.72     13288446.85
      2298837.74     13288796.82
#Sta/Elev= 30
  4213.2  130.34  4263.3  127.56    4305  122.99  4319.3  123.83  4355.7  119.42
  4383.1  119.41  4483.3  113.82  4504.1  115.12  4511.9  113.67  4658.8  114.11
  4724.1  114.19  4781.4  110.51  4812.7   110.2  4821.2  110.08  4888.1  108.43
  4929.8   99.68  4955.4   97.25  4958.2   96.75  4961.4   97.25  5002.1    97.9
  5029.5  106.53  5039.6  106.83  5051.8  110.43  5206.6   116.8  5228.2  119.91
  5259.1  120.73  5271.4  123.28    5303  123.85  5330.4  127.33  5397.3  131.17
#Mann= 6 ,-1 , 0
  4213.2     .05       0  4658.8      .1       0  4812.7     .05       0
  4821.2      .1       0  4955.4     .07       0  4961.4      .1       0
Bank Sta=4955.4,4961.4
XS Rating Curve= 0 ,0
Exp/Cntr=0.3,0.1

Type RM Length L Ch R = 1 ,9803    ,668,668,668
BEGIN DESCRIPTION:
LA PARA CREEK 12.0
END DESCRIPTION:
XS GIS Cut Line= 3
      2299437.75     13287546.84      2298637.72     13288046.85
      2298587.73     13288446.81
#Sta/Elev= 30
  4047.6  133.13  4076.5  131.53  4091.9  128.38  4106.6  127.92  4186.2  119.19
  4200.9  118.98    4244  114.66  4301.8  112.29  4396.1  111.54  4475.1  112.74
  4584.8  110.37  4700.3  112.31  4773.5  110.89  4858.2  111.63  4867.8  111.65
  4896.7  106.67  4910.2  102.43  4919.7  100.94  4929.1   97.25  4931.8   96.75
  4935.1   97.25  4993.5   97.44  5011.2   98.86  5081.7  108.58    5122  111.15
  5190.1  112.74  5261.8  116.18  5345.8  120.62  5384.1  124.03  5394.1  123.12
#Mann= 6 ,-1 , 0
  4047.6     .05       0  4858.2      .1       0  4929.1     .07       0
  4935.1      .1       0  5261.8     .05       0  5345.8      .1       0
Bank Sta=4929.1,4935.1
XS Rating Curve= 0 ,0
Exp/Cntr=0.3,0.1

Type RM Length L Ch R = 1 ,9135    ,515,515,515
BEGIN DESCRIPTION:
LA PARA CREEK 11.0
END DESCRIPTION:
XS GIS Cut Line= 4
      2298170.95     13286807.42      2298183.72     13287426.87
      2298083.58     13287804.19      2298396.07     13288590.61
#Sta/Elev= 30
  4178.7  130.92  4244.3  128.11  4568.2  111.26  4772.6  107.29  4824.5  104.77
  4932.8  102.04  4979.9   99.15  4990.4   98.12  4993.1   97.62  4996.4   98.12
    5003   98.92  5025.9   98.91  5038.8  101.21  5067.3   102.2  5113.9  106.72
  5152.2  108.44  5240.2  110.63  5363.7  110.74  5557.4  108.72    5604  109.87
  5718.8  114.52  5731.4  116.37  5750.4  116.01  5794.1  119.73  5890.4  124.38
  5915.8  124.71    5996  125.59  6001.4  127.34  6025.7  126.32  6034.9  127.34
#Mann= 12 ,-1 , 0
  4178.7     .08       0  4244.3      .1       0  4772.6     .05       0
  4824.5      .1       0  4979.9     .05       0  4990.4     .03       0
  4996.4     .05       0    5003      .1       0  5152.2     .05       0
    5604      .1       0  5890.4     .05       0  5915.8      .1       0
Bank Sta=4990.4,4996.4
XS Rating Curve= 0 ,0
Exp/Cntr=0.3,0.1

Type RM Length L Ch R = 1 ,8620    ,1541,1541,1541
BEGIN DESCRIPTION:
LA PARA CREEK 10.0
END DESCRIPTION:
XS GIS Cut Line= 3
      2297787.71     13287046.89      2297648.83     13287544.08
      2296908.13     13288241.96
#Sta/Elev= 30
  4663.3  130.35  4979.6  113.84  4985.1  107.16  4992.5   94.76  4995.3   94.26
  4998.5   94.76  5026.7   95.59  5053.1   99.28  5068.2   97.33  5078.6  100.47
  5116.3  102.58  5123.2  103.08  5165.9  106.13  5224.6  107.81  5450.4  106.93
  5770.3  104.56  5826.2  103.23  5847.2  101.48  5861.4  103.13  5868.3  101.31
  5910.8   99.98  5974.7  100.61  6031.3  105.86  6038.2  108.19  6059.7   111.5
  6066.5  114.36  6087.9  119.18  6094.8  119.73  6101.7  124.23  6197.2  125.43
#Mann= 7 ,-1 , 0
  4663.3      .1       0  4992.5     .07       0  4998.5      .1       0
  5116.3     .16       0  5123.2      .1       0  5450.4     .16       0
  5770.3      .1       0
Bank Sta=4992.5,4998.5
XS Rating Curve= 0 ,0
Exp/Cntr=0.3,0.1

Type RM Length L Ch R = 1 ,7079    ,469,469,469
BEGIN DESCRIPTION:
LA PARA CREEK 9.0
END DESCRIPTION:
XS GIS Cut Line= 3
      2297737.71     13286846.87      2296546.88      13287867.1
      2295787.74     13288446.84
#Sta/Elev= 30
  3258.4  135.95  3513.6  124.68  3696.8   114.8  3713.5  113.87  3740.8  111.53
  3828.6  108.37  4013.6  107.57  4022.8  107.75  4128.2  107.11  4264.8  107.49
  4847.6  102.13    4986   93.12  4988.8   92.62    4992   93.12  5011.7   93.19
  5032.6    96.4  5076.1   96.26    5097   99.52  5103.3  104.96  5117.8  104.39
  5132.3   97.88  5161.4  102.63  5167.7  105.32  5175.9   104.4  5182.2  105.72
    5311  107.95  5417.1  114.55  5425.3  116.23  5489.7  118.74  5781.7  137.26
#Mann= 10 ,-1 , 0
  3258.4      .1       0  3696.8     .12       0  3713.5      .1       0
  3828.6     .12       0  4013.6     .16       0  4022.8      .1       0
  4128.2     .16       0  4264.8      .1       0    4986     .07       0
    4992      .1       0
Bank Sta=4986,4992
XS Rating Curve= 0 ,0
Exp/Cntr=0.3,0.1

Type RM Length L Ch R = 1 ,6610    ,810,810,810
BEGIN DESCRIPTION:
LA PARA CREEK 8.0
END DESCRIPTION:
XS GIS Cut Line= 3
       2296837.7     13286896.87      2296087.72     13287696.85
       2295787.7      13288346.9
#Sta/Elev= 30
  3900.9  119.72  3985.6  117.39  3992.9  115.69  4054.5  112.69  4155.6  105.04
  4211.3  102.84  4226.4  101.59  4233.3   98.24  4240.6  100.12  4261.6   92.64
  4325.6    95.6  4366.2   95.55  4422.1   95.14    4546   93.22  4622.6   96.29
  4693.4    95.6  4764.2   98.81  4792.1  102.67  4898.5  102.46  4958.7   96.72
  4983.5   95.76  4990.4   92.14  5016.5   91.64  5019.2   91.14  5022.5   91.64
  5034.6    91.9  5063.5  101.05  5200.8  103.56  5279.2  109.47  5713.4  134.24
#Mann= 10 ,-1 , 0
  3900.9      .1       0  4054.5     .12       0  4211.3     .16       0
  4366.2      .1       0  4422.1     .16       0    4546      .1       0
  4958.7     .12       0  5016.5     .07       0  5022.5     .12       0
  5279.2      .1       0
Bank Sta=5016.5,5022.5
XS Rating Curve= 0 ,0
Exp/Cntr=0.3,0.1

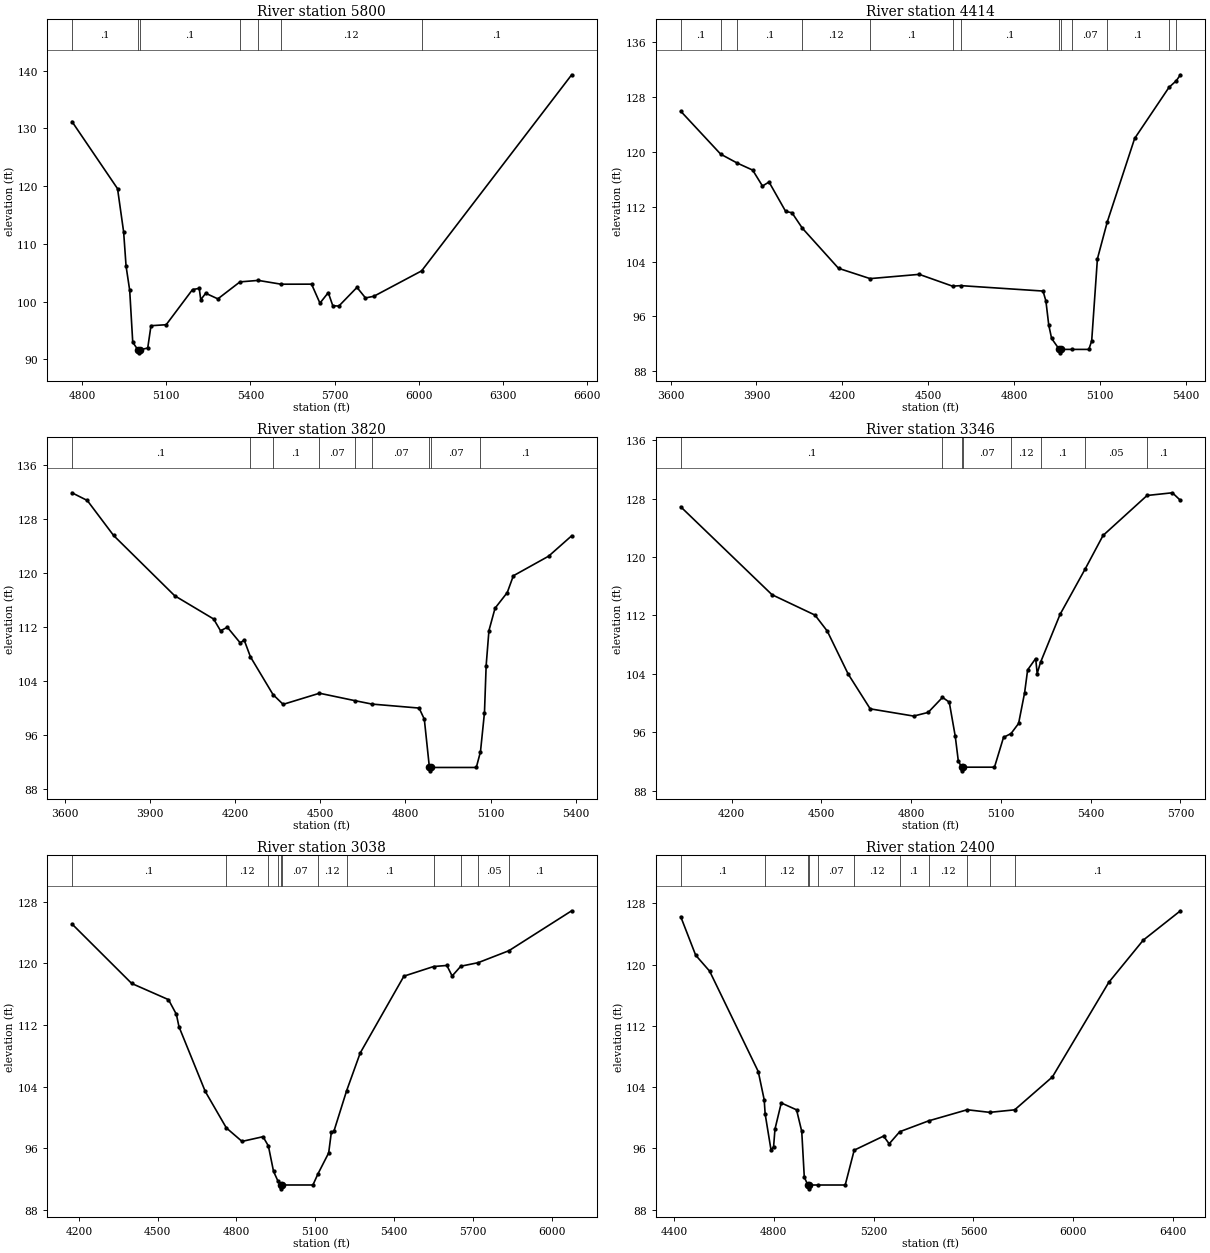
Type RM Length L Ch R = 1 ,5800    ,1386,1386,1386
BEGIN DESCRIPTION:
LA PARA CREEK 7.0
END DESCRIPTION:
XS GIS Cut Line= 3
      2296137.71     13286746.88      2295896.08     13287330.24
      2295474.22      13288397.9
#Sta/Elev= 30
  4764.3  131.18  4926.6  119.55  4948.3  112.05    4957  106.11  4969.9  101.93
  4980.7   92.95  4999.4   91.61  5002.1   91.11  5005.4   91.61  5034.1   91.95
  5045.7   95.81  5099.8   95.98  5193.6  102.07  5217.5  102.28  5222.9  100.31
  5240.5  101.43  5283.8  100.46  5362.5   103.4  5427.5  103.66  5509.1     103
  5617.5  103.01  5647.3   99.72    5677  101.54  5693.1   99.27  5714.6   99.21
  5779.2  102.45  5809.5  100.62  5839.3  100.91  6009.4  105.31  6543.7  139.28
#Mann= 7 ,-1 , 0
  4764.3      .1       0  4999.4     .07       0  5005.4      .1       0
  5362.5     .16       0  5427.5      .1       0  5509.1     .12       0
  6009.4      .1       0
Bank Sta=4999.4,5005.4
XS Rating Curve= 0 ,0
Exp/Cntr=0.3,0.1

Type RM Length L Ch R = 1 ,4414    ,594,594,594
BEGIN DESCRIPTION:
LA PARA CREEK 6.0
END DESCRIPTION:
XS GIS Cut Line= 3
      2295987.73     13286846.85       2294894.1     13287450.43
      2294887.72     13287946.86
#Sta/Elev= 30
  3635.5  125.87  3775.1  119.62    3833  118.32  3886.8   117.3  3921.1  114.98
  3943.9  115.57  4002.2  111.28    4024   111.1  4060.3  108.85  4186.7  103.01
    4297  101.51  4468.6  102.13  4585.2  100.41    4614  100.49  4901.1    99.7
  4911.1   98.27  4921.1   94.76  4931.1    92.8  4958.1   91.21  4960.8   90.71
  4964.1   91.21  5001.2   91.21  5061.1   91.21  5071.1   92.44  5091.1  104.39
  5125.6  109.77  5221.1   121.9  5341.2  129.34  5366.4  130.29  5381.1  131.17
#Mann= 13 ,-1 , 0
  3635.5      .1       0  3775.1     .12       0    3833      .1       0
  4060.3     .12       0    4297      .1       0  4585.2     .12       0
    4614      .1       0  4958.1     .07       0  4964.1      .1       0
  5001.2     .07       0  5125.6      .1       0  5341.2     .16       0
  5366.4      .1       0
Bank Sta=4958.1,4964.1
XS Rating Curve= 0 ,0
Exp/Cntr=0.3,0.1

Type RM Length L Ch R = 1 ,3820    ,474,474,474
BEGIN DESCRIPTION:
LA PARA CREEK 5.0
END DESCRIPTION:
XS GIS Cut Line= 3
      2296087.72     13286696.86      2294935.76     13287158.76
      2294487.71     13286896.85
#Sta/Elev= 30
  3625.2  131.95  3679.1  130.81  3771.8  125.62    3987  116.68  4124.2  113.23
  4148.4  111.49  4172.6     112  4217.8  109.69  4231.8  110.11  4253.8  107.62
  4333.4  102.02    4369  100.57    4497  102.22  4622.8  101.11    4682  100.61
  4847.9  100.02  4866.3   98.37  4884.2   91.21    4887   90.71  4890.2   91.21
  5049.4   91.21  5064.1   93.55  5078.2   99.36  5084.1  106.33  5093.9  111.51
  5115.4  114.83  5158.4  117.15  5179.9  119.64  5304.2  122.55  5385.3  125.57
#Mann= 9 ,-1 , 0
  3625.2      .1       0  4253.8     .12       0  4333.4      .1       0
    4497     .07       0  4622.8      .1       0    4682     .07       0
  4884.2     .07       0  4890.2     .07       0  5064.1      .1       0
Bank Sta=4884.2,4890.2
XS Rating Curve= 0 ,0
Exp/Cntr=0.3,0.1

Type RM Length L Ch R = 1 ,3346    ,308,308,308
BEGIN DESCRIPTION:
LA PARA CREEK 4.0
END DESCRIPTION:
XS GIS Cut Line= 3
      2296005.23     13286547.65       2295269.1     13286714.32
      2294361.01     13286603.41
#Sta/Elev= 30
  4030.2  126.87  4335.2  114.83  4478.8  112.04  4519.8  109.85  4589.6  103.97
  4663.3    99.2  4808.4   98.21  4856.9   98.71  4904.8  100.77  4927.4  100.12
  4947.5   95.43  4957.6   92.08  4968.5   91.21  4971.2   90.71  4974.5   91.21
  5078.5   91.21  5108.7   95.29  5133.9   95.82  5159.1    97.2  5179.2  101.41
  5189.3  104.54  5216.1  106.09  5221.2  104.04  5232.4  105.57  5297.7  112.14
  5382.4  118.42  5441.2  122.94  5588.3  128.42  5672.9  128.79  5699.8  127.75
#Mann= 8 ,-1 , 0
  4030.2      .1       0  4904.8     .07       0  4968.5     .07       0
  4974.5     .07       0  5133.9     .12       0  5232.4      .1       0
  5382.4     .05       0  5588.3      .1       0
Bank Sta=4968.5,4974.5
XS Rating Curve= 0 ,0
Exp/Cntr=0.3,0.1

Type RM Length L Ch R = 1 ,3038    ,638,638,638
BEGIN DESCRIPTION:
LA PARA CREEK 3.0
END DESCRIPTION:
XS GIS Cut Line= 2
      2296005.17     13286415.71      2294102.59     13286394.88
#Sta/Elev= 30
  4173.6  125.11  4401.1  117.38  4541.1  115.28  4571.1  113.38  4581.1  111.76
  4681.1  103.36  4761.5   98.62  4821.1   96.87  4901.1   97.48  4921.5   96.28
  4941.1   92.98  4957.8   91.73  4968.1   91.21  4970.8   90.71  4974.1   91.21
  5091.1   91.21  5110.2   92.65  5151.1   95.38  5161.1   98.03  5171.1    98.2
  5219.4  103.45  5271.1  108.35  5437.6  118.33  5550.7  119.58  5601.1  119.72
  5621.1  118.35  5654.2  119.62  5720.1  120.08  5837.1  121.63  6076.3  126.82
#Mann= 12 ,-1 , 0
  4173.6      .1       0  4761.5     .12       0  4921.5      .1       0
  4957.8     .07       0  4968.1     .07       0  4974.1     .07       0
  5110.2     .12       0  5219.4      .1       0  5550.7     .05       0
  5654.2      .1       0  5720.1     .05       0  5837.1      .1       0
Bank Sta=4968.1,4974.1
XS Rating Curve= 0 ,0
Exp/Cntr=0.3,0.1

Type RM Length L Ch R = 1 ,2400    ,625,625,625
BEGIN DESCRIPTION:
LA PARA CREEK 2.0
END DESCRIPTION:
XS GIS Cut Line= 3
      2296060.76     13285985.15      2294338.54     13285596.26
      2294213.55     13285797.64
#Sta/Elev= 30
  4427.1  126.26    4487  121.23    4543  119.14  4737.8  106.03  4761.6  102.35
  4765.5  100.47    4789   95.78  4799.3   96.22  4804.8   98.51    4830  101.93
  4891.3  101.03  4912.1   98.21  4922.3   92.23  4936.6   91.21  4939.3   90.71
  4942.6   91.21  4975.3   91.21  5086.3   91.21  5122.3   95.76  5240.1    97.6
  5262.5   96.59  5304.7   98.17  5420.7   99.59  5575.2  101.04  5665.4   100.7
  5765.4  101.03  5916.7  105.33  6142.3  117.67  6280.6  123.19  6429.7  127.03
#Mann= 11 ,-1 , 0
  4427.1      .1       0  4765.5     .12       0  4936.6     .07       0
  4942.6     .12       0  4975.3     .07       0  5122.3     .12       0
  5304.7      .1       0  5420.7     .12       0  5575.2      .1       0
  5665.4     .12       0  5765.4      .1       0
Bank Sta=4936.6,4942.6
XS Rating Curve= 0 ,0
Exp/Cntr=0.3,0.1

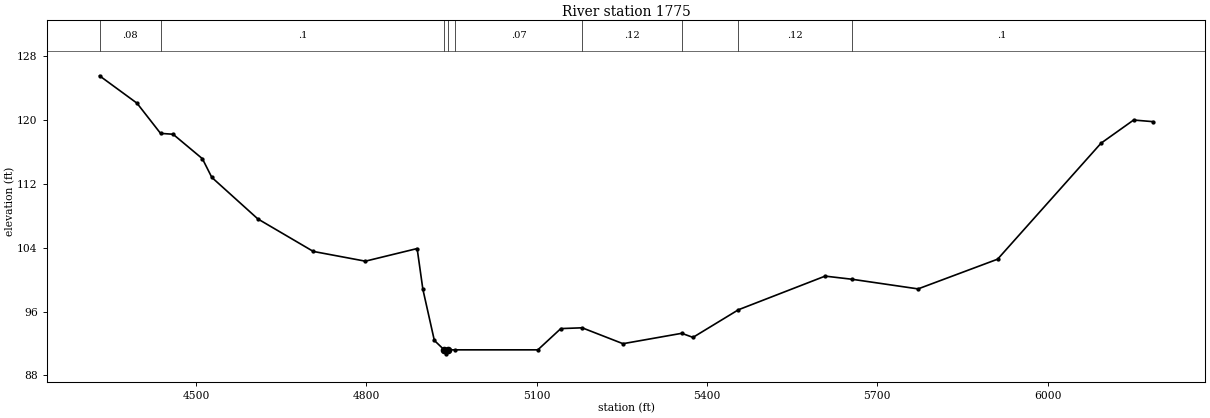
Type RM Length L Ch R = 1 ,1775    ,0,0,0
BEGIN DESCRIPTION:
LA PARA CREEK 1.0
END DESCRIPTION:
XS GIS Cut Line= 3
      2296237.75     13285396.87       2295855.9       13285223.
      2294437.73     13285446.85
#Sta/Elev= 30
  4329.9  125.52  4395.9  122.09  4437.4  118.31  4459.5   118.2  4511.1  115.14
  4527.7   112.8  4608.8   107.6  4706.5  103.53  4798.2  102.31  4889.4  103.89
  4899.5   98.79  4919.7   92.39    4937   91.21  4939.7   90.71    4943   91.21
  4956.1   91.21    5102   91.21  5142.5   93.87  5180.1   93.97    5252   91.98
  5355.5   93.28  5375.3   92.77  5455.4   96.23  5608.1  100.44  5655.1  100.05
  5771.8   98.84  5911.9  102.56  6094.1  117.08  6151.5  119.98  6185.2  119.78
#Mann= 9 ,-1 , 0
  4329.9     .08       0  4437.4      .1       0    4937     .07       0
    4943      .1       0  4956.1     .07       0  5180.1     .12       0
  5355.5      .1       0  5455.4     .12       0  5655.1      .1       0
Bank Sta=4937,4943
XS Rating Curve= 0 ,0
Exp/Cntr=0.3,0.1

Chan Stop Cuts=-1
Use User Specified Reach Order=0
Composite Channel Slope=5