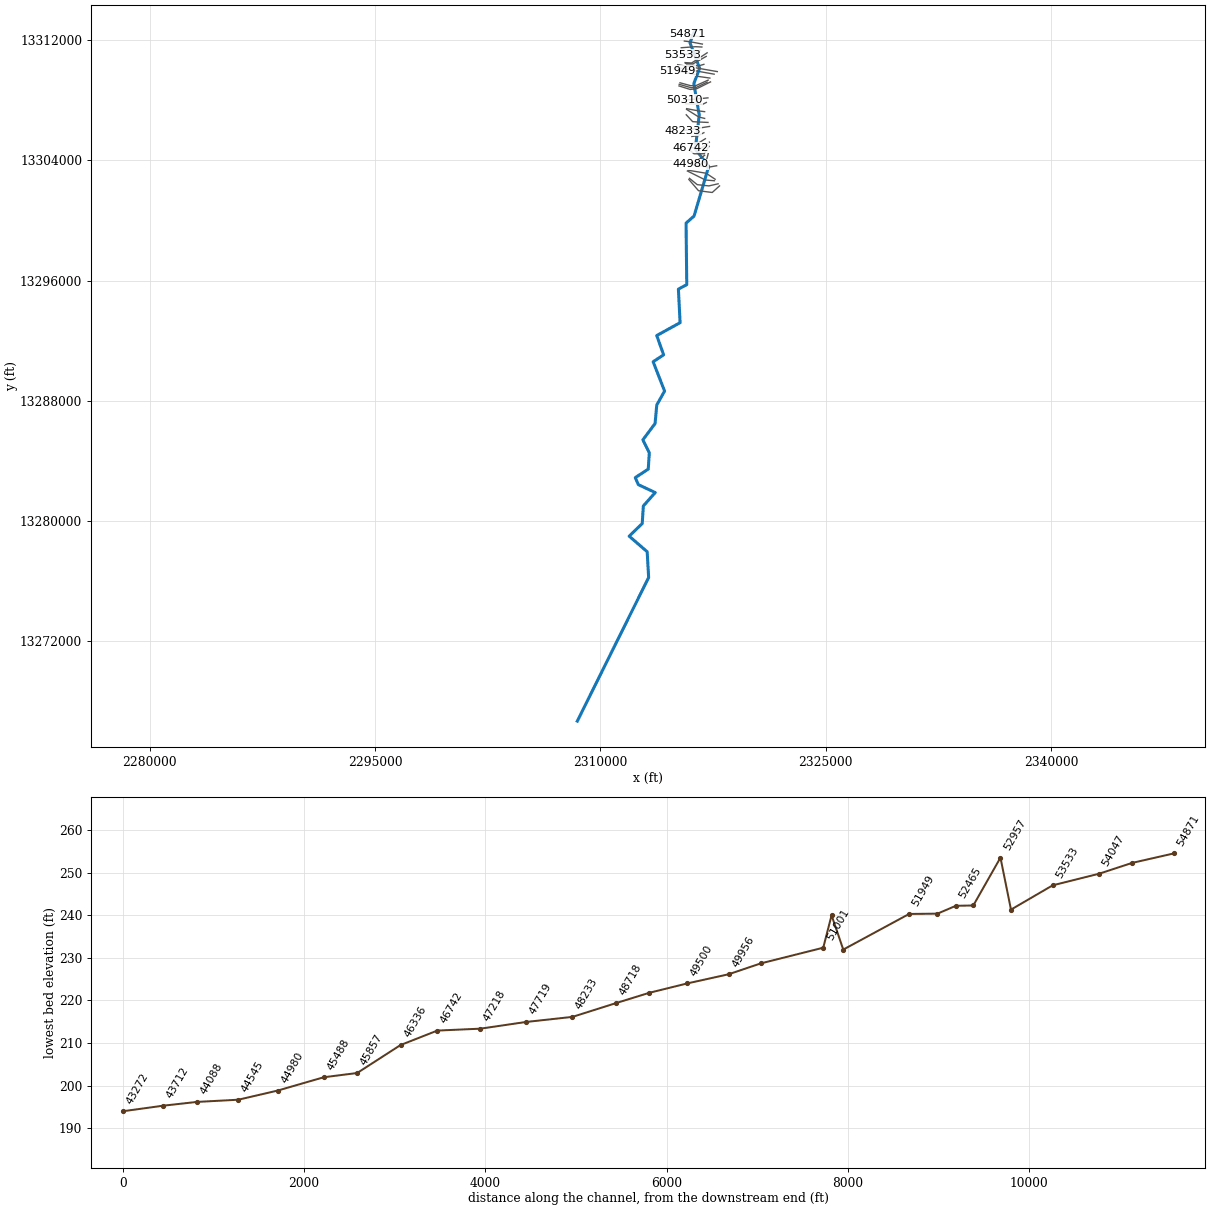
--- MUSTANG CREEK.prj (project) ---

Proj Title=MUSTANG CREEK Base Level Engineering
Current Plan=p01
Default Exp/Contr=0.3,0.1
English Units
Geom File=g01
Flow File=f01
Plan File=p01
Y Axis Title=Elevation
X Axis Title(PF)=Main Channel Distance
X Axis Title(XS)=Station
BEGIN DESCRIPTION:
MUSTANG CREEK
END DESCRIPTION:
DSS Export Rating Curves= 0
DSS Export Rating Curve Sorted= 0
DSS Export Volume Flow Curves= 0
DXF OffsetX= 0
DXF OffsetY= 0
DXF ScaleX= 1
DXF ScaleY= 10

--- MUSTANG CREEK.p01 (plan) ---

Plan Title=Multiple Run
Short Identifier=Multiple
Geom File=g01
Flow File=f01
Subcritical Flow
K Sum by GR= 0
Std Step Tol= 0.01
Critical Tol= 0.01
Num of Std Step Trials= 20
Max Error Tol= 0.3
Flow Tol Ratio= 0.001
Split Flow NTrial= 30
Split Flow Tol= 0.02
Split Flow Ratio= 0.02
Log Output Level= 0
Friction Slope Method= 1
Unsteady Friction Slope Method= 2
Unsteady Bridges Friction Slope Method= 1
Parabolic Critical Depth
Global Vel Dist=  1 , 1 , 1
Global Log Level= 0
CheckData=True
Encroach Param= -1, 0, 0, 0
BEGIN DESCRIPTION:
Multiple Run
END DESCRIPTION:

--- MUSTANG CREEK.f01 (steady flow) ---

Flow Title=Multiple
Program Version=4.10
Number of Profiles= 7
Profile Names=10-year,25-year,50-year,1pct_min,100-year,1pct_plu,500-year
River Rch & RM=MUSTANG CREEK,Reach-1         ,54871
     676     962    1203    1099    1486    2010    2277
River Rch & RM=MUSTANG CREEK,Reach-1         ,54047
     935    1352    1710    1577    2132    2883    3330
River Rch & RM=MUSTANG CREEK,Reach-1         ,50310
    1279    1876    2393    2224    3008    4068    4776
River Rch & RM=MUSTANG CREEK,Reach-1         ,44980
    1955    2919    3770    3542    4790    6478    7773
River Rch & RM=MUSTANG CREEK,Reach-1         ,40994
    2056    3074    3974    3736    5053    6833    8210
River Rch & RM=MUSTANG CREEK,Reach-1         ,40407
    2056    3074    3974    3736    5053    6833    8210
River Rch & RM=MUSTANG CREEK,Reach-1         ,39018
    2371    3567    4630    4369    5909    7991    9672
River Rch & RM=MUSTANG CREEK,Reach-1         ,36899
    2813    4244    5518    5213    7050    9535   11566
River Rch & RM=MUSTANG CREEK,Reach-1         ,36413
    2813    4244    5518    5213    7050    9535   11566
River Rch & RM=MUSTANG CREEK,Reach-1         ,24990
    3053    4619    6017    5694    7700   10413   12673
River Rch & RM=MUSTANG CREEK,Reach-1         ,22174
    3916    5971    7822    7438   10059   13604   16718
River Rch & RM=MUSTANG CREEK,Reach-1         ,21585
    3916    5971    7822    7438   10059   13604   16718
River Rch & RM=MUSTANG CREEK,Reach-1         ,18131
    4074    6215    8143    7744   10473   14164   17407
River Rch & RM=MUSTANG CREEK,Reach-1         ,17424
    4074    6215    8143    7744   10473   14164   17407
River Rch & RM=MUSTANG CREEK,Reach-1         ,16456
    4181    6362    8322    7898   10681   14445   17681
Boundary for River Rch & Prof#=MUSTANG CREEK,Reach-1         , 1
Up Type= 0
Dn Type= 3
Dn Slope=0.0035
Boundary for River Rch & Prof#=MUSTANG CREEK,Reach-1         , 2
Up Type= 0
Dn Type= 3
Dn Slope=0.0035
Boundary for River Rch & Prof#=MUSTANG CREEK,Reach-1         , 3
Up Type= 0
Dn Type= 3
Dn Slope=0.0035
Boundary for River Rch & Prof#=MUSTANG CREEK,Reach-1         , 4
Up Type= 0
Dn Type= 3
Dn Slope=0.0035
Boundary for River Rch & Prof#=MUSTANG CREEK,Reach-1         , 5
Up Type= 0
Dn Type= 3
Dn Slope=0.0035
Boundary for River Rch & Prof#=MUSTANG CREEK,Reach-1         , 6
Up Type= 0
Dn Type= 3
Dn Slope=0.0035
Boundary for River Rch & Prof#=MUSTANG CREEK,Reach-1         , 7
Up Type= 0
Dn Type= 3
Dn Slope=0.0035
DSS Import GetInterval= 0
DSS Import GetPeak= 0
DSS Import FillOption= 0

--- MUSTANG CREEK.g01 (geometry) ---

Geom Title=Existing Conditions
Program Version=4.10

River Reach=MUSTANG CREEK   ,Reach-1
Reach XY= 30
      2316281.82      13312646.2      2315960.61     13311838.75
      2316605.02     13310136.67      2316216.57     13309112.36
      2316576.84     13307026.85      2316318.37     13304761.47
      2317207.72     13303596.85      2316234.34     13300298.22
      2315700.36     13299825.72      2315747.46     13295731.38
      2315189.49     13295431.12      2315304.57     13293198.22
      2313749.72     13292341.41      2314206.56     13291057.34
      2313508.92     13290597.29       2314271.3     13288644.27
      2313750.65     13287720.42      2313638.02     13286483.38
      2312825.52     13285397.45      2313255.21     13284538.07
      2313183.95     13283448.38      2312319.61     13282882.79
      2312524.97     13282411.72      2313647.62     13281889.61
      2312855.84     13280993.19      2312781.94     13279824.45
      2311913.49     13278983.01      2313112.15     13277949.34
      2313209.84     13276233.46      2308459.87     13266669.01

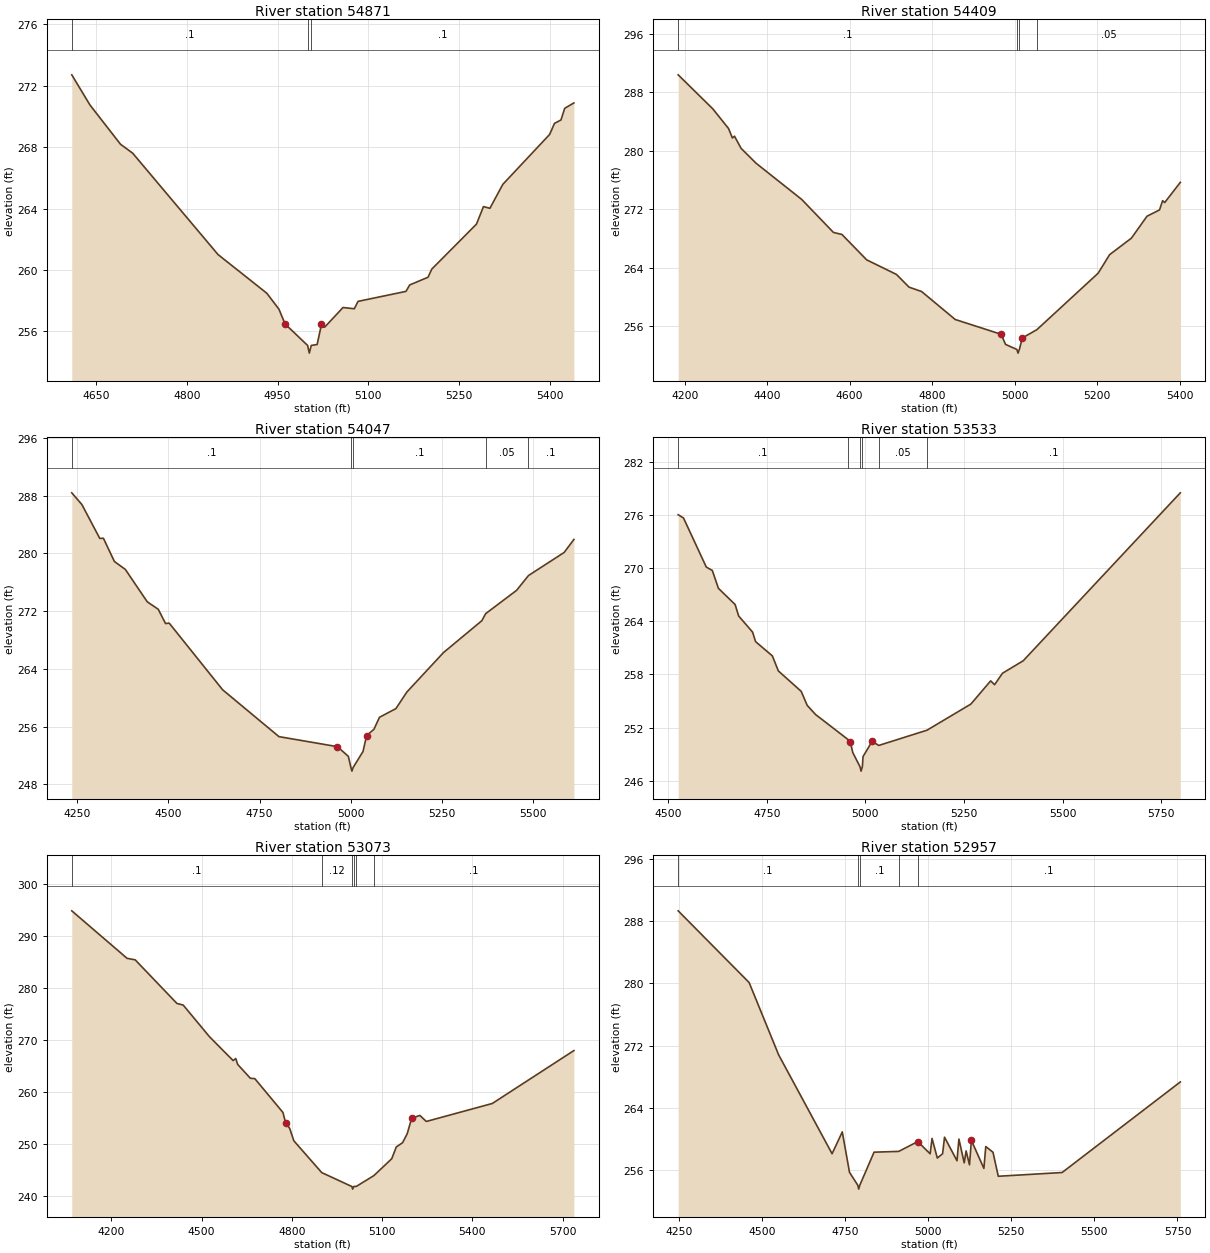
Type RM Length L Ch R = 1 ,54871   ,462,462,462
BEGIN DESCRIPTION:
MUSTANG CREEK 86.0
END DESCRIPTION:
XS GIS Cut Line= 3
      2316587.69     13312246.86      2316187.72     13312296.85
       2315787.7     13312446.86
#Sta/Elev= 30
  4609.8  272.71    4640  270.74  4690.4  268.19  4710.5  267.61  4851.6  261.01
  4932.3  258.49  4952.4  257.45  4962.5  256.49  4999.8  255.09  5002.6  254.59
  5005.8  255.09  5015.5  255.15  5022.7  256.46    5028  256.28  5058.3  257.56
    5077  257.48  5083.2  257.96  5162.4  258.61  5168.6  259.03  5198.9  259.53
  5205.1  260.06    5279  262.99  5290.6  264.13  5301.2  264.02  5322.6  265.58
    5400  268.83    5408  269.55  5418.7  269.77  5424.9  270.53  5440.1  270.88
#Mann= 3 ,-1 , 0
  4609.8      .1       0  4999.8     .07       0  5005.8      .1       0
Bank Sta=4962.5,5022.7
XS Rating Curve= 0 ,0
Exp/Cntr=0.3,0.1

Type RM Length L Ch R = 1 ,54409   ,362,362,362
BEGIN DESCRIPTION:
MUSTANG CREEK 85.0
END DESCRIPTION:
XS GIS Cut Line= 3
      2316787.72     13311746.86      2315987.72     13311896.85
      2315587.67     13311946.86
#Sta/Elev= 30
  4184.3   290.4  4268.2  285.75  4306.4  283.06  4315.7  281.77  4320.8  282.01
  4336.9  280.34  4373.4   278.3  4483.6  273.37  4560.7  268.85  4581.1  268.58
  4641.3   265.1  4713.4  263.11  4743.9  261.37  4774.4  260.77  4855.8  256.95
  4966.9  254.93  4977.9  253.54  5005.3  252.85  5008.1  252.35  5011.3  252.85
  5018.4  254.42  5053.8  255.56  5202.3  263.28    5230  265.81  5282.9  268.07
  5320.7  271.07    5351  271.93  5358.5  273.19  5363.6  272.94  5401.4   275.7
#Mann= 4 ,-1 , 0
  4184.3      .1       0  5005.3     .07       0  5011.3      .1       0
  5053.8     .05       0
Bank Sta=4966.9,5018.4
XS Rating Curve= 0 ,0
Exp/Cntr=0.3,0.1

Type RM Length L Ch R = 1 ,54047   ,514,514,514
BEGIN DESCRIPTION:
MUSTANG CREEK 84.0
END DESCRIPTION:
XS GIS Cut Line= 3
      2316754.35      13311550.6      2316340.08     13311572.44
      2315381.08     13311503.84
#Sta/Elev= 30
  4235.1  288.38  4262.8  286.76  4311.8  282.07  4321.9  282.08  4351.9  278.87
  4381.9  277.77    4442  273.28  4472.1  272.25  4492.1  270.27  4502.1  270.33
  4648.6  261.09    4803   254.6  4963.1  253.21  4993.2  251.87  5000.2  250.32
    5003  249.82  5006.2  250.32  5033.3  252.53  5043.3  254.75  5063.4  255.62
  5078.5  257.28  5123.5  258.48  5153.6  260.78  5253.8  266.24    5359  270.66
  5369.6  271.64  5454.4  274.87  5486.9  276.92  5584.7  280.12  5611.4  281.92
#Mann= 5 ,-1 , 0
  4235.1      .1       0  5000.2     .07       0  5006.2      .1       0
  5369.6     .05       0  5486.9      .1       0
Bank Sta=4963.1,5043.3
XS Rating Curve= 0 ,0
Exp/Cntr=0.3,0.1

Type RM Length L Ch R = 1 ,53533   ,460,460,460
BEGIN DESCRIPTION:
MUSTANG CREEK 83.0
END DESCRIPTION:
XS GIS Cut Line= 3
      2316637.69     13311346.83      2316237.72     13311096.85
      2315437.74     13311046.86
#Sta/Elev= 30
  4525.3  276.03  4538.8  275.66  4596.6  270.12  4611.9  269.73  4627.3  267.72
  4669.7  265.89  4678.6   264.6  4713.9  262.78  4721.6   261.7  4764.1  260.09
  4779.4  258.39  4837.2  256.09  4852.5   254.5  4873.7  253.47  4956.2  250.64
  4961.6  250.42  4968.1  249.17  4986.3  247.58    4989  247.08  4992.3  247.58
    4994  248.72    5017  250.44  5033.9  249.98  5156.2   251.7  5267.5  254.65
  5317.6  257.27  5327.6  256.84  5347.6  258.13  5400.2  259.54  5798.5   278.5
#Mann= 6 ,-1 , 0
  4525.3      .1       0  4956.2     .07       0  4986.3     .07       0
  4992.3     .07       0  5033.9     .05       0  5156.2      .1       0
Bank Sta=4961.6,5017
XS Rating Curve= 0 ,0
Exp/Cntr=0.3,0.1

Type RM Length L Ch R = 1 ,53073   ,116,116,116
BEGIN DESCRIPTION:
Mapping XS d44eefb6
END DESCRIPTION:
XS GIS Cut Line= 3
      2317103.85      13311164.4      2316070.89     13310487.33
      2315636.86     13310513.37
#Sta/Elev= 30
    4068  294.92  4251.9  285.78  4278.9  285.49  4417.7   277.1  4438.7  276.78
  4526.2  270.68  4604.5  266.11  4613.4   266.5  4619.6  265.38  4661.8  262.71
  4676.9  262.62  4770.3  256.12  4779.4  254.08  4792.7  253.06  4806.5  250.67
  4899.3  244.55  4999.5  241.87  5002.2  241.37  5005.5  241.87  5014.5   241.9
  5072.7  243.97  5132.1  247.22  5147.2  249.48  5168.3  250.32  5183.4  252.01
  5198.5  255.01  5225.5  255.55  5247.1  254.39  5466.5  257.85  5737.9  268.03
#Mann= 6 ,-1 , 0
    4068      .1       0  4899.3     .12       0  4999.5     .07       0
  5005.5     .12       0  5014.5     .07       0  5072.7      .1       0
Bank Sta=4779.4,5198.5
XS Rating Curve= 0 ,0
Exp/Cntr=0.3,0.1

Type RM Length L Ch R = 1 ,52957   ,300,300,300
BEGIN DESCRIPTION:
MUSTANG CREEK 82.0
END DESCRIPTION:
XS GIS Cut Line= 3
      2317040.87     13310925.61      2316155.44      13310425.6
      2315663.03     13310461.88
#Sta/Elev= 30
    4248   289.3  4461.5   280.1  4550.2  270.83    4711  258.14  4741.7  260.94
  4763.4  255.76  4788.4   254.1  4791.1   253.6  4794.4   254.1  4837.3  258.34
  4911.5  258.44  4968.4  259.69  4969.5  259.67    5006  258.13  5011.7   260.1
  5027.6  257.59  5043.5  258.14  5049.3  260.26  5086.8  257.24  5092.6  260.02
  5108.5  256.97  5114.2  258.51  5124.4  256.72  5130.1  259.85  5167.7  256.26
  5173.4  259.06  5195.1  258.33    5211  255.25    5403  255.73  5758.6  267.35
#Mann= 5 ,-1 , 0
    4248      .1       0  4788.4     .07       0  4794.4      .1       0
  4911.5     .12       0  4969.5      .1       0
Bank Sta=4968.4,5130.1
XS Rating Curve= 0 ,0
Exp/Cntr=0.3,0.1

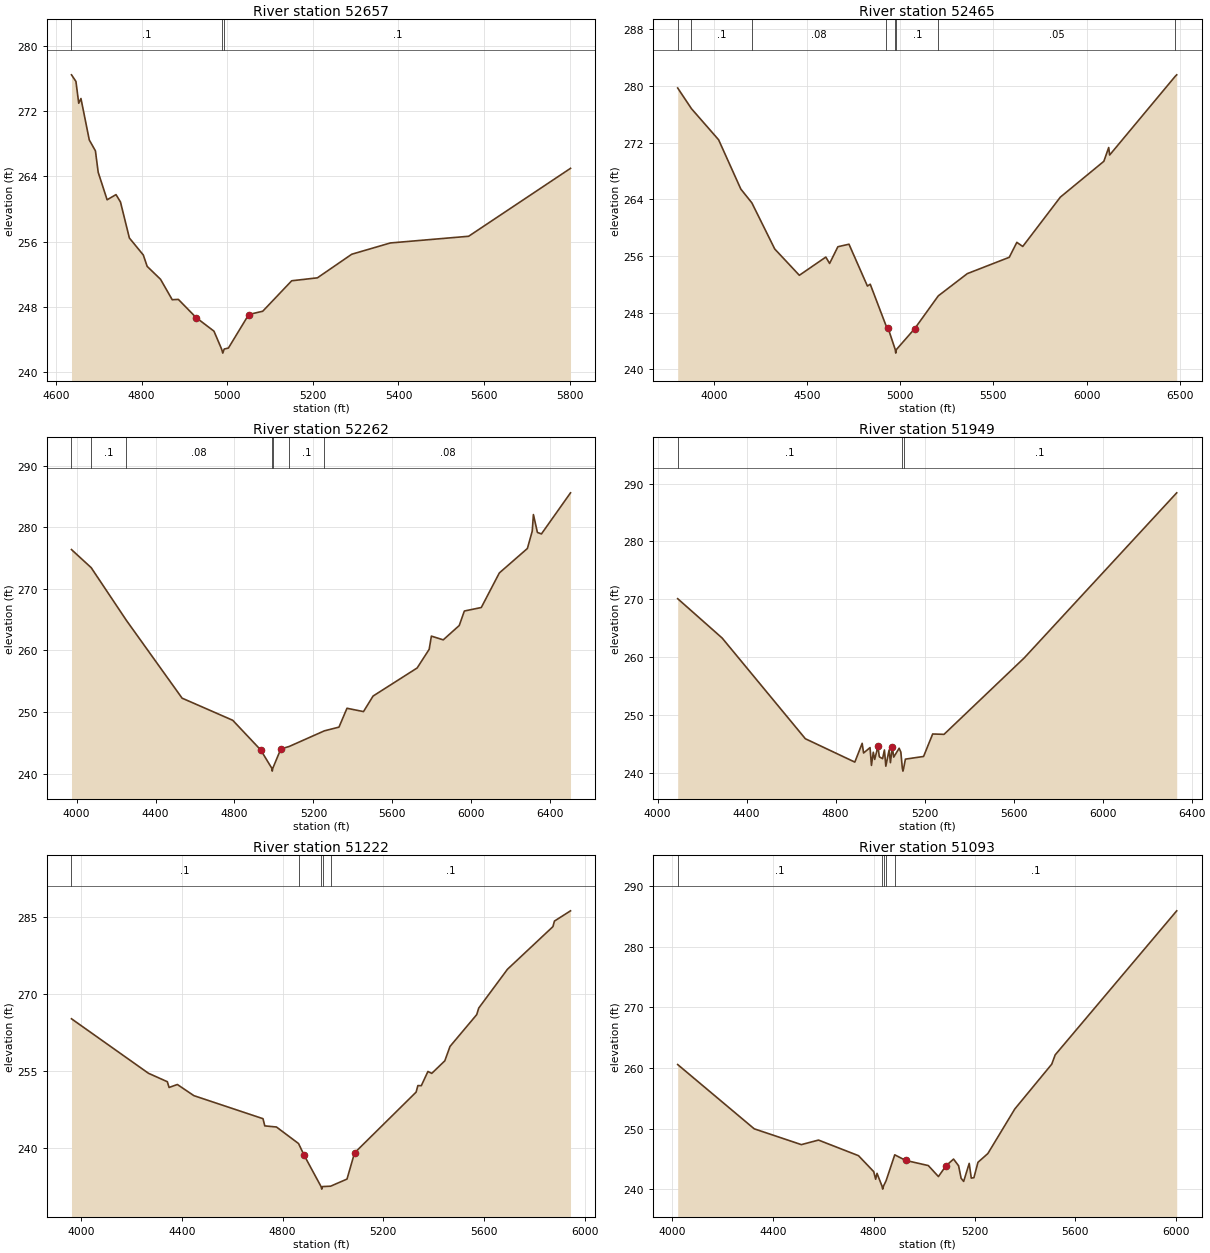
Type RM Length L Ch R = 1 ,52657   ,192,192,192
BEGIN DESCRIPTION:
MUSTANG CREEK 81.0
END DESCRIPTION:
XS GIS Cut Line= 3
      2316887.72     13310396.86      2316537.72     13310296.85
      2315737.69     13310346.86
#Sta/Elev= 30
  4636.3  276.42  4646.7  275.61  4653.2  272.94  4658.4  273.52  4677.9  268.44
  4692.2  267.11  4698.7  264.48  4719.5  261.12  4740.3  261.75  4750.7  260.85
  4771.5  256.44    4804  254.36  4813.1  252.96  4844.3  251.38  4871.6  248.88
  4885.9  248.92  4927.5  246.69  4969.1  245.03  4986.9  242.84  4989.7  242.34
  4992.9  242.84  5002.8  242.96  5050.4  247.07    5083  247.47  5150.6   251.2
  5210.7  251.56  5290.9  254.45    5381  255.83  5563.9  256.65  5801.9  264.97
#Mann= 3 ,-1 , 0
  4636.3      .1       0  4986.9     .07       0  4992.9      .1       0
Bank Sta=4927.5,5050.4
XS Rating Curve= 0 ,0
Exp/Cntr=0.3,0.1

Type RM Length L Ch R = 1 ,52465   ,203,203,203
BEGIN DESCRIPTION:
Mapping XS b1c863fc
END DESCRIPTION:
XS GIS Cut Line= 2
        2317781.      13309914.4       2315142.4     13310374.42
#Sta/Elev= 30
  3805.7  279.73  3879.6  276.81  4025.5  272.41  4144.6  265.45  4203.9   263.5
  4326.7  256.98  4458.7  253.27  4600.8  255.84  4621.1  254.94  4665.5   257.3
  4725.1  257.66  4824.1  251.74  4839.1  252.01  4922.1  246.28  4935.8  245.75
  4973.4  242.77  4976.1  242.27  4979.4  242.77  5077.9  245.73  5204.4  250.36
    5360   253.5  5585.4  255.81    5626  257.92  5657.8  257.34  5859.5  264.31
    6093  269.37  6119.1  271.32  6124.2  270.26  6475.8  281.37  6484.1  281.59
#Mann= 8 ,-1 , 0
  3805.7     .05       0  3879.6      .1       0  4203.9     .08       0
  4922.1      .1       0  4973.4     .07       0  4979.4      .1       0
  5204.4     .05       0  6475.8     .08       0
Bank Sta=4935.8,5077.9
XS Rating Curve= 0 ,0
Exp/Cntr=0.3,0.1

Type RM Length L Ch R = 1 ,52262   ,313,313,313
BEGIN DESCRIPTION:
MUSTANG CREEK 80.0
END DESCRIPTION:
XS GIS Cut Line= 2
      2317572.08     13309743.31      2315082.64     13310185.99
#Sta/Elev= 30
  3974.2  276.37  4073.9  273.44  4251.8  264.91  4534.6  252.26  4791.2  248.67
  4932.6  243.87  4988.6  240.92  4991.4  240.42  4994.6  240.92  5034.9  244.02
  5077.2  244.42  5255.7  246.96  5329.5  247.56  5370.1  250.62  5453.7  250.08
  5502.2   252.6  5725.6  257.16  5786.6  260.19  5797.7  262.33  5857.7  261.72
  5938.9  264.05  5964.7   266.4  6050.6  266.97    6142  272.58  6284.2  276.55
  6308.7  279.36  6314.7  282.05    6335  279.15  6355.3  278.91  6502.7  285.58
#Mann= 7 ,-1 , 0
  3974.2     .08       0  4073.9      .1       0  4251.8     .08       0
  4988.6     .07       0  4994.6     .08       0  5077.2      .1       0
  5255.7     .08       0
Bank Sta=4932.6,5034.9
XS Rating Curve= 0 ,0
Exp/Cntr=0.3,0.1

Type RM Length L Ch R = 1 ,51949   ,727,727,727
BEGIN DESCRIPTION:
MUSTANG CREEK 79.0
END DESCRIPTION:
XS GIS Cut Line= 4
      2317285.69     13309482.88      2316483.56     13309597.47
      2316337.73     13309706.85      2315114.21     13309961.97
#Sta/Elev= 30
  4090.6  270.12  4290.5  263.32  4664.3  245.94  4886.6  241.91  4919.6  245.15
  4925.9  243.48    4955  244.41  4961.3  241.34  4969.6  243.61  4975.9  242.37
  4990.5  244.61  4996.7  242.82  5011.3   242.5  5019.6     244  5025.9   241.2
  5040.5  243.99  5046.7  241.81    5055  244.55  5061.3  242.77  5085.7   244.3
  5093.4  243.63  5100.1  240.85  5102.8  240.35  5106.1  240.85  5113.8  242.42
  5195.5  242.88  5236.4  246.76  5287.5   246.7  5648.3  259.91    6333  288.39
#Mann= 3 ,-1 , 0
  4090.6      .1       0  5100.1     .07       0  5106.1      .1       0
Bank Sta=4990.5,5055
XS Rating Curve= 0 ,0
Exp/Cntr=0.3,0.1

Type RM Length L Ch R = 1 ,51222   ,129,129,129
BEGIN DESCRIPTION:
MUSTANG CREEK 78.0
END DESCRIPTION:
XS GIS Cut Line= 4
      2317171.03     13309347.46      2316337.73     13308972.47
      2316004.39     13308977.68       2315296.1     13309170.38
#Sta/Elev= 30
  3961.8   265.2  4267.4  254.57  4342.4  252.92  4349.2   251.8  4382.1  252.38
  4447.9   250.2  4722.1  245.71  4729.2  244.31  4775.5  244.09  4863.3  240.86
  4885.6  238.56  4952.6  232.47  4955.4  231.97  4958.6  232.47  4990.4  232.54
  5055.6  233.93  5085.6  239.04  5329.9  250.89  5337.1  252.17  5350.6  252.15
  5376.9  254.92  5392.1  254.55  5443.9     257  5464.6  259.81  5570.6  266.01
  5578.6  267.29  5692.6  274.86  5873.2  283.18  5879.1  284.26    5943  286.26
#Mann= 5 ,-1 , 0
  3961.8      .1       0  4863.3     .12       0  4952.6     .07       0
  4958.6     .12       0  4990.4      .1       0
Bank Sta=4885.6,5085.6
XS Rating Curve= 0 ,0
Exp/Cntr=0.3,0.1

Type RM Length L Ch R = 1 ,51093   ,92,92,92
BEGIN DESCRIPTION:
MUSTANG CREEK 77.0
END DESCRIPTION:
XS GIS Cut Line= 4
      2317108.61     13309212.08      2316348.14     13308847.47
      2316035.64     13308842.27        2315244.     13309066.22
#Sta/Elev= 30
    4023  260.56  4326.6  249.97  4513.4  247.37  4581.3  248.12  4739.9  245.55
  4800.3  242.92  4807.9  241.67  4813.4  242.64  4833.1  240.54  4835.8  240.04
  4839.1  240.54  4849.4  241.43  4883.6  245.69  4926.8  244.77  5016.8  243.92
  5056.8  242.11  5086.8  243.88  5116.8  244.99  5136.8  243.89  5146.8  241.82
  5156.8  241.31  5178.9  244.28  5187.1  241.86  5197.5  241.92  5213.6  244.46
  5252.8   245.9  5359.8  253.25  5506.1  260.62  5519.7  262.15  6001.6  285.88
#Mann= 5 ,-1 , 0
    4023      .1       0  4833.1     .07       0  4839.1      .1       0
  4849.4     .12       0  4883.6      .1       0
Bank Sta=4926.8,5086.8
XS Rating Curve= 0 ,0
Exp/Cntr=0.3,0.1

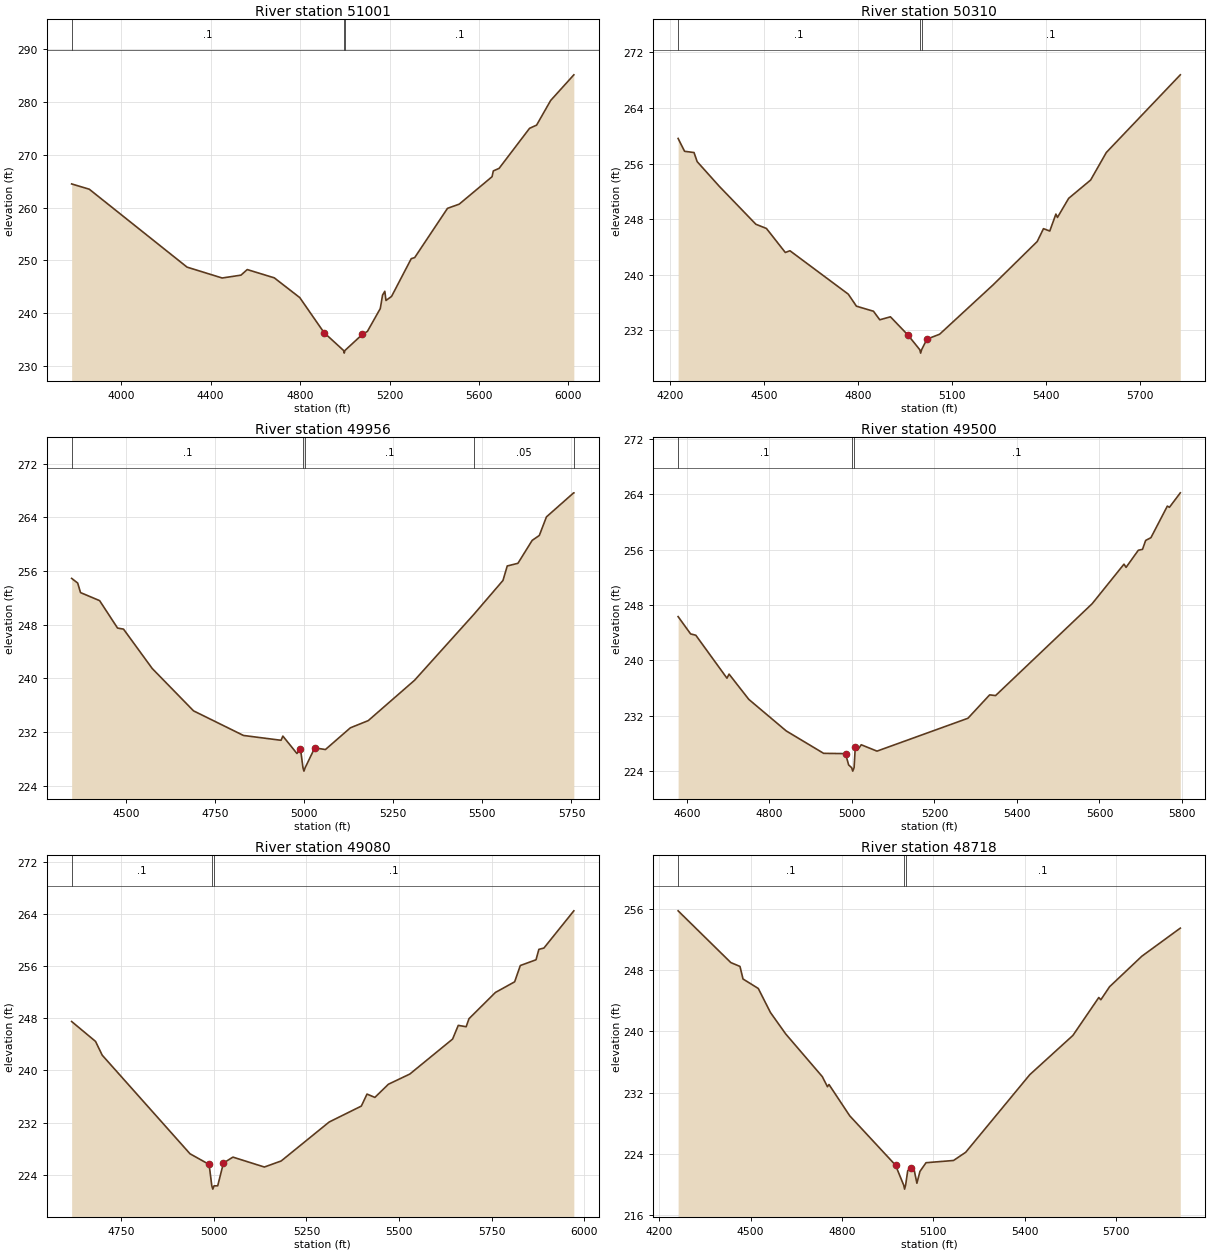
Type RM Length L Ch R = 1 ,51001   ,691,691,691
BEGIN DESCRIPTION:
Mapping XS bfe8703e
END DESCRIPTION:
XS GIS Cut Line= 4
       2317329.6     13309228.66      2316418.11     13308777.26
       2315975.4     13308725.17      2315228.83     13308959.56
#Sta/Elev= 30
  3778.7  264.48  3857.5  263.48  4294.7  248.71  4451.7  246.65  4535.8  247.19
  4563.8  248.25  4684.7  246.68  4798.6  242.94    4907  236.31  4994.6  232.91
  4997.4  232.41  5000.6  232.91  5078.2  235.95  5101.1  236.53  5158.7  240.86
  5168.8  243.41  5178.9  244.13  5184.2  242.39  5209.1  243.16  5297.1  250.31
  5312.5  250.52  5459.1  259.85  5511.7  260.65  5658.4  265.85  5664.1  266.95
  5689.9  267.43  5826.1  275.02  5857.6  275.63  5920.5   280.3  6024.1  285.16
#Mann= 3 ,-1 , 0
  3778.7      .1       0  4994.6     .07       0  5000.6      .1       0
Bank Sta=4907,5078.2
XS Rating Curve= 0 ,0
Exp/Cntr=0.3,0.1

Type RM Length L Ch R = 1 ,50310   ,354,354,354
BEGIN DESCRIPTION:
MUSTANG CREEK 76.0
END DESCRIPTION:
XS GIS Cut Line= 3
      2317158.23     13308165.29      2315912.74     13308047.96
      2315561.76     13308038.96
#Sta/Elev= 30
  4225.6  259.62  4246.2  257.77  4276.3  257.59  4286.4  256.28  4356.7  252.74
  4473.8  247.26  4507.4  246.66  4567.6   243.2  4582.4  243.45  4768.5   237.2
  4794.5  235.47  4848.9  234.74  4868.9  233.51    4903  233.94  4959.3  231.29
  4996.5  229.21  4999.3  228.71  5002.5  229.21  5019.6  230.73  5059.8  231.43
  5230.5  238.54  5371.2  244.78  5391.2  246.63  5411.3  246.29  5430.8  248.73
  5435.8  248.25  5471.6     251  5541.6  253.63  5591.7   257.6  5827.7  268.78
#Mann= 3 ,-1 , 0
  4225.6      .1       0  4996.5     .07       0  5002.5      .1       0
Bank Sta=4959.3,5019.6
XS Rating Curve= 0 ,0
Exp/Cntr=0.3,0.1

Type RM Length L Ch R = 1 ,49956   ,456,456,456
BEGIN DESCRIPTION:
MUSTANG CREEK 75.0
END DESCRIPTION:
XS GIS Cut Line= 3
      2317049.96     13307858.45      2316797.22     13307732.08
      2315670.87     13307768.12
#Sta/Elev= 30
  4347.2  254.91  4364.2  254.21  4372.1  252.79  4425.7  251.59    4476   247.5
  4492.8  247.34  4573.3  241.47  4689.3  235.15  4829.4  231.48  4934.9  230.76
    4940  231.39  4979.5  228.79  4989.5  229.48  4996.5  226.66  4999.2  226.16
  5002.5  226.66  5029.5  229.63  5059.5  229.38  5129.5  232.62  5179.6  233.69
  5309.6  239.71  5476.6  249.57  5557.8   254.6  5569.8  256.76  5599.8  257.16
  5639.8  260.58  5659.8  261.31  5679.8  264.08  5756.2  267.67  5756.7  267.67
#Mann= 5 ,-1 , 0
  4347.2      .1       0  4996.5     .07       0  5002.5      .1       0
  5476.6     .05       0  5756.2      .1       0
Bank Sta=4989.5,5029.5
XS Rating Curve= 0 ,0
Exp/Cntr=0.3,0.1

Type RM Length L Ch R = 1 ,49500   ,420,420,420
BEGIN DESCRIPTION:
MUSTANG CREEK 74.0
END DESCRIPTION:
XS GIS Cut Line= 3
      2316937.74     13307246.85      2316537.72     13307296.85
       2315737.7     13307446.86
#Sta/Elev= 30
  4578.8  246.34  4609.1  243.84  4621.7  243.65  4697.2  237.44  4702.3  238.03
  4750.1  234.38  4840.8  229.82  4931.5  226.58  4984.5  226.54  4992.1   224.9
  4999.3  224.51    5002  224.01  5005.3  224.51  5008.2   227.5  5013.3  227.02
  5022.6  227.82  5060.8   226.9  5281.2  231.65  5333.8  235.03  5348.2  234.93
  5582.2   248.2  5659.4  253.92  5664.5  253.46  5694.1  255.93  5704.3  256.06
  5711.9  257.35  5724.7  257.75  5764.5  262.31  5769.6  262.14  5795.9  264.23
#Mann= 3 ,-1 , 0
  4578.8      .1       0  4999.3     .07       0  5005.3      .1       0
Bank Sta=4984.5,5008.2
XS Rating Curve= 0 ,0
Exp/Cntr=0.3,0.1

Type RM Length L Ch R = 1 ,49080   ,362,362,362
BEGIN DESCRIPTION:
MUSTANG CREEK 73.0
END DESCRIPTION:
XS GIS Cut Line= 3
      2316937.77     13306796.84      2316537.72     13306896.85
      2315737.68     13307396.88
#Sta/Elev= 30
    4616  247.51  4680.5  244.46  4698.5  242.35  4935.6  227.22  4987.1  225.59
  4994.4   222.3  4997.2   221.8  5000.4   222.3  5010.3  222.31  5025.8   225.8
  5051.4  226.71  5136.3  225.19  5181.7  226.12  5311.4   232.1  5398.1  234.54
  5413.4  236.38  5434.6  235.87  5471.2  237.89  5528.9  239.45  5644.5  244.82
  5659.8  246.92  5681.1  246.71  5688.7  247.94  5760.1  251.97    5812   253.6
  5827.3   256.1  5869.7  256.98  5877.4  258.58    5891  258.78  5971.8  264.49
#Mann= 3 ,-1 , 0
    4616      .1       0  4994.4     .07       0  5000.4      .1       0
Bank Sta=4987.1,5025.8
XS Rating Curve= 0 ,0
Exp/Cntr=0.3,0.1

Type RM Length L Ch R = 1 ,48718   ,485,485,485
BEGIN DESCRIPTION:
MUSTANG CREEK 72.0
END DESCRIPTION:
XS GIS Cut Line= 4
      2317160.65     13306529.77      2316548.78     13306557.25
      2316139.81     13306581.85       2315712.7     13307040.21
#Sta/Elev= 30
  4262.2  255.75  4435.3  248.99  4465.3  248.49  4475.3  246.85  4525.4  245.61
  4565.4  242.47  4615.5  239.67  4735.6   234.1  4752.5  232.78  4757.5  233.07
  4825.7  228.98  4975.9  222.54    5003  219.91  5005.7  219.41    5009  219.91
    5016  221.81    5026  222.21    5036  222.14  5046.1  220.18  5056.1  221.72
  5076.1  222.86  5166.3  223.15  5206.3  224.22  5416.6  234.35  5558.3  239.48
  5643.3  244.43  5650.1  244.14  5678.5  245.83  5784.5  249.82  5910.9  253.49
#Mann= 3 ,-1 , 0
  4262.2      .1       0    5003     .07       0    5009      .1       0
Bank Sta=4975.9,5026
XS Rating Curve= 0 ,0
Exp/Cntr=0.3,0.1

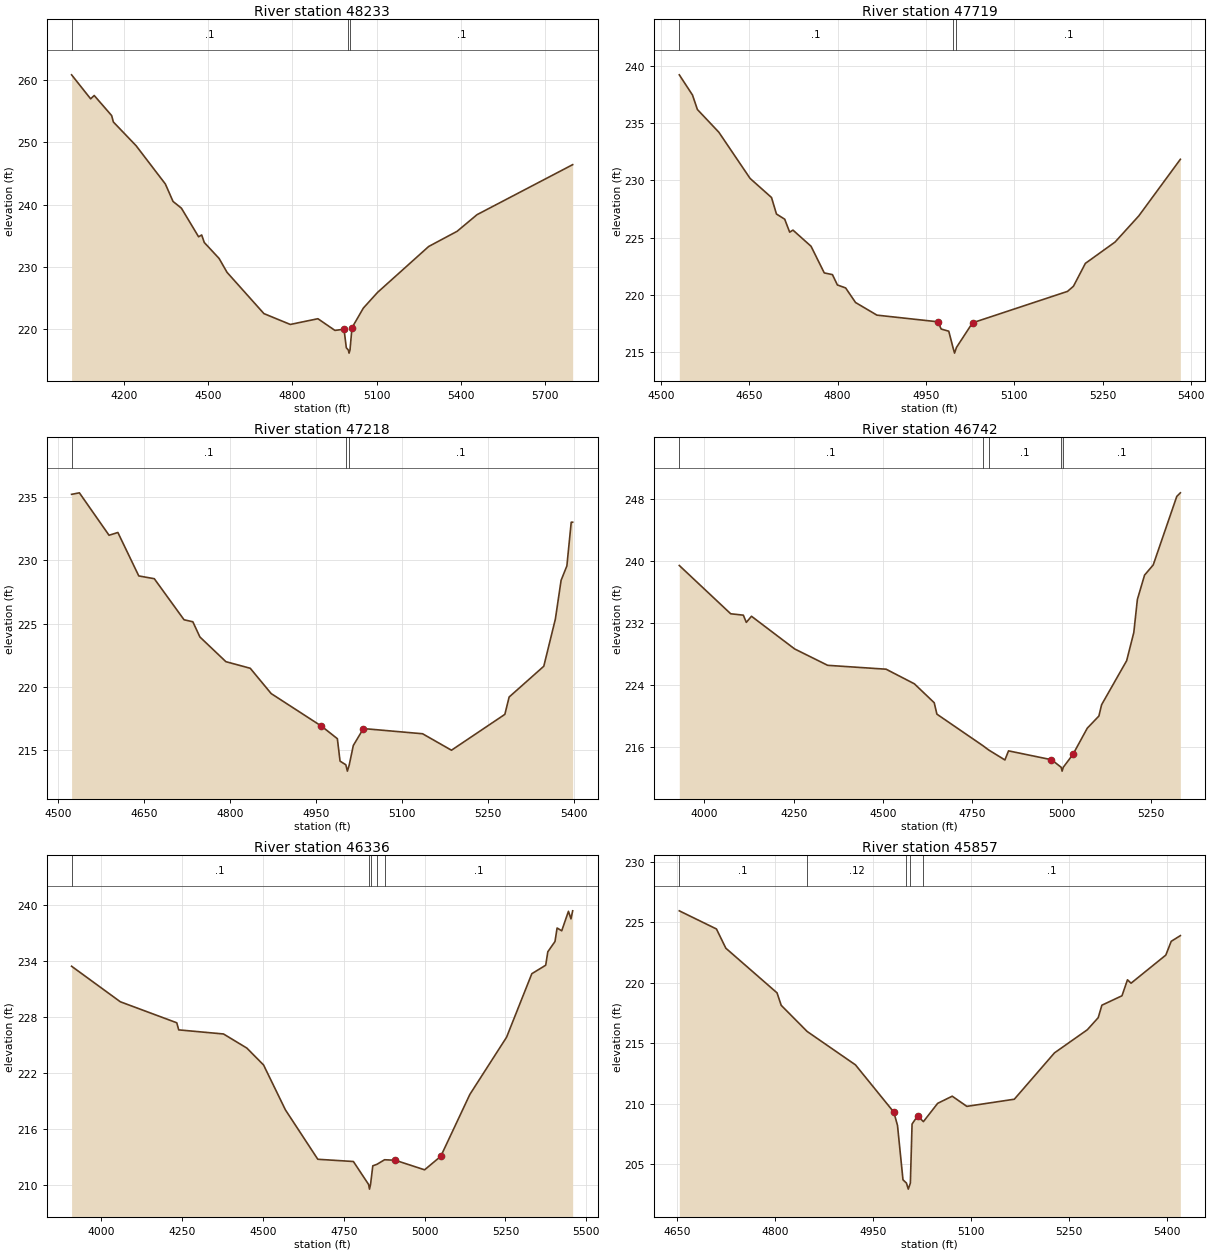
Type RM Length L Ch R = 1 ,48233   ,514,514,514
BEGIN DESCRIPTION:
MUSTANG CREEK 71.0
END DESCRIPTION:
XS GIS Cut Line= 2
      2317264.79     13306264.14      2315500.93     13305983.17
#Sta/Elev= 30
  4012.8  260.87  4080.7  257.01  4093.4  257.55  4155.6  254.32  4161.7  253.29
  4242.7  249.48  4347.1  243.32  4374.4  240.52  4404.2  239.44  4465.5  234.84
  4476.5  235.13  4485.8  233.92  4538.7  231.35  4566.8  229.13  4698.4  222.49
  4792.4  220.75  4890.8  221.67  4951.6  219.79  4983.9  219.98  4992.1     217
  4999.2  216.64  5001.9  216.14  5005.2  216.64  5012.3  220.22  5052.8  223.38
  5103.2  225.89  5285.7  233.28    5387  235.72  5457.9  238.39  5798.9  246.43
#Mann= 3 ,-1 , 0
  4012.8      .1       0  4999.2     .07       0  5005.2      .1       0
Bank Sta=4983.9,5012.3
XS Rating Curve= 0 ,0
Exp/Cntr=0.3,0.1

Type RM Length L Ch R = 1 ,47719   ,501,501,501
BEGIN DESCRIPTION:
MUSTANG CREEK 70.0
END DESCRIPTION:
XS GIS Cut Line= 3
      2316887.72     13305846.86      2316487.72     13305646.85
      2316087.75     13305596.86
#Sta/Elev= 30
  4531.4  239.19  4553.8  237.43  4562.1  236.17  4598.5  234.19  4651.6  230.16
  4687.9   228.5  4696.3  227.06  4710.3  226.61  4718.7  225.48  4724.3  225.66
    4755  224.25  4777.4  221.93  4791.3  221.78  4799.7  220.88  4813.7  220.62
  4830.5  219.35  4866.8  218.25  4970.2  217.67  4975.8  217.04  4988.7  216.85
  4995.8  215.44  4998.5  214.94  5001.8  215.44    5029  217.58  5190.2  220.32
  5200.3  220.77  5220.5  222.76  5270.9  224.62  5311.2   226.9  5381.7  231.83
#Mann= 3 ,-1 , 0
  4531.4      .1       0  4995.8     .07       0  5001.8      .1       0
Bank Sta=4970.2,5029
XS Rating Curve= 0 ,0
Exp/Cntr=0.3,0.1

Type RM Length L Ch R = 1 ,47218   ,476,476,476
BEGIN DESCRIPTION:
MUSTANG CREEK 69.0
END DESCRIPTION:
XS GIS Cut Line= 3
      2316987.71     13305446.85      2316587.72     13305196.85
      2316187.72     13305146.86
#Sta/Elev= 30
  4523.7  235.22  4537.3  235.34  4589.1  231.99  4604.5  232.21    4641  228.78
  4668.1  228.56    4720  225.32  4735.4  225.16  4747.7  223.96  4793.1  222.01
  4835.6  221.49  4872.2  219.49    4960  216.92  4987.7  215.93  4992.4  214.16
  5002.5  213.87  5005.2  213.37  5008.5  213.87  5015.5  215.39  5033.2  216.73
  5136.5  216.32  5186.9  215.02  5280.1  217.85  5287.6  219.22  5348.1  221.65
  5368.3  225.37  5378.3  228.43  5388.4  229.57    5396  233.02  5398.5  233.02
#Mann= 3 ,-1 , 0
  4523.7      .1       0  5002.5     .07       0  5008.5      .1       0
Bank Sta=4960,5033.2
XS Rating Curve= 0 ,0
Exp/Cntr=0.3,0.1

Type RM Length L Ch R = 1 ,46742   ,406,406,406
BEGIN DESCRIPTION:
MUSTANG CREEK 68.0
END DESCRIPTION:
XS GIS Cut Line= 3
       2317249.2     13305217.27       2316697.1      13304800.6
      2315987.69     13304846.86
#Sta/Elev= 30
  3929.5  239.41  4073.4  233.19  4108.8  233.01  4117.1  232.08  4131.6  232.87
  4252.4  228.66  4344.8  226.55  4508.4  226.05  4587.5  224.17  4643.1  221.73
  4650.6  220.26    4779  216.21  4795.7  215.64    4841  214.36  4851.1  215.53
  4971.3  214.39  4998.4  213.42  5001.1  212.92  5004.4  213.42  5031.4  215.07
  5071.5  218.45  5104.1  220.02  5111.6  221.47  5181.8  227.15  5201.8  230.78
  5211.8  235.04  5231.9  238.17  5256.1  239.48  5322.1  248.31  5332.1  248.77
#Mann= 5 ,-1 , 0
  3929.5      .1       0    4779     .12       0  4795.7      .1       0
  4998.4     .07       0  5004.4      .1       0
Bank Sta=4971.3,5031.4
XS Rating Curve= 0 ,0
Exp/Cntr=0.3,0.1

Type RM Length L Ch R = 1 ,46336   ,479,479,479
BEGIN DESCRIPTION:
MUSTANG CREEK 67.0
END DESCRIPTION:
XS GIS Cut Line= 4
      2317233.54      13304941.2      2316905.44     13304446.85
      2316233.56     13304441.22      2316015.78      13304622.7
#Sta/Elev= 30
  3908.9  233.41  4059.6   229.6    4234  227.35    4240  226.59  4378.4  226.15
  4450.5  224.64  4502.2  222.83  4569.9  218.01  4669.9  212.72  4779.9  212.48
  4826.9  210.02  4829.7  209.52  4832.9  210.02  4839.9  212.02  4852.7  212.18
  4876.3  212.67  4909.9  212.61    5000  211.59    5050  213.04    5140  219.68
  5253.3   225.8  5331.4  232.61  5374.3  233.52  5380.8  234.96    5403  236.06
  5409.5  237.51  5423.8  237.21  5444.6   239.3  5452.4  238.49  5457.6  239.35
#Mann= 5 ,-1 , 0
  3908.9      .1       0  4826.9     .07       0  4832.9      .1       0
  4852.7     .12       0  4876.3      .1       0
Bank Sta=4909.9,5050
XS Rating Curve= 0 ,0
Exp/Cntr=0.3,0.1

Type RM Length L Ch R = 1 ,45857   ,369,369,369
BEGIN DESCRIPTION:
MUSTANG CREEK 66.0
END DESCRIPTION:
XS GIS Cut Line= 3
      2316937.75     13304346.88      2316687.72     13304146.85
      2316287.73     13303946.86
#Sta/Elev= 30
  4653.3  225.94  4710.2  224.44  4724.6  222.85    4803  219.16  4809.4  218.13
  4849.1  215.97  4923.1  213.21  4981.9   209.3  4987.5   208.2  4995.9  203.71
  5001.2  203.44    5004  202.94  5007.2  203.44  5009.8  208.32  5018.2  208.98
  5027.2  208.52    5049  210.03  5071.3  210.62  5093.7  209.78  5166.4  210.37
  5227.9   214.2  5278.2  216.11  5294.9  217.11  5300.5  218.14  5331.3  218.92
  5339.7  220.24  5345.2  219.96  5398.4  222.28  5406.7  223.42  5420.7  223.89
#Mann= 5 ,-1 , 0
  4653.3      .1       0  4849.1     .12       0  5001.2     .07       0
  5007.2     .12       0  5027.2      .1       0
Bank Sta=4981.9,5018.2
XS Rating Curve= 0 ,0
Exp/Cntr=0.3,0.1

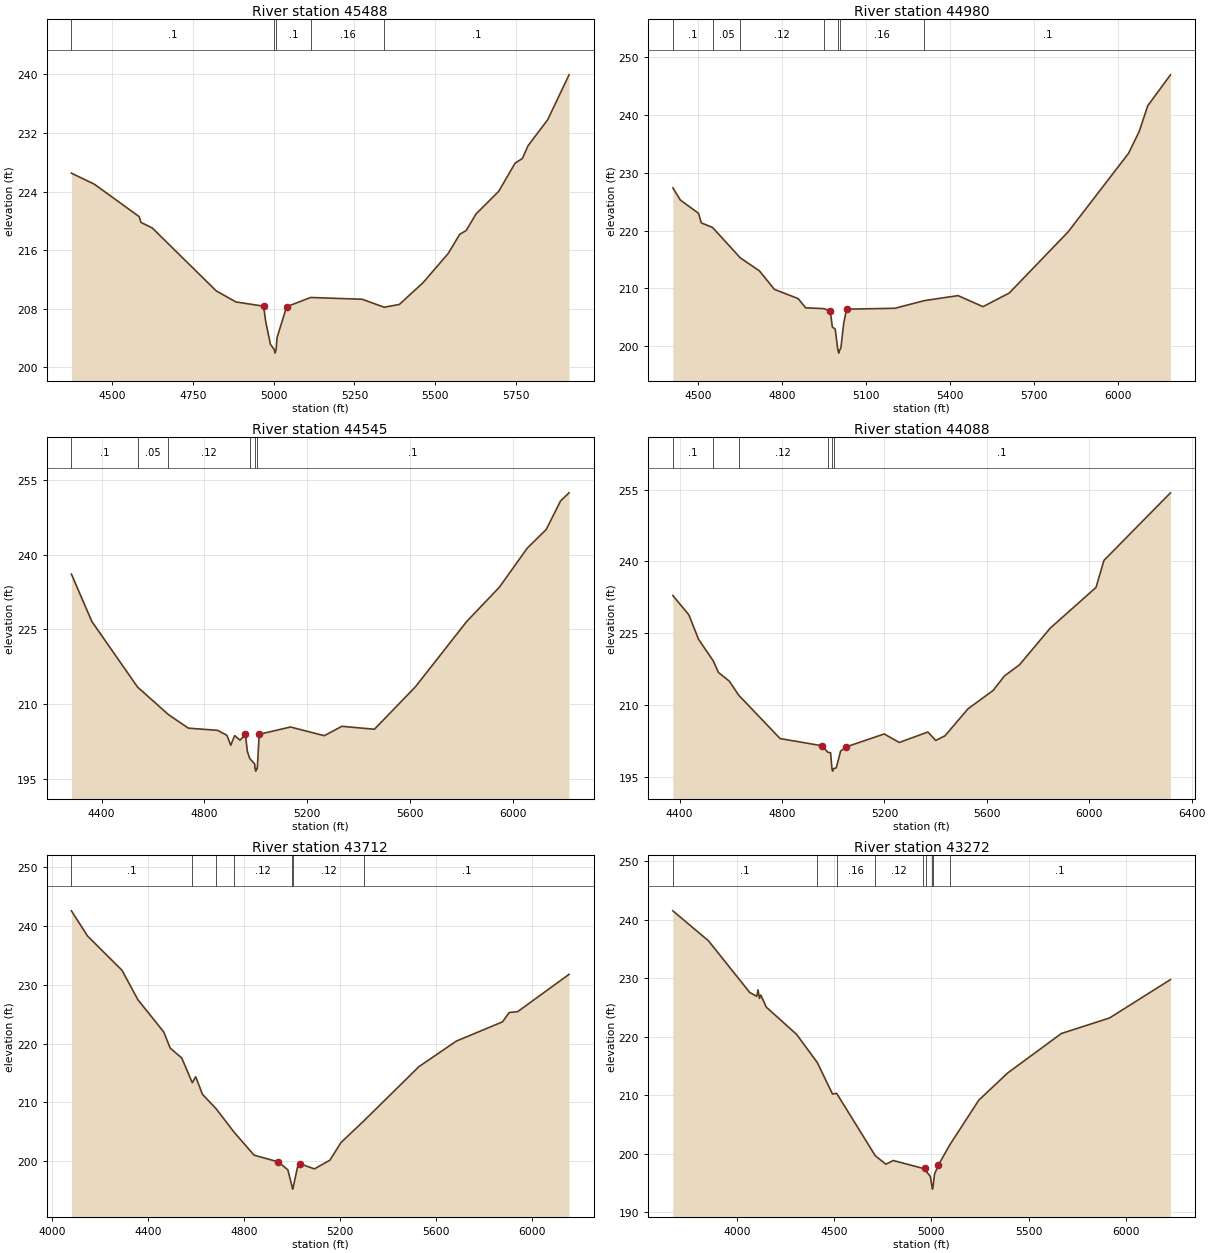
Type RM Length L Ch R = 1 ,45488   ,508,508,508
BEGIN DESCRIPTION:
MUSTANG CREEK 65.0
END DESCRIPTION:
XS GIS Cut Line= 4
      2317175.24     13304455.41      2317055.46      13303991.9
      2316737.75     13303762.73      2316071.87     13303851.17
#Sta/Elev= 30
  4372.8  226.52  4443.6  225.02  4582.9  220.58  4588.2   219.8  4623.5  219.03
  4821.6  210.44  4882.7  208.93  4968.6  208.35  4974.7  206.31  4989.5  203.16
  5001.2  202.44  5003.9  201.94  5007.2  202.44  5010.3  204.09  5039.8  208.28
  5114.3  209.54  5273.6   209.3  5342.3  208.21  5389.1  208.59  5462.3  211.55
  5540.7  215.56  5576.2  218.17  5596.4  218.69  5626.6  220.94  5697.3  224.05
  5747.7  227.88  5770.6  228.53    5788  230.27  5848.9  233.82    5915  239.95
#Mann= 5 ,-1 , 0
  4372.8      .1       0  5001.2     .07       0  5007.2      .1       0
  5114.3     .16       0  5342.3      .1       0
Bank Sta=4968.6,5039.8
XS Rating Curve= 0 ,0
Exp/Cntr=0.3,0.1

Type RM Length L Ch R = 1 ,44980   ,435,435,435
BEGIN DESCRIPTION:
MUSTANG CREEK 64.0
END DESCRIPTION:
XS GIS Cut Line= 3
      2317737.72     13303646.85      2317187.72     13303546.85
      2315987.69     13303746.86
#Sta/Elev= 30
  4410.1  227.38  4436.8  225.27  4501.6  222.98  4511.7  221.31  4551.6  220.54
  4650.9  215.27  4718.8  213.04  4772.2  209.84  4857.3  208.23    4884  206.64
  4948.7   206.5  4971.7  206.12  4979.3  203.32  4989.4  202.96  4999.1  199.31
  5001.8  198.81  5005.1  199.31  5009.7  199.72  5019.8  203.97  5029.9  206.41
  5202.3  206.56  5307.9  207.89  5427.9  208.75  5516.6  206.84  5610.3  209.19
  5820.7  219.78  6036.1  233.34  6074.2  237.12  6104.6  241.56  6185.7  246.91
#Mann= 7 ,-1 , 0
  4410.1      .1       0  4551.6     .05       0  4650.9     .12       0
  4948.7     .16       0  4999.1     .07       0  5005.1     .16       0
  5307.9      .1       0
Bank Sta=4971.7,5029.9
XS Rating Curve= 0 ,0
Exp/Cntr=0.3,0.1

Type RM Length L Ch R = 1 ,44545   ,457,457,457
BEGIN DESCRIPTION:
MUSTANG CREEK 63.0
END DESCRIPTION:
XS GIS Cut Line= 3
      2317637.73     13302746.85      2317037.72     13303146.85
       2315837.7     13303346.86
#Sta/Elev= 30
  4282.2  236.08  4361.8   226.6  4539.6  213.49    4660  207.97  4737.4  205.26
  4851.6  204.82  4887.6  203.83  4902.7  201.83  4917.7  203.77  4938.7  202.85
  4959.8  204.02  4967.3  200.61  4976.6  199.18  4995.8  198.11  4997.3  197.16
  5000.1  196.66  5003.3  197.16  5005.9  197.16  5013.5  204.03  5135.1  205.49
  5266.9  203.75  5335.3  205.63  5462.1  205.04  5621.7  213.53    5822  226.63
  5948.7  233.46  6057.7   241.3  6131.2  245.01  6186.9  250.72  6219.9  252.34
#Mann= 6 ,-1 , 0
  4282.2      .1       0  4539.6     .05       0    4660     .12       0
  4976.6      .1       0  4997.3     .07       0  5003.3      .1       0
Bank Sta=4959.8,5013.5
XS Rating Curve= 0 ,0
Exp/Cntr=0.3,0.1

Type RM Length L Ch R = 1 ,44088   ,376,376,376
BEGIN DESCRIPTION:
MUSTANG CREEK 62.0
END DESCRIPTION:
XS GIS Cut Line= 3
      2317587.74     13302646.85      2316987.72     13302696.85
      2315787.75     13303296.84
#Sta/Elev= 30
  4373.5  232.85  4436.2   228.8  4473.9   223.7  4531.5  219.18  4551.6  216.77
  4594.3  214.94  4630.3  212.04  4792.5  202.95  4955.5  201.45  4979.4  200.06
  4989.6  199.99    4995  196.64  4997.7  196.14    5001  196.64  5011.9  196.84
  5028.7  200.33  5051.1  201.22  5199.2  203.91  5257.9  202.13  5369.7  204.32
  5400.4  202.55  5436.8  203.54  5526.2  209.16  5624.1  212.99  5668.8  216.04
  5727.5  218.37  5847.7  226.04  6026.5  234.55  6057.3  240.19  6317.2  254.32
#Mann= 6 ,-1 , 0
  4373.5      .1       0  4531.5     .05       0  4630.3     .12       0
  4979.4      .1       0    4995     .07       0    5001      .1       0
Bank Sta=4955.5,5051.1
XS Rating Curve= 0 ,0
Exp/Cntr=0.3,0.1

Type RM Length L Ch R = 1 ,43712   ,440,440,440
BEGIN DESCRIPTION:
MUSTANG CREEK 61.0
END DESCRIPTION:
XS GIS Cut Line= 4
      2317833.28      13302443.3      2317221.26      13302304.4
      2316444.35     13302386.86      2315927.86     13302807.87
#Sta/Elev= 30
  4079.6  242.56  4146.8  238.28  4290.4  232.46  4357.1  227.43  4464.7  221.96
  4491.6  219.22  4539.8  217.53  4583.7  213.33    4598  214.34    4626  211.37
  4683.7  208.88  4757.4  204.95  4841.5  201.01    4942  199.88  4982.3  198.51
  4999.4  195.74  5002.1  195.24  5005.4  195.74  5022.5  198.98  5032.5  199.56
  5092.9  198.68  5157.5  200.16  5203.5  203.15  5299.7  206.87  5528.6  216.06
  5685.2  220.42  5876.9  223.67  5905.6  225.27  5940.8  225.42  6154.8  231.76
#Mann= 7 ,-1 , 0
  4079.6      .1       0  4583.7     .05       0  4683.7      .1       0
  4757.4     .12       0  4999.4     .07       0  5005.4     .12       0
  5299.7      .1       0
Bank Sta=4942,5032.5
XS Rating Curve= 0 ,0
Exp/Cntr=0.3,0.1

Type RM Length L Ch R = 1 ,43272   ,546,546,546
BEGIN DESCRIPTION:
MUSTANG CREEK 60.0
END DESCRIPTION:
XS GIS Cut Line= 4
      2317928.72     13302304.39      2317442.61     13301866.03
      2316531.15     13301983.22      2315888.78     13302729.75
#Sta/Elev= 30
  3671.3  241.51  3854.4  236.39  4066.6  227.56  4102.5   226.9  4109.2  228.01
  4116.7  226.54  4123.4  227.12  4151.8  225.05  4307.3  220.41  4414.2  215.57
  4492.1   210.2  4513.5  210.32  4712.3  199.65  4766.5  198.21  4804.7  198.84
  4958.3  197.49    4966   197.5    4974  196.99  4995.1  196.12  5003.3  194.45
  5006.1  193.95  5009.3  194.45  5016.4  196.48  5036.6  198.07  5094.2  201.47
    5244  209.14    5392  213.78  5668.5  220.54  5916.4   223.2  6229.7  229.76
#Mann= 9 ,-1 , 0
  3671.3      .1       0  4414.2     .05       0  4513.5     .16       0
  4712.3     .12       0  4958.3      .1       0    4974     .12       0
  5003.3     .07       0  5009.3     .12       0  5094.2      .1       0
Bank Sta=4966,5036.6
XS Rating Curve= 0 ,0
Exp/Cntr=0.3,0.1