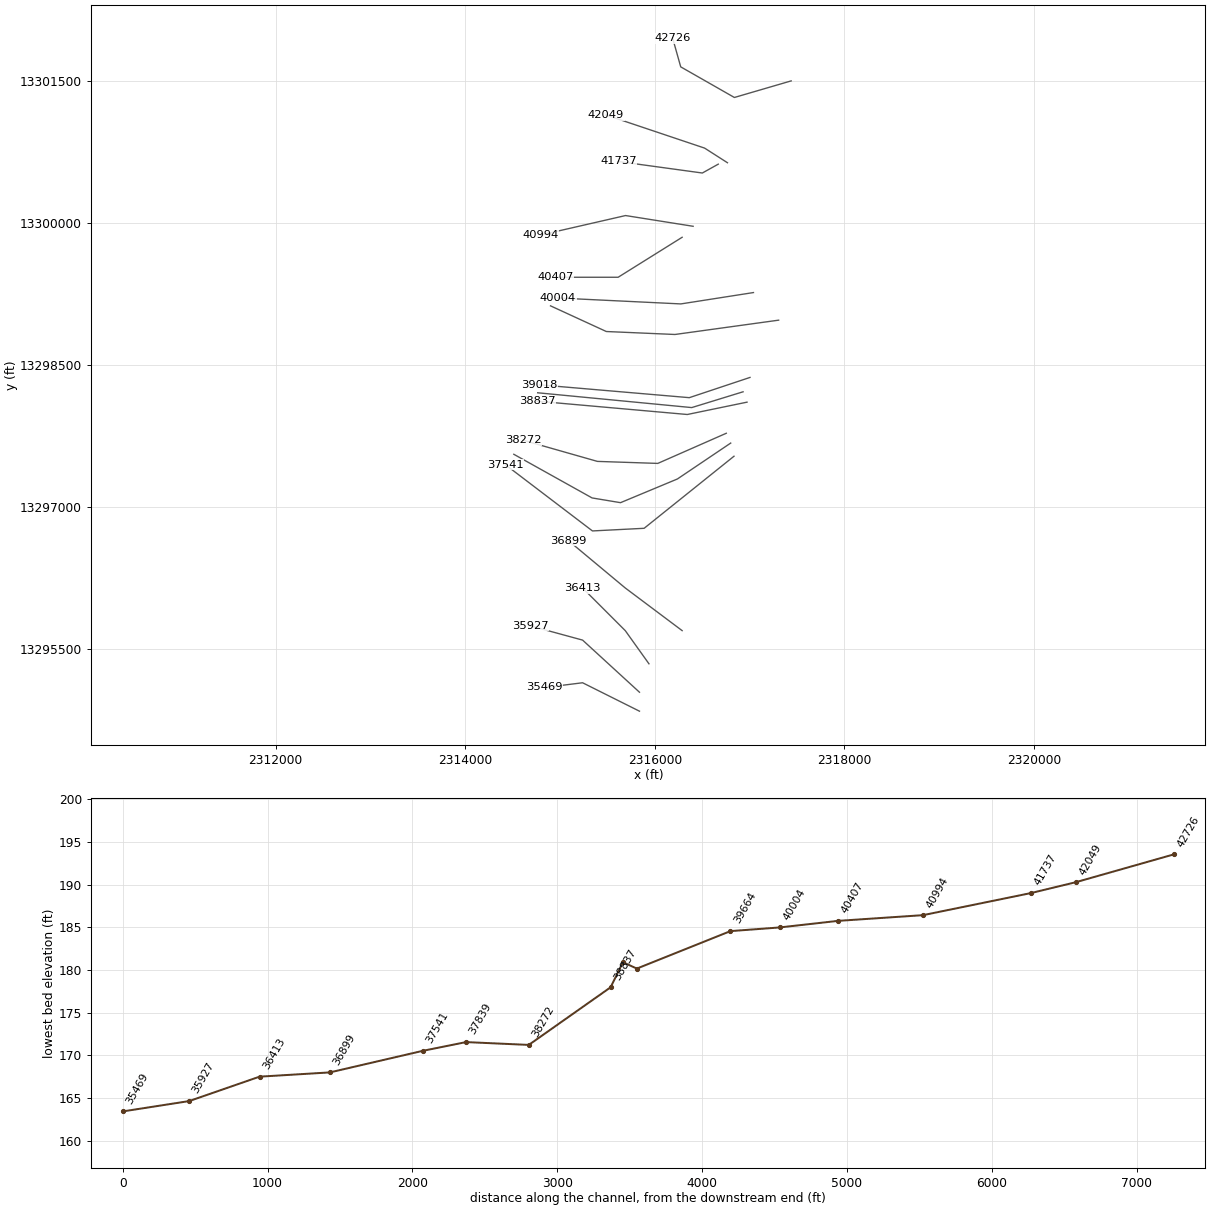
HEC-RAS study MUSTANG CREEK.prj: MUSTANG CREEK Base Level Engineering

--- MUSTANG CREEK.g01 (geometry) --- (continued)

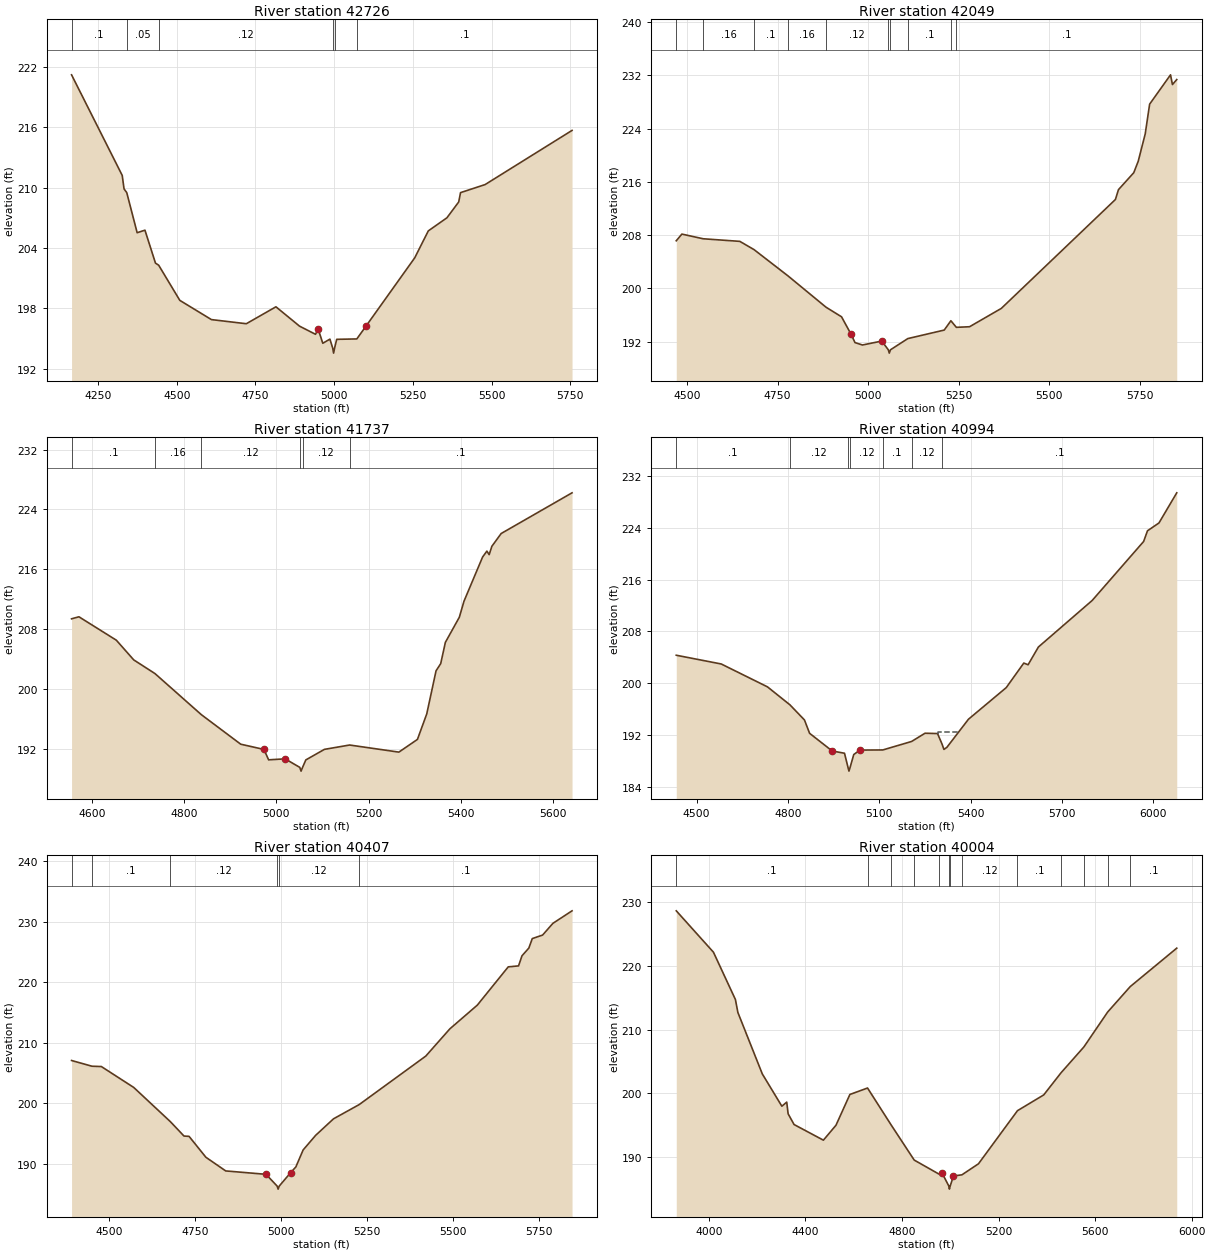
Type RM Length L Ch R = 1 ,42726   ,677,677,677
BEGIN DESCRIPTION:
MUSTANG CREEK 59.0
END DESCRIPTION:
XS GIS Cut Line= 4
       2317437.7     13301496.85      2316838.73     13301321.83
      2316272.76     13301644.75      2316187.71     13301946.88
#Sta/Elev= 30
    4166   221.2  4326.9  211.21  4332.7  209.87  4341.3   209.5  4374.3  205.52
  4399.1  205.77  4432.5   202.5  4442.7  202.29  4509.8   198.8  4610.2  196.89
    4721  196.48  4815.1  198.16    4890  196.24  4940.8  195.43  4949.1  195.96
  4963.9  194.54  4986.5  194.95  4995.4  194.06  4998.2  193.56  5001.4  194.06
  5008.1  194.93    5072  194.97    5102  196.28  5255.8  203.02    5299   205.7
  5358.1     207  5395.5  208.57  5401.4   209.5  5479.4   210.3  5755.5  215.68
#Mann= 6 ,-1 , 0
    4166      .1       0  4341.3     .05       0  4442.7     .12       0
  4995.4     .07       0  5001.4     .12       0    5072      .1       0
Bank Sta=4949.1,5102
XS Rating Curve= 0 ,0
Exp/Cntr=0.3,0.1

Type RM Length L Ch R = 1 ,42049   ,312,312,312
BEGIN DESCRIPTION:
MUSTANG CREEK 58.0
END DESCRIPTION:
XS GIS Cut Line= 3
      2316765.57     13300633.36      2316524.68     13300787.64
      2315485.13     13301136.87
#Sta/Elev= 30
    4470  207.16  4485.5  208.16  4544.3  207.46  4645.6  207.07  4684.9  205.83
  4778.9  201.88  4883.5   197.2  4926.6  195.75  4952.9  193.13  4963.8  191.88
  4984.4  191.52  5037.7  192.11  5055.8   190.8  5058.5   190.3  5061.8   190.8
  5109.6  192.48  5210.3  193.76  5228.7  195.16  5243.8  194.17  5280.3  194.26
    5368  197.01  5683.2  213.35  5691.7  214.83  5733.9  217.37  5746.2  219.08
  5765.6   223.2  5777.8  227.66  5835.5  232.06  5840.8   230.6  5852.7  231.35
#Mann= 10 ,-1 , 0
    4470      .1       0  4544.3     .16       0  4684.9      .1       0
  4778.9     .16       0  4883.5     .12       0  5055.8     .07       0
  5061.8     .12       0  5109.6      .1       0  5228.7     .12       0
  5243.8      .1       0
Bank Sta=4952.9,5037.7
XS Rating Curve= 0 ,0
Exp/Cntr=0.3,0.1

Type RM Length L Ch R = 1 ,41737   ,743,743,743
BEGIN DESCRIPTION:
MUSTANG CREEK 57.0
END DESCRIPTION:
XS GIS Cut Line= 3
      2316668.89     13300618.45      2316500.77     13300524.88
      2315615.38     13300646.41
#Sta/Elev= 30
  4555.6  209.38  4571.6  209.65  4652.8  206.52  4690.5  203.89  4736.6  202.06
  4837.2  196.57  4922.7  192.62  4973.1  191.92  4983.2  190.53  5019.2  190.66
  5050.9  189.52  5053.6  189.02  5056.9  189.52    5064  190.52  5104.4  191.93
  5159.1  192.51  5265.9  191.56  5306.2  193.26  5326.4  196.67  5346.6  202.43
  5356.7  203.39  5366.8  206.23  5397.1  209.59  5407.2  211.73  5447.6  217.64
  5456.9  218.43  5461.9  217.96  5467.7  219.07  5487.9  220.78  5641.7  226.22
#Mann= 6 ,-1 , 0
  4555.6      .1       0  4736.6     .16       0  4837.2     .12       0
  5050.9     .07       0  5056.9     .12       0  5159.1      .1       0
Bank Sta=4973.1,5019.2
XS Rating Curve= 0 ,0
Exp/Cntr=0.3,0.1

Type RM Length L Ch R = 1 ,40994   ,587,587,587
BEGIN DESCRIPTION:
MUSTANG CREEK 56.0
END DESCRIPTION:
XS GIS Cut Line= 3
      2316403.58     13299962.82      2315690.87      13300076.1
      2314791.71     13299869.73
#Sta/Elev= 30
  4433.2  204.33  4580.9  202.98  4732.8  199.45  4806.7  196.67  4854.3  194.34
  4871.2  192.28  4945.4  189.55  4985.9   189.2  4997.8  186.94  5000.5  186.44
  5003.8  186.94  5016.3     189  5036.5  189.69  5111.8  189.71  5206.4  191.02
  5250.4  192.29  5291.5  192.24  5306.4  190.61  5312.5  189.79  5322.2  190.11
  5393.1  194.45  5517.2  199.33  5574.9  203.12    5589  202.86  5622.9   205.6
  5799.5  212.78  5968.6  221.89  5981.3  223.54    6019  224.75  6077.4   229.4
#Mann= 7 ,-1 , 0
  4433.2      .1       0  4806.7     .12       0  4997.8     .07       0
  5003.8     .12       0  5111.8      .1       0  5206.4     .12       0
  5306.4      .1       0
#XS Ineff= 1 ,-1
 5291.56 5361.88  192.44
Permanent Ineff=
       F
Bank Sta=4945.4,5036.5
XS Rating Curve= 0 ,0
Exp/Cntr=0.3,0.1

Type RM Length L Ch R = 1 ,40407   ,403,403,403
BEGIN DESCRIPTION:
MUSTANG CREEK 55.0
END DESCRIPTION:
XS GIS Cut Line= 3
      2316287.74     13299846.87      2315612.75     13299425.06
        2314952.     13299425.06
#Sta/Elev= 30
  4389.8  207.05  4449.4   206.1  4476.5  206.05  4570.8  202.59  4676.9  196.96
  4717.1  194.55  4731.8   194.5  4780.8  191.04  4838.5  188.78  4955.8  188.22
  4988.2  186.27    4991  185.77  4994.2  186.27  5027.2  188.48  5042.6  189.44
  5063.8  192.25  5100.3  194.67  5152.2   197.4  5226.8  199.75  5420.8  207.78
  5490.8  212.28  5570.8  216.21  5660.8  222.54  5690.8   222.7  5700.8  224.37
  5720.8  225.65  5730.8  227.22  5760.8   227.8  5790.8  229.74  5846.5  231.81
#Mann= 6 ,-1 , 0
  4389.8     .05       0  4449.4      .1       0  4676.9     .12       0
  4988.2     .07       0  4994.2     .12       0  5226.8      .1       0
Bank Sta=4955.8,5027.2
XS Rating Curve= 0 ,0
Exp/Cntr=0.3,0.1

Type RM Length L Ch R = 1 ,40004   ,340,340,340
BEGIN DESCRIPTION:
MUSTANG CREEK 54.0
END DESCRIPTION:
XS GIS Cut Line= 3
      2317039.87      13299263.6      2316274.21     13299143.81
      2314977.29     13299206.31
#Sta/Elev= 30
  3864.9   228.6  4018.9  222.12    4110   214.7  4120.1  212.68  4221.3  203.05
  4302.3  197.99  4322.5  198.63  4328.3   196.8  4352.9  195.12  4474.4  192.67
  4526.6  195.01  4584.2  199.83  4657.3  200.84  4755.7  195.02  4850.7  189.55
  4952.6  187.37  4966.7  187.48  4993.8   185.5  4996.5     185  4999.8   185.5
  5013.3  187.06  5048.3  187.24  5116.9  188.97  5278.5  197.29  5387.2  199.76
    5459  203.23  5553.7  207.28    5652  212.74  5745.6  216.73  5938.3  222.75
#Mann= 13 ,-1 , 0
  3864.9      .1       0  4657.3     .05       0  4755.7     .16       0
  4850.7     .05       0  4952.6     .16       0  4993.8     .07       0
  4999.8     .16       0  5048.3     .12       0  5278.5      .1       0
    5459     .16       0  5553.7      .1       0    5652     .16       0
  5745.6      .1       0
Bank Sta=4966.7,5013.3
XS Rating Curve= 0 ,0
Exp/Cntr=0.3,0.1

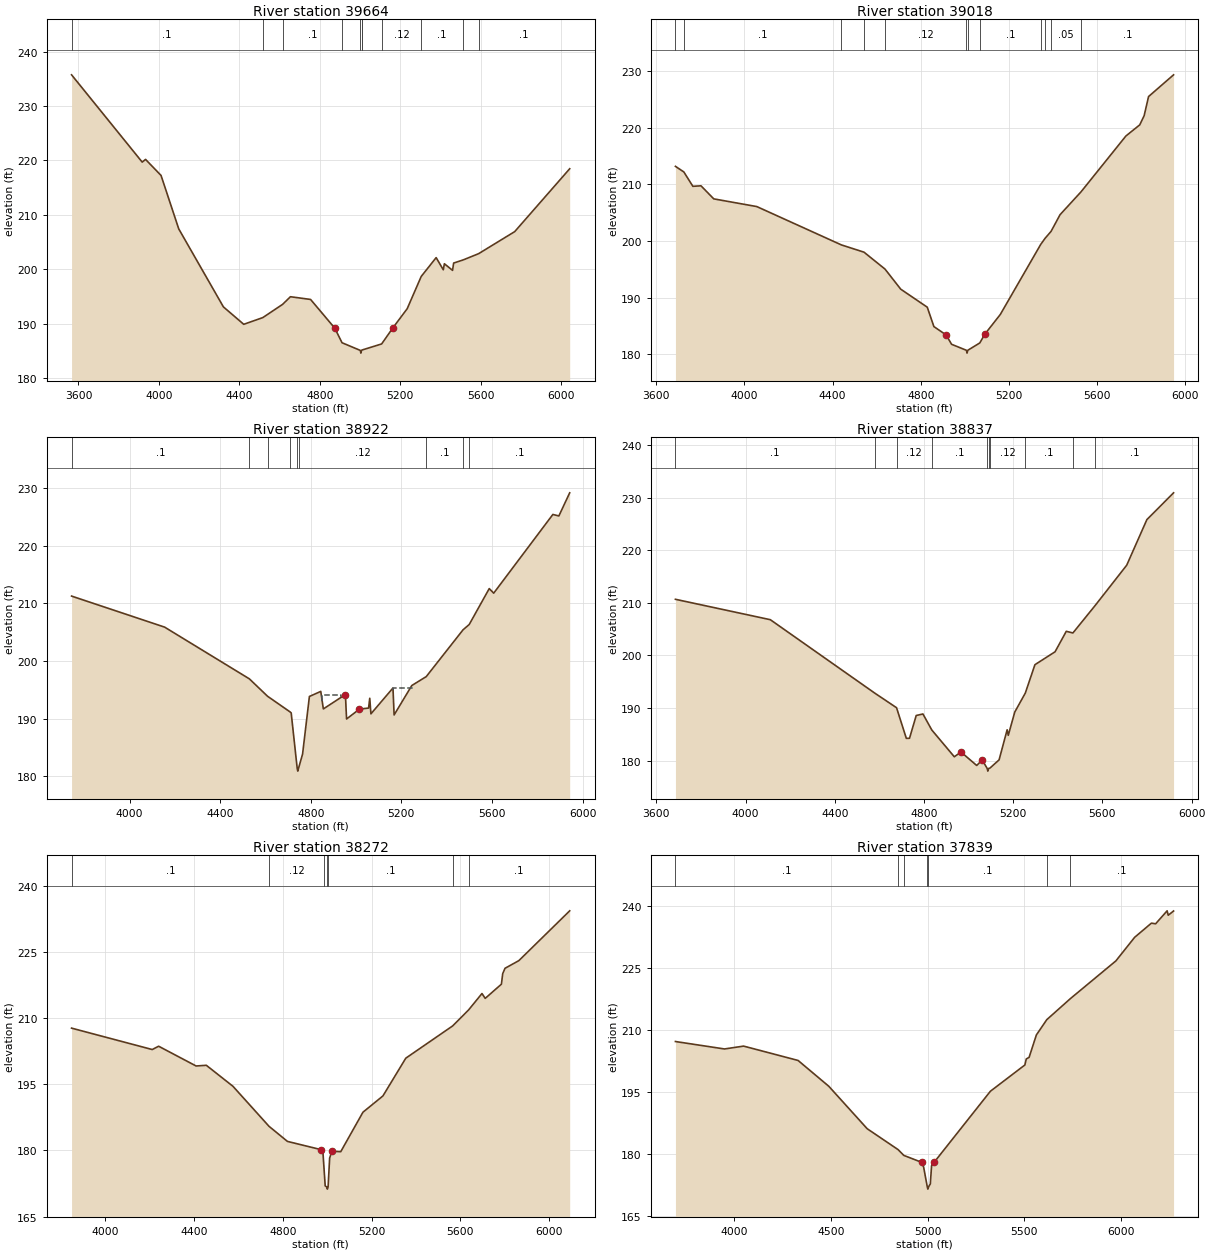
Type RM Length L Ch R = 1 ,39664   ,646,646,646
BEGIN DESCRIPTION:
Mapping XS f1f73687
END DESCRIPTION:
XS GIS Cut Line= 4
      2317305.65      13298972.4      2316211.86     13298821.36
       2315487.9     13298852.61      2314899.33     13299123.45
#Sta/Elev= 30
  3565.8  235.74    3917  219.69  3933.7  220.19  4010.7  217.24  4098.7  207.41
  4320.8  193.07  4421.8  189.87  4516.5   191.1  4615.2  193.54    4654  194.94
  4754.2  194.44  4874.3  189.17  4910.6  186.48  5001.4  185.07  5004.2  184.57
  5007.4  185.07    5009  185.13  5107.5  186.26  5164.6  189.28  5234.6  192.74
  5304.3  198.67  5378.5  202.13    5414   199.9  5419.5     201    5460  199.79
  5465.5  201.13  5513.2  201.71  5589.8  202.86  5769.1  206.91  6042.5  218.47
#Mann= 11 ,-1 , 0
  3565.8      .1       0  4516.5     .05       0  4615.2      .1       0
  4910.6     .12       0  5001.4     .07       0  5007.4     .12       0
    5009      .1       0  5107.5     .12       0  5304.3      .1       0
  5513.2     .05       0  5589.8      .1       0
Bank Sta=4874.3,5164.6
XS Rating Curve= 0 ,0
Exp/Cntr=0.3,0.1

Type RM Length L Ch R = 1 ,39018   ,96,96,96
BEGIN DESCRIPTION:
Mapping XS 96bc66fd
END DESCRIPTION:
XS GIS Cut Line= 3
      2317003.48     13298368.22       2316362.9     13298154.69
      2314784.73     13298290.11
#Sta/Elev= 30
  3686.9   213.2    3725  212.21  3765.9  209.67  3802.8  209.76  3860.7  207.45
  4055.8  206.09  4439.6  199.31    4542  198.03  4637.3  195.04  4708.6  191.49
    4829   188.3  4859.1  184.87  4914.1  183.41  4939.4  181.74  5006.7  180.68
  5009.4  180.18  5012.7  180.68  5067.2  181.98    5090  183.52  5160.2  187.01
  5343.6   199.4  5363.2  200.47  5390.4   201.7  5431.2  204.65  5526.5   208.7
    5730  218.57  5792.6  220.53  5812.6  222.15  5832.7  225.54  5946.1  229.38
#Mann= 12 ,-1 , 0
  3686.9     .05       0    3725      .1       0  4439.6     .16       0
    4542      .1       0  4637.3     .12       0  5006.7     .07       0
  5012.7     .12       0  5067.2      .1       0  5343.6     .12       0
  5363.2      .1       0  5390.4     .05       0  5526.5      .1       0
Bank Sta=4914.1,5090
XS Rating Curve= 0 ,0
Exp/Cntr=0.3,0.1

Type RM Length L Ch R = 1 ,38922   ,85,85,85
BEGIN DESCRIPTION:
MUSTANG CREEK 53.0
END DESCRIPTION:
XS GIS Cut Line= 3
      2316930.43     13298216.72      2316388.79     13298050.06
      2314763.79     13298206.31
#Sta/Elev= 30
    3744  211.27  4154.9  205.89  4529.1  196.92  4609.2  193.91  4708.1  191.21
  4713.6  191.03  4740.1  181.43  4742.8  180.93  4746.1  181.43  4763.9  183.89
    4794  193.87  4844.2  194.75  4855.6  191.71    4953  194.21  4958.1  189.97
    5015  191.68  5055.2  191.86  5060.5  193.56  5065.6  190.86    5163  195.34
    5168  190.67  5246.1  195.77  5309.8  197.31  5472.5  205.43  5499.5  206.34
    5588  212.57  5607.7  211.78  5868.9  225.42  5895.4  225.16  5943.2  229.17
#Mann= 9 ,-1 , 0
    3744      .1       0  4529.1     .16       0  4609.2      .1       0
  4708.1     .12       0  4740.1     .07       0  4746.1     .12       0
  5309.8      .1       0  5472.5     .05       0  5499.5      .1       0
#XS Ineff= 2 ,-1
 4850.76 4934.13  194.12 5163.39 5249.36  195.36
Permanent Ineff=
       F       F
Bank Sta=4953,5015
XS Rating Curve= 0 ,0
Exp/Cntr=0.3,0.1

Type RM Length L Ch R = 1 ,38837   ,565,565,565
BEGIN DESCRIPTION:
MUSTANG CREEK 52.0
END DESCRIPTION:
XS GIS Cut Line= 3
      2316972.12     13298107.35      2316341.92     13297977.14
      2314758.56     13298117.77
#Sta/Elev= 30
  3685.9  210.67  4111.3  206.79  4578.3  192.86  4677.1  190.05    4721  184.22
  4735.2  184.24  4765.3  188.57  4795.4  188.86  4835.2  185.81    4936  180.72
  4966.1  181.62  5036.4  179.07  5061.2   180.1  5083.6  178.49  5086.3  177.99
  5089.6  178.49  5096.2  178.58  5136.8  180.13  5172.9  185.85    5178   184.8
  5207.1  189.23  5254.3  192.83  5297.4  198.23  5387.8  200.69    5438  204.58
  5467.8  204.27  5566.7  209.45    5709  217.16  5799.4  225.83    5919  230.92
#Mann= 10 ,-1 , 0
  3685.9      .1       0  4578.3     .16       0  4677.1     .12       0
  4835.2      .1       0  5083.6     .07       0  5089.6      .1       0
  5096.2     .12       0  5254.3      .1       0  5467.8     .05       0
  5566.7      .1       0
Bank Sta=4966.1,5061.2
XS Rating Curve= 0 ,0
Exp/Cntr=0.3,0.1

Type RM Length L Ch R = 1 ,38272   ,433,433,433
BEGIN DESCRIPTION:
MUSTANG CREEK 51.0
END DESCRIPTION:
XS GIS Cut Line= 4
      2316753.36     13297779.22       2316030.8     13297461.12
        2315394.     13297482.35       2314607.5     13297706.32
#Sta/Elev= 30
  3848.5  207.74    4212  202.89  4240.8  203.64  4409.6  199.16  4455.6  199.32
  4575.8  194.55  4738.2  185.48  4821.2  182.06  4971.2  180.21  4981.3  179.44
  4985.2  176.52  4991.3  171.95  4998.3  171.74    5001  171.24  5004.3  171.74
  5011.3  178.28  5021.3  179.82  5061.3  179.73  5161.4  188.68  5251.4  192.37
  5354.4  200.93  5565.4  208.24  5637.4  211.87  5697.6  215.59  5712.3  214.49
  5785.2  217.71  5791.1   220.1  5801.5  221.31  5863.9  223.05  6092.9  234.34
#Mann= 7 ,-1 , 0
  3848.5      .1       0  4738.2     .12       0  4985.2      .1       0
  4998.3     .07       0  5004.3      .1       0  5565.4     .05       0
  5637.4      .1       0
Bank Sta=4971.2,5021.3
XS Rating Curve= 0 ,0
Exp/Cntr=0.3,0.1

Type RM Length L Ch R = 1 ,37839   ,298,298,298
BEGIN DESCRIPTION:
MUSTANG CREEK 50.0
END DESCRIPTION:
XS GIS Cut Line= 5
      2316799.93     13297675.74      2316237.72     13297296.85
      2315637.72     13297046.85      2315337.72     13297096.85
      2314512.21     13297557.42
#Sta/Elev= 30
  3694.7  207.29  3948.4  205.49  4047.4  206.18  4329.2  202.71    4488  196.47
  4686.8  186.19  4846.8  181.13  4876.4  179.73  4968.5  178.06  4978.8  176.92
    4998  172.07  5000.7  171.57    5004  172.07  5013.5  172.84    5020  177.26
  5032.8  178.04  5324.3  195.26  5502.8  201.62    5510  203.07  5524.5  203.45
  5562.2  208.88  5616.1  212.58  5738.4  217.68  5973.6   226.8  6070.7  232.51
  6157.5  235.94  6179.2  235.78  6238.7  238.92  6244.4  237.85  6272.1  238.88
#Mann= 7 ,-1 , 0
  3694.7      .1       0  4846.8     .12       0  4876.4      .1       0
    4998     .07       0    5004      .1       0  5616.1     .05       0
  5738.4      .1       0
Bank Sta=4968.5,5032.8
XS Rating Curve= 0 ,0
Exp/Cntr=0.3,0.1

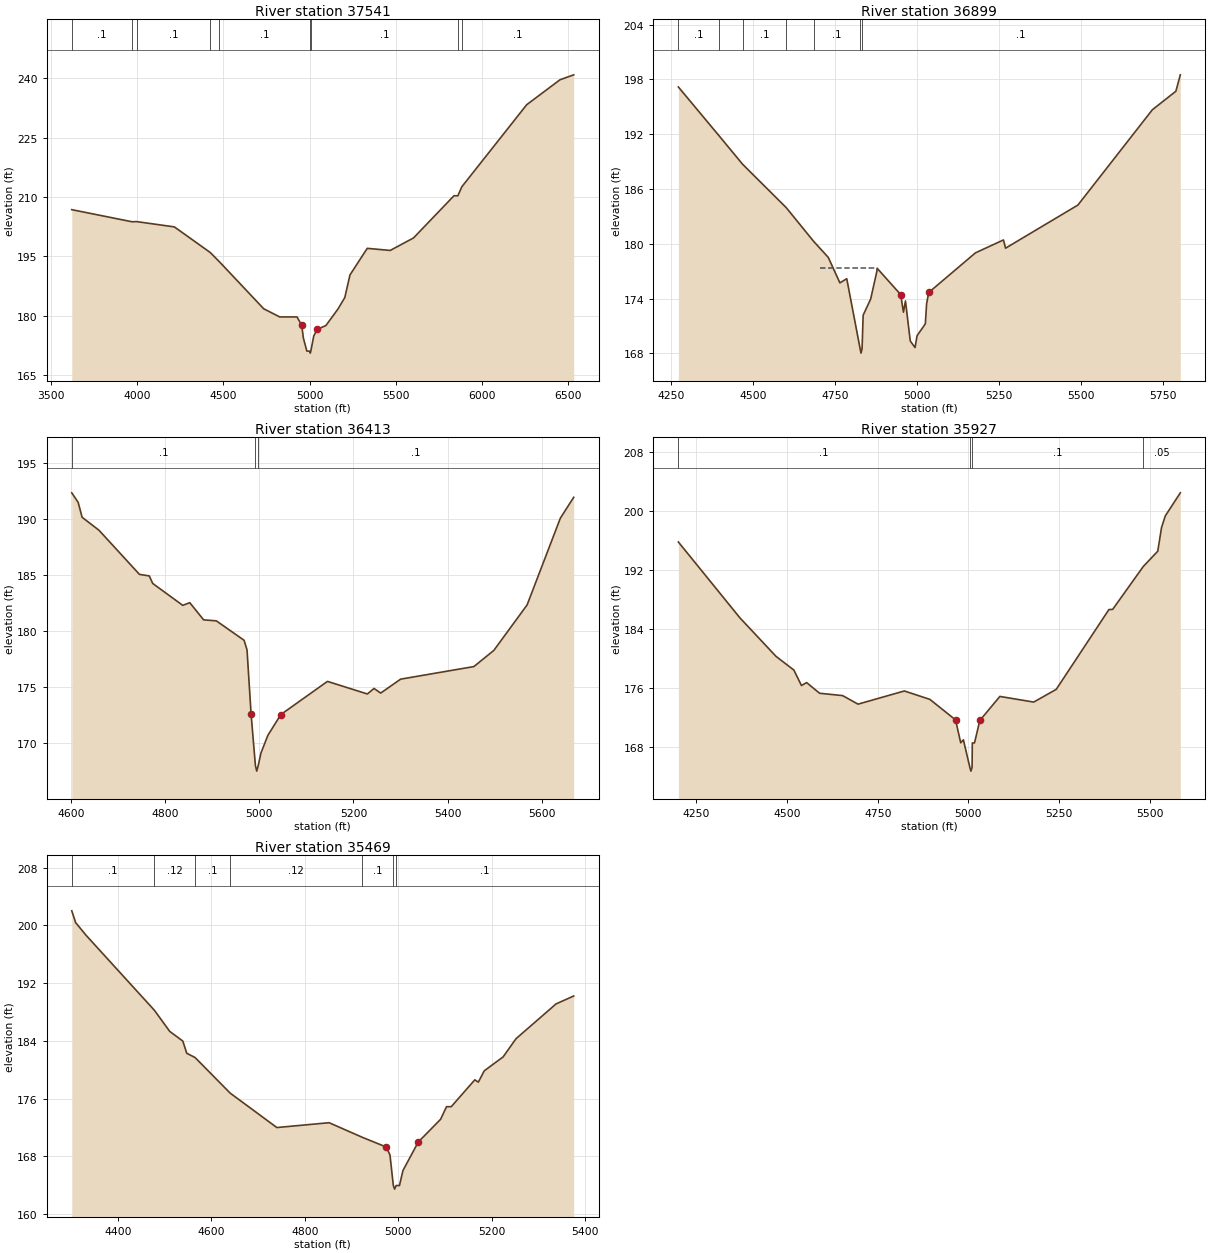
Type RM Length L Ch R = 1 ,37541   ,642,642,642
BEGIN DESCRIPTION:
MUSTANG CREEK 49.0
END DESCRIPTION:
XS GIS Cut Line= 4
      2316834.63     13297536.84      2315886.74     13296776.44
       2315341.6     13296748.66       2314424.9      13297446.6
#Sta/Elev= 30
  3619.5  206.82  3969.7  203.76  3996.5   203.8  4215.2  202.46  4423.8  195.97
  4476.9  193.63  4733.7  181.76  4826.5   179.7  4926.8   179.7  4953.9  177.63
  4963.9  174.34  4983.9  171.07  5000.9  171.05  5003.7  170.55  5006.9  171.05
    5024  174.89    5044  176.56  5094.1  177.51  5164.1  181.67  5204.2   184.6
  5234.2  190.32  5334.4  197.04  5467.7  196.51  5602.9  199.67  5837.9  210.34
  5860.4  210.33  5883.2   212.6  6259.8  233.35  6453.1  239.66  6532.7  240.91
#Mann= 9 ,-1 , 0
  3619.5      .1       0  3969.7     .05       0  3996.5      .1       0
  4423.8     .05       0  4476.9      .1       0  5000.9     .07       0
  5006.9      .1       0  5860.4     .05       0  5883.2      .1       0
Bank Sta=4953.9,5044
XS Rating Curve= 0 ,0
Exp/Cntr=0.3,0.1

Type RM Length L Ch R = 1 ,36899   ,486,486,486
BEGIN DESCRIPTION:
MUSTANG CREEK 48.0
END DESCRIPTION:
XS GIS Cut Line= 3
      2316287.74     13295696.84      2315687.72     13296146.85
      2315087.75     13296646.83
#Sta/Elev= 30
  4272.1  197.16  4394.8  191.88    4468   188.7  4601.1  183.95  4684.4  180.27
  4729.4   178.5  4764.8  175.71  4785.7  176.17  4826.4  168.52  4829.2  168.02
  4832.4  168.52  4835.7  172.17  4858.6  173.94  4879.4  177.27  4950.2  174.43
  4958.6   172.5  4964.8  173.73  4979.4  169.35    4994  168.63  5000.2  169.93
  5025.4  171.23  5029.3  173.44  5035.8  174.66  5178.3     179  5263.6  180.41
  5270.1  179.51  5490.7  184.23  5717.9  194.67  5789.5  196.69  5803.1  198.49
#Mann= 7 ,-1 , 0
  4272.1      .1       0  4394.8     .12       0    4468      .1       0
  4601.1     .12       0  4684.4      .1       0  4826.4     .07       0
  4832.4      .1       0
#XS Ineff= 1 ,-1
 4704.84 4877.81  177.33
Permanent Ineff=
       F
Bank Sta=4950.2,5035.8
XS Rating Curve= 0 ,0
Exp/Cntr=0.3,0.1

Type RM Length L Ch R = 1 ,36413   ,486,486,486
BEGIN DESCRIPTION:
MUSTANG CREEK 47.0
END DESCRIPTION:
XS GIS Cut Line= 3
      2315937.72     13295346.86      2315687.72     13295696.85
      2315237.73     13296146.85
#Sta/Elev= 30
  4601.4   192.3  4614.9  191.46  4623.5  190.12  4659.2  188.97  4745.2  185.04
  4766.1   184.9  4773.4  184.23  4837.3  182.28  4852.1  182.52  4881.6  180.99
  4908.6   180.9  4967.6  179.17  4973.8  178.31  4982.4  172.62  4991.6  168.02
  4994.4  167.52  4997.6  168.02  5003.3  169.12    5018   170.7  5045.7  172.56
  5144.7  175.51  5229.5  174.39  5243.6  174.88  5257.8  174.47  5300.2  175.71
  5455.8  176.83  5498.2  178.27  5568.9  182.32  5639.6  190.05  5667.9   191.9
#Mann= 3 ,-1 , 0
  4601.4      .1       0  4991.6     .07       0  4997.6      .1       0
Bank Sta=4982.4,5045.7
XS Rating Curve= 0 ,0
Exp/Cntr=0.3,0.1

Type RM Length L Ch R = 1 ,35927   ,458,458,458
BEGIN DESCRIPTION:
MUSTANG CREEK 46.0
END DESCRIPTION:
XS GIS Cut Line= 3
       2315837.7     13295046.88      2315237.72     13295596.85
      2314687.72     13295746.86
#Sta/Elev= 30
  4200.4  195.79  4370.2  185.48  4469.5  180.26  4518.9  178.39  4539.8  176.29
    4554  176.69  4589.8  175.24  4653.3  174.92  4695.8  173.76  4823.5  175.55
  4893.8  174.41  4964.7  171.62  4978.9  168.51  4986.3  168.91  5004.2  165.16
    5007  164.66  5010.2  165.16  5010.9  168.49  5016.9  168.49  5031.6  171.54
  5086.9  174.81  5180.2  174.04  5242.3  175.77  5387.5  186.61  5397.8  186.63
  5482.3  192.46  5522.2  194.54  5532.6  197.75  5542.9  199.33  5584.4  202.47
#Mann= 4 ,-1 , 0
  4200.4      .1       0  5004.2     .07       0  5010.2      .1       0
  5482.3     .05       0
Bank Sta=4964.7,5031.6
XS Rating Curve= 0 ,0
Exp/Cntr=0.3,0.1

Type RM Length L Ch R = 1 ,35469   ,464,464,464
BEGIN DESCRIPTION:
MUSTANG CREEK 45.0
END DESCRIPTION:
XS GIS Cut Line= 3
      2315837.73     13294846.85      2315237.72     13295146.85
      2314837.76     13295096.86
#Sta/Elev= 30
  4301.3     202  4309.7  200.36  4332.1   198.6  4478.3  188.21  4510.9   185.3
  4538.9  183.96  4547.3  182.27  4565.1  181.68  4640.2  176.75  4740.1  171.98
  4851.9  172.65  4922.5  170.64  4974.6  169.27  4982.2  168.14  4989.3  163.95
    4992  163.45  4995.3  163.95  5002.4  163.95  5009.9  166.03  5042.7  169.98
  5090.5  173.13  5103.1  174.87  5113.2  174.87  5163.6  178.59  5171.2  178.27
  5183.8  179.84  5224.1  181.76  5251.8  184.29  5337.5  189.11  5375.2   190.2
#Mann= 7 ,-1 , 0
  4301.3      .1       0  4478.3     .12       0  4565.1      .1       0
  4640.2     .12       0  4922.5      .1       0  4989.3     .07       0
  4995.3      .1       0
Bank Sta=4974.6,5042.7
XS Rating Curve= 0 ,0
Exp/Cntr=0.3,0.1