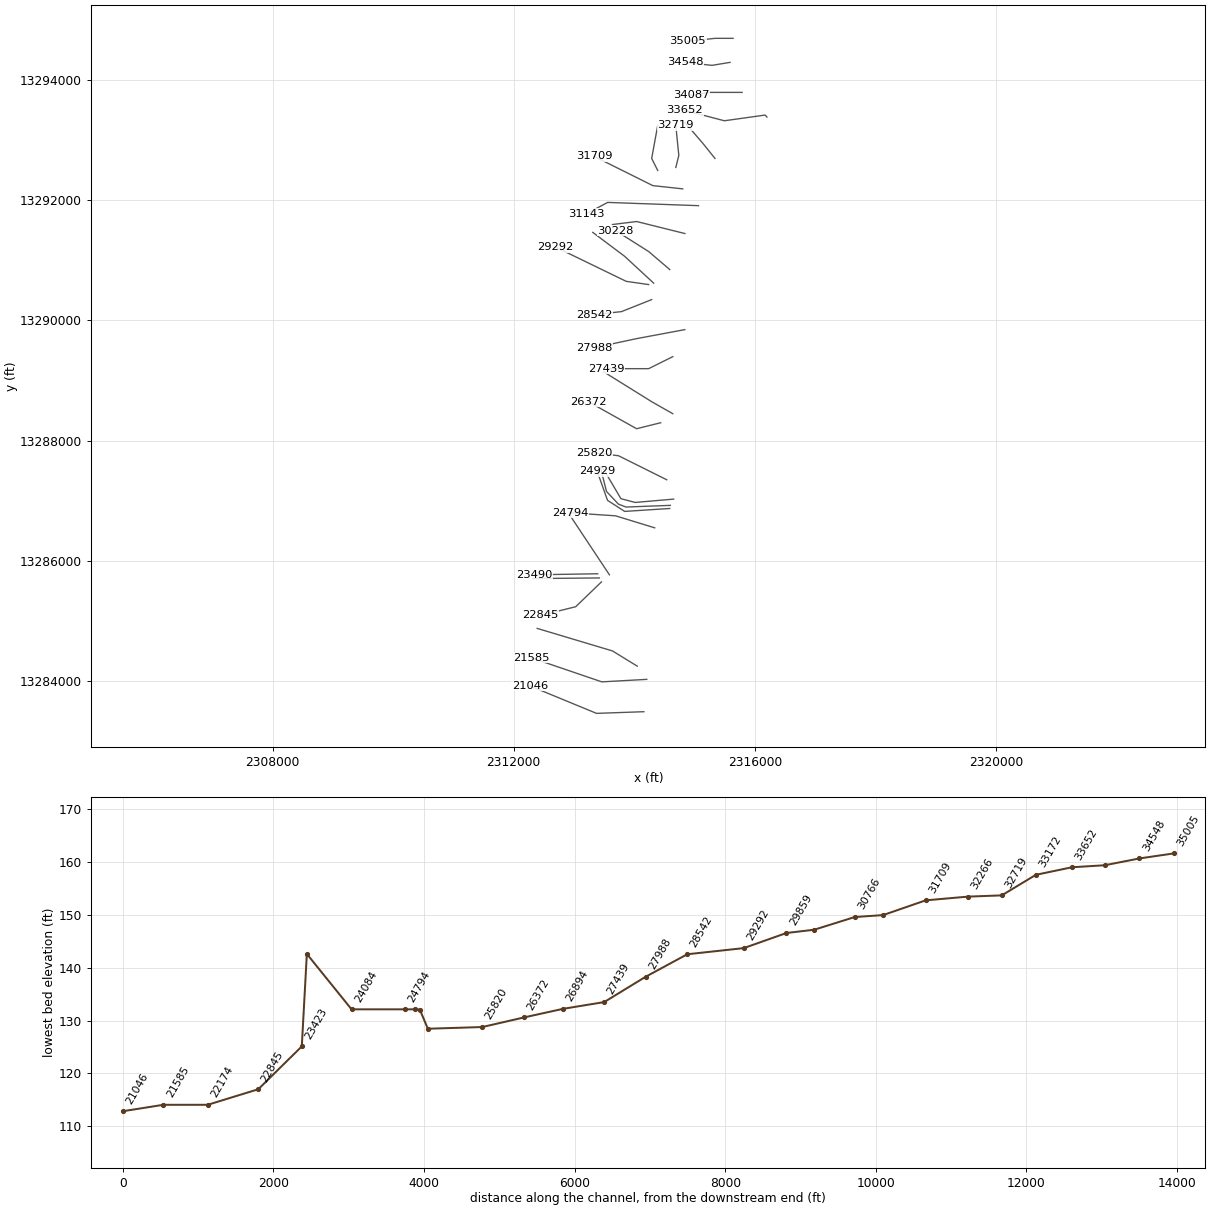
HEC-RAS study MUSTANG CREEK.prj: MUSTANG CREEK Base Level Engineering

--- MUSTANG CREEK.g01 (geometry) --- (continued)

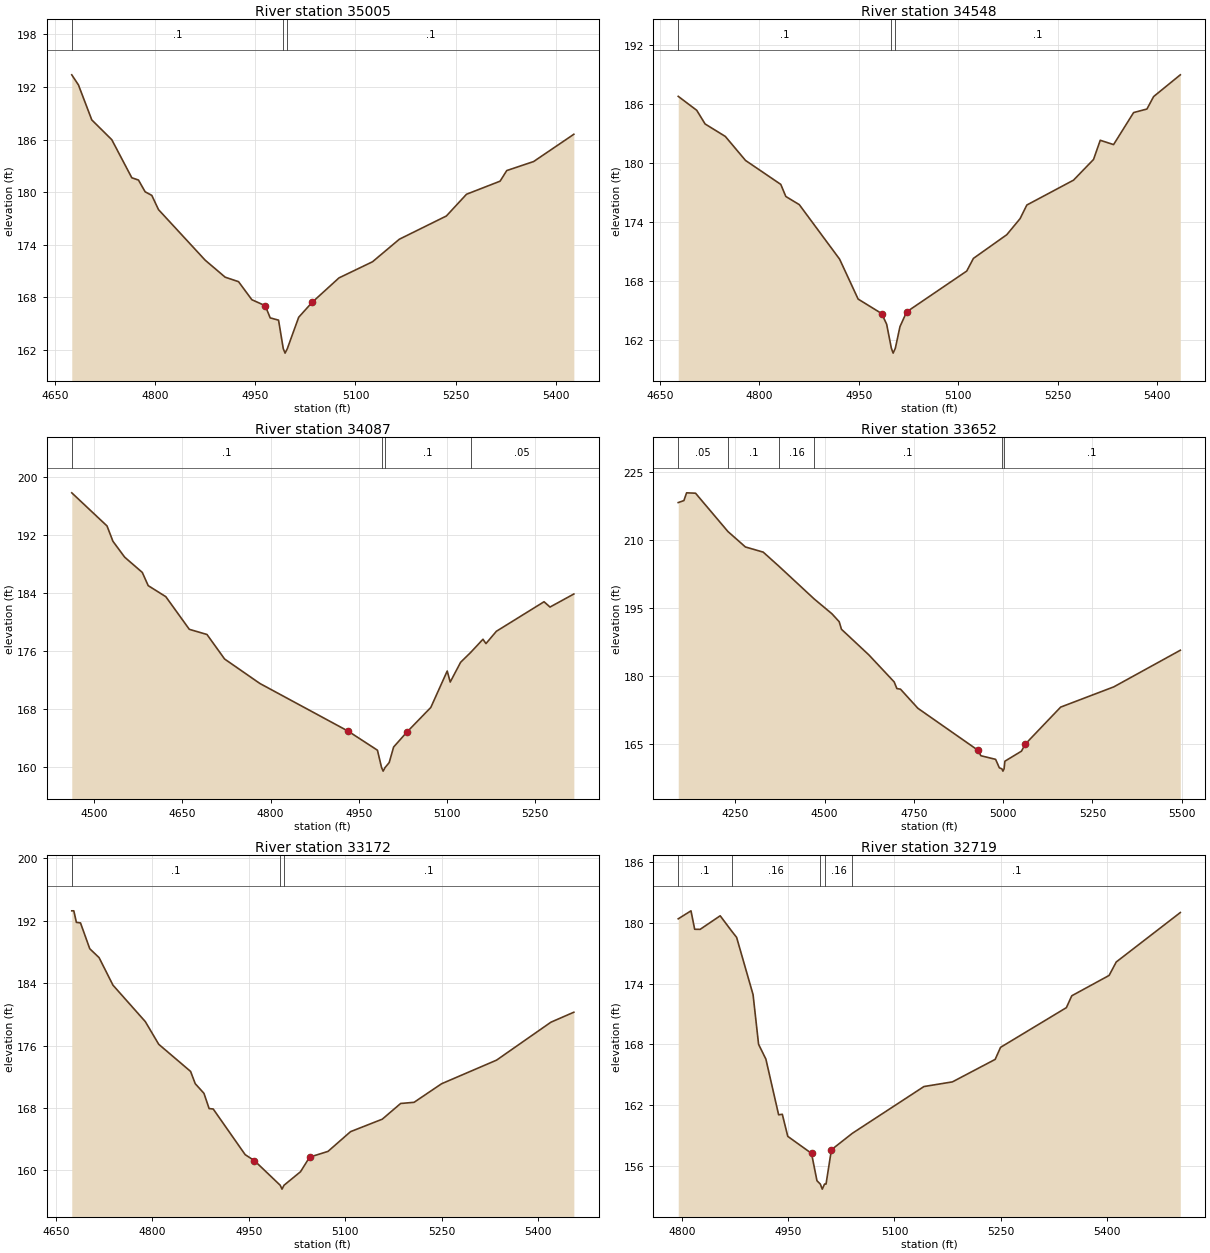
Type RM Length L Ch R = 1 ,35005   ,457,457,457
BEGIN DESCRIPTION:
MUSTANG CREEK 44.0
END DESCRIPTION:
XS GIS Cut Line= 3
      2315637.69     13294696.85      2315337.72     13294696.85
      2314887.76     13294646.86
#Sta/Elev= 30
  4674.7  193.38  4684.7  192.23  4704.7  188.24  4734.7  185.98  4764.7  181.64
  4774.7  181.38  4784.7  180.04  4794.7  179.63  4804.7  178.01  4874.7  172.24
  4904.7   170.3  4924.7  169.79  4944.7  167.73  4964.7  167.05  4972.2  165.66
  4984.7   165.4  4991.8  162.14  4994.5  161.64  4997.8  162.14  5014.9  165.73
    5035  167.43  5075.3  170.22  5125.6  172.06  5165.8  174.63  5236.3  177.28
  5266.5  179.76  5316.8  181.25  5326.8  182.46  5367.1  183.49  5427.4   186.6
#Mann= 3 ,-1 , 0
  4674.7      .1       0  4991.8     .07       0  4997.8      .1       0
Bank Sta=4964.7,5035
XS Rating Curve= 0 ,0
Exp/Cntr=0.3,0.1

Type RM Length L Ch R = 1 ,34548   ,461,461,461
BEGIN DESCRIPTION:
MUSTANG CREEK 43.0
END DESCRIPTION:
XS GIS Cut Line= 3
      2315587.71     13294296.85      2315287.72     13294246.85
      2314837.72     13294296.85
#Sta/Elev= 30
  4677.8  186.82  4705.7   185.4  4718.3  184.01  4748.8  182.74  4779.2   180.3
  4832.4  177.86    4840  176.63  4860.3   175.8  4921.1  170.25    4949  166.19
  4984.4  164.72    4992  163.63  4999.1  161.19  5001.8  160.69  5005.1  161.19
  5012.1  163.39  5022.2  164.89  5112.7  169.04  5122.8  170.33  5173.1  172.74
  5193.2  174.38  5203.3  175.76  5273.7  178.29  5303.9   180.4    5314  182.35
  5334.1  181.91  5364.3  185.17  5384.4  185.53  5394.5   186.8  5434.7  189.01
#Mann= 3 ,-1 , 0
  4677.8      .1       0  4999.1     .07       0  5005.1      .1       0
Bank Sta=4984.4,5022.2
XS Rating Curve= 0 ,0
Exp/Cntr=0.3,0.1

Type RM Length L Ch R = 1 ,34087   ,435,435,435
BEGIN DESCRIPTION:
MUSTANG CREEK 42.0
END DESCRIPTION:
XS GIS Cut Line= 3
      2315787.72     13293796.85      2315237.72     13293796.85
      2314937.76     13293746.86
#Sta/Elev= 30
  4461.9  197.85  4521.9  193.27  4531.9  191.16  4551.9  188.96  4581.9  186.85
  4591.9  185.03  4621.9   183.5  4661.9  178.99  4691.9  178.28  4721.9  174.89
  4781.9  171.51  4931.9  164.93  4981.9  162.29  4988.9   159.9  4991.6   159.4
  4994.9   159.9  5001.9  160.58  5009.4  162.73  5032.2  164.81  5072.7   168.2
  5100.6  173.23  5105.7  171.71  5123.4  174.44  5140.3  175.78  5161.4  177.62
  5166.5  177.02  5184.2  178.72  5265.3   182.8  5275.5  182.07    5316  183.87
#Mann= 4 ,-1 , 0
  4461.9      .1       0  4988.9     .07       0  4994.9      .1       0
  5140.3     .05       0
Bank Sta=4931.9,5032.2
XS Rating Curve= 0 ,0
Exp/Cntr=0.3,0.1

Type RM Length L Ch R = 1 ,33652   ,480,480,480
BEGIN DESCRIPTION:
MUSTANG CREEK 41.0
END DESCRIPTION:
XS GIS Cut Line= 4
      2316199.36     13293385.61      2316169.38     13293419.26
      2315492.96     13293324.36      2314837.69     13293496.86
#Sta/Elev= 30
  4090.3   218.3  4106.2  218.74  4113.7  220.45  4138.7  220.37  4229.4  211.91
  4278.4   208.5  4328.2  207.36  4372.3  204.24    4471  197.02  4520.8  193.74
    4541     192  4547.3  190.33  4623.7   184.7    4695   178.7  4702.5  177.24
  4712.6  177.11  4761.3  172.89  4929.4  163.63  4937.6  162.42  4978.9  161.62
  4989.3  159.75  4996.6  159.52  4999.4  159.02  5002.6  159.52  5004.9  161.21
  5051.3  163.43  5061.7  164.96    5161  173.15  5309.8  177.62    5496   185.7
#Mann= 6 ,-1 , 0
  4090.3     .05       0  4229.4      .1       0  4372.3     .16       0
    4471      .1       0  4996.6     .07       0  5002.6      .1       0
Bank Sta=4929.4,5061.7
XS Rating Curve= 0 ,0
Exp/Cntr=0.3,0.1

Type RM Length L Ch R = 1 ,33172   ,453,453,453
BEGIN DESCRIPTION:
MUSTANG CREEK 40.0
END DESCRIPTION:
XS GIS Cut Line= 3
      2315337.74     13292696.83      2315137.72     13292946.85
       2314837.7     13293296.88
#Sta/Elev= 30
  4674.7  193.27  4677.9  193.27  4681.9  191.79  4688.3  191.72  4702.7  188.41
  4717.2  187.27  4738.8  183.74  4789.2  179.06    4810  176.16  4859.6  172.68
  4866.8  171.11  4880.4  169.87  4888.4  167.92  4894.8  167.86  4944.5  162.01
  4958.9  161.24    4999  158.09  5001.8  157.59    5005  158.09  5030.6  159.82
  5044.8  161.69  5073.4  162.43  5108.5  164.96  5157.9  166.56  5186.4  168.57
  5207.3  168.72  5250.1   171.1  5335.7  174.13  5420.2  178.99  5455.9  180.27
#Mann= 3 ,-1 , 0
  4674.7      .1       0    4999     .07       0    5005      .1       0
Bank Sta=4958.9,5044.8
XS Rating Curve= 0 ,0
Exp/Cntr=0.3,0.1

Type RM Length L Ch R = 1 ,32719   ,453,453,453
BEGIN DESCRIPTION:
MUSTANG CREEK 39.0
END DESCRIPTION:
XS GIS Cut Line= 3
      2314687.73     13292546.88      2314737.72     13292746.85
      2314687.72     13293246.84
#Sta/Elev= 30
  4794.8  180.39  4812.8  181.18    4818  179.36  4825.7  179.35    4854  180.69
  4870.1  179.19  4877.2  178.56  4900.4  172.91  4908.2     168  4918.5  166.54
  4936.5  161.04  4941.7  161.09  4949.4  158.91  4982.9  157.23  4990.6  154.53
  4995.3   154.2  4998.1   153.7  5001.3   154.2  5003.4   154.2    5011  157.59
  5040.7  159.22  5141.6  163.83  5181.8  164.29  5242.1  166.51  5249.7   167.7
  5342.6  171.62  5350.2  172.79  5402.9   174.8    5413  176.13  5503.4  181.01
#Mann= 5 ,-1 , 0
  4794.8      .1       0  4870.1     .16       0  4995.3     .07       0
  5001.3     .16       0  5040.7      .1       0
Bank Sta=4982.9,5011
XS Rating Curve= 0 ,0
Exp/Cntr=0.3,0.1

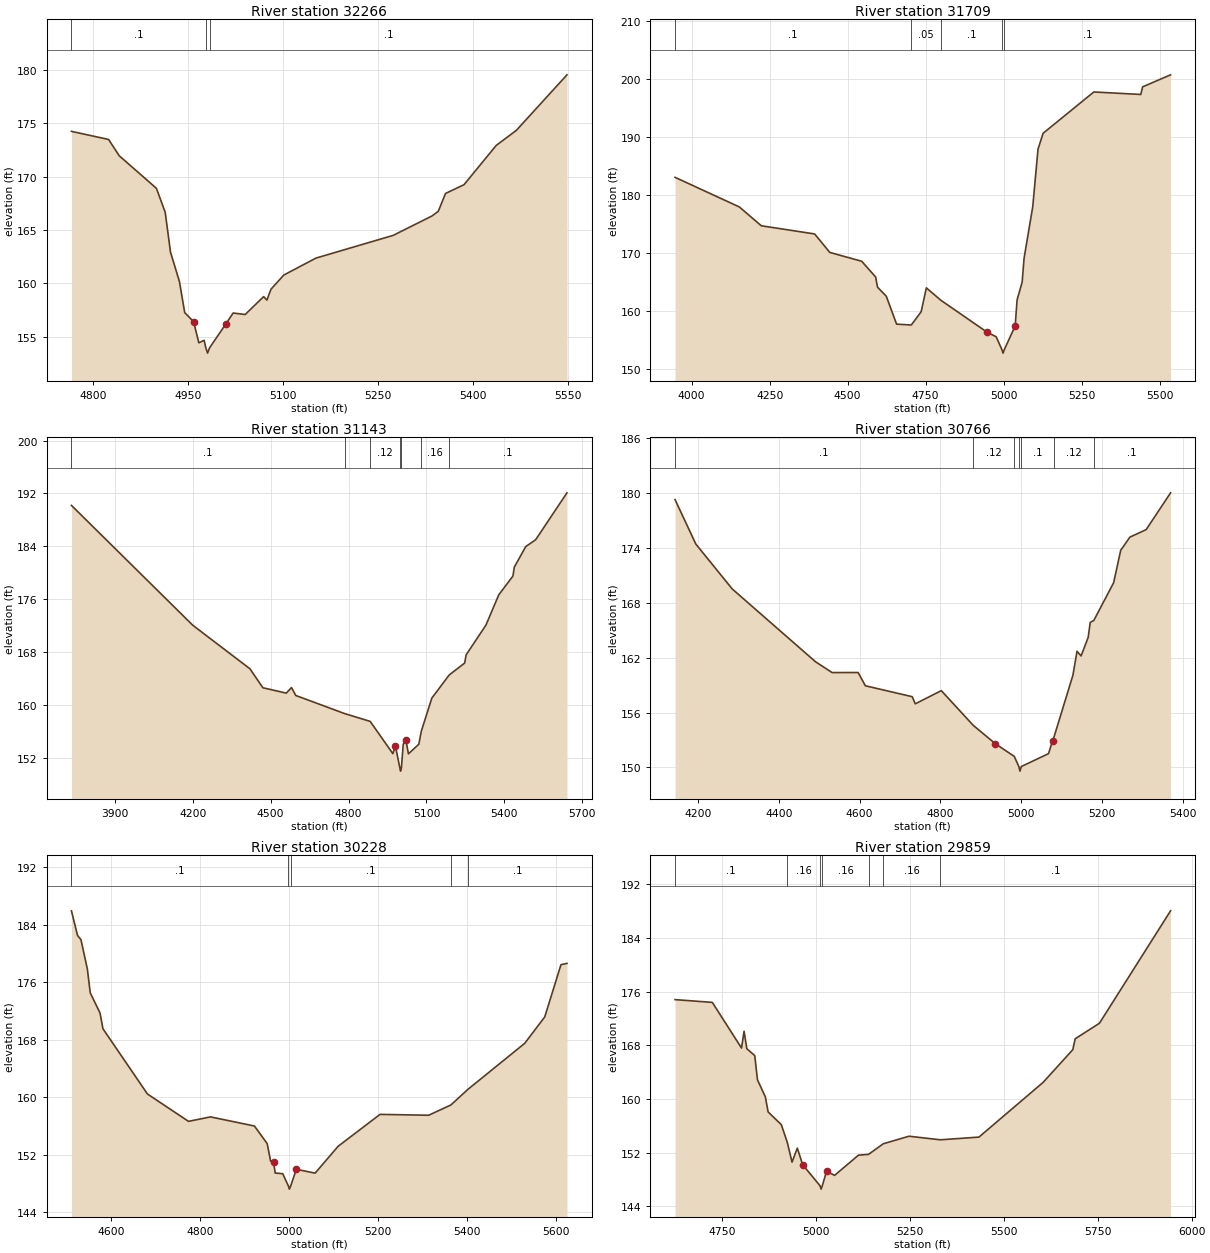
Type RM Length L Ch R = 1 ,32266   ,557,557,557
BEGIN DESCRIPTION:
MUSTANG CREEK 38.0
END DESCRIPTION:
XS GIS Cut Line= 3
      2314387.72     13292496.86      2314287.72     13292696.85
      2314387.72     13293246.84
#Sta/Elev= 30
    4766  174.25  4824.7  173.49  4841.5  171.96  4900.2  168.91  4914.1  166.66
  4922.5  162.91  4936.5  160.19  4944.9  157.26  4958.9  156.41  4967.2  154.43
  4975.6  154.66  4978.2  153.96    4981  153.46  4984.2  153.96  5009.9   156.2
  5021.4  157.22  5040.4  157.08  5069.6  158.76  5074.7  158.43  5081.1  159.45
  5101.4  160.78  5152.2  162.37  5274.2   164.5  5335.2  166.31  5345.3  166.75
  5356.8  168.43    5386  169.25  5436.8  172.93  5468.6  174.34  5548.6  179.55
#Mann= 3 ,-1 , 0
    4766      .1       0  4978.2     .07       0  4984.2      .1       0
Bank Sta=4958.9,5009.9
XS Rating Curve= 0 ,0
Exp/Cntr=0.3,0.1

Type RM Length L Ch R = 1 ,31709   ,566,566,566
BEGIN DESCRIPTION:
MUSTANG CREEK 37.0
END DESCRIPTION:
XS GIS Cut Line= 3
      2314802.61     13292190.56      2314306.24     13292244.71
      2313332.31     13292731.68
#Sta/Elev= 30
  3946.7  183.02  4152.8  177.92  4223.2  174.68  4394.2  173.27  4442.8  170.09
    4545  168.57  4589.7  165.86  4595.7  164.11  4623.7  162.56  4656.8  157.75
  4703.9   157.6  4735.5  159.88  4752.2  163.99  4799.1  161.84  4947.5  156.34
  4975.9  155.58  4995.2  153.26    4998  152.76  5001.2  153.26  5036.9  157.45
  5042.9   161.9  5059.3     165  5065.3  169.05  5093.2  177.97    5110  187.86
  5126.4   190.6  5288.9  197.71  5439.4  197.28  5445.4  198.59  5534.9  200.66
#Mann= 5 ,-1 , 0
  3946.7      .1       0  4703.9     .05       0  4799.1      .1       0
  4995.2     .07       0  5001.2      .1       0
Bank Sta=4947.5,5036.9
XS Rating Curve= 0 ,0
Exp/Cntr=0.3,0.1

Type RM Length L Ch R = 1 ,31143   ,377,377,377
BEGIN DESCRIPTION:
MUSTANG CREEK 36.0
END DESCRIPTION:
XS GIS Cut Line= 3
       2315064.4     13291910.78      2313557.14     13291964.93
      2313205.16      13291775.4
#Sta/Elev= 30
    3733   190.2    4200  172.06  4420.1  165.47  4470.2  162.59  4560.2  161.78
  4580.2  162.62  4596.9  161.42    4785  158.68  4883.3   157.5  4970.5  152.62
  4980.5  153.75  4997.5  150.47  5000.2  149.97  5003.5  150.47  5010.5  154.03
  5020.5  154.74  5030.5  152.59  5070.5  154.04  5080.1  156.01  5120.6  161.02
  5187.3  164.52    5247  166.33  5252.7  167.57  5328.9  172.07  5378.4  176.66
  5432.8  179.49  5438.4  180.87  5482.2  183.96  5520.4     185    5641   192.1
#Mann= 7 ,-1 , 0
    3733      .1       0    4785     .05       0  4883.3     .12       0
  4997.5     .07       0  5003.5     .12       0  5080.1     .16       0
  5187.3      .1       0
Bank Sta=4980.5,5020.5
XS Rating Curve= 0 ,0
Exp/Cntr=0.3,0.1

Type RM Length L Ch R = 1 ,30766   ,538,538,538
BEGIN DESCRIPTION:
MUSTANG CREEK 35.0
END DESCRIPTION:
XS GIS Cut Line= 3
      2314837.77     13291446.84      2314037.72     13291646.85
       2313637.7     13291596.85
#Sta/Elev= 30
  4142.5  179.25  4194.1  174.39  4284.3  169.49  4490.4  161.55  4531.7  160.36
  4596.1  160.37  4614.1  158.92  4730.1  157.73  4737.8  156.95  4802.2  158.39
  4881.6  154.59  4936.2  152.59    4983  151.21  4994.4   150.1  4997.2   149.6
  5000.4   150.1  5067.9  151.51    5078  152.93  5081.6  153.34  5128.4  160.08
  5138.5  162.69  5148.6  162.18  5166.2  164.21  5171.2  165.84  5180.2  166.06
  5229.2  170.17  5246.8  173.72  5269.5  175.15  5309.8  175.97  5370.3  179.99
#Mann= 7 ,-1 , 0
  4142.5      .1       0  4881.6     .12       0    4983      .1       0
  4994.4     .07       0  5000.4      .1       0  5081.6     .12       0
  5180.2      .1       0
Bank Sta=4936.2,5078
XS Rating Curve= 0 ,0
Exp/Cntr=0.3,0.1

Type RM Length L Ch R = 1 ,30228   ,369,369,369
BEGIN DESCRIPTION:
MUSTANG CREEK 34.0
END DESCRIPTION:
XS GIS Cut Line= 3
      2314587.73     13290846.85      2314237.72     13291146.85
      2313687.73     13291496.85
#Sta/Elev= 30
  4511.2  185.96  4524.9  182.53  4532.6  181.94  4546.9  177.87  4553.5  174.53
  4575.4  171.73    4582  169.53  4681.9  160.45  4774.1  156.64  4823.5  157.26
  4922.2  155.99  4950.8  153.54  4958.5   151.1  4965.1  150.93  4968.9  149.44
  4985.7  149.35    4998   147.7  5000.7   147.2    5004   147.7  5016.2  149.96
  5058.5  149.43  5110.2  153.17  5204.2  157.61  5313.4  157.49  5363.4  158.92
  5402.3  161.13  5529.3  167.51  5574.2  171.19  5610.6  178.46  5624.1  178.64
#Mann= 5 ,-1 , 0
  4511.2      .1       0    4998     .07       0    5004      .1       0
  5363.4     .16       0  5402.3      .1       0
Bank Sta=4965.1,5016.2
XS Rating Curve= 0 ,0
Exp/Cntr=0.3,0.1

Type RM Length L Ch R = 1 ,29859   ,567,567,567
BEGIN DESCRIPTION:
MUSTANG CREEK 33.0
END DESCRIPTION:
XS GIS Cut Line= 3
       2314321.1     13290620.35      2313839.31     13291067.42
      2313311.28      13291465.6
#Sta/Elev= 30
  4625.3  174.81  4724.5   174.4  4802.2   167.6    4809   170.1  4816.4  167.49
  4837.4  166.48  4844.7  162.86  4865.7  160.32    4873  158.08  4908.2  156.18
  4924.4  153.47  4936.6   150.6  4950.7  152.69  4964.9  150.22  5011.2  147.08
    5014  146.58  5017.2  147.08  5028.4  149.25  5049.9  148.63  5113.4  151.64
  5140.3  151.76  5179.5  153.34  5247.8  154.46  5331.2  153.93    5434  154.33
  5604.7  162.48  5683.8  167.36  5690.1  168.98  5754.6  171.29  5943.9  188.04
#Mann= 7 ,-1 , 0
  4625.3      .1       0  4924.4     .16       0  5011.2     .07       0
  5017.2     .16       0  5140.3      .1       0  5179.5     .16       0
  5331.2      .1       0
Bank Sta=4964.9,5028.4
XS Rating Curve= 0 ,0
Exp/Cntr=0.3,0.1

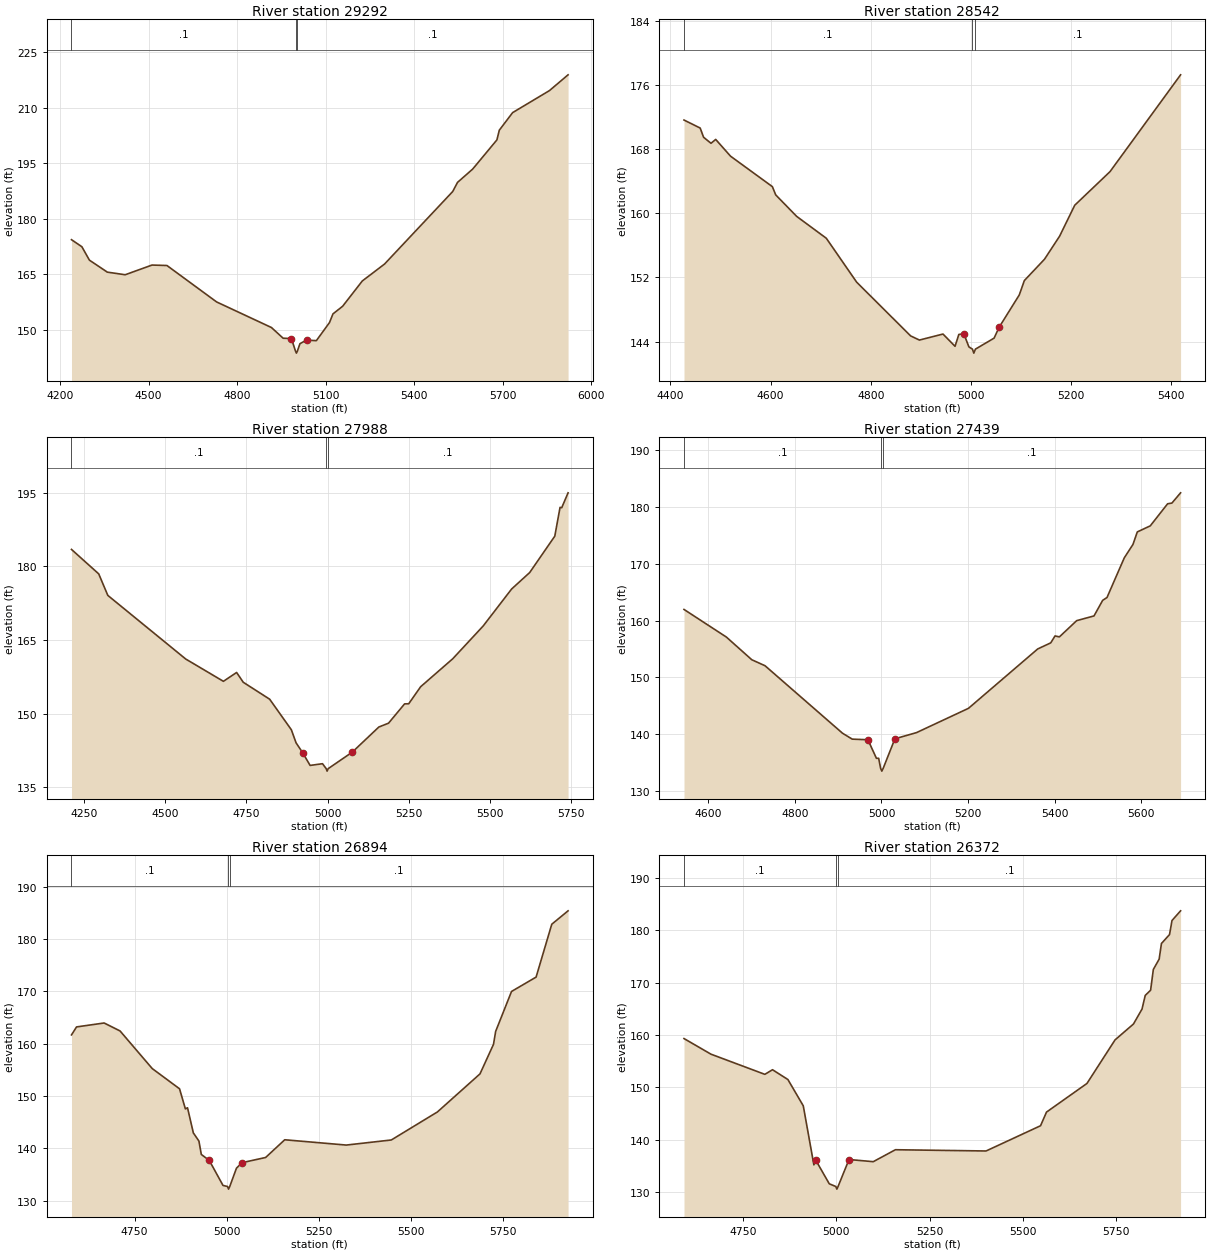
Type RM Length L Ch R = 1 ,29292   ,750,750,750
BEGIN DESCRIPTION:
MUSTANG CREEK 32.0
END DESCRIPTION:
XS GIS Cut Line= 3
      2314237.75     13290596.85      2313865.35     13290650.75
      2312690.94     13291222.79
#Sta/Elev= 30
  4238.9  174.39  4274.1  172.48  4299.6  168.86  4360.2  165.62  4420.8  164.91
  4511.7  167.53  4562.3  167.41  4730.6  157.56  4916.5  150.64    4956  147.75
  4984.1  147.66  4998.1  144.22  5000.9  143.72  5004.1  144.22    5013  146.27
  5035.2  147.24  5068.6  147.09  5113.1  151.98  5124.9  154.33  5157.6  156.39
  5224.3  163.23  5299.7  167.81  5530.7  187.42  5546.9  189.88  5598.3  193.48
  5680.4  201.37  5688.5  203.99  5733.6  208.74  5858.3  214.69  5921.5  218.96
#Mann= 3 ,-1 , 0
  4238.9      .1       0  4998.1     .07       0  5004.1      .1       0
Bank Sta=4984.1,5035.2
XS Rating Curve= 0 ,0
Exp/Cntr=0.3,0.1

Type RM Length L Ch R = 1 ,28542   ,554,554,554
BEGIN DESCRIPTION:
MUSTANG CREEK 31.0
END DESCRIPTION:
XS GIS Cut Line= 3
      2314287.74     13290346.86      2313787.72     13290146.85
      2313337.73     13290096.86
#Sta/Elev= 30
  4427.2  171.64  4459.5  170.64  4466.3  169.49  4481.1  168.74  4490.5  169.22
  4520.1  167.13  4603.6  163.33  4610.3   162.3  4652.1  159.62  4711.3  156.89
  4771.9  151.41  4879.6  144.71  4897.1  144.19  4944.2  144.94  4968.3  143.41
  4975.8  144.89  4985.9  144.97  4995.9  143.34    5003  143.06  5005.7  142.56
    5009  143.06  5046.2  144.43  5056.3  145.79  5096.5  149.82  5106.6  151.61
  5146.8  154.27    5177  157.15  5207.2  161.01  5277.6   165.2  5418.5  177.28
#Mann= 3 ,-1 , 0
  4427.2      .1       0    5003     .07       0    5009      .1       0
Bank Sta=4985.9,5056.3
XS Rating Curve= 0 ,0
Exp/Cntr=0.3,0.1

Type RM Length L Ch R = 1 ,27988   ,549,549,549
BEGIN DESCRIPTION:
MUSTANG CREEK 30.0
END DESCRIPTION:
XS GIS Cut Line= 3
      2314837.73     13289846.86      2314037.72     13289696.85
      2313337.76     13289546.86
#Sta/Elev= 30
    4211  183.42  4294.9  178.44  4322.9  174.06  4562.9  161.11    4679  156.57
  4719.7  158.37  4740.1  156.38  4821.5  152.93  4888.4   146.7  4902.9  144.04
  4923.2  142.04  4946.1  139.45  4984.3   139.8  4995.7  138.79  4998.4  138.29
  5001.7  138.79  5076.1  142.16  5157.9  147.27  5187.7  148.05  5237.2  151.98
  5249.9     152  5286.6  155.47  5385.5  161.16  5479.2  167.83    5567  175.37
  5622.4   178.7  5699.9  186.12  5716.1  191.98  5721.2  191.91  5740.8  194.94
#Mann= 3 ,-1 , 0
    4211      .1       0  4995.7     .07       0  5001.7      .1       0
Bank Sta=4923.2,5076.1
XS Rating Curve= 0 ,0
Exp/Cntr=0.3,0.1

Type RM Length L Ch R = 1 ,27439   ,545,545,545
BEGIN DESCRIPTION:
MUSTANG CREEK 29.0
END DESCRIPTION:
XS GIS Cut Line= 3
      2314637.75     13289396.87      2314237.72     13289196.85
      2313537.77     13289196.85
#Sta/Elev= 30
  4543.8  161.96  4641.7   157.1  4700.4  153.11  4731.1  152.05    4910  140.18
  4932.4  139.14  4968.7  139.03  4988.3  135.77  4993.5  135.77    4998  134.01
  5000.8  133.51    5004  134.01    5031   139.2    5081  140.29    5201  144.56
    5361  155.01    5391  156.08    5401   157.3    5411  157.13    5451  159.99
    5491  160.82    5511  163.56    5521  164.06    5561  171.05    5581   173.4
    5591   175.6    5621  176.67    5661  180.55    5671  180.68    5691  182.48
#Mann= 3 ,-1 , 0
  4543.8      .1       0    4998     .07       0    5004      .1       0
Bank Sta=4968.7,5031
XS Rating Curve= 0 ,0
Exp/Cntr=0.3,0.1

Type RM Length L Ch R = 1 ,26894   ,522,522,522
BEGIN DESCRIPTION:
MUSTANG CREEK 28.0
END DESCRIPTION:
XS GIS Cut Line= 3
      2314637.73     13288446.85      2314287.72     13288646.85
      2313487.74     13289146.84
#Sta/Elev= 30
  4578.8  161.68  4592.5   163.2  4667.3  163.95  4710.5  162.43  4797.6  155.26
  4871.8  151.39  4887.6  147.55  4893.4  147.77  4909.2  142.97  4924.3  141.42
  4930.8  138.86  4952.4  137.72  4989.6  132.95  5001.9  132.74  5004.7  132.24
  5007.9  132.74  5026.1  136.23  5040.9  137.28  5105.2  138.28    5157  141.66
  5323.9  140.65    5446  141.62    5571  146.97  5686.5  154.24  5723.1  159.88
    5729  162.36    5772  169.97  5838.6  172.71  5881.1   182.8  5925.3  185.36
#Mann= 3 ,-1 , 0
  4578.8      .1       0  5001.9     .07       0  5007.9      .1       0
Bank Sta=4952.4,5040.9
XS Rating Curve= 0 ,0
Exp/Cntr=0.3,0.1

Type RM Length L Ch R = 1 ,26372   ,552,552,552
BEGIN DESCRIPTION:
MUSTANG CREEK 27.0
END DESCRIPTION:
XS GIS Cut Line= 3
      2314437.73     13288296.86      2314037.72     13288196.85
      2313237.72     13288646.86
#Sta/Elev= 30
    4592  159.34  4664.2  156.36  4808.5  152.51  4829.1  153.39  4870.3  151.52
  4911.5   146.5  4939.9  135.23    4945  136.12  4981.1  131.62  4998.7   131.1
  5001.5   130.6  5004.7   131.1    5034  136.25    5099  135.84  5158.3  138.12
  5401.1  137.88  5547.1   142.7    5563   145.3  5671.4  150.77  5746.6  159.08
    5796  162.12  5818.9  164.97  5827.5  167.57  5841.9  168.57  5849.2  172.53
  5864.8   174.5  5870.9  177.48  5892.6  179.19  5899.2  181.87  5922.2  183.72
#Mann= 3 ,-1 , 0
    4592      .1       0  4998.7     .07       0  5004.7      .1       0
Bank Sta=4945,5034
XS Rating Curve= 0 ,0
Exp/Cntr=0.3,0.1

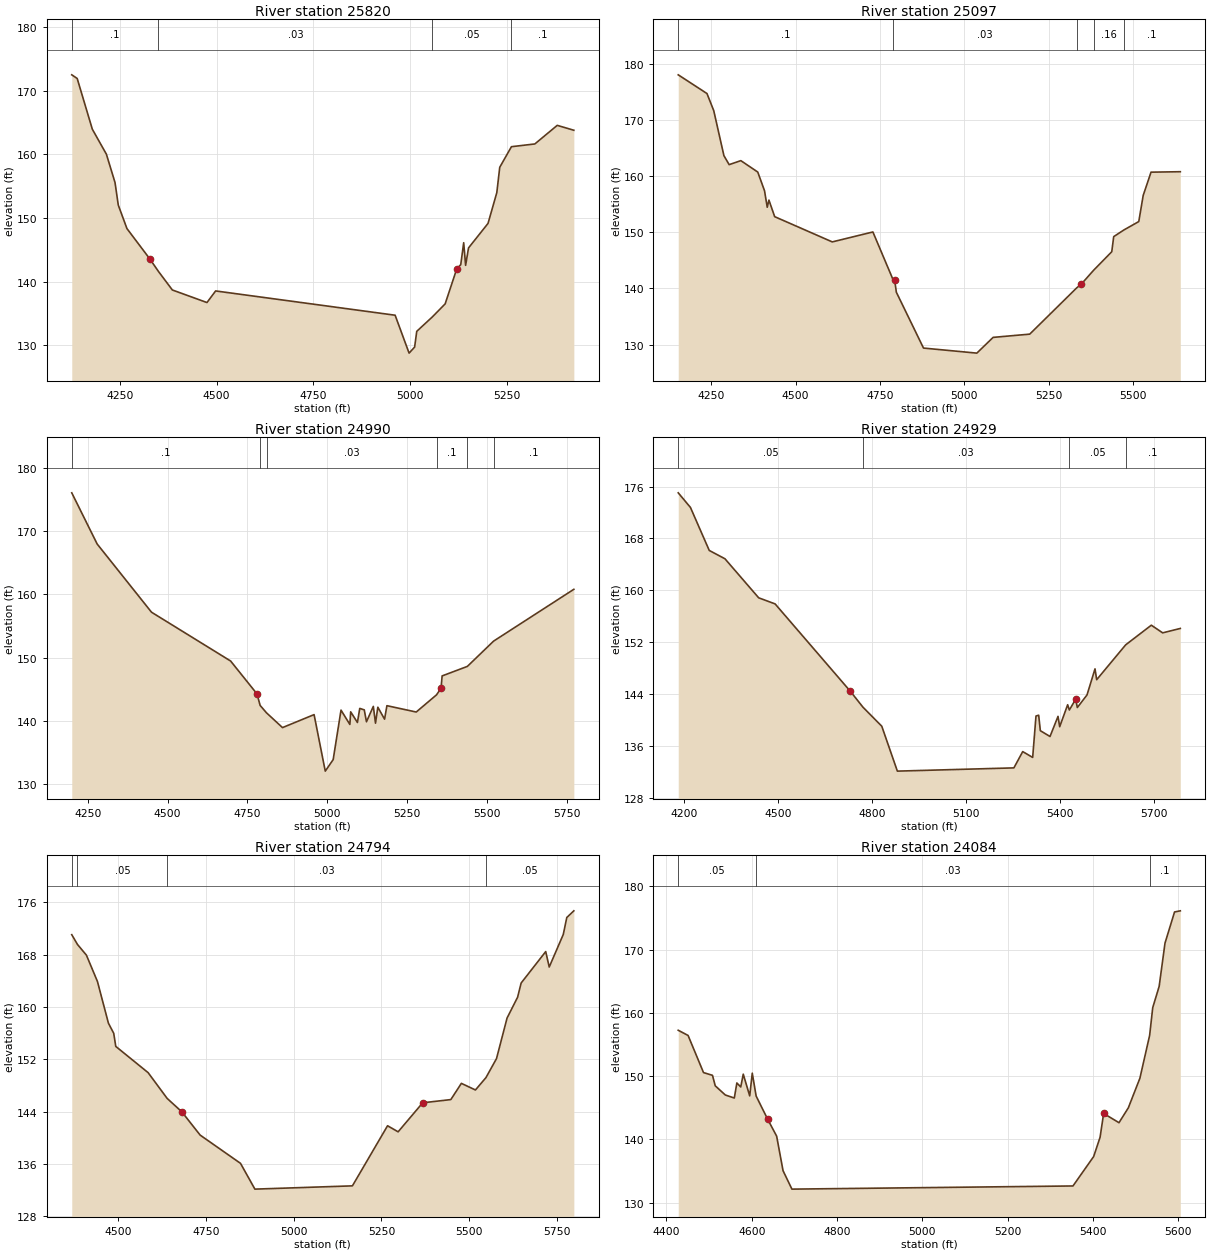
Type RM Length L Ch R = 1 ,25820   ,723,723,723
BEGIN DESCRIPTION:
MUSTANG CREEK 26.0
END DESCRIPTION:
XS GIS Cut Line= 3
      2314537.73     13287346.85      2313737.72     13287746.85
      2313337.67     13287796.86
#Sta/Elev= 30
  4125.8  172.47  4139.8   171.9  4178.9  163.94  4215.3  160.01  4237.6  155.56
    4246  152.03  4268.4  148.34  4327.1  143.61  4349.4  141.65  4385.8   138.7
  4475.2  136.73  4497.6  138.55  4961.5  134.74  4997.6  128.79  5011.9  129.74
  5017.4  132.21    5058  134.49  5090.8  136.52    5121  142.05  5131.1  142.67
  5138.7  146.12  5143.7  142.57  5151.2   145.3  5201.6  149.15  5224.3  153.98
  5231.9  157.96  5262.1  161.19  5322.6  161.62  5380.5  164.54  5423.4  163.77
#Mann= 4 ,-1 , 0
  4125.8      .1       0  4349.4     .03       0    5058     .05       0
  5262.1      .1       0
Bank Sta=4327.1,5121
XS Rating Curve= 0 ,0
Exp/Cntr=0.3,0.1

Type RM Length L Ch R = 1 ,25097   ,107,107,107
BEGIN DESCRIPTION:
Mapping XS 525aa2de
END DESCRIPTION:
XS GIS Cut Line= 4
      2314652.58     13287024.97      2314013.73     13286969.42
      2313777.62     13287031.92      2313472.64     13287551.76
#Sta/Elev= 30
  4152.3  177.99  4237.5  174.66  4257.6  171.61  4287.7  163.61  4303.2  162.01
  4337.9  162.72    4388  160.69  4408.1  157.36  4416.1  154.43  4421.1   155.7
  4438.2  152.75  4608.9  148.26  4729.3  150.03    4789  141.55  4793.6  141.55
  4798.8  139.31  4879.3  129.37  5037.4  128.47  5085.6  131.27  5194.2  131.85
  5333.4  140.08  5347.3  140.76  5383.6  143.22  5437.3  146.51  5443.1   149.2
  5473.4  150.39  5517.4  151.88  5530.5  156.53  5553.7  160.67  5640.5  160.75
#Mann= 5 ,-1 , 0
  4152.3      .1       0    4789     .03       0  5333.4     .05       0
  5383.6     .16       0  5473.4      .1       0
Bank Sta=4793.6,5347.3
XS Rating Curve= 0 ,0
Exp/Cntr=0.3,0.1

Type RM Length L Ch R = 1 ,24990   ,61,61,61
BEGIN DESCRIPTION:
MUSTANG CREEK 25.0
END DESCRIPTION:
XS GIS Cut Line= 5
      2314597.09     13286920.71      2313861.01     13286892.94
      2313736.01     13286941.55       2313538.1     13287153.35
       2313437.5     13287552.26
#Sta/Elev= 30
  4199.9  176.03  4279.3  167.96  4449.5  157.19  4697.3  149.48  4779.7   144.3
  4789.7  142.47  4809.7   141.3  4859.7  138.97  4958.6  141.02  4993.6   132.1
  5018.4  133.92  5042.9  141.73  5070.6  139.47  5073.2  141.46  5094.3  139.78
  5101.6     142  5115.7  141.77  5122.6  139.89  5144.1  142.32  5150.9  139.67
  5158.2  142.19  5179.3   140.3  5186.6  142.43  5278.4  141.43  5341.9  144.14
  5356.1  145.18  5359.5  147.13  5438.5  148.63  5520.6  152.62  5771.9   160.8
#Mann= 6 ,-1 , 0
  4199.9      .1       0  4789.7     .07       0  4809.7     .03       0
  5341.9      .1       0  5438.5     .16       0  5520.6      .1       0
Bank Sta=4779.7,5356.1
XS Rating Curve= 0 ,0
Exp/Cntr=0.3,0.1

Type RM Length L Ch R = 1 ,24929   ,135,135,135
BEGIN DESCRIPTION:
Mapping XS 003c418d
END DESCRIPTION:
XS GIS Cut Line= 4
       2314586.6     13286868.72      2313840.12     13286820.11
      2313555.39     13287004.14       2313382.6     13287491.43
#Sta/Elev= 30
  4180.6  175.03  4219.6  172.78  4279.7  166.15  4329.8  164.87  4437.6  158.85
  4490.1  157.91  4730.6  144.44  4770.7     142  4830.9  139.06  4880.7  132.14
    5253  132.64  5281.2  135.15    5313  134.25  5323.6  140.63  5332.2  140.76
  5337.5  138.37  5368.4  137.48    5394  140.58  5399.3  138.98  5424.8  142.37
  5430.2  141.56  5450.4  143.22  5455.7  141.94  5486.6  143.88  5512.2   147.9
  5517.5  146.23  5610.1   151.6  5692.1  154.63  5728.3  153.45  5784.7  154.13
#Mann= 4 ,-1 , 0
  4180.6     .05       0  4770.7     .03       0  5430.2     .05       0
  5610.1      .1       0
Bank Sta=4730.6,5450.4
XS Rating Curve= 0 ,0
Exp/Cntr=0.3,0.1

Type RM Length L Ch R = 1 ,24794   ,710,710,710
BEGIN DESCRIPTION:
MUSTANG CREEK 24.0
END DESCRIPTION:
XS GIS Cut Line= 3
      2314337.68     13286546.87      2313687.72     13286746.85
      2312937.71     13286796.86
#Sta/Elev= 30
  4366.9  171.04  4383.2  169.55  4408.7  167.91  4440.1  163.89  4471.5   157.5
  4486.5  155.97  4492.4  153.96  4584.6  149.95  4638.9  146.01  4680.7  143.96
    4733   140.4  4848.1  136.08  4889.1  132.14  5167.2  132.64  5267.4  141.83
  5297.5   140.9  5367.6  145.34  5447.8  145.83  5477.9  148.31    5518   147.3
    5548  149.19  5578.1   152.1  5608.2   158.3  5638.2  161.48  5648.3  163.65
  5718.4  168.46  5728.4   166.1  5768.5  171.08  5778.5  173.67  5798.6  174.69
#Mann= 4 ,-1 , 0
  4366.9      .1       0  4383.2     .05       0  4638.9     .03       0
    5548     .05       0
Bank Sta=4680.7,5367.6
XS Rating Curve= 0 ,0
Exp/Cntr=0.3,0.1

Type RM Length L Ch R = 1 ,24084   ,594,594,594
BEGIN DESCRIPTION:
MUSTANG CREEK 23.0
END DESCRIPTION:
XS GIS Cut Line= 2
      2313586.72     13285764.45      2312937.73     13286746.83
#Sta/Elev= 30
  4427.6  157.25  4450.7  156.43  4486.9  150.56  4507.9  150.13  4514.4  148.47
    4538  147.02  4559.1  146.54  4565.1  148.92  4574.2  148.29  4580.1  150.31
  4595.2  146.88  4601.2  150.47  4610.3  146.85  4637.3  143.19  4658.4  140.51
  4673.4  135.05  4694.2  132.14  5353.3  132.64  5401.8  137.29  5416.9  140.35
  5425.2   144.1  5461.2  142.64  5483.1  144.99  5510.2  149.66  5533.1  156.45
  5540.3  160.82  5555.4  164.19  5569.1  171.03  5591.5  175.95    5605  176.13
#Mann= 3 ,-1 , 0
  4427.6     .05       0  4610.3     .03       0  5533.1      .1       0
Bank Sta=4637.3,5425.2
XS Rating Curve= 0 ,0
Exp/Cntr=0.3,0.1

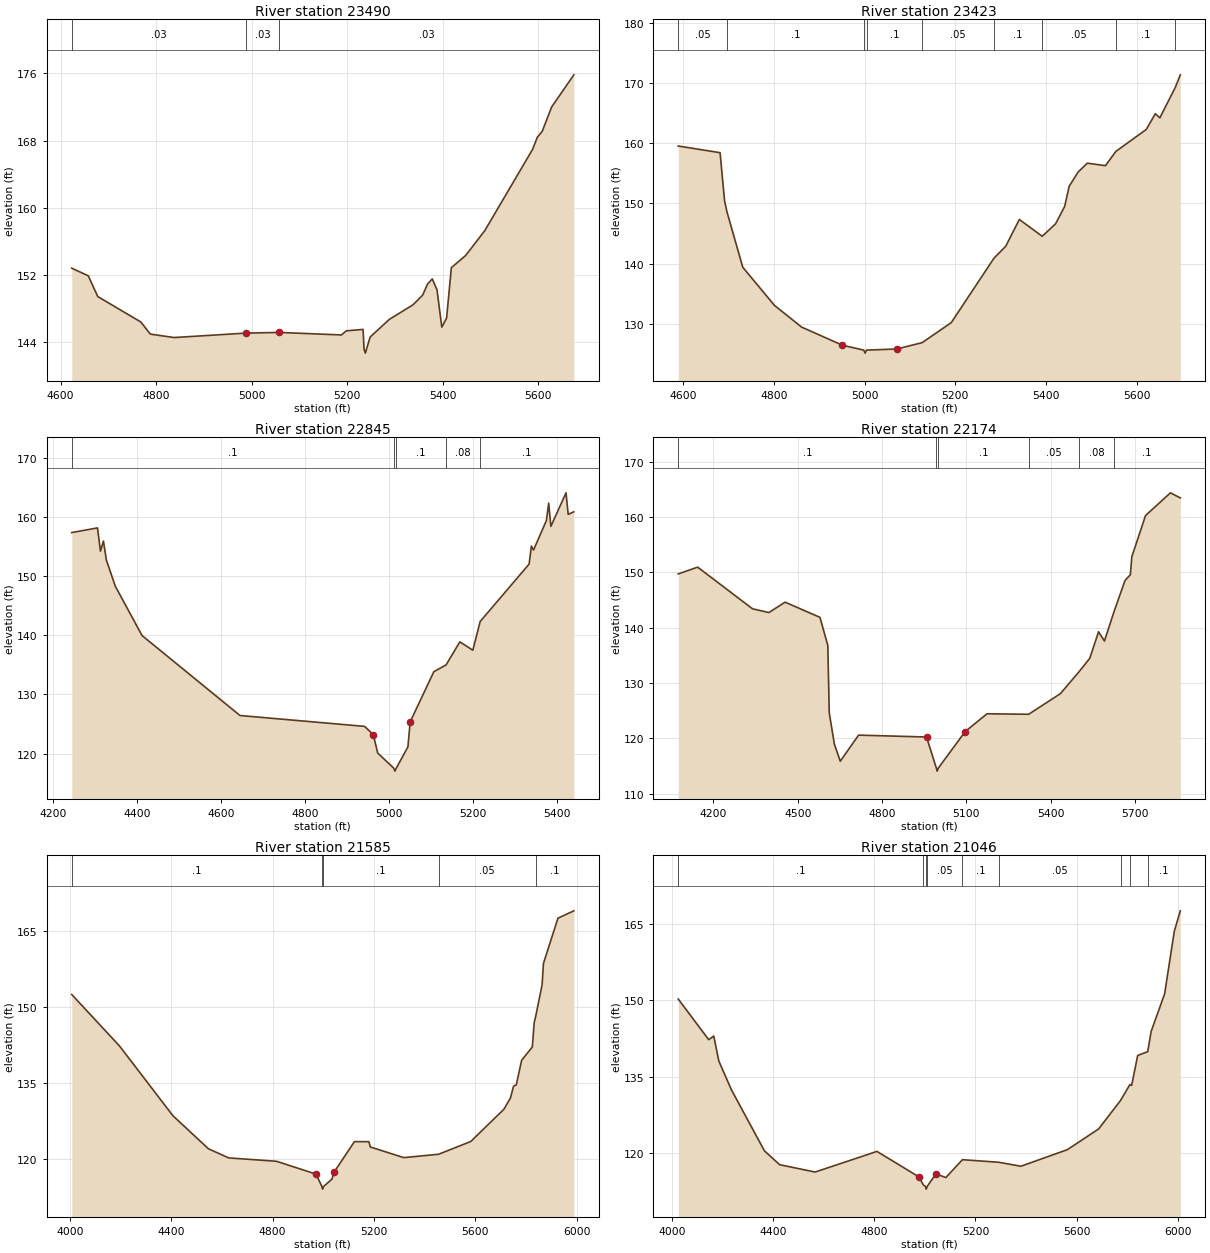
Type RM Length L Ch R = 1 ,23490   ,67,67,67
BEGIN DESCRIPTION:
MUSTANG CREEK 22.0
END DESCRIPTION:
XS GIS Cut Line= 2
      2313392.23     13285781.83      2312341.37     13285764.65
#Sta/Elev= 30
  4623.3  152.76  4657.8  151.85  4677.8  149.37  4767.8  146.34  4787.8  144.89
  4837.8  144.48  4987.9  145.01  5057.9  145.09  5187.9  144.79  5197.9  145.28
  5233.1  145.45  5235.1  143.12  5237.8  142.62  5247.9  144.54  5287.9  146.64
  5337.9   148.4  5357.9  149.55  5367.9  150.85  5377.9  151.48  5387.9  150.17
  5397.9  145.72  5407.9   146.8  5417.9  152.82  5447.9  154.28  5487.9  157.24
  5587.9  166.94  5597.9  168.39  5607.9  169.07  5627.9  172.01  5674.3  175.84
#Mann= 3 , 0 , 0
  4623.3     .03       0  4987.9     .03       0  5057.9     .03       0
Bank Sta=4987.9,5057.9
XS Rating Curve= 0 ,0
Exp/Cntr=0.3,0.1

Type RM Length L Ch R = 1 ,23423   ,578,578,578
BEGIN DESCRIPTION:
MUSTANG CREEK 21.0
END DESCRIPTION:
XS GIS Cut Line= 2
      2313420.04     13285712.38      2312312.59     13285701.97
#Sta/Elev= 30
  4588.9  159.55  4681.2  158.44  4691.2  150.39  4696.5  148.58  4731.2  139.41
  4801.2  133.06  4861.2  129.45  4951.2  126.44  4998.2  125.63    5001  125.13
  5004.2  125.63  5071.2  125.82  5126.9  126.87  5191.2   130.2  5285.5  140.92
  5311.3  142.89  5341.3  147.34  5391.8  144.55  5421.3  146.62  5441.3  149.51
  5451.3  152.87  5471.3  155.25  5491.3   156.7  5531.3  156.28  5554.3  158.66
  5621.3   162.3  5641.3  164.92  5651.3  164.23  5685.4   169.3  5696.4  171.38
#Mann= 9 ,-1 , 0
  4588.9     .05       0  4696.5      .1       0  4998.2     .07       0
  5004.2      .1       0  5126.9     .05       0  5285.5      .1       0
  5391.8     .05       0  5554.3      .1       0  5685.4     .05       0
Bank Sta=4951.2,5071.2
XS Rating Curve= 0 ,0
Exp/Cntr=0.3,0.1

Type RM Length L Ch R = 1 ,22845   ,671,671,671
BEGIN DESCRIPTION:
MUSTANG CREEK 20.0
END DESCRIPTION:
XS GIS Cut Line= 3
      2313454.77     13285646.42      2313027.68     13285233.22
      2312444.39     13285087.39
#Sta/Elev= 30
  4245.2  157.43  4306.5  158.22  4313.5  154.28  4320.6  155.99  4327.6  152.77
  4348.9  148.34  4412.5  139.99  4645.8  126.44  4942.5   124.6  4963.1  123.19
  4973.7  120.09  5011.9  117.52  5014.6  117.02  5017.9  117.52  5045.6  121.12
    5051  125.36  5107.4  133.87  5136.6  135.02  5169.3  138.92  5200.2   137.5
  5217.6  142.36  5334.2  152.09  5339.6  155.14  5344.7  154.47  5375.4  159.47
  5380.8  162.42    5386  158.48  5422.1  164.16  5427.2  160.51  5440.7  160.95
#Mann= 5 ,-1 , 0
  4245.2      .1       0  5011.9     .07       0  5017.9      .1       0
  5136.6     .08       0  5217.6      .1       0
Bank Sta=4963.1,5051
XS Rating Curve= 0 ,0
Exp/Cntr=0.3,0.1

Type RM Length L Ch R = 1 ,22174   ,589,589,589
BEGIN DESCRIPTION:
MUSTANG CREEK 19.0
END DESCRIPTION:
XS GIS Cut Line= 3
       2314048.5     13284243.64      2313637.72     13284496.85
       2312389.2     13284871.98
#Sta/Elev= 30
  4074.8  149.74    4144  150.96  4339.1  143.43  4397.1  142.75    4455  144.63
  4579.1  141.88  4606.9  136.81  4612.1   124.6  4630.4  118.95  4651.3  115.87
  4716.5  120.59  4958.2  120.25  4993.4  114.58  4996.2  114.08  4999.4  114.58
  5095.6  121.23  5173.4  124.45  5321.5  124.36  5434.4  128.09  5501.2  132.08
  5538.9  134.48  5570.2  139.28  5591.1  137.61  5625.5  142.96  5664.2  148.54
  5683.3   149.6  5688.5  152.83  5737.3  160.29  5825.9   164.4    5861  163.48
#Mann= 6 ,-1 , 0
  4074.8      .1       0  4993.4     .07       0  4999.4      .1       0
  5321.5     .05       0  5501.2     .08       0  5625.5      .1       0
#XS Ineff= 1 ,-1
 4589.06 4717.19  120.57
Permanent Ineff=
       F
Bank Sta=4958.2,5095.6
XS Rating Curve= 0 ,0
Exp/Cntr=0.3,0.1

Type RM Length L Ch R = 1 ,21585   ,539,539,539
BEGIN DESCRIPTION:
MUSTANG CREEK 18.0
END DESCRIPTION:
XS GIS Cut Line= 3
      2314206.01     13284023.68      2313461.22     13283982.02
       2312292.8     13284381.87
#Sta/Elev= 30
  4007.6  152.49  4196.2  142.32  4406.5  128.58  4546.7  122.05  4626.9  120.24
  4815.1  119.58  4971.6  117.04  4994.6  114.58  4997.4  114.08  5000.6  114.58
  5034.2  116.06  5042.6  117.43  5122.8  123.46    5180  123.44  5185.4   122.4
  5317.4   120.3  5454.9  120.96  5581.7  123.48  5712.1  129.82  5738.1  132.02
  5750.8  134.41  5761.3  134.64  5782.5  139.51  5824.8  142.14    5832  146.95
  5837.6  148.07  5863.3  154.43  5868.6  158.63  5925.9  167.56  5988.5  169.01
#Mann= 5 ,-1 , 0
  4007.6      .1       0  4994.6     .07       0  5000.6      .1       0
  5454.9     .05       0  5837.6      .1       0
Bank Sta=4971.6,5042.6
XS Rating Curve= 0 ,0
Exp/Cntr=0.3,0.1

Type RM Length L Ch R = 1 ,21046   ,282,282,282
BEGIN DESCRIPTION:
MUSTANG CREEK 17.0
END DESCRIPTION:
XS GIS Cut Line= 3
      2314158.05     13283485.14      2313373.37     13283457.36
      2312265.72      13283915.7
#Sta/Elev= 30
  4025.6  150.25    4146  142.26    4166  142.97    4186  138.06  4236.1  132.36
  4366.1   120.4  4426.2  117.67  4566.3  116.22  4810.8  120.28  4976.6  115.27
  4993.8  113.72  5002.9  113.36  5005.7  112.86  5008.9  113.36  5044.2  115.87
    5083  115.13  5148.4  118.65  5292.3  118.14  5379.6  117.36  5563.6  120.63
  5686.8   124.7  5773.2  130.29  5810.6  133.44  5817.2  133.26  5841.1  139.15
  5880.8   139.9  5894.3  143.88  5947.5  151.26  5985.7  163.57  6009.5   167.6
#Mann= 9 ,-1 , 0
  4025.6      .1       0  4993.8     .05       0  5002.9     .03       0
  5008.9     .05       0  5148.4      .1       0  5292.3     .05       0
  5773.2     .08       0  5810.6     .05       0  5880.8      .1       0
Bank Sta=4976.6,5044.2
XS Rating Curve= 0 ,0
Exp/Cntr=0.3,0.1