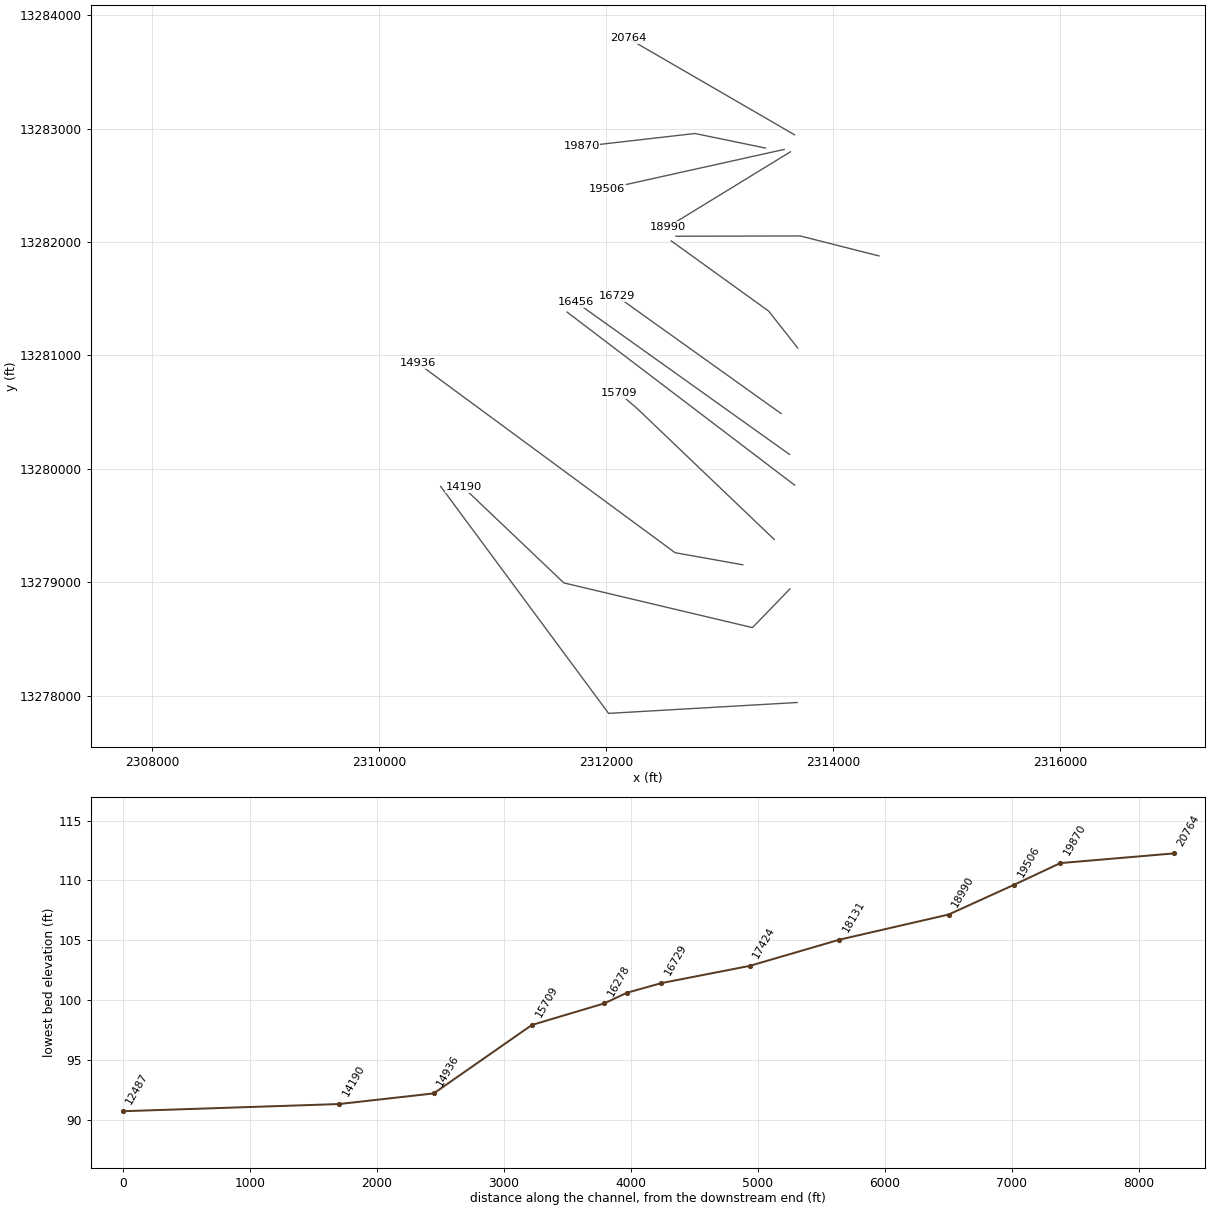
HEC-RAS study MUSTANG CREEK.prj: MUSTANG CREEK Base Level Engineering

--- MUSTANG CREEK.g01 (geometry) --- (continued)

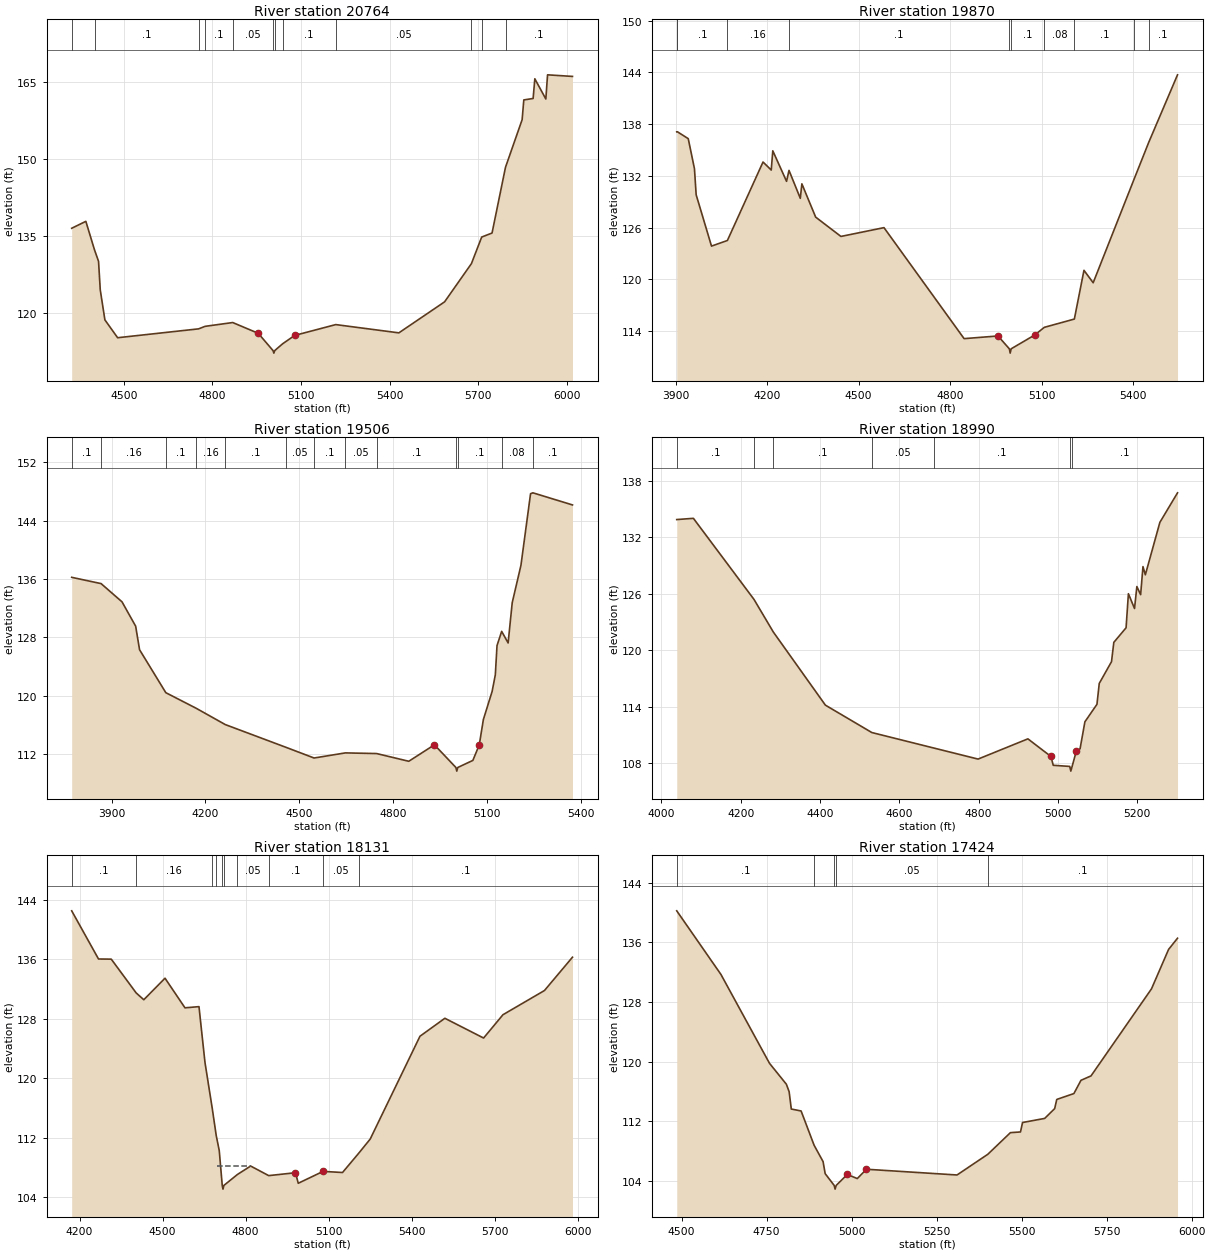
Type RM Length L Ch R = 1 ,20764   ,894,894,894
BEGIN DESCRIPTION:
MUSTANG CREEK 16.0
END DESCRIPTION:
XS GIS Cut Line= 2
       2313660.9     13282945.98      2312193.91     13283796.67
#Sta/Elev= 30
  4323.8  136.59  4371.7  137.94    4401  132.39  4414.7  130.14  4420.5  124.58
  4436.2  118.74  4479.3  115.26  4753.6  116.99  4775.6  117.48  4869.1  118.22
  4955.5  116.12  5005.5  112.76  5008.3  112.26  5011.5  112.76  5037.8  114.07
  5078.9  115.71    5218  117.82  5431.7  116.21  5586.5  122.25  5677.4   129.7
  5712.2  134.88  5747.2  135.66  5792.8  148.48  5849.1  157.75  5854.8   161.6
  5886.3  161.88  5892.1  165.72  5929.4  161.78  5935.2  166.49  6019.6  166.18
#Mann= 12 ,-1 , 0
  4323.8     .16       0    4401      .1       0  4753.6     .05       0
  4775.6      .1       0  4869.1     .05       0  5005.5     .03       0
  5011.5     .05       0  5037.8      .1       0    5218     .05       0
  5677.4      .1       0  5712.2     .08       0  5792.8      .1       0
Bank Sta=4955.5,5078.9
XS Rating Curve= 0 ,0
Exp/Cntr=0.3,0.1

Type RM Length L Ch R = 1 ,19870   ,364,364,364
BEGIN DESCRIPTION:
MUSTANG CREEK 15.0
END DESCRIPTION:
XS GIS Cut Line= 3
      2313404.64     13282828.89      2312783.09     13282957.36
      2311783.12     13282842.78
#Sta/Elev= 30
    3904  137.11    3906  137.12  3941.7  136.32  3962.1  132.83  3967.6  129.82
  4017.9  123.86    4070  124.51  4186.8  133.61  4213.7  132.68  4218.8  134.91
  4263.9  131.37  4271.9  132.64    4309   129.4  4314.1  131.08  4359.3  127.22
  4442.1  124.98  4583.2     126  4845.8  113.13  4956.8  113.44    4994  111.95
  4996.8  111.45    5000  111.95  5077.6  113.56  5108.6  114.44  5207.1   115.4
  5238.6  121.05  5268.8  119.61  5404.1  131.73    5451   135.9  5545.2  143.72
#Mann= 10 ,-1 , 0
    3904     .16       0    3906      .1       0    4070     .16       0
  4271.9      .1       0    4994     .07       0    5000      .1       0
  5108.6     .08       0  5207.1      .1       0  5404.1     .16       0
    5451      .1       0
Bank Sta=4956.8,5077.6
XS Rating Curve= 0 ,0
Exp/Cntr=0.3,0.1

Type RM Length L Ch R = 1 ,19506   ,516,516,516
BEGIN DESCRIPTION:
Mapping XS 6c739648
END DESCRIPTION:
XS GIS Cut Line= 2
      2313569.44      13282816.8      2312006.95     13282469.59
#Sta/Elev= 30
  3772.4  136.22  3866.3  135.36  3933.2  132.86  3976.8  129.52  3989.3  126.29
  4073.2   120.4  4170.3  118.26    4263  116.03  4458.8  112.88  4547.1  111.44
    4647  112.14    4747  112.05  4849.8  110.99  4931.7  113.25  5000.4  110.14
  5003.2  109.64  5006.4  110.14  5054.6  111.11  5075.1  113.24  5088.2  116.72
  5116.1  120.56  5126.4  122.85  5131.8  126.86  5146.7  128.81  5167.3  127.22
  5180.4  132.74  5208.3  137.87    5239  147.69  5246.6  147.81    5373  146.15
#Mann= 13 ,-1 , 0
  3772.4      .1       0  3866.3     .16       0  4073.2      .1       0
  4170.3     .16       0    4263      .1       0  4458.8     .05       0
  4547.1      .1       0    4647     .05       0    4747      .1       0
  5000.4     .07       0  5006.4      .1       0  5146.7     .08       0
  5246.6      .1       0
Bank Sta=4931.7,5075.1
XS Rating Curve= 0 ,0
Exp/Cntr=0.3,0.1

Type RM Length L Ch R = 1 ,18990   ,859,859,859
BEGIN DESCRIPTION:
Mapping XS a9dadd5d
END DESCRIPTION:
XS GIS Cut Line= 2
      2313625.02     13282795.99      2312548.61     13282136.26
#Sta/Elev= 30
  4038.9  133.88  4080.9  134.01  4233.6   125.4  4282.4  121.93  4413.7  114.16
  4530.7  111.25  4686.4  109.61  4798.6  108.43  4924.2  110.58  4982.2  108.71
  4988.1  107.77  5029.7  107.65  5032.4  107.15  5035.7  107.65  5046.1  109.25
  5055.7  109.52  5067.9  112.39  5098.3  114.25  5104.1  116.47    5135  118.78
  5140.8  120.83  5171.7  122.38  5177.6     126    5193  124.43  5198.9  126.76
  5208.4   125.9  5214.3  128.88  5220.3  128.01  5256.9  133.58  5301.4  136.72
#Mann= 7 ,-1 , 0
  4038.9      .1       0  4233.6     .16       0  4282.4      .1       0
  4530.7     .05       0  4686.4      .1       0  5029.7     .07       0
  5035.7      .1       0
Bank Sta=4982.2,5046.1
XS Rating Curve= 0 ,0
Exp/Cntr=0.3,0.1

Type RM Length L Ch R = 1 ,18131   ,707,707,707
BEGIN DESCRIPTION:
MUSTANG CREEK 14.0
END DESCRIPTION:
XS GIS Cut Line= 3
      2314404.64     13281877.49      2313711.28      13282053.7
      2312616.39     13282051.11
#Sta/Elev= 30
  4171.4  142.55  4268.3  136.06  4314.4  136.04  4404.6  131.48    4432  130.57
  4508.7  133.47  4580.9  129.48  4631.5  129.64  4653.2  122.12  4679.5  115.92
  4693.8  112.28  4704.8  110.23  4715.6  105.55  4718.3  105.05  4721.6  105.55
  4770.7  107.03  4818.3  108.16  4883.6  106.87  4980.4  107.26  4990.4  105.84
  5080.1  107.44  5150.4  107.29    5209  109.89  5250.4  111.79  5430.4  125.65
  5520.4  128.07  5660.4  125.41  5730.4  128.55  5880.4  131.81  5981.7   136.3
#Mann= 10 ,-1 , 0
  4171.4      .1       0  4404.6     .16       0  4679.5     .05       0
  4693.8      .1       0  4715.6     .07       0  4721.6      .1       0
  4770.7     .05       0  4883.6      .1       0  5080.1     .05       0
    5209      .1       0
#XS Ineff= 1 ,-1
 4696.88 4818.75  108.16
Permanent Ineff=
       F
Bank Sta=4980.4,5080.1
XS Rating Curve= 0 ,0
Exp/Cntr=0.3,0.1

Type RM Length L Ch R = 1 ,17424   ,695,695,695
BEGIN DESCRIPTION:
MUSTANG CREEK 13.0
END DESCRIPTION:
XS GIS Cut Line= 3
      2313689.36     13281064.98       2313432.4     13281391.39
      2312574.72     13282009.47
#Sta/Elev= 30
  4485.9  140.25  4615.9   131.7  4758.6  119.77  4808.3  116.95  4816.4  115.95
  4822.8  113.62  4851.6  113.36  4889.9  108.75  4916.2  106.56  4922.4  104.94
  4948.8  103.36  4951.6  102.86  4954.8  103.36  4987.4  104.83  5016.8  104.28
  5043.9  105.53  5310.1  104.76  5400.6  107.54  5467.2  110.45  5496.7  110.54
  5502.8  111.81  5567.9  112.36  5597.3  113.68  5603.4  114.91  5653.8   115.7
  5674.6  117.48  5704.1  118.07    5882  129.77  5932.3  135.07  5958.5  136.57
#Mann= 5 ,-1 , 0
  4485.9      .1       0  4889.9     .05       0  4948.8     .03       0
  4954.8     .05       0  5400.6      .1       0
Bank Sta=4987.4,5043.9
XS Rating Curve= 0 ,0
Exp/Cntr=0.3,0.1

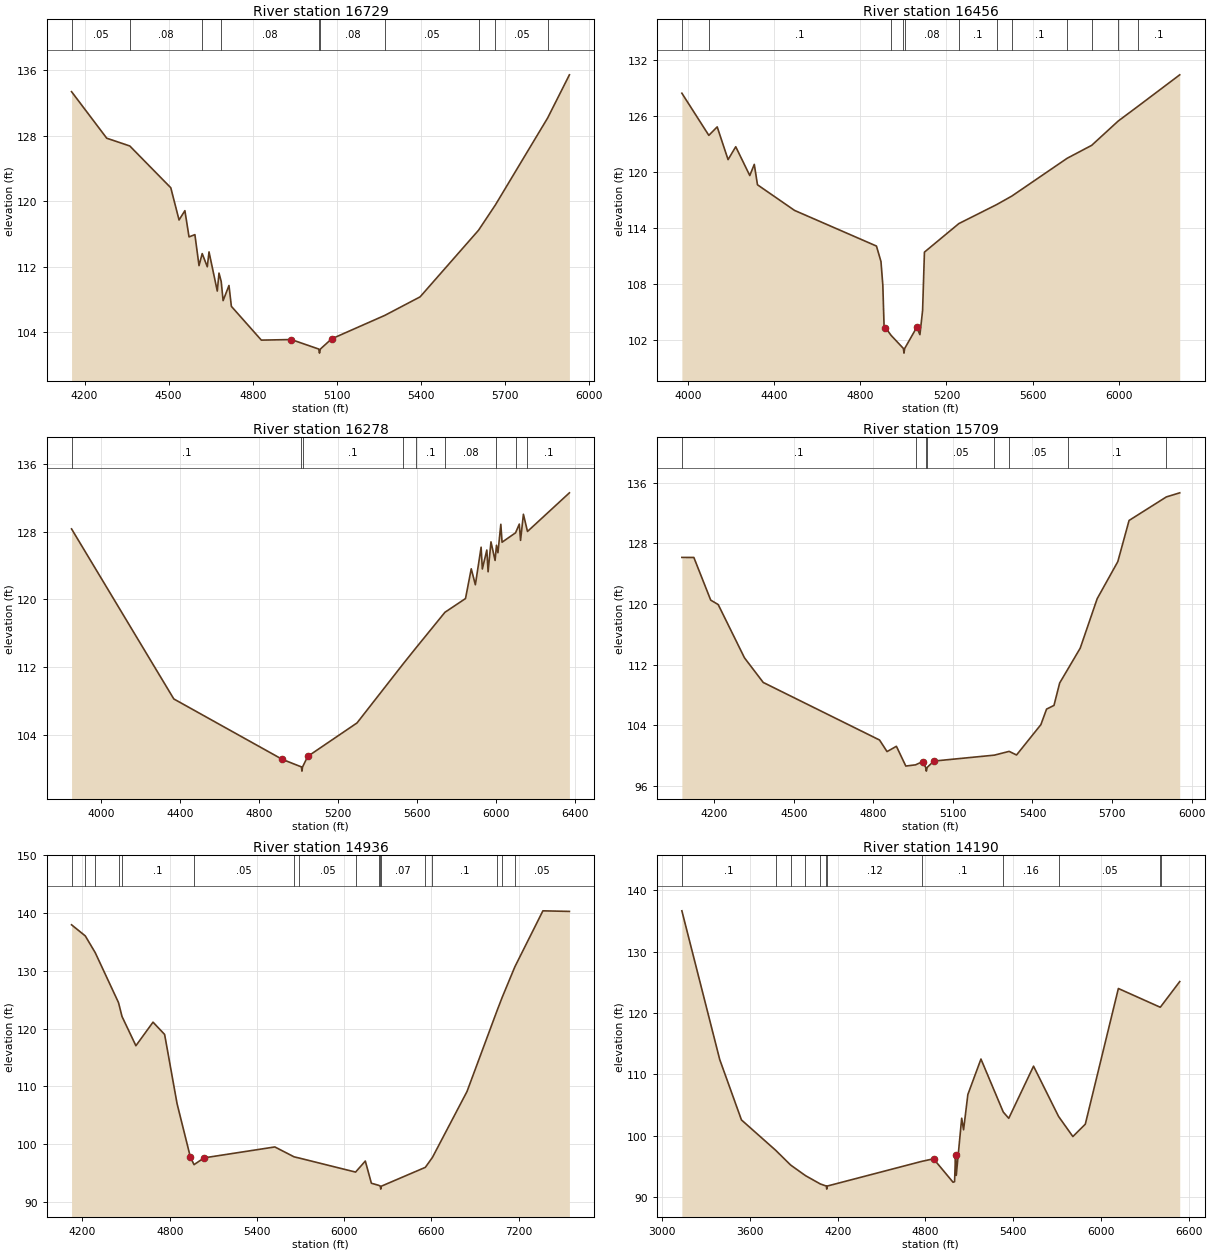
Type RM Length L Ch R = 1 ,16729   ,273,273,273
BEGIN DESCRIPTION:
MUSTANG CREEK 12.0
END DESCRIPTION:
XS GIS Cut Line= 2
      2313542.47     13280487.18      2312097.17     13281520.16
#Sta/Elev= 30
  4153.5  133.39    4279   127.7  4361.3  126.75  4507.6  121.64  4537.1   117.7
  4557.9  118.84  4572.7  115.63  4593.6  115.91  4608.3  112.12  4619.7  113.59
  4637.8  111.98    4644   113.8  4673.5  109.01  4679.6  111.21  4687.5  110.18
  4694.3  107.84  4715.2  109.69  4723.8  107.14  4830.7  103.01  4937.6  103.08
  5035.4  101.92  5038.2  101.42  5041.4  101.92  5081.2  103.16  5271.6  106.04
  5397.2   108.3  5605.8  116.45    5666  119.55  5852.4  130.18    5930  135.45
#Mann= 10 ,-1 , 0
  4153.5     .05       0  4361.3     .08       0  4619.7      .1       0
  4687.5     .08       0  5035.4     .07       0  5041.4     .08       0
  5271.6     .05       0  5605.8      .1       0    5666     .05       0
  5852.4     .08       0
Bank Sta=4937.6,5081.2
XS Rating Curve= 0 ,0
Exp/Cntr=0.3,0.1

Type RM Length L Ch R = 1 ,16456   ,178,178,178
BEGIN DESCRIPTION:
MUSTANG CREEK 11.0
END DESCRIPTION:
XS GIS Cut Line= 2
      2313616.29     13280126.92      2311736.95     13281468.06
#Sta/Elev= 30
    3973  128.48    4098  123.96  4136.8  124.87  4187.2  121.36  4222.8  122.74
  4287.9  119.65  4308.8  120.85  4323.6  118.66  4495.7  115.91  4875.4  112.09
  4896.3  110.43  4904.9  107.91  4911.1  103.16  4917.2  103.34  4943.4  102.51
  5000.3  101.11    5003  100.61  5006.3  101.11  5062.3  103.38  5076.9  102.59
  5089.3  105.17  5097.9  111.44  5257.5   114.5  5433.1  116.54  5503.9  117.46
  5759.6   121.5  5873.5  122.89  5996.7   125.5  6086.1  127.04  6281.8  130.45
#Mann= 12 ,-1 , 0
    3973     .08       0    4098      .1       0  4943.4     .08       0
  5000.3     .07       0  5006.3     .08       0  5257.5      .1       0
  5433.1     .08       0  5503.9      .1       0  5759.6     .08       0
  5873.5      .1       0  5996.7     .08       0  6086.1      .1       0
Bank Sta=4917.2,5062.3
XS Rating Curve= 0 ,0
Exp/Cntr=0.3,0.1

Type RM Length L Ch R = 1 ,16278   ,569,569,569
BEGIN DESCRIPTION:
MUSTANG CREEK 10.0
END DESCRIPTION:
XS GIS Cut Line= 2
      2313661.38     13279856.12      2311656.38       13281382.
#Sta/Elev= 30
  3851.7  128.31  4369.2  108.24  4918.1  101.11  5014.9  100.22  5017.6   99.72
  5020.9  100.22    5047  101.46  5296.5  105.41  5531.3  112.42  5593.8  114.24
  5741.4  118.47  5845.4  120.09  5874.5   123.6  5895.3  121.72  5924.4  126.15
  5930.6  123.58  5953.4  125.82  5959.7  123.25  5974.3  126.78  5995.1  124.59
  6002.2  126.38  6009.6   125.5  6024.2  128.86  6030.4  126.74  6098.7  127.85
  6117.7  128.88    6124  126.96  6138.5  130.04  6159.1  128.01  6371.3  132.57
#Mann= 9 ,-1 , 0
  3851.7      .1       0  5014.9     .07       0  5020.9      .1       0
  5531.3     .08       0  5593.8      .1       0  5741.4     .08       0
  6002.2      .1       0  6098.7     .08       0  6159.1      .1       0
Bank Sta=4918.1,5047
XS Rating Curve= 0 ,0
Exp/Cntr=0.3,0.1

Type RM Length L Ch R = 1 ,15709   ,773,773,773
BEGIN DESCRIPTION:
MUSTANG CREEK 9.0
END DESCRIPTION:
XS GIS Cut Line= 3
      2313481.66     13279377.12      2312277.66     13280527.85
      2312117.81     13280666.39
#Sta/Elev= 30
  4078.2  126.15  4123.4  126.14  4186.9  120.51  4215.2  119.92  4314.3  112.88
    4385  109.63  4823.4  102.03  4851.7   100.5    4887   101.2  4922.5   98.59
  4959.1   98.75    4986   99.18  4997.2   98.42  4999.9   97.92  5003.2   98.42
  5028.5   99.25  5256.1  100.03  5312.1  100.53  5339.9  100.05  5431.7  104.06
  5453.1  106.11  5481.1   106.6  5502.5  109.56  5533.4  111.39  5580.1  114.17
    5644   120.7  5721.7  125.59  5764.2  131.03  5904.8  134.14  5955.2  134.68
#Mann= 8 ,-1 , 0
  4078.2      .1       0  4959.1     .05       0  4997.2     .03       0
  5003.2     .05       0  5256.1      .1       0  5312.1     .05       0
  5533.4      .1       0  5904.8     .05       0
Bank Sta=4986,5028.5
XS Rating Curve= 0 ,0
Exp/Cntr=0.3,0.1

Type RM Length L Ch R = 1 ,14936   ,746,746,746
BEGIN DESCRIPTION:
Mapping XS f0a8b587
END DESCRIPTION:
XS GIS Cut Line= 3
       2313204.6     13279153.38      2312607.96     13279259.92
      2310339.08     13280932.29
#Sta/Elev= 30
  4124.8  137.95  4219.2  136.03  4287.6  133.13  4447.7  124.49  4471.9  122.08
  4567.4  117.02  4685.2   121.1    4765  118.97  4850.7  106.98  4942.5   97.71
  4967.4   96.44  5036.5   97.61  5523.2    99.5  5655.5   97.79  5692.1   97.57
  6078.5   95.15  6145.5   97.06  6187.2   93.22  6238.5   92.85    6249    92.7
  6251.7    92.2    6255    92.7  6558.5   95.97    6607   97.68  6845.1   109.1
  7054.7  123.29  7086.8  125.38  7174.4  130.69  7367.2  140.37  7549.5  140.27
#Mann= 17 ,-1 , 0
  4124.8      .1       0  4219.2     .16       0  4287.6      .1       0
  4447.7     .16       0  4471.9      .1       0  4967.4     .05       0
  5655.5      .1       0  5692.1     .05       0  6078.5     .08       0
  6238.5     .07       0    6249     .03       0    6255     .07       0
  6558.5     .05       0    6607      .1       0  7054.7     .05       0
  7086.8      .1       0  7174.4     .05       0
Bank Sta=4942.5,5036.5
XS Rating Curve= 0 ,0
Exp/Cntr=0.3,0.1

Type RM Length L Ch R = 1 ,14190   ,1703,1703,1703
BEGIN DESCRIPTION:
MUSTANG CREEK 7.0
END DESCRIPTION:
XS GIS Cut Line= 4
      2313620.16     13278940.27      2313289.87     13278599.32
      2311627.71     13278993.55      2310743.33     13279835.31
#Sta/Elev= 30
  3134.5  136.67  3393.2  112.44  3541.8  102.59  3776.3   97.63  3877.9   95.24
  3979.5   93.51  4081.2   92.15  4122.3   91.81    4125   91.31  4128.3   91.81
  4773.9   95.83    4855   96.25  4988.6   92.43  4998.9   92.52  5005.4   96.89
  5010.5   93.55  5047.6  102.87  5060.5  100.98  5089.8  106.73  5179.4  112.51
    5332  103.87  5369.4  102.85  5538.9  111.35  5709.9  103.16  5807.8   99.88
  5892.8   101.9  6118.9  124.01  6404.5  120.96    6408  121.03  6538.4  125.14
#Mann= 12 ,-1 , 0
  3134.5      .1       0  3776.3     .16       0  3877.9      .1       0
  3979.5     .07       0  4081.2     .12       0  4122.3     .07       0
  4128.3     .12       0  4773.9      .1       0    5332     .16       0
  5709.9     .05       0  6404.5      .1       0    6408     .08       0
Bank Sta=4855,5005.4
XS Rating Curve= 0 ,0
Exp/Cntr=0.3,0.1

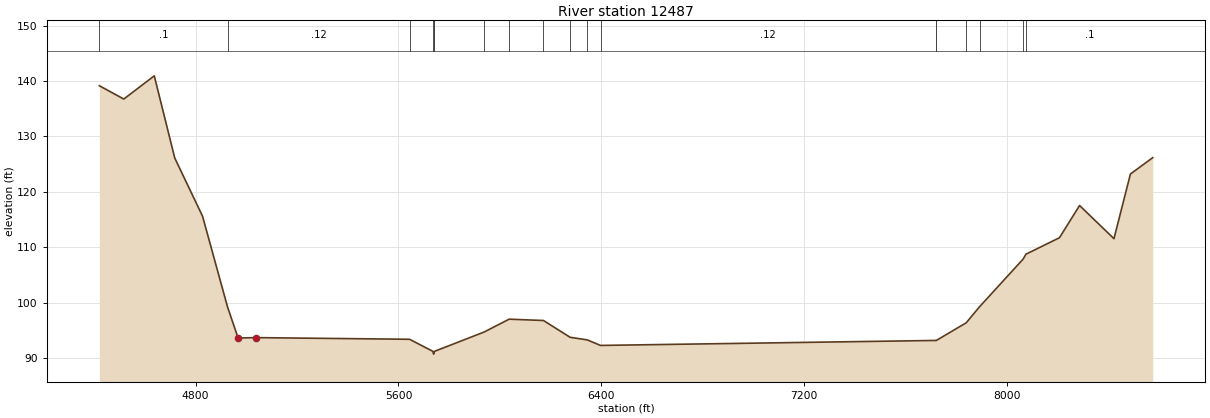
Type RM Length L Ch R = 1 ,12487   ,0,0,0
BEGIN DESCRIPTION:
MUSTANG CREEK 1.0
END DESCRIPTION:
XS GIS Cut Line= 3
      2313684.11     13277938.72      2312021.94     13277842.83
       2310541.8     13279844.74
#Sta/Elev= 30
  4420.2  139.16  4516.7  136.76  4636.9  140.95  4717.6  126.12  4827.3   115.6
  4925.8   99.23  4967.5   93.62  5037.6   93.69  5643.8   93.39  5735.8   91.21
  5738.5   90.71  5741.8   91.21    5742   91.21  5938.3   94.71  6036.5   97.02
  6171.9   96.78  6276.8   93.75  6343.9   93.29    6397   92.28  7718.7   93.18
  7719.8   93.14  7839.3   96.37  7891.7   99.26  8063.7  107.87  8074.6  108.75
  8206.9  111.72  8286.2  117.54  8421.9  111.55  8486.7  123.22  8574.8  126.18
#Mann= 18 ,-1 , 0
  4420.2      .1       0  4925.8     .12       0  5643.8     .07       0
  5735.8     .07       0  5741.8     .07       0    5742     .05       0
  5938.3     .12       0  6036.5      .1       0  6171.9     .16       0
  6276.8     .12       0  6343.9      .1       0    6397     .12       0
  7718.7      .1       0  7719.8     .08       0  7839.3      .1       0
  7891.7     .08       0  8063.7     .12       0  8074.6      .1       0
Bank Sta=4967.5,5037.6
XS Rating Curve= 0 ,0
Exp/Cntr=0.3,0.1

Chan Stop Cuts=-1
Use User Specified Reach Order=0
Composite Channel Slope=5