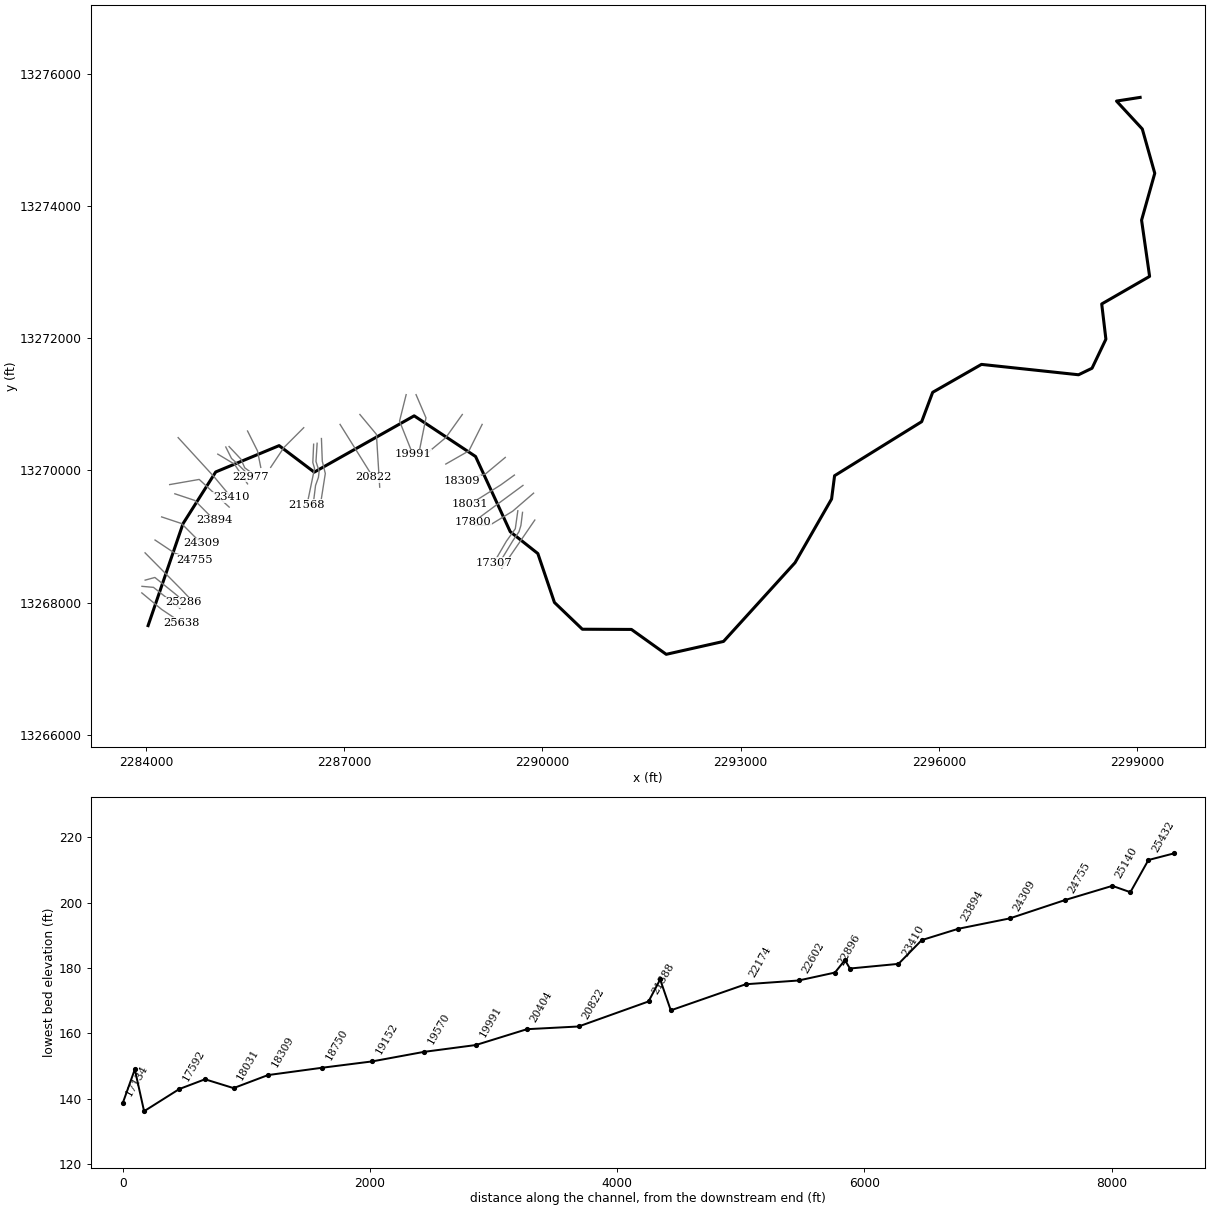
--- PAISANO CREEK.prj (project) ---

Proj Title=PAISANO CREEK Base Level Engineering
Current Plan=p01
Default Exp/Contr=0.3,0.1
English Units
Geom File=g01
Flow File=f01
Plan File=p01
Y Axis Title=Elevation
X Axis Title(PF)=Main Channel Distance
X Axis Title(XS)=Station
BEGIN DESCRIPTION:
PAISANO CREEK
END DESCRIPTION:
DSS Export Rating Curves= 0
DSS Export Rating Curve Sorted= 0
DSS Export Volume Flow Curves= 0
DXF OffsetX= 0
DXF OffsetY= 0
DXF ScaleX= 1
DXF ScaleY= 10

--- PAISANO CREEK.p01 (plan) ---

Plan Title=Multiple Run
Short Identifier=Multiple
Geom File=g01
Flow File=f01
Subcritical Flow
K Sum by GR= 0
Std Step Tol= 0.01
Critical Tol= 0.01
Num of Std Step Trials= 20
Max Error Tol= 0.3
Flow Tol Ratio= 0.001
Split Flow NTrial= 30
Split Flow Tol= 0.02
Split Flow Ratio= 0.02
Log Output Level= 0
Friction Slope Method= 1
Unsteady Friction Slope Method= 2
Unsteady Bridges Friction Slope Method= 1
Parabolic Critical Depth
Global Vel Dist=  1 , 1 , 1
Global Log Level= 0
CheckData=True
Encroach Param= -1, 0, 0, 0
BEGIN DESCRIPTION:
Multiple Run
END DESCRIPTION:

--- PAISANO CREEK.f01 (steady flow) ---

Flow Title=Multiple
Program Version=4.10
Number of Profiles= 7
Profile Names=10-year,25-year,50-year,1pct_min,100-year,1pct_plu,500-year
River Rch & RM=PAISANO CREEK,Reach-1         ,25638
     273     386     482     444     600     812     945
River Rch & RM=PAISANO CREEK,Reach-1         ,21482
     479     691     875     813    1100    1488    1765
River Rch & RM=PAISANO CREEK,Reach-1         ,13336
    1217    1798    2309    2169    2933    3967    4796
River Rch & RM=PAISANO CREEK,Reach-1         ,5250
    1341    1982    2545    2388    3239    4367    5264
Boundary for River Rch & Prof#=PAISANO CREEK,Reach-1         , 1
Up Type= 0
Dn Type= 3
Dn Slope=0.005
Boundary for River Rch & Prof#=PAISANO CREEK,Reach-1         , 2
Up Type= 0
Dn Type= 3
Dn Slope=0.005
Boundary for River Rch & Prof#=PAISANO CREEK,Reach-1         , 3
Up Type= 0
Dn Type= 3
Dn Slope=0.005
Boundary for River Rch & Prof#=PAISANO CREEK,Reach-1         , 4
Up Type= 0
Dn Type= 3
Dn Slope=0.005
Boundary for River Rch & Prof#=PAISANO CREEK,Reach-1         , 5
Up Type= 0
Dn Type= 3
Dn Slope=0.005
Boundary for River Rch & Prof#=PAISANO CREEK,Reach-1         , 6
Up Type= 0
Dn Type= 3
Dn Slope=0.005
Boundary for River Rch & Prof#=PAISANO CREEK,Reach-1         , 7
Up Type= 0
Dn Type= 3
Dn Slope=0.005
DSS Import GetInterval= 0
DSS Import GetPeak= 0
DSS Import FillOption= 0

--- PAISANO CREEK.g01 (geometry) ---

Geom Title=Existing Conditions
Program Version=4.10

River Reach=PAISANO CREEK   ,Reach-1
Reach XY= 30
      2284032.72     13267651.85      2284561.65     13269195.14
      2285056.06     13269977.21      2286015.36     13270375.68
      2286547.04      13269974.2      2288059.31     13270826.55
      2288988.16     13270211.28      2289512.59      13269073.3
      2289930.67     13268742.35      2290181.71     13268002.07
      2290603.96     13267597.02      2291346.53     13267593.97
      2291873.14     13267217.33      2292740.19     13267412.27
      2293822.58     13268604.27      2294375.61     13269568.08
      2294420.85      13269920.3      2295738.69     13270738.04
      2295905.06     13271182.31      2296643.46     13271605.06
       2298112.7     13271448.07      2298316.63     13271546.82
      2298526.48     13271986.34      2298463.25     13272519.56
      2299187.91     13272936.87      2299066.38     13273787.56
      2299266.03      13274497.2      2299077.23     13275167.77
      2298686.98     13275590.23      2299044.62     13275645.79

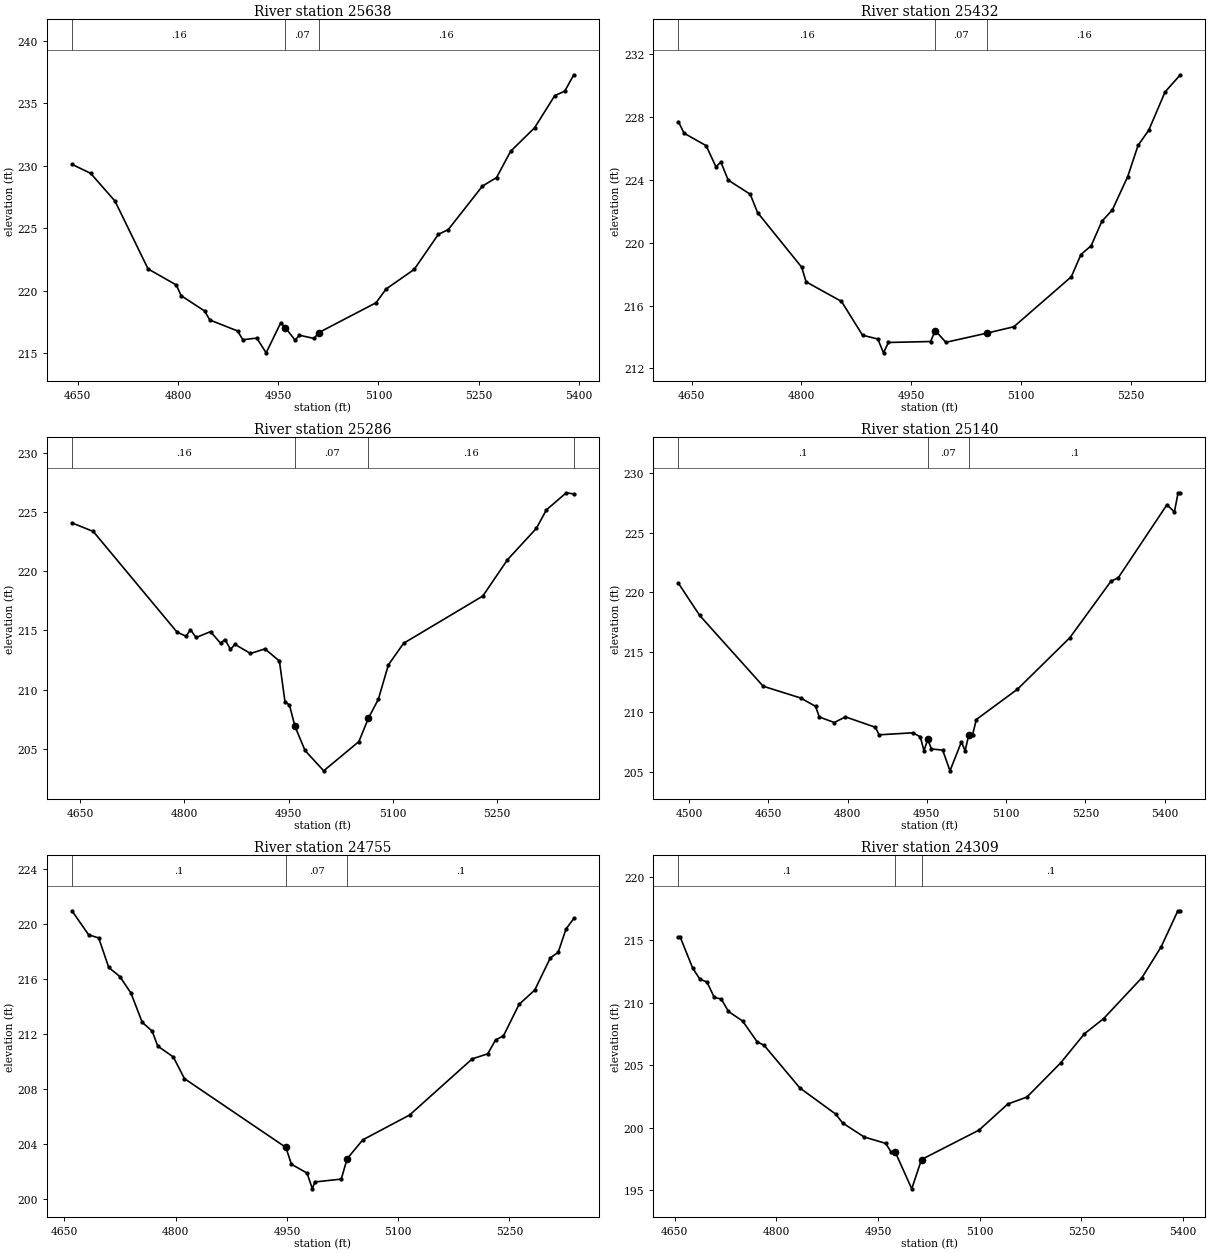
Type RM Length L Ch R = 1 ,25638   ,206,206,206
BEGIN DESCRIPTION:
PAISANO CREEK 42.0
END DESCRIPTION:
XS GIS Cut Line= 3
      2283937.75     13268146.83      2284237.72     13267896.85
      2284537.69     13267696.87
#Sta/Elev= 30
  4641.4   230.1  4669.4  229.38  4705.8  227.16  4755.3  221.73  4797.6  220.44
  4804.7  219.59  4839.9  218.36  4847.7  217.64  4889.3  216.76  4897.1  216.06
    4918  216.19    4932  215.01  4953.8  217.41  4960.9  217.01  4975.3  216.03
  4981.8  216.42  5003.9  216.16  5010.4  216.62  5096.5  219.02  5111.5  220.12
  5153.6  221.69  5189.6  224.49  5204.6  224.88  5255.7  228.36  5276.8  229.04
  5297.8  231.14  5333.8  233.03  5363.9   235.6  5378.9  235.96  5392.4  237.27
#Mann= 3 , 0 , 0
  4641.4     .16       0  4960.9     .07       0  5010.4     .16       0
Bank Sta=4960.9,5010.4
XS Rating Curve= 0 ,0
Exp/Cntr=0.3,0.1

Type RM Length L Ch R = 1 ,25432   ,146,146,146
BEGIN DESCRIPTION:
Mapping XS 3ae1e4ff
END DESCRIPTION:
XS GIS Cut Line= 3
      2283940.08     13268246.28      2284114.55     13268230.66
      2284514.01      13267912.9
#Sta/Elev= 30
  4632.2  227.69  4639.9  226.96    4670  226.17  4683.4  224.82  4690.1  225.13
  4700.1  223.98  4730.2  223.08  4740.3  221.91  4800.5  218.44  4806.5  217.51
  4854.9  216.26  4883.7  214.11  4904.5  213.87  4912.3  212.99    4919  213.65
  4976.6  213.71    4983  214.41  4997.5  213.66  5054.2  214.25  5090.4  214.65
  5168.9  217.83    5182  219.24  5196.1  219.81  5210.5  221.35  5224.9  222.08
  5245.9   224.2  5260.1  226.19  5274.6  227.15    5297  229.59  5317.8  230.68
#Mann= 3 , 0 , 0
  4632.2     .16       0    4983     .07       0  5054.2     .16       0
Bank Sta=4983,5054.2
XS Rating Curve= 0 ,0
Exp/Cntr=0.3,0.1

Type RM Length L Ch R = 1 ,25286   ,146,146,146
BEGIN DESCRIPTION:
Mapping XS f772d2bb
END DESCRIPTION:
XS GIS Cut Line= 4
      2283988.25     13268340.03      2284135.38      13268380.4
      2284481.73     13268100.45      2284561.17     13268005.38
#Sta/Elev= 30
  4638.3  224.07  4668.9  223.35  4789.5  214.85  4802.4  214.51  4808.8  215.05
  4816.8   214.4  4837.6  214.89    4852  213.92  4858.4  214.23  4866.3   213.4
  4872.8  213.82  4895.1  213.05  4915.9  213.44  4936.7  212.41  4944.7  208.98
  4951.1   208.7  4959.1   206.9  4973.5  204.87  5000.4  203.15    5051  205.62
  5064.7  207.59    5079  209.19  5093.4  212.09  5115.3  213.91  5229.3   217.9
  5264.7  220.96  5306.3  223.61  5320.7  225.17  5349.3  226.61  5360.1  226.51
#Mann= 4 ,-1 , 0
  4638.3     .16       0  4959.1     .07       0  5064.7     .16       0
  5360.1     .05       0
Bank Sta=4959.1,5064.7
XS Rating Curve= 0 ,0
Exp/Cntr=0.3,0.1

Type RM Length L Ch R = 1 ,25140   ,385,385,385
BEGIN DESCRIPTION:
PAISANO CREEK 41.0
END DESCRIPTION:
XS GIS Cut Line= 3
      2283986.94     13268752.79      2284535.12     13268199.41
      2284652.29     13268075.73
#Sta/Elev= 30
  4480.2  220.76  4520.3  218.08  4640.5  212.16  4711.2  211.18  4739.5  210.48
  4746.6  209.59  4774.9  209.13  4796.1   209.6  4852.7  208.73  4859.7   208.1
  4923.4  208.27  4937.5  207.94  4944.6  206.77  4951.7  207.72  4958.7  206.92
    4980  206.82  4993.8  205.09  5015.3   207.5  5022.4  206.77  5029.4  208.11
  5036.5   208.1  5043.6  209.38  5121.4  211.91  5220.4  216.21  5298.2  220.93
  5312.3  221.24  5404.2  227.33  5418.3  226.73  5425.3  228.33  5429.5  228.33
#Mann= 3 , 0 , 0
  4480.2      .1       0  4951.7     .07       0  5029.4      .1       0
Bank Sta=4951.7,5029.4
XS Rating Curve= 0 ,0
Exp/Cntr=0.3,0.1

Type RM Length L Ch R = 1 ,24755   ,446,446,446
BEGIN DESCRIPTION:
PAISANO CREEK 40.0
END DESCRIPTION:
XS GIS Cut Line= 3
      2284137.71     13268946.86      2284437.72     13268746.85
      2284737.72     13268646.85
#Sta/Elev= 30
  4660.1  220.98  4682.6  219.23  4696.2     219  4709.7  216.85  4724.7  216.19
  4739.7  214.98  4754.8  212.86  4768.3  212.21  4775.8  211.12  4796.8  210.33
  4811.8  208.75  4948.6  203.74  4956.1  202.51  4977.1  201.87  4984.4  200.72
  4987.6  201.22  5023.3  201.43  5031.2  202.91  5052.3  204.29  5115.5   206.1
  5199.9  210.19  5220.9  210.56  5231.5  211.58    5242  211.86  5263.1  214.16
  5284.2   215.2  5305.3  217.55  5315.8  217.95  5326.4  219.65  5336.9  220.42
#Mann= 3 , 0 , 0
  4660.1      .1       0  4948.6     .07       0  5031.2      .1       0
Bank Sta=4948.6,5031.2
XS Rating Curve= 0 ,0
Exp/Cntr=0.3,0.1

Type RM Length L Ch R = 1 ,24309   ,415,415,415
BEGIN DESCRIPTION:
PAISANO CREEK 39.0
END DESCRIPTION:
XS GIS Cut Line= 3
      2284237.75     13269296.84      2284537.72     13269196.85
      2284837.75     13268896.83
#Sta/Elev= 30
  4655.4  215.22    4658  215.22  4676.4  212.75    4687  211.87  4697.5  211.64
  4708.1  210.42  4718.6  210.28  4729.2  209.29  4750.2  208.52  4771.3  206.88
  4781.9  206.58  4834.6  203.18  4887.3   201.1  4897.8  200.38  4929.4  199.27
  4961.1  198.76    4969  198.09  4975.1  198.09  4999.6  195.13    5014  197.47
  5098.9  199.82  5141.3   201.9  5169.6  202.46  5219.1  205.17  5254.4  207.51
  5282.7  208.72  5339.3  211.99  5367.6  214.45  5392.3  217.33  5395.9  217.33
#Mann= 3 , 0 , 0
  4655.4      .1       0  4975.1     .07       0    5014      .1       0
Bank Sta=4975.1,5014
XS Rating Curve= 0 ,0
Exp/Cntr=0.3,0.1

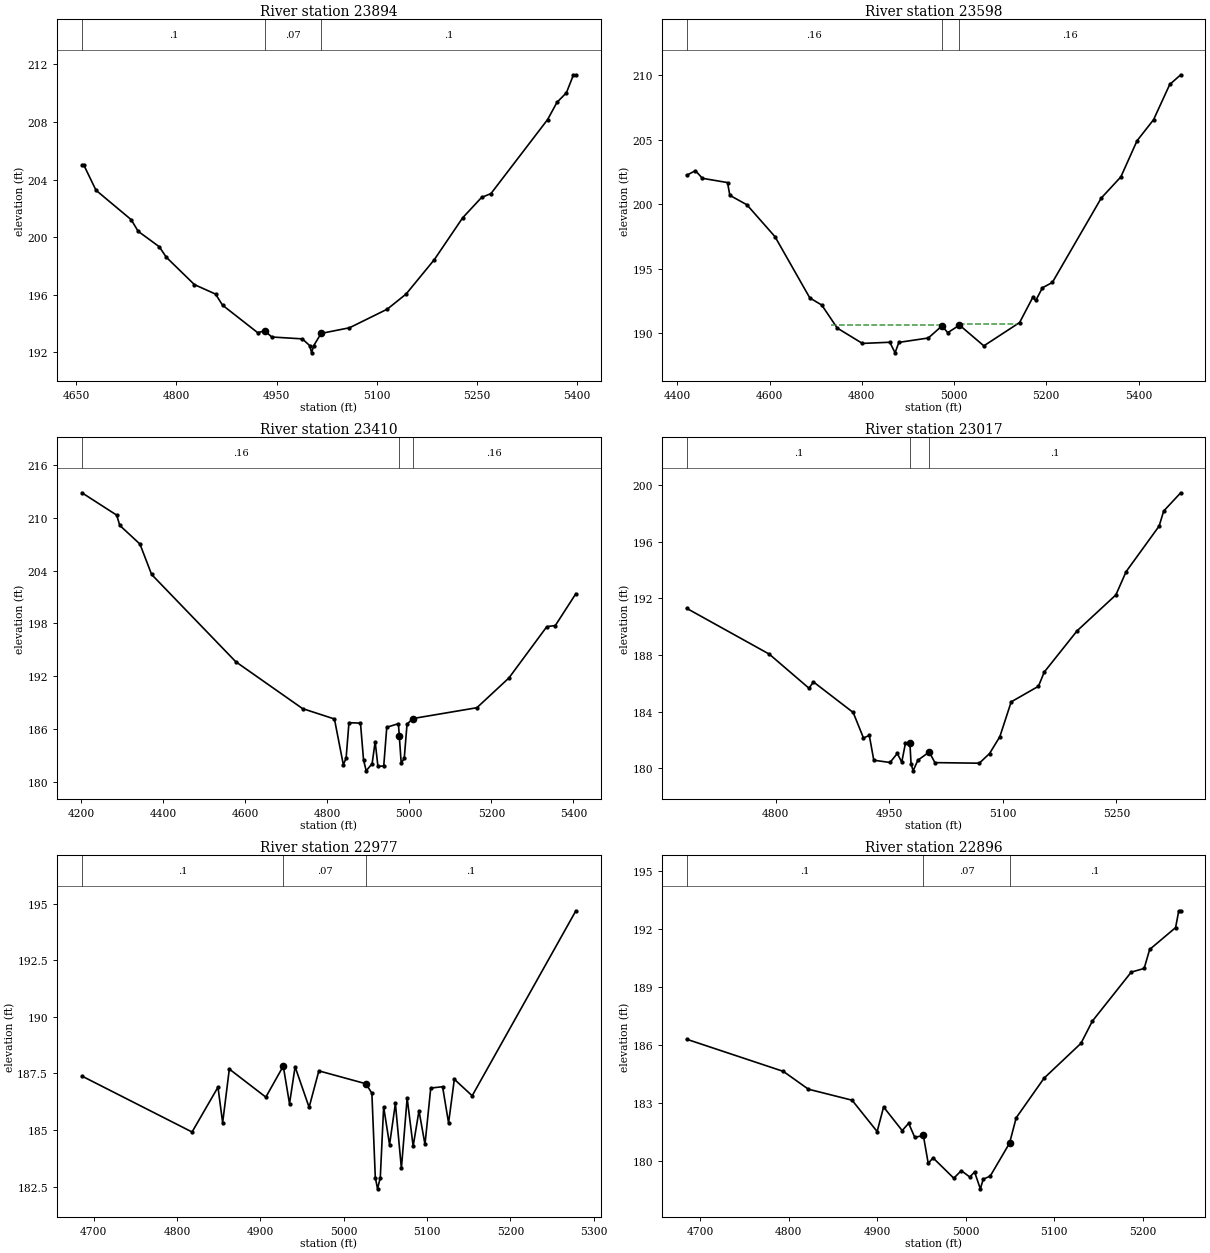
Type RM Length L Ch R = 1 ,23894   ,296,296,296
BEGIN DESCRIPTION:
PAISANO CREEK 38.0
END DESCRIPTION:
XS GIS Cut Line= 3
      2284437.73     13269646.85      2284737.72     13269546.85
      2285037.73     13269246.84
#Sta/Elev= 30
  4658.3  205.03  4660.9  205.03  4679.4  203.26  4732.1  201.22  4742.6  200.41
  4774.2  199.34  4784.8  198.61  4826.9  196.71  4858.6  196.05  4869.1  195.28
  4921.8  193.37  4932.4   193.5  4942.9  193.07  4988.7  192.94  4999.8  192.47
  5002.6  191.97  5005.8  192.47  5016.9  193.32  5059.4  193.71  5115.9     195
  5144.2  196.05  5186.7  198.45  5229.1  201.35  5257.4  202.76  5271.5  203.03
  5356.4  208.17  5370.5  209.37  5384.6  210.03  5395.2  211.28  5398.8  211.28
#Mann= 3 , 0 , 0
  4658.3      .1       0  4932.4     .07       0  5016.9      .1       0
Bank Sta=4932.4,5016.9
XS Rating Curve= 0 ,0
Exp/Cntr=0.3,0.1

Type RM Length L Ch R = 1 ,23598   ,188,188,188
BEGIN DESCRIPTION:
PAISANO CREEK 37.0
END DESCRIPTION:
XS GIS Cut Line= 3
      2284359.25     13269786.02      2284806.25     13269864.14
      2285259.78     13269445.33
#Sta/Elev= 30
  4420.4  202.26  4439.2  202.61  4454.3  202.02  4508.8  201.69  4513.8   200.7
  4550.8  199.97  4611.7   197.5  4687.3  192.75  4713.2   192.2  4746.7  190.42
  4801.2  189.23  4860.7  189.32  4872.1   188.5  4880.3  189.31  4944.2  189.65
 4973.91  190.59  4986.3  190.06 5011.78  190.65  5064.6  189.04  5142.2  190.85
  5170.6  192.79  5177.4  192.57  5191.6  193.54  5213.1  193.95  5319.2  200.49
  5361.7  202.13  5396.8  204.93  5432.6  206.56  5467.7  209.29  5491.5  210.04
#Mann= 3 , 0 , 0
  4420.4     .16       0 4973.91     .07       0 5011.78     .16       0
#XS Ineff= 2 ,-1
 4732.71 4972.04190.6464 5014.59 5134.54190.7299
Permanent Ineff=
       F       F
Bank Sta=4973.91,5011.78
XS Rating Curve= 0 ,0
Exp/Cntr=0.3,0.1

Type RM Length L Ch R = 1 ,23410   ,393,393,393
BEGIN DESCRIPTION:
PAISANO CREEK 37.1
END DESCRIPTION:
XS GIS Cut Line= 3
      2284487.72     13270496.85      2285037.72     13269896.85
      2285287.69     13269596.89
#Sta/Elev= 30
  4201.8  212.83  4286.6  210.29    4294  209.13  4343.3     207  4371.7  203.55
    4577  193.63  4739.8  188.31  4817.5  187.13  4839.1  181.95  4845.9  182.66
  4852.9  186.71    4881  186.66  4888.4   182.5  4894.9  181.24  4909.4  182.06
  4916.8  184.56  4923.5  181.75  4937.7  181.79  4945.1  186.19  4973.5   186.6
 4975.57  185.22  4980.3   182.1  4987.7  182.66  4994.5  186.54  5008.6  187.18
  5164.8  188.41  5242.9  191.79  5335.3  197.62  5356.1  197.75  5406.2  201.37
#Mann= 3 , 0 , 0
  4201.8     .16       0 4975.57     .07       0  5008.6     .16       0
#XS Ineff= 2 ,-1
 4808.28 4857.62185.9954  4879.9 4962.75185.9621
Permanent Ineff=
       F       F
Bank Sta=4975.57,5008.6
XS Rating Curve= 0 ,0
Exp/Cntr=0.3,0.1

Type RM Length L Ch R = 1 ,23017   ,40,40,40
BEGIN DESCRIPTION:
PAISANO CREEK 36.0
END DESCRIPTION:
XS GIS Cut Line= 3
      2285087.69     13270246.87      2285337.72     13270096.85
       2285537.7     13269796.88
#Sta/Elev= 30
  4682.8  191.29  4791.7  188.06  4844.2  185.65    4850   186.1  4902.5  183.94
  4916.1  182.14  4923.8  182.32  4929.7  180.57  4951.1  180.41  4960.8  181.05
  4966.6  180.43  4971.5  181.77  4977.4  181.77  4978.9  180.32  4981.6  179.82
  4987.9  180.57  5002.9  181.15  5010.4   180.4    5069  180.36  5082.5  181.04
  5096.1  182.23  5111.1  184.69  5147.1  185.79  5154.7  186.79  5198.2  189.71
  5249.3  192.24  5262.8  193.88  5306.4   197.1  5312.4  198.16  5334.9  199.45
#Mann= 3 , 0 , 0
  4682.8      .1       0  4977.4     .07       0  5002.9      .1       0
Bank Sta=4977.4,5002.9
XS Rating Curve= 0 ,0
Exp/Cntr=0.3,0.1

Type RM Length L Ch R = 1 ,22977   ,81,81,81
BEGIN DESCRIPTION:
Mapping XS 31b1ab36
END DESCRIPTION:
XS GIS Cut Line= 4
       2285208.3     13270355.03      2285295.11     13270181.41
       2285353.7     13270129.33       2285583.2     13269906.33
#Sta/Elev= 30
    4686  187.38  4818.1  184.91  4849.2  186.89  4854.8  185.32  4862.8  187.69
  4906.6  186.45  4927.5  187.82    4935  186.16  4941.7  187.79  4958.5     186
  4970.2  187.61  5026.7  187.04  5033.8  186.62  5037.9   182.9  5040.6   182.4
  5043.9   182.9  5047.9  186.02    5055  184.35    5062  186.17  5069.2   183.3
  5076.1  186.41  5083.3  184.28  5090.3  185.85  5097.5  184.36  5104.4  186.85
  5118.6  186.91  5125.8  185.31  5132.7  187.24  5154.1  186.51  5278.5  194.68
#Mann= 3 , 0 , 0
    4686      .1       0  4927.5     .07       0  5026.7      .1       0
Bank Sta=4927.5,5026.7
XS Rating Curve= 0 ,0
Exp/Cntr=0.3,0.1

Type RM Length L Ch R = 1 ,22896   ,294,294,294
BEGIN DESCRIPTION:
Mapping XS 1afe7c45
END DESCRIPTION:
XS GIS Cut Line= 4
      2285258.19     13270361.57      2285438.34     13270170.56
      2285494.76     13270040.36      2285618.45     13269949.22
#Sta/Elev= 30
  4684.8  186.31  4793.9  184.65  4822.2  183.73  4871.6  183.16  4899.9  181.54
  4907.2  182.81  4928.2  181.59  4935.5  181.97  4942.4  181.24  4952.1  181.34
  4957.6   179.9  4963.1  180.18  4986.5  179.13    4995  179.52  5004.6  179.19
    5010  179.45  5016.5  178.58  5019.8  179.08  5027.7  179.24  5049.5  180.94
    5057  182.25  5088.5   184.3  5130.2   186.1  5143.1  187.25    5187  189.78
  5201.6  189.97  5207.8  190.95  5237.1  192.08  5240.7  192.95  5242.9  192.95
#Mann= 3 , 0 , 0
  4684.8      .1       0  4952.1     .07       0  5049.5      .1       0
Bank Sta=4952.1,5049.5
XS Rating Curve= 0 ,0
Exp/Cntr=0.3,0.1

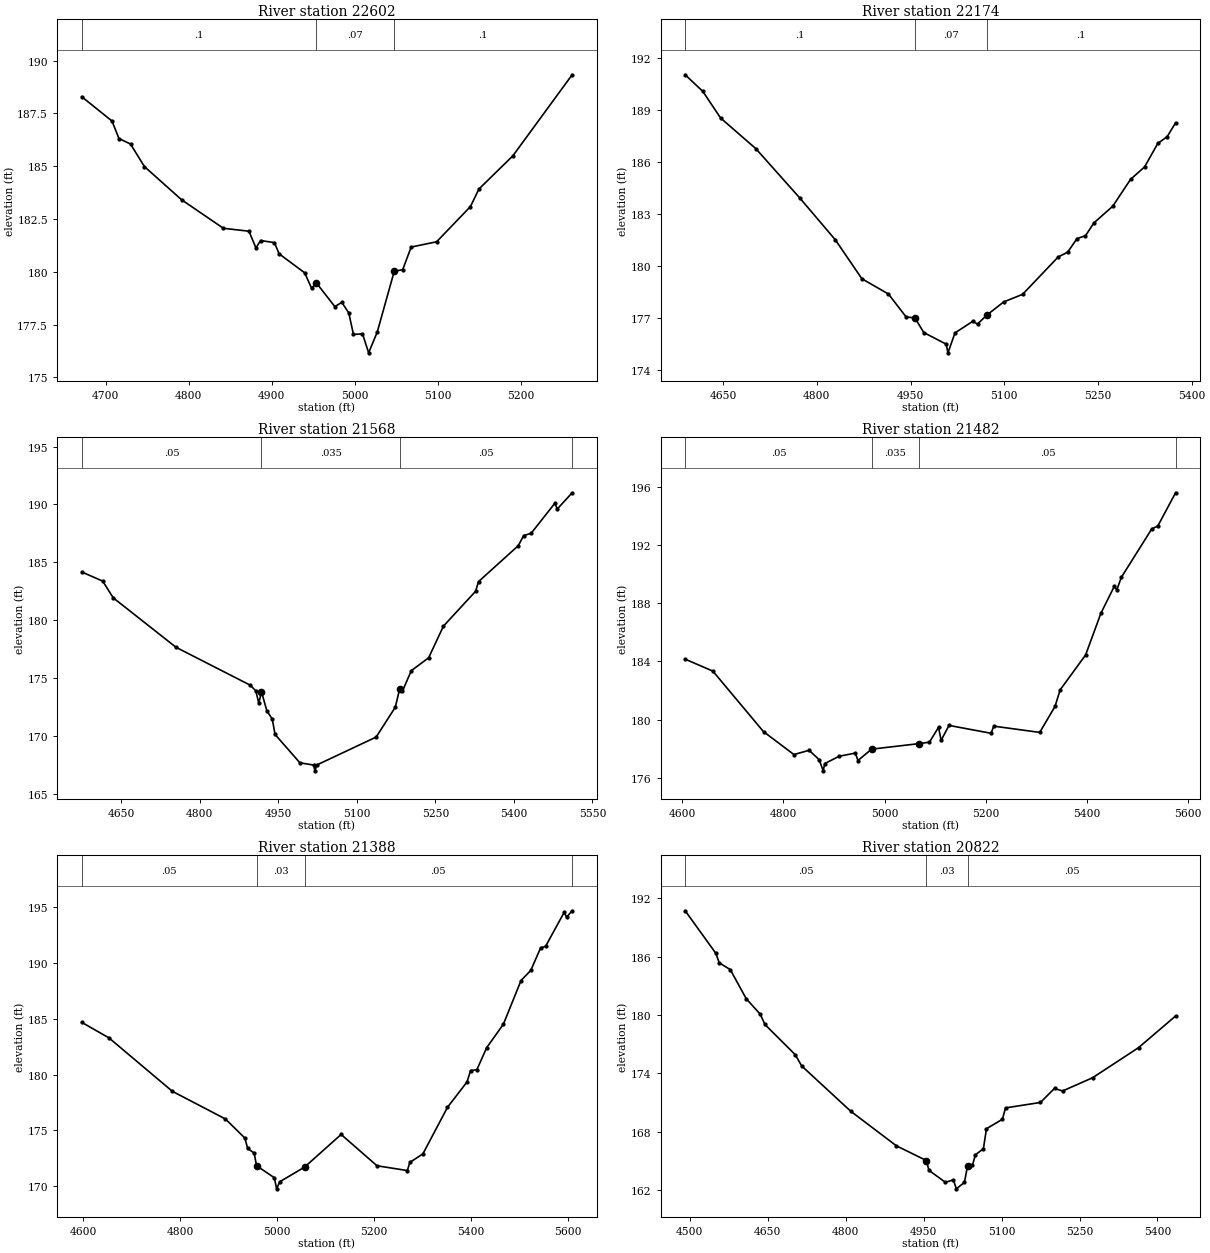
Type RM Length L Ch R = 1 ,22602   ,428,428,428
BEGIN DESCRIPTION:
PAISANO CREEK 35.0
END DESCRIPTION:
XS GIS Cut Line= 3
       2285537.7     13270596.89      2285687.72     13270296.85
      2285737.72     13270046.86
#Sta/Elev= 30
  4671.3  188.29  4707.7  187.14  4716.1  186.31    4730  186.05  4746.8  184.98
  4791.5  183.41  4841.8  182.06  4872.6  181.92    4881  181.13  4886.6  181.48
  4903.3  181.38  4908.9  180.85  4939.7  179.95  4948.1  179.21  4953.6  179.48
    4976  178.35  4984.4  178.55  4992.8  178.05  4998.4  177.03  5009.3  177.06
  5016.7  176.16  5027.1  177.15  5047.5  180.02  5057.7   180.1  5067.9  181.17
  5098.5  181.42  5139.3  183.09  5149.5  183.92  5190.3  185.49  5261.7  189.33
#Mann= 3 , 0 , 0
  4671.3      .1       0  4953.6     .07       0  5047.5      .1       0
Bank Sta=4953.6,5047.5
XS Rating Curve= 0 ,0
Exp/Cntr=0.3,0.1

Type RM Length L Ch R = 1 ,22174   ,606,606,606
BEGIN DESCRIPTION:
PAISANO CREEK 34.0
END DESCRIPTION:
XS GIS Cut Line= 3
      2286387.72     13270646.85      2286087.72     13270346.85
      2285887.73     13270046.87
#Sta/Elev= 30
  4589.4  191.04  4617.7  190.08    4646  188.55  4702.5  186.78  4773.2  183.92
  4829.8  181.52  4872.2  179.28  4914.7   178.4  4942.9  177.08  4957.1  177.02
  4971.2  176.18  5007.1  175.51  5009.9  175.01  5021.2  176.16  5049.7  176.83
  5057.2  176.67  5072.3  177.19  5099.3  177.95  5129.3  178.38  5186.4  180.54
  5201.4  180.81  5216.5   181.6    5230  181.76  5243.5   182.5  5273.6  183.46
  5302.1  185.01  5324.6  185.73  5345.7  187.08  5360.7  187.47  5374.2  188.27
#Mann= 3 , 0 , 0
  4589.4      .1       0  4957.1     .07       0  5072.3      .1       0
Bank Sta=4957.1,5072.3
XS Rating Curve= 0 ,0
Exp/Cntr=0.3,0.1

Type RM Length L Ch R = 1 ,21568   ,86,86,86
BEGIN DESCRIPTION:
PAISANO CREEK 33.0
END DESCRIPTION:
XS GIS Cut Line= 4
      2286537.72     13270396.89      2286525.58     13270118.48
      2286551.62     13270031.68      2286436.61     13269476.15
#Sta/Elev= 30
  4574.7  184.18  4614.8  183.39  4634.8  181.95  4754.9  177.68  4896.8  174.41
  4907.3  173.92  4912.8  172.86    4918  173.85  4928.2  172.21  4938.6  171.49
  4943.9  170.17  4991.4  167.72  5017.4  167.53  5020.2  167.03  5023.4  167.53
  5136.9  169.94  5173.6  172.52  5181.9  174.11  5187.1   173.9  5204.2  175.67
  5237.2  176.78  5265.5  179.51  5326.8  182.51  5332.5  183.35  5408.5  186.45
  5418.7  187.32  5432.9  187.51    5478  190.09  5483.1  189.62  5511.3  191.01
#Mann= 4 ,-1 , 0
  4574.7     .05       0    4918    .035       0  5181.9     .05       0
  5511.3     .05       0
Bank Sta=4918,5181.9
XS Rating Curve= 0 ,0
Exp/Cntr=0.3,0.1

Type RM Length L Ch R = 1 ,21482   ,94,94,94
BEGIN DESCRIPTION:
Mapping XS 3d2ffe63
END DESCRIPTION:
XS GIS Cut Line= 6
      2286590.68     13270411.41      2286573.32     13270135.84
      2286621.07      13269986.1      2286610.21     13269894.96
      2286566.81     13269773.43      2286527.95     13269460.34
#Sta/Elev= 30
  4605.8  184.15  4660.5  183.33  4760.7  179.17  4820.8   177.6  4850.8  177.89
  4870.9  177.24  4878.6  176.48  4881.9  176.98    4910  177.48  4942.2   177.7
  4947.4  177.19  4974.4  177.97  5068.5  178.35  5088.7  178.45  5106.7  179.47
  5111.8  178.57  5127.4   179.6  5210.6  179.06  5215.9  179.55  5306.8  179.12
  5337.1  180.91  5347.1  182.04  5397.5  184.44  5427.8  187.31  5454.2  189.15
  5459.3  188.92  5468.1  189.77  5528.5  193.11  5540.1  193.29  5575.4  195.58
#Mann= 4 ,-1 , 0
  4605.8     .05       0  4974.4    .035       0  5068.5     .05       0
  5575.4      .1       0
Bank Sta=4974.4,5068.5
XS Rating Curve= 0 ,0
Exp/Cntr=0.3,0.1

Type RM Length L Ch R = 1 ,21388   ,566,566,566
BEGIN DESCRIPTION:
PAISANO CREEK 32.0
END DESCRIPTION:
XS GIS Cut Line= 4
      2286655.79     13270483.07      2286668.81     13270140.18
      2286714.38     13269953.55       2286640.6     13269482.64
#Sta/Elev= 30
  4596.7  184.69    4653  183.29  4783.7   178.5  4893.1  176.02  4933.2  174.31
    4939  173.38  4952.4  172.96  4957.5  171.82    4994  170.75  4998.9  169.75
    5005  170.38  5056.5   171.7  5131.9  174.63  5205.9  171.82  5268.6  171.39
  5273.6  172.12  5300.7  172.89  5351.3  177.06  5391.8  179.35    5399  180.36
    5412  180.44  5432.3  182.42  5466.7  184.52  5503.1  188.44  5523.4  189.36
  5543.6  191.38  5553.7   191.5    5592  194.55  5597.1  194.13  5608.6   194.7
#Mann= 4 ,-1 , 0
  4596.7     .05       0  4957.5     .03       0  5056.5     .05       0
  5608.6      .1       0
Bank Sta=4957.5,5056.5
XS Rating Curve= 0 ,0
Exp/Cntr=0.3,0.1

Type RM Length L Ch R = 1 ,20822   ,418,418,418
BEGIN DESCRIPTION:
PAISANO CREEK 31.0
END DESCRIPTION:
XS GIS Cut Line= 3
       2286937.7     13270696.89      2287187.72     13270296.85
       2287437.7     13269896.89
#Sta/Elev= 30
  4491.4  190.72  4550.4  186.34  4556.9  185.36  4578.1  184.67  4608.8  181.67
  4635.9  180.07  4644.7  179.02  4703.1  175.91  4715.5  174.75  4809.8  170.09
  4897.7  166.53  4955.5  165.01  4960.2  164.01    4992  162.77  5007.4  163.03
    5013   162.1  5028.6  162.76  5034.5  164.45  5043.9  164.52  5049.8  165.61
  5065.1  166.23    5071  168.29  5101.7  169.26  5107.6  170.43  5174.8  170.99
  5201.9  172.44  5217.3  172.17    5275  173.53  5363.5  176.63  5434.8  179.89
#Mann= 3 , 0 , 0
  4491.4     .05       0  4955.5     .03       0  5034.5     .05       0
Bank Sta=4955.5,5034.5
XS Rating Curve= 0 ,0
Exp/Cntr=0.3,0.1

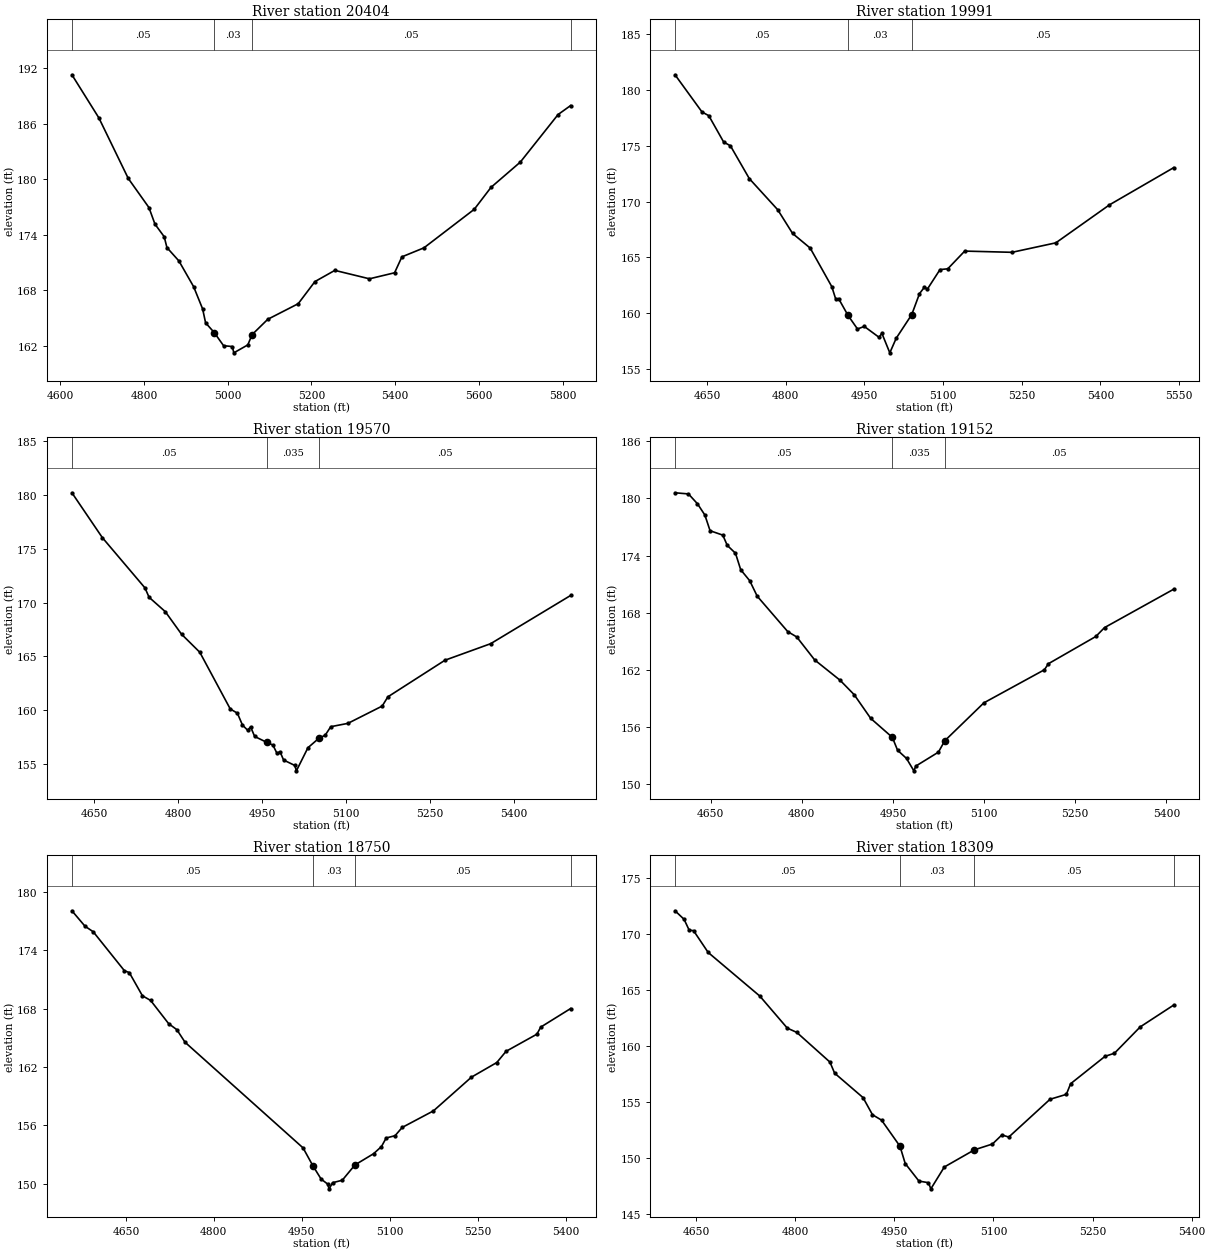
Type RM Length L Ch R = 1 ,20404   ,413,413,413
BEGIN DESCRIPTION:
PAISANO CREEK 30.0
END DESCRIPTION:
XS GIS Cut Line= 3
      2287237.75     13270846.82      2287487.72     13270546.85
      2287537.72     13269746.88
#Sta/Elev= 30
  4627.4  191.28  4691.8  186.63  4762.1  180.09  4811.5  176.95  4825.9  175.16
    4848   173.8  4854.5  172.63  4883.1  171.19  4918.3  168.41  4939.8  166.01
  4946.9  164.51  4967.7  163.45  4989.9  162.04  5010.7  161.95  5014.4  161.27
  5047.9  162.13  5057.9  163.23  5095.5  164.89  5168.2  166.57  5208.2  168.96
  5255.8  170.17  5338.5  169.26  5398.6  169.91  5416.1  171.63  5468.7   172.6
    5589  176.76  5629.1  179.13  5699.2  181.86  5789.4  186.99  5819.4  187.96
#Mann= 4 ,-1 , 0
  4627.4     .05       0  4967.7     .03       0  5057.9     .05       0
  5819.4     .05       0
Bank Sta=4967.7,5057.9
XS Rating Curve= 0 ,0
Exp/Cntr=0.3,0.1

Type RM Length L Ch R = 1 ,19991   ,421,421,421
BEGIN DESCRIPTION:
PAISANO CREEK 29.0
END DESCRIPTION:
XS GIS Cut Line= 3
      2287937.72     13271146.84      2287837.72     13270746.85
      2288037.72     13270246.86
#Sta/Elev= 30
  4589.1  181.38  4640.6  178.04  4653.5  177.71  4681.9  175.34  4694.7  175.01
  4730.8  172.06  4784.9  169.27  4813.3  167.14  4846.8  165.83    4888  162.37
  4895.7  161.22  4900.9   161.3  4918.9  159.79    4937  158.57  4949.9   158.8
  4978.2  157.82  4983.4  158.19  4998.6  156.43  5010.8  157.74  5040.4  159.86
  5055.2  161.74  5064.7  162.33  5070.1  162.14  5094.3   163.9  5109.1  163.97
  5141.4  165.56  5231.6  165.45  5315.1   166.3  5417.4  169.71  5539.9  173.05
#Mann= 3 , 0 , 0
  4589.1     .05       0  4918.9     .03       0  5040.4     .05       0
Bank Sta=4918.9,5040.4
XS Rating Curve= 0 ,0
Exp/Cntr=0.3,0.1

Type RM Length L Ch R = 1 ,19570   ,418,418,418
BEGIN DESCRIPTION:
PAISANO CREEK 28.0
END DESCRIPTION:
XS GIS Cut Line= 3
      2288087.73     13271146.82      2288237.72     13270796.85
      2288137.71     13270296.81
#Sta/Elev= 30
    4610  180.22  4664.4  176.04  4740.5  171.36  4747.8  170.49  4776.8  169.15
  4805.8  167.05  4838.4  165.37  4892.8  160.09  4905.5   159.7  4914.6  158.59
  4923.7  158.12  4929.1  158.42  4936.4  157.53  4958.1  156.98    4969  156.73
  4976.2  155.96  4981.7  156.11    4988  155.34  5008.1  154.83  5010.9  154.33
  5031.5  156.48  5051.9   157.4  5062.1  157.63  5072.3  158.44  5102.9  158.75
  5164.1  160.36  5174.3  161.22  5276.3  164.63  5357.9  166.17  5500.7  170.66
#Mann= 3 , 0 , 0
    4610     .05       0  4958.1    .035       0  5051.9     .05       0
Bank Sta=4958.1,5051.9
XS Rating Curve= 0 ,0
Exp/Cntr=0.3,0.1

Type RM Length L Ch R = 1 ,19152   ,402,402,402
BEGIN DESCRIPTION:
PAISANO CREEK 27.0
END DESCRIPTION:
XS GIS Cut Line= 3
      2288787.71     13270846.84      2288537.72     13270496.85
      2288237.73     13270246.86
#Sta/Elev= 30
  4591.4  180.58  4613.5  180.46  4628.3  179.43  4640.5  178.25  4649.1   176.6
    4670  176.14  4677.4  175.06  4690.9  174.24  4699.5  172.51  4714.3  171.36
  4726.6  169.74  4776.9  166.02  4791.7  165.46  4821.2  163.05    4863  160.92
  4886.3   159.4  4913.4  156.92    4949  154.93  4957.6  153.58  4972.3  152.72
  4984.4  151.42  4987.6  151.92  5024.8  153.38  5035.2  154.57  5099.6  158.55
  5199.2  162.02  5205.7  162.65  5283.8  165.51  5298.1  166.44    5412  170.47
#Mann= 3 , 0 , 0
  4591.4     .05       0    4949    .035       0  5035.2     .05       0
Bank Sta=4949,5035.2
XS Rating Curve= 0 ,0
Exp/Cntr=0.3,0.1

Type RM Length L Ch R = 1 ,18750   ,441,441,441
BEGIN DESCRIPTION:
PAISANO CREEK 26.0
END DESCRIPTION:
XS GIS Cut Line= 3
      2289087.73     13270696.87      2288887.72     13270296.85
      2288537.75     13270096.87
#Sta/Elev= 30
    4558  178.03  4580.4  176.44  4594.3  175.88  4647.5  171.88  4655.8  171.69
  4678.2  169.31  4692.2  168.83  4722.9  166.45  4736.9  165.83  4750.9  164.54
  4952.1   153.7  4968.9  151.86  4982.9   150.5  4993.8     150  4996.6   149.5
  5002.4  150.13  5018.9  150.38  5040.5  151.95  5072.2   153.1  5085.8  153.84
  5093.8  154.72  5108.9  154.95  5121.1   155.8  5174.4   157.5  5239.2  160.96
  5282.4  162.46  5298.2  163.61  5350.8  165.37  5357.2  166.09  5408.3     168
#Mann= 4 ,-1 , 0
    4558     .05       0  4968.9     .03       0  5040.5     .05       0
  5408.3     .05       0
Bank Sta=4968.9,5040.5
XS Rating Curve= 0 ,0
Exp/Cntr=0.3,0.1

Type RM Length L Ch R = 1 ,18309   ,278,278,278
BEGIN DESCRIPTION:
PAISANO CREEK 25.0
END DESCRIPTION:
XS GIS Cut Line= 3
      2289437.76     13270196.89      2289137.72     13269946.85
      2288787.69     13269846.85
#Sta/Elev= 30
  4618.2  172.05  4631.9  171.29  4639.7  170.31  4646.2  170.28  4668.4  168.33
  4746.5  164.44  4788.1  161.58  4802.4   161.2  4852.6  158.55  4859.7  157.56
  4902.7  155.38    4917  153.85  4930.7  153.37  4958.6  151.04  4966.5   149.5
  4987.3  147.93  5001.6  147.79  5005.3  147.24  5025.7  149.19  5071.2  150.72
  5098.5  151.24  5112.8  152.05  5123.2  151.86  5185.6  155.23  5210.3  155.67
  5216.8  156.62  5268.8  159.06  5283.1  159.34  5322.1  161.69  5372.8  163.64
#Mann= 4 ,-1 , 0
  4618.2     .05       0  4958.6     .03       0  5071.2     .05       0
  5372.8     .05       0
Bank Sta=4958.6,5071.2
XS Rating Curve= 0 ,0
Exp/Cntr=0.3,0.1

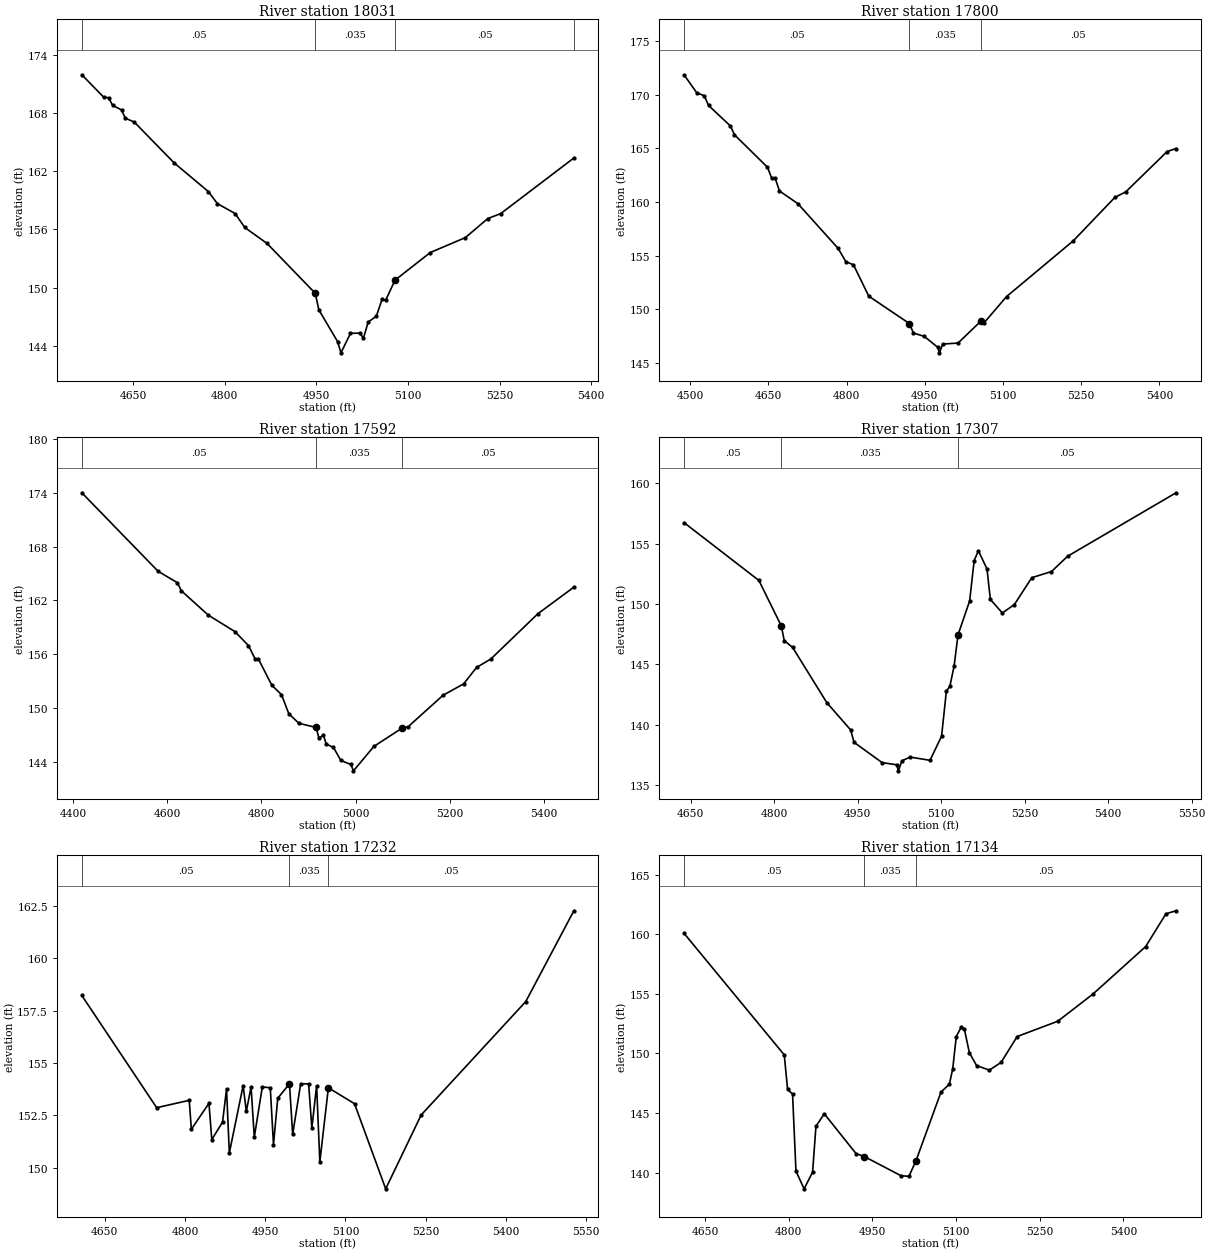
Type RM Length L Ch R = 1 ,18031   ,231,231,231
BEGIN DESCRIPTION:
PAISANO CREEK 24.0
END DESCRIPTION:
XS GIS Cut Line= 3
      2289575.43     13269929.92      2289371.44     13269782.35
      2288902.68     13269487.21
#Sta/Elev= 30
  4565.9  171.96  4601.5  169.66    4610  169.58  4616.2  168.81  4630.9  168.33
  4637.1  167.48  4651.8  167.08  4716.8  162.88  4773.2   159.9  4787.9  158.66
  4816.9  157.64  4832.7   156.2  4869.2  154.55  4948.1  149.41    4954   147.7
  4984.6  144.43  4990.2  143.26  5005.8  145.27  5021.1   145.3    5027  144.77
  5034.8  146.44  5048.2  147.04  5057.5  148.78  5063.5  148.69  5078.7  150.76
  5136.4  153.61  5194.1  155.16  5230.6  157.12  5251.8  157.63  5371.6  163.37
#Mann= 4 ,-1 , 0
  4565.9     .05       0  4948.1    .035       0  5078.7     .05       0
  5371.6     .05       0
Bank Sta=4948.1,5078.7
XS Rating Curve= 0 ,0
Exp/Cntr=0.3,0.1

Type RM Length L Ch R = 1 ,17800   ,208,208,208
BEGIN DESCRIPTION:
Mapping XS 9a0f8f21
END DESCRIPTION:
XS GIS Cut Line= 3
      2289705.66     13269773.69      2289128.38     13269348.33
      2288946.12      13269213.8
#Sta/Elev= 30
  4488.3  171.86  4512.5   170.2  4527.2   169.9  4535.4     169  4577.3  167.09
  4585.1  166.27  4648.3  163.25  4656.7   162.2  4662.9  162.26  4671.3  161.04
  4706.8  159.85    4784  155.68  4798.7  154.45  4813.3  154.16  4842.6  151.24
  4920.5  148.69  4928.2  147.81  4949.1  147.49  4975.3  146.46  4978.1  145.96
  4984.5  146.78  5013.8  146.87  5057.1  148.89    5064  148.77  5106.8   151.2
  5235.2  156.41  5314.6  160.44  5335.4  160.95  5414.8  164.71  5431.9  164.99
#Mann= 3 , 0 , 0
  4488.3     .05       0  4920.5    .035       0  5057.1     .05       0
Bank Sta=4920.5,5057.1
XS Rating Curve= 0 ,0
Exp/Cntr=0.3,0.1

Type RM Length L Ch R = 1 ,17592   ,285,285,285
BEGIN DESCRIPTION:
Mapping XS e13ce380
END DESCRIPTION:
XS GIS Cut Line= 4
      2289866.26     13269656.51      2289549.39     13269383.05
      2289215.19     13269179.06      2288981.75     13269166.09
#Sta/Elev= 30
  4419.1  174.02  4580.8  165.26  4621.9  163.98  4630.2  163.08  4687.2  160.37
  4744.2  158.51  4772.7  156.96    4787  155.45  4793.6  155.48  4822.1  152.54
  4842.7  151.49  4858.2  149.36  4879.5  148.29  4916.2  147.82  4922.1  146.63
  4931.7  146.96  4937.6  145.97    4953  145.59  4968.5  144.15  4989.8  143.69
  4995.4  142.98  5038.8  145.71  5097.4  147.71  5111.8  147.92  5185.3  151.41
  5229.2  152.69  5256.7  154.53  5286.8  155.46  5386.9  160.53    5463  163.48
#Mann= 3 , 0 , 0
  4419.1     .05       0  4916.2    .035       0  5097.4     .05       0
Bank Sta=4916.2,5097.4
XS Rating Curve= 0 ,0
Exp/Cntr=0.3,0.1

Type RM Length L Ch R = 1 ,17307   ,75,75,75
BEGIN DESCRIPTION:
PAISANO CREEK 23.0
END DESCRIPTION:
XS GIS Cut Line= 4
      2289627.72     13269390.01      2289589.53     13269117.47
      2289454.11     13268928.23      2289264.86     13268603.56
#Sta/Elev= 30
  4638.3  156.74  4772.8  151.95  4813.1  148.18  4818.3  146.97  4833.3  146.41
  4894.7  141.84  4937.5  139.58  4943.7  138.55  4994.1  136.87  5020.5  136.69
  5023.3  136.19  5029.7  137.02  5044.4  137.33  5080.1  137.06  5100.9  139.06
  5109.5   142.8  5115.7  143.18  5123.3  144.84  5130.4  147.44  5151.3  150.26
  5159.4  153.59    5167  154.41  5182.5   152.9  5188.5  150.38    5210  149.26
  5231.5  149.95  5262.9  152.18  5298.3  152.69  5327.4  153.96    5522  159.21
#Mann= 3 , 0 , 0
  4638.3     .05       0  4813.1    .035       0  5130.4     .05       0
Bank Sta=4813.1,5130.4
XS Rating Curve= 0 ,0
Exp/Cntr=0.3,0.1

Type RM Length L Ch R = 1 ,17232   ,98,98,98
BEGIN DESCRIPTION:
Mapping XS 4ab214a0
END DESCRIPTION:
XS GIS Cut Line= 5
       2289698.9     13269365.74       2289674.6     13269169.55
      2289645.08     13269072.33       2289554.8     13268940.38
      2289315.21     13268546.27
#Sta/Elev= 30
    4607  158.22    4747  152.87  4807.9  153.22  4811.9  151.84  4844.8  153.08
  4850.1  151.35  4870.2  152.18  4877.7  153.76  4882.9  150.71  4908.7  153.92
  4914.7   152.7  4923.6  153.86  4929.6  151.46  4944.6  153.86  4959.5  153.82
  4965.5  151.11  4973.5  153.32  4995.4  154.01  5001.4   151.6  5016.3     154
  5031.2  154.01  5037.3   151.9  5046.2  153.92  5052.2  150.29  5068.2  153.82
  5117.1  153.06  5175.4     149  5241.7  152.52  5437.4  157.93  5527.4  162.26
#Mann= 3 , 0 , 0
    4607     .05       0  4995.4    .035       0  5068.2     .05       0
Bank Sta=4995.4,5068.2
XS Rating Curve= 0 ,0
Exp/Cntr=0.3,0.1

Type RM Length L Ch R = 1 ,17134   ,692,692,692
BEGIN DESCRIPTION:
PAISANO CREEK 22.0
END DESCRIPTION:
XS GIS Cut Line= 2
      2289884.64     13269249.38      2289386.39     13268521.96
#Sta/Elev= 30
  4612.6  160.07  4792.2  149.87  4798.2  146.98  4807.1  146.58  4813.2  140.12
  4827.8  138.63    4843  140.03    4849  143.87  4863.9  144.93  4920.8  141.59
  4935.7  141.34  5001.4  139.73  5015.7  139.68  5028.4     141  5073.1  146.75
  5088.1  147.41  5094.1   148.7  5100.5  151.41    5109  152.17  5115.1     152
  5123.9  150.06  5136.9  148.97  5159.8  148.59  5180.8  149.24  5209.6  151.41
  5282.3  152.69  5345.3  154.97  5439.9  158.96  5476.2  161.71  5494.3  161.96
#Mann= 3 , 0 , 0
  4612.6     .05       0  4935.7    .035       0  5028.4     .05       0
Bank Sta=4935.7,5028.4
XS Rating Curve= 0 ,0
Exp/Cntr=0.3,0.1