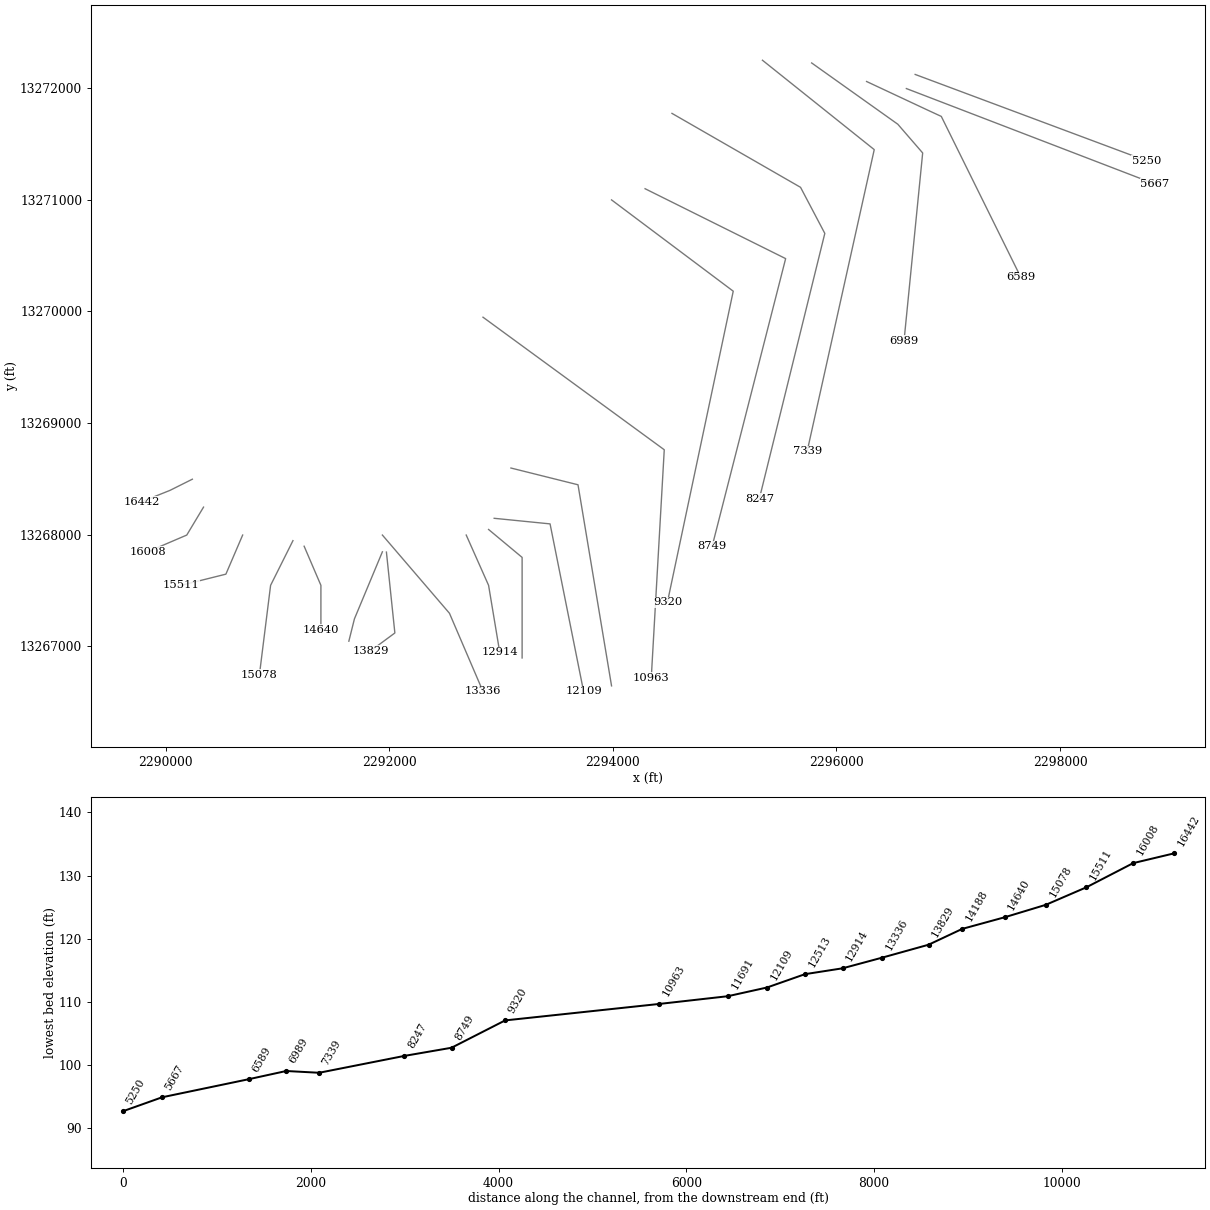
HEC-RAS study PAISANO CREEK.prj: PAISANO CREEK Base Level Engineering

--- PAISANO CREEK.g01 (geometry) --- (continued)

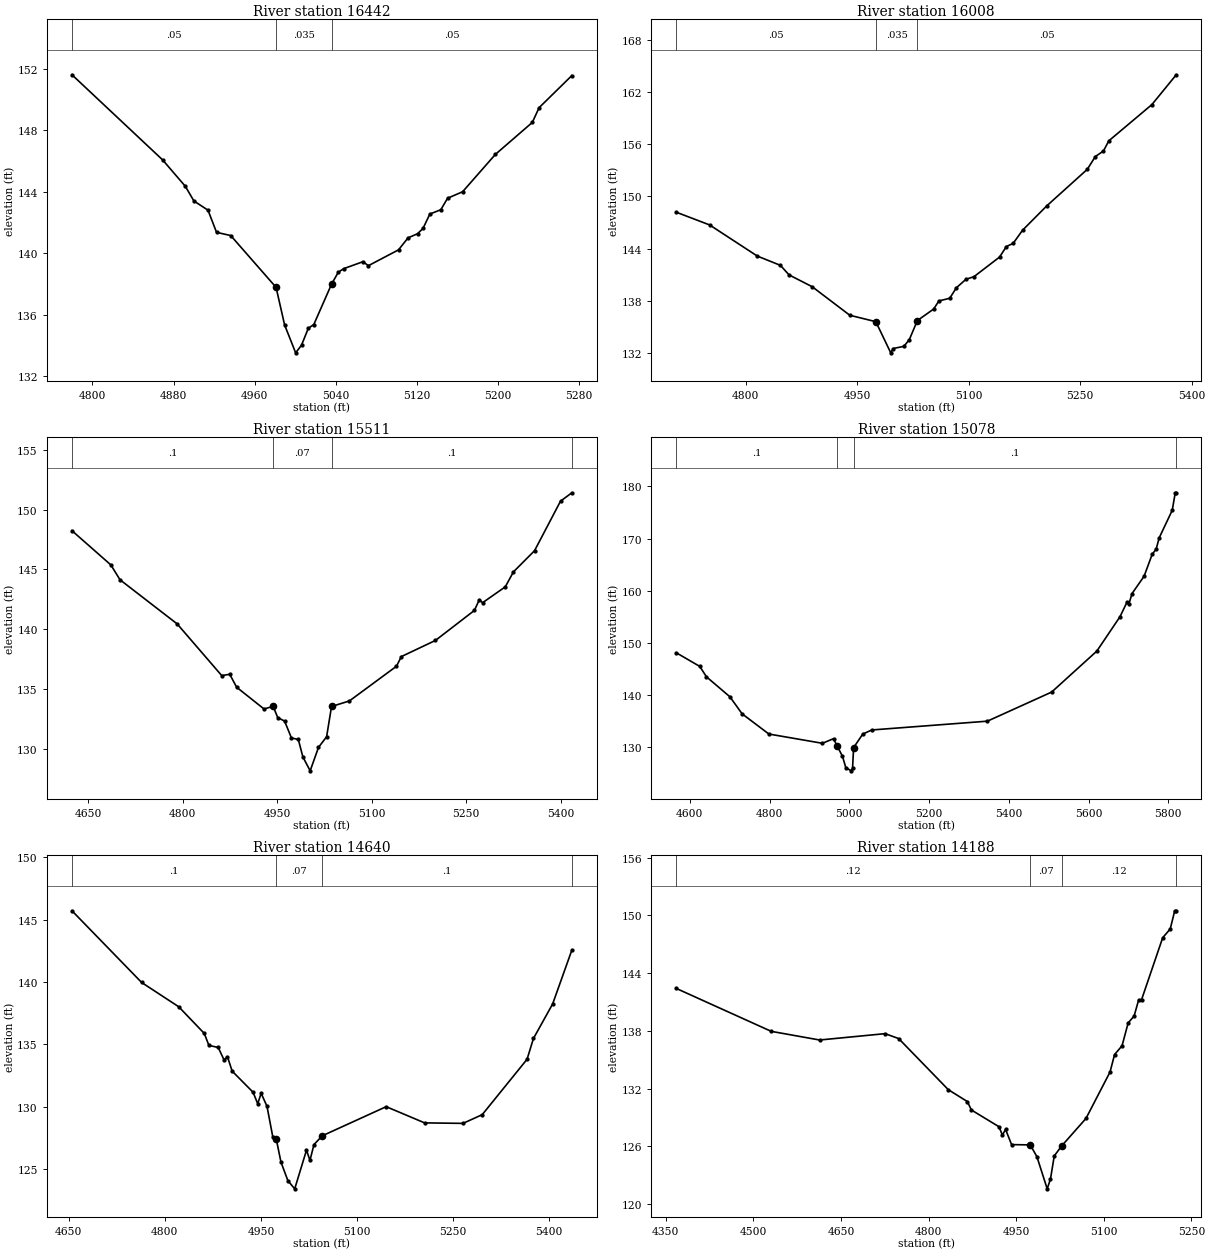
Type RM Length L Ch R = 1 ,16442   ,434,434,434
BEGIN DESCRIPTION:
PAISANO CREEK 21.0
END DESCRIPTION:
XS GIS Cut Line= 3
       2290237.7     13268496.84      2290037.72     13268396.85
      2289787.76     13268296.87
#Sta/Elev= 30
  4779.9  151.61  4869.3  146.07  4891.7  144.35  4900.1   143.4    4914   142.8
  4922.4  141.36  4936.4  141.15  4981.1  137.78  4989.5  135.34  5000.4  133.52
  5006.2  134.02  5012.9  135.12  5018.3  135.36  5035.8  137.99  5042.5  138.77
  5047.9     139  5066.8  139.45  5072.1  139.19  5101.8  140.22  5111.2     141
  5120.6  141.27    5126  141.62  5132.7  142.55  5143.5  142.83  5150.2  143.58
    5165     144  5197.3  146.43  5233.7  148.51  5240.4  149.47  5272.7  151.56
#Mann= 3 , 0 , 0
  4779.9     .05       0  4981.1    .035       0  5035.8     .05       0
Bank Sta=4981.1,5035.8
XS Rating Curve= 0 ,0
Exp/Cntr=0.3,0.1

Type RM Length L Ch R = 1 ,16008   ,497,497,497
BEGIN DESCRIPTION:
PAISANO CREEK 20.0
END DESCRIPTION:
XS GIS Cut Line= 3
      2290337.74     13268246.89      2290187.72     13267996.85
       2289837.7     13267846.85
#Sta/Elev= 30
  4706.8  148.18  4751.5  146.72  4815.7  143.13  4846.8  142.06  4858.4  140.96
  4889.5   139.6  4940.1  136.31  4975.1  135.57  4995.2  131.98  4998.5  132.48
  5012.9  132.73  5020.2  133.51    5031   135.7  5052.8  137.02    5060  137.96
  5074.5  138.27  5083.6  139.49  5096.3  140.45  5107.2  140.76  5141.6  143.02
  5150.7  144.23  5159.8  144.59  5172.5  146.11  5205.1  148.92  5259.5  153.12
  5270.4   154.6  5281.3  155.24  5288.5  156.41  5346.5  160.59  5379.2  164.02
#Mann= 3 , 0 , 0
  4706.8     .05       0  4975.1    .035       0    5031     .05       0
Bank Sta=4975.1,5031
XS Rating Curve= 0 ,0
Exp/Cntr=0.3,0.1

Type RM Length L Ch R = 1 ,15511   ,433,433,433
BEGIN DESCRIPTION:
PAISANO CREEK 19.0
END DESCRIPTION:
XS GIS Cut Line= 3
      2290687.74     13267996.89      2290537.72     13267646.85
      2290137.76     13267546.86
#Sta/Elev= 30
  4624.4  148.23  4686.1  145.37  4700.6  144.13  4791.3  140.44    4862  136.12
  4874.7  136.23  4885.6  135.15  4929.1  133.33  4943.6  133.55  4950.8  132.61
  4961.7  132.32  4972.6  130.91  4983.5  130.78  4990.7  129.33  5002.3  128.16
  5015.5  130.12  5028.4  131.01  5036.2  133.54  5064.5     134  5139.2   136.9
    5147  137.71  5201.1  139.06  5262.9  141.57  5270.7  142.47  5275.8  142.21
  5311.9  143.54  5324.8  144.79  5358.3  146.56  5399.5   150.7  5417.5   151.4
#Mann= 4 ,-1 , 0
  4624.4      .1       0  4943.6     .07       0  5036.2      .1       0
  5417.5     .05       0
Bank Sta=4943.6,5036.2
XS Rating Curve= 0 ,0
Exp/Cntr=0.3,0.1

Type RM Length L Ch R = 1 ,15078   ,438,438,438
BEGIN DESCRIPTION:
PAISANO CREEK 18.0
END DESCRIPTION:
XS GIS Cut Line= 3
      2291137.72     13267946.86      2290937.72     13267546.85
      2290837.73      13266746.9
#Sta/Elev= 30
  4566.4  148.05  4625.1  145.44  4641.9  143.44  4700.6  139.61  4731.3  136.33
  4798.4  132.45  4932.6  130.67  4960.5  131.56  4968.9  130.24  4982.9  128.19
  4991.3  125.99    5005  125.38  5008.2  125.88  5010.8  129.84  5033.8  132.44
  5056.4  133.23  5346.2  134.92  5507.4  140.51  5620.8  148.39  5678.8  154.99
  5696.4  157.79  5701.4   157.5    5709  159.44  5739.2  162.76  5759.4  166.96
  5769.5  167.98    5777  170.13  5809.8  175.44  5817.3  178.79  5819.8  178.79
#Mann= 4 ,-1 , 0
  4566.4      .1       0  4968.9     .07       0  5010.8      .1       0
  5819.8     .16       0
Bank Sta=4968.9,5010.8
XS Rating Curve= 0 ,0
Exp/Cntr=0.3,0.1

Type RM Length L Ch R = 1 ,14640   ,452,452,452
BEGIN DESCRIPTION:
PAISANO CREEK 17.0
END DESCRIPTION:
XS GIS Cut Line= 3
      2291237.73     13267896.83      2291387.72     13267546.85
      2291387.72     13267146.81
#Sta/Elev= 30
  4654.9  145.71  4763.7  139.96  4821.7  138.01  4861.6  135.87  4868.8  134.91
  4883.3  134.75  4892.4  133.75  4897.8     134  4905.1  132.85  4937.7  131.16
    4945  130.24  4950.4  131.07  4959.5  130.03  4968.6  127.57    4974   127.4
  4981.3  125.56  4992.1  124.07  5002.8  123.41  5021.2  126.51  5026.6  125.69
  5032.9  126.96  5045.7  127.66  5145.7     130  5205.7   128.7  5265.7  128.66
  5295.7  129.36  5365.7   133.8  5375.7  135.47  5405.7  138.24  5435.7  142.56
#Mann= 4 ,-1 , 0
  4654.9      .1       0    4974     .07       0  5045.7      .1       0
  5435.7     .16       0
Bank Sta=4974,5045.7
XS Rating Curve= 0 ,0
Exp/Cntr=0.3,0.1

Type RM Length L Ch R = 1 ,14188   ,359,359,359
BEGIN DESCRIPTION:
PAISANO CREEK 16.0
END DESCRIPTION:
XS GIS Cut Line= 3
       2291937.7     13267846.82      2291687.72     13267246.85
      2291637.72     13267046.87
#Sta/Elev= 30
    4368  142.41  4530.5  137.95  4613.3  137.05  4725.5  137.71  4748.7   137.2
  4833.8  131.88  4866.3  130.65  4873.3  129.77  4920.5  128.03  4926.4  127.16
  4931.8  127.75  4942.1  126.17  4974.1  126.14  4985.5  124.91  5003.1  121.57
  5008.7  122.59  5015.2     125  5028.3  126.06  5069.5  128.89  5110.7  133.72
  5118.5  135.54  5131.3  136.45  5141.7  138.82    5152  139.55  5159.7  141.22
  5164.8  141.26  5200.9  147.69  5213.8   148.6  5221.5  150.49  5224.1  150.49
#Mann= 4 ,-1 , 0
    4368     .12       0  4974.1     .07       0  5028.3     .12       0
  5224.1      .1       0
Bank Sta=4974.1,5028.3
XS Rating Curve= 0 ,0
Exp/Cntr=0.3,0.1

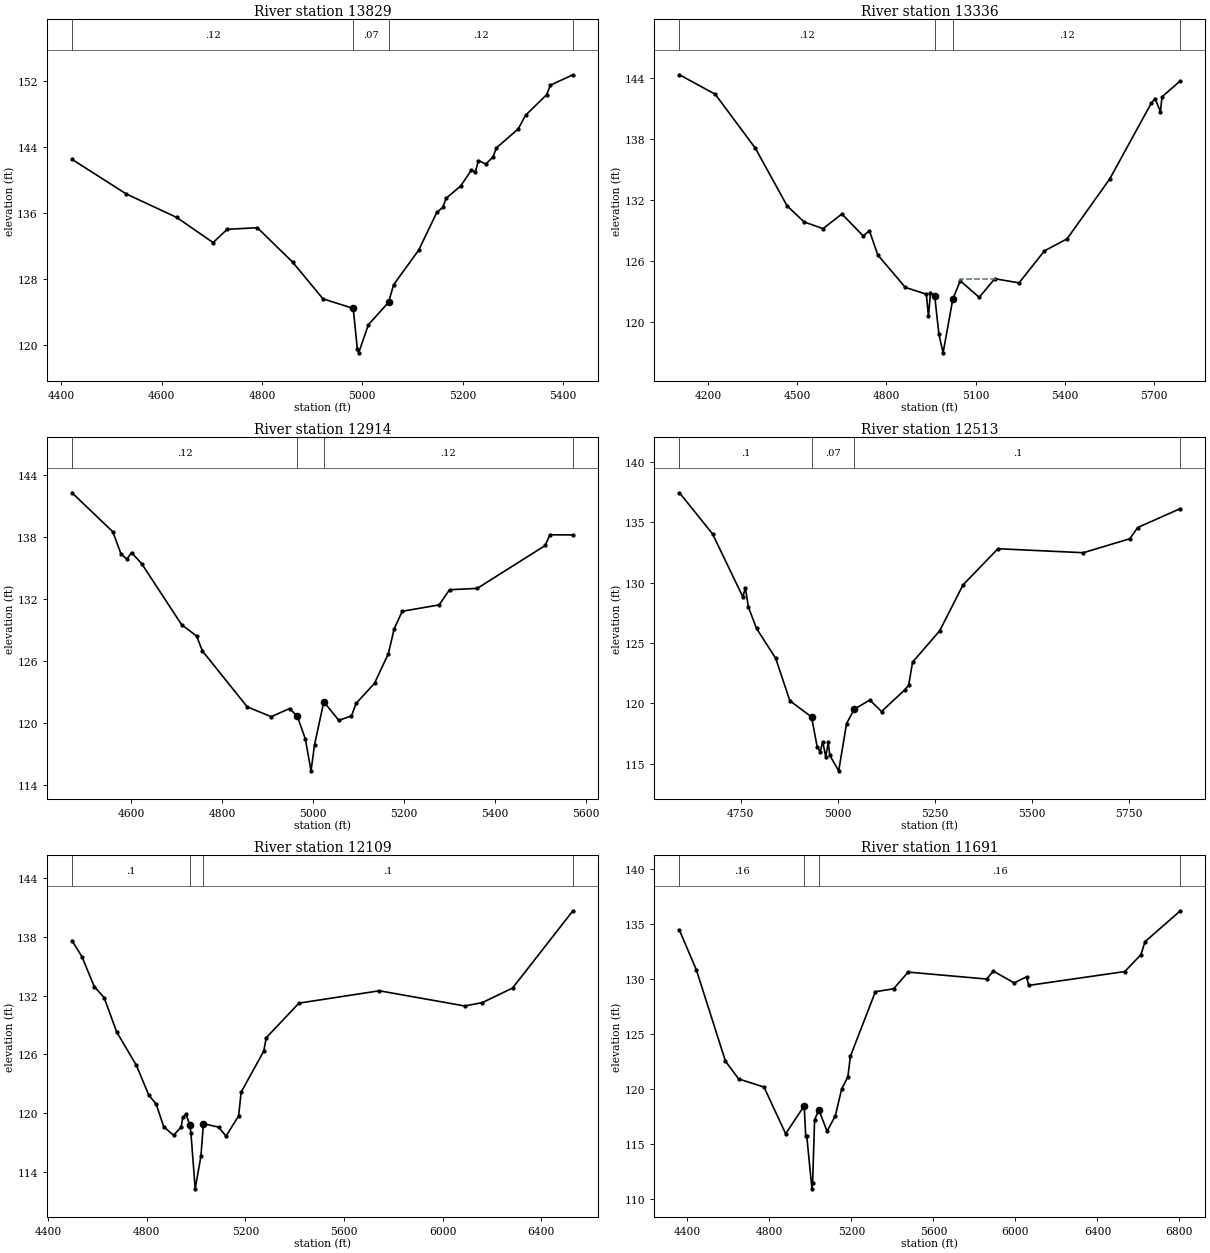
Type RM Length L Ch R = 1 ,13829   ,493,493,493
BEGIN DESCRIPTION:
PAISANO CREEK 15.0
END DESCRIPTION:
XS GIS Cut Line= 3
      2291973.82     13267844.36      2292049.34     13267120.42
      2291831.68     13266959.76
#Sta/Elev= 30
  4421.5  142.49  4529.6   138.3  4630.1  135.46  4702.8  132.41  4730.7  134.02
    4791  134.21  4861.4  130.03  4921.7   125.6    4982  124.44  4990.1  119.56
  4992.9  119.06  5012.2  122.46  5052.4  125.18  5062.5   127.3  5112.7  131.52
  5148.6  136.07  5160.7  136.68  5166.9  137.76  5196.2  139.27    5217  141.14
  5225.4  140.98  5231.7  142.34  5246.3  141.92  5260.9   142.8  5267.1  143.86
    5311  146.18  5325.4  147.82  5367.4  150.31  5375.1  151.47  5419.9  152.73
#Mann= 4 ,-1 , 0
  4421.5     .12       0    4982     .07       0  5052.4     .12       0
  5419.9      .1       0
Bank Sta=4982,5052.4
XS Rating Curve= 0 ,0
Exp/Cntr=0.3,0.1

Type RM Length L Ch R = 1 ,13336   ,422,422,422
BEGIN DESCRIPTION:
PAISANO CREEK 14.0
END DESCRIPTION:
XS GIS Cut Line= 3
      2291937.73     13267996.85      2292537.72     13267296.85
      2292837.71     13266596.87
#Sta/Elev= 30
  4104.4  144.29  4224.6  142.38  4359.6  137.08    4466  131.44  4523.1  129.86
  4586.8   129.2  4650.4  130.64  4721.8  128.48  4742.6     129  4771.2  126.61
  4863.4  123.44  4934.1  122.77  4941.3   120.6  4947.9   122.9  4962.1  122.61
  4976.4  118.83  4990.4  117.02    5023  122.28  5048.1  124.09  5111.6  122.46
  5164.2  124.29  5245.7  123.88    5331  127.02  5407.1   128.2  5550.4  134.07
    5690   141.5  5702.7  141.96  5720.8  140.68  5726.3  142.13  5787.9   143.7
#Mann= 4 ,-1 , 0
  4104.4     .12       0  4962.1     .07       0    5023     .12       0
  5787.9      .1       0
#XS Ineff= 1 ,-1
 5047.66 5168.59  124.31
Permanent Ineff=
       F
Bank Sta=4962.1,5023
XS Rating Curve= 0 ,0
Exp/Cntr=0.3,0.1

Type RM Length L Ch R = 1 ,12914   ,401,401,401
BEGIN DESCRIPTION:
PAISANO CREEK 13.0
END DESCRIPTION:
XS GIS Cut Line= 3
      2292687.71     13267996.88      2292887.72     13267546.85
      2292987.71      13266946.9
#Sta/Elev= 30
  4470.2  142.29  4559.8  138.51  4577.6  136.39  4590.6  135.84  4600.9  136.49
  4623.4  135.41    4711   129.5  4743.8  128.41  4756.8  126.95  4855.3  121.53
    4908  120.58  4948.3  121.37  4965.2  120.63  4982.9  118.42  4995.4  115.33
  5003.2  117.87  5023.5  122.03  5056.4  120.22  5084.3  120.66  5094.5  121.87
    5135  123.82  5165.4   126.7  5178.1   129.1  5195.8   130.8  5276.9  131.42
  5299.8  132.89  5360.6  133.02  5510.1  137.18  5520.3  138.22  5570.9   138.2
#Mann= 4 ,-1 , 0
  4470.2     .12       0  4965.2     .07       0  5023.5     .12       0
  5570.9      .1       0
Bank Sta=4965.2,5023.5
XS Rating Curve= 0 ,0
Exp/Cntr=0.3,0.1

Type RM Length L Ch R = 1 ,12513   ,404,404,404
BEGIN DESCRIPTION:
PAISANO CREEK 12.0
END DESCRIPTION:
XS GIS Cut Line= 3
      2292887.76     13268046.82      2293187.72     13267796.85
      2293187.72     13266896.82
#Sta/Elev= 30
  4592.6  137.46  4677.8  134.05  4755.9  128.82  4762.4  129.58  4770.2  127.98
  4791.1  126.21  4840.5  123.73    4877  120.21  4932.9  118.87  4947.3   116.4
  4955.1  115.97  4961.6  116.82  4969.4  115.57  4975.9  116.76  4979.8  115.69
  5002.8   114.4  5023.1  118.32  5043.1  119.52  5083.1  120.27  5113.1  119.32
  5173.1  121.12  5183.1   121.5  5193.1  123.41  5263.1  126.02  5323.1  129.82
  5413.1  132.82  5633.1  132.49  5753.1  133.65  5773.1  134.58  5883.1  136.15
#Mann= 4 ,-1 , 0
  4592.6      .1       0  4932.9     .07       0  5043.1      .1       0
  5883.1      .1       0
Bank Sta=4932.9,5043.1
XS Rating Curve= 0 ,0
Exp/Cntr=0.3,0.1

Type RM Length L Ch R = 1 ,12109   ,418,418,418
BEGIN DESCRIPTION:
PAISANO CREEK 11.0
END DESCRIPTION:
XS GIS Cut Line= 3
      2292937.73     13268146.85      2293437.72     13268096.85
      2293737.72     13266596.85
#Sta/Elev= 30
  4496.4   137.6  4536.6  135.97  4586.8  132.91    4627  131.78  4677.3   128.3
  4757.7  124.88  4807.9  121.85  4838.1  120.92  4868.2  118.64  4908.4  117.75
  4938.6  118.57  4946.1  119.57  4958.7  119.92  4973.6  118.84  4978.8  117.99
  4996.1  112.29  5019.3  115.62  5029.5  118.94  5090.7  118.58  5121.3  117.67
  5172.3  119.73  5182.5  122.15  5274.2  126.33  5284.4   127.7    5417  131.23
  5743.3  132.49  6090.1  130.94  6161.5  131.29  6283.8  132.77  6528.6  140.65
#Mann= 4 ,-1 , 0
  4496.4      .1       0  4973.6     .07       0  5029.5      .1       0
  6528.6      .1       0
Bank Sta=4973.6,5029.5
XS Rating Curve= 0 ,0
Exp/Cntr=0.3,0.1

Type RM Length L Ch R = 1 ,11691   ,728,728,728
BEGIN DESCRIPTION:
PAISANO CREEK 10.0
END DESCRIPTION:
XS GIS Cut Line= 3
      2293087.69     13268596.86      2293687.72     13268446.85
      2293987.72     13266646.88
#Sta/Elev= 30
  4361.1  134.43  4443.6  130.83  4585.3  122.53  4649.7  120.91  4773.4  120.17
  4879.1  115.92  4969.3  118.46    4977  115.69  4982.1  115.69  5007.2  110.91
  5010.5  111.41  5020.1  117.17  5040.4  118.12    5081  116.15  5121.5  117.56
  5151.9  119.97  5182.4  121.11    5195  122.98  5316.7  128.85  5405.4  129.11
  5476.4  130.63  5859.1     130    5892  130.72  5993.4  129.65  6054.2   130.2
  6064.4  129.42  6533.2  130.68  6611.8  132.21  6632.1   133.4  6804.4  136.21
#Mann= 4 ,-1 , 0
  4361.1     .16       0  4969.3     .07       0  5040.4     .16       0
  6804.4     .05       0
Bank Sta=4969.3,5040.4
XS Rating Curve= 0 ,0
Exp/Cntr=0.3,0.1

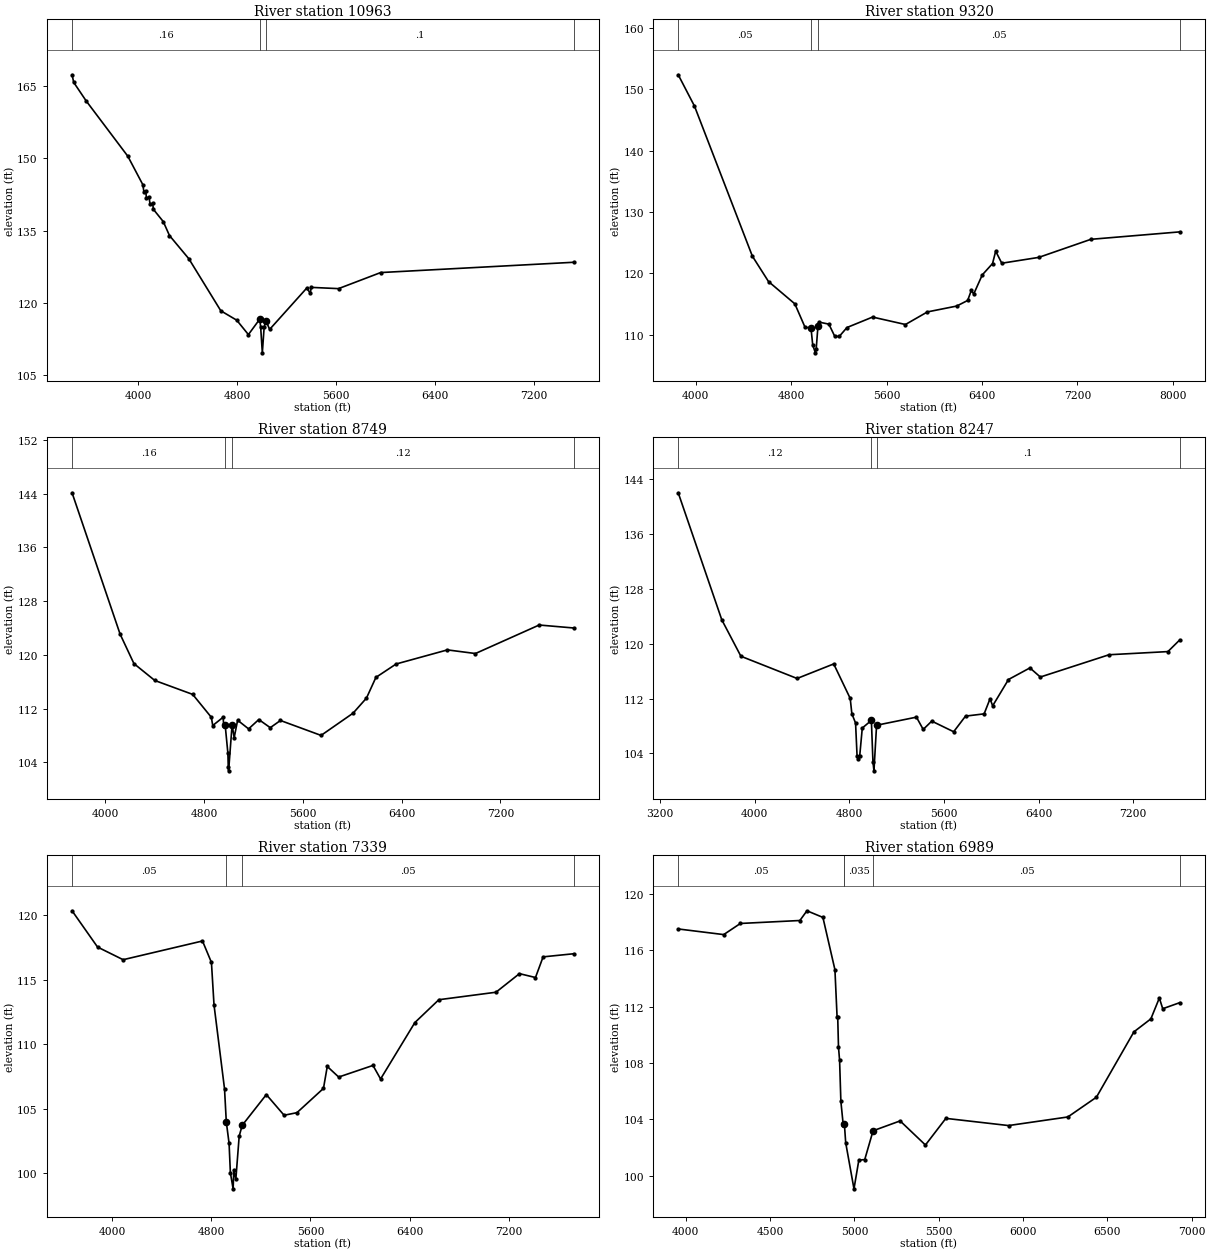
Type RM Length L Ch R = 1 ,10963   ,1643,1643,1643
BEGIN DESCRIPTION:
PAISANO CREEK 9.0
END DESCRIPTION:
XS GIS Cut Line= 3
      2292837.76     13269946.83      2294459.25     13268760.47
      2294343.17     13266720.82
#Sta/Elev= 30
  3467.7  167.29  3481.2  165.71  3581.6  161.88  3918.2  150.42  4039.4  144.53
  4047.9  143.11  4062.4   143.3  4068.7  141.84  4089.6  141.91  4098.1  140.49
  4118.9  140.64  4125.1  139.41  4204.6  136.88  4254.8  133.99  4411.6  129.17
  4669.6   118.4  4798.4  116.45  4892.5  113.47  4984.4  116.68  4991.7     115
  5005.1  109.69    5020  115.12  5034.6  116.34    5064  114.54  5363.4  123.09
  5392.1  122.07  5400.6  123.25  5620.7  122.99  5961.2  126.32  7519.8  128.45
#Mann= 4 ,-1 , 0
  3467.7     .16       0  4984.4     .07       0  5034.6      .1       0
  7519.8      .1       0
Bank Sta=4984.4,5034.6
XS Rating Curve= 0 ,0
Exp/Cntr=0.3,0.1

Type RM Length L Ch R = 1 ,9320    ,571,571,571
BEGIN DESCRIPTION:
PAISANO CREEK 8.0
END DESCRIPTION:
XS GIS Cut Line= 3
      2293987.68     13270996.88      2295076.38     13270179.65
      2294487.71     13267396.83
#Sta/Elev= 30
    3853  152.32  3989.5  147.22  4474.8  122.81  4610.2  118.68  4831.1  115.05
  4916.5  111.24  4966.5  111.12    4981  108.35  5003.2  107.08  5010.2  107.72
  5024.8  111.41    5031  112.09  5116.4  111.75  5166.4  109.74  5203.5  109.75
  5268.3   111.2  5482.9   112.9  5758.6  111.69  5942.9  113.74  6188.2  114.69
  6280.2   115.6  6310.8  117.23  6331.3  116.66  6402.8  119.76    6489  121.61
  6515.3  123.62  6566.4  121.66  6876.5  122.61  7313.7  125.55  8058.7  126.76
#Mann= 4 ,-1 , 0
    3853     .05       0  4966.5    .035       0  5024.8     .05       0
  8058.7     .05       0
Bank Sta=4966.5,5024.8
XS Rating Curve= 0 ,0
Exp/Cntr=0.3,0.1

Type RM Length L Ch R = 1 ,8749    ,502,502,502
BEGIN DESCRIPTION:
PAISANO CREEK 7.0
END DESCRIPTION:
XS GIS Cut Line= 3
      2294287.68     13271096.87      2295545.13     13270471.31
      2294887.73     13267896.88
#Sta/Elev= 30
  3731.6  144.11  4120.8  123.08  4232.7   118.7  4401.8  116.19  4708.6  114.12
  4859.7  110.71  4870.9  109.49  4954.9  110.72  4960.5  109.35  4971.4  109.58
  4971.5  109.57  4993.7  105.36  4996.7  103.25  4999.5  102.75  5027.7   109.6
  5044.5  107.69  5072.5  110.28  5161.3  108.99  5243.9  110.38  5336.8  109.17
  5419.3  110.24  5748.2  108.02  6007.6  111.33  6115.9  113.57  6192.4  116.65
  6355.8  118.64  6771.4  120.74  6998.4   120.2  7514.5  124.44  7793.1     124
#Mann= 4 ,-1 , 0
  3731.6     .16       0  4971.4     .07       0  5027.7     .12       0
  7793.1     .05       0
Bank Sta=4971.5,5027.7
XS Rating Curve= 0 ,0
Exp/Cntr=0.3,0.1

Type RM Length L Ch R = 1 ,8247    ,908,908,908
BEGIN DESCRIPTION:
Mapping XS eaa094dc
END DESCRIPTION:
XS GIS Cut Line= 4
      2294528.34      13271771.2      2295678.51     13271109.31
      2295895.52     13270696.99      2295309.74     13268321.31
#Sta/Elev= 30
  3353.3  142.01  3721.8  123.48  3883.3  118.17  4358.3  114.93  4667.9  117.05
  4807.4  112.02  4821.3  109.79  4852.6  108.43  4865.3  103.64  4875.2  103.24
  4887.4  103.58  4909.4   107.7  4986.3  108.82  4999.5  102.81    5008  101.46
  5030.3  108.11  5367.3  109.29  5424.5   107.5  5496.9  108.71    5682  107.16
  5782.2  109.44  5939.5  109.77  5989.6  111.97  6011.6  110.94  6145.5  114.78
  6326.6  116.47  6414.7  115.14  6995.5  118.39  7493.3  118.85  7593.1  120.55
#Mann= 4 ,-1 , 0
  3353.3     .12       0  4986.3     .07       0  5030.3      .1       0
  7593.1     .16       0
Bank Sta=4986.3,5030.3
XS Rating Curve= 0 ,0
Exp/Cntr=0.3,0.1

Type RM Length L Ch R = 1 ,7339    ,350,350,350
BEGIN DESCRIPTION:
PAISANO CREEK 6.0
END DESCRIPTION:
XS GIS Cut Line= 3
       2295337.7     13272246.87      2296337.72     13271446.85
      2295737.72     13268746.86
#Sta/Elev= 30
    3677  120.33  3882.7  117.52  4089.2  116.54  4729.5  117.99  4801.6  116.33
  4822.4  113.04  4907.2  106.54  4921.6  103.97    4944  102.31  4954.4  100.04
  4976.6   98.79    4982  100.25  4998.6   99.54  5025.5  102.87  5049.8  103.71
  5244.5  106.09  5387.9  104.49  5491.6  104.69  5705.5  106.57  5736.2  108.27
  5828.4  107.45    6105  108.35  6166.4   107.3    6443  111.67  6636.4  113.44
  7097.3  114.02  7286.9  115.46  7416.2  115.16  7477.7  116.76  7723.5     117
#Mann= 4 ,-1 , 0
    3677     .05       0  4921.6    .035       0  5049.8     .05       0
  7723.5      .1       0
Bank Sta=4921.6,5049.8
XS Rating Curve= 0 ,0
Exp/Cntr=0.3,0.1

Type RM Length L Ch R = 1 ,6989    ,400,400,400
BEGIN DESCRIPTION:
Mapping XS ad98101e
END DESCRIPTION:
XS GIS Cut Line= 4
      2295777.89      13272222.6      2296548.73     13271673.98
      2296770.96     13271417.04      2296604.29     13269736.53
#Sta/Elev= 30
  3954.8  117.51  4224.6  117.11  4323.6   117.9  4676.5  118.11  4718.3   118.8
    4813  118.33  4884.3  114.62  4897.2  111.24  4900.9  111.24  4905.4  109.14
    4912  108.18  4919.6  105.27  4933.9  103.57  4940.5  103.65  4948.2  102.34
  4997.3   99.07    5026   101.1  5061.2  101.15  5110.5  103.19    5271  103.89
  5421.1  102.18  5542.3  104.07  5914.1  103.56  6265.8  104.17  6435.2  105.57
  6657.7  110.21  6758.2  111.13  6808.5  112.61  6828.6  111.85  6929.4  112.28
#Mann= 5 ,-1 , 0
  3954.8     .05       0  4940.5      .1       0  4940.5    .035       0
  5110.5     .05       0  6929.4      .1       0
Bank Sta=4940.5,5110.5
XS Rating Curve= 0 ,0
Exp/Cntr=0.3,0.1

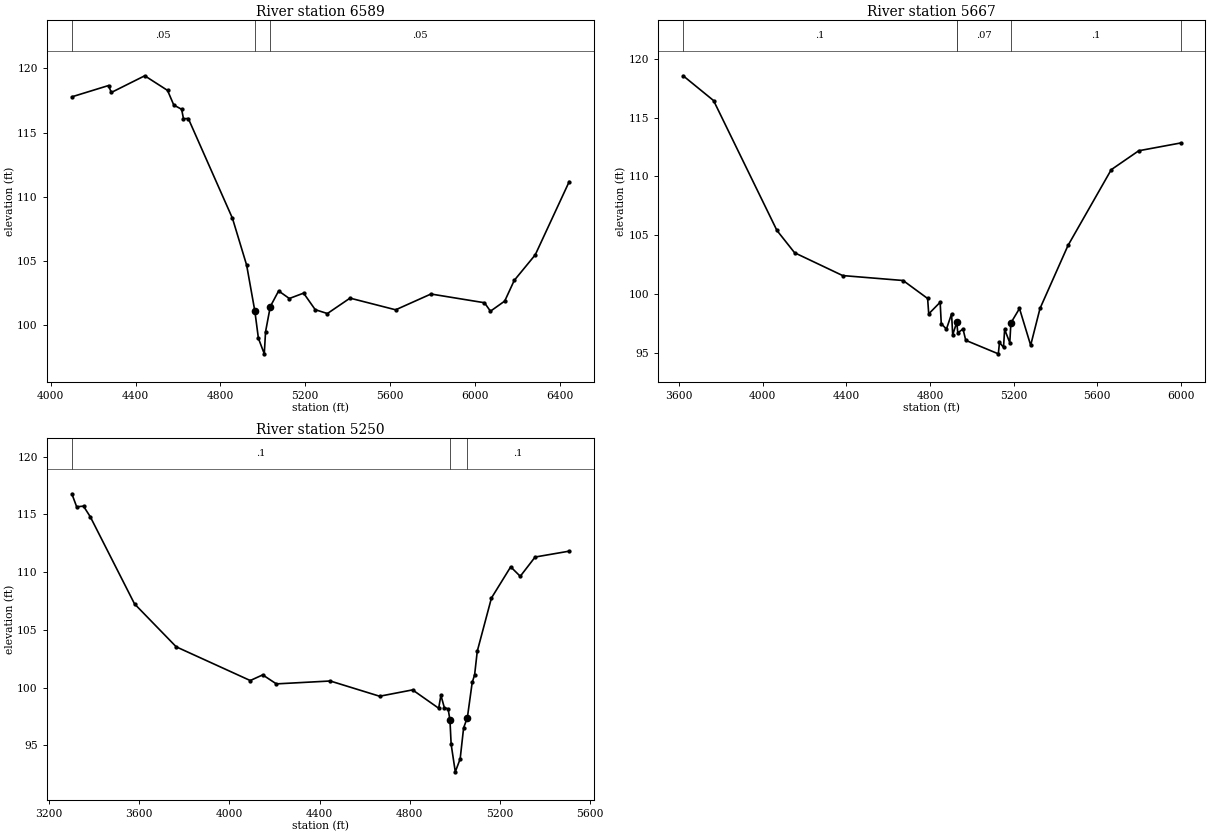
Type RM Length L Ch R = 1 ,6589    ,922,922,922
BEGIN DESCRIPTION:
Mapping XS c47d2e2a
END DESCRIPTION:
XS GIS Cut Line= 4
      2296269.18     13272056.64      2296824.78     13271796.21
      2296937.62     13271744.12      2297649.44     13270303.14
#Sta/Elev= 30
  4099.5  117.79  4272.4  118.67  4285.6  118.13  4443.2  119.43  4550.7  118.29
  4580.1  117.15    4617  116.82  4625.8  116.09  4648.6   116.1  4856.7  108.33
  4923.6  104.68  4962.2  101.11  4979.1   98.98  5006.8   97.77  5012.8   99.49
  5035.1  101.45  5074.4  102.67  5124.9  102.08  5192.2   102.5    5247  101.21
  5304.4  100.91  5411.1  102.11  5626.2   101.2  5792.6  102.43    6045  101.75
  6073.1  101.09  6140.4  101.88  6185.3  103.49  6284.3  105.48  6444.6  111.19
#Mann= 3 , 0 , 0
  4099.5     .05       0  4962.2    .035       0  5035.1     .05       0
Bank Sta=4962.2,5035.1
XS Rating Curve= 0 ,0
Exp/Cntr=0.3,0.1

Type RM Length L Ch R = 1 ,5667    ,417,417,417
BEGIN DESCRIPTION:
Mapping XS 972e748e
END DESCRIPTION:
XS GIS Cut Line= 2
      2296625.14     13271993.42      2298847.33     13271139.27
#Sta/Elev= 30
  3618.6  118.57  3764.2  116.46  4067.4  105.41  4152.1  103.51    4382  101.57
  4671.3  101.15  4788.7   99.62    4794   98.31  4848.7    99.3    4854   97.48
  4878.7   97.01  4903.3   98.31  4908.7   96.53    4928   97.59  4933.3   96.69
    4958   97.03  4971.2   96.06  5127.1   94.91  5132.7   95.88    5152   95.46
  5157.3   96.99    5182   95.86  5187.3   97.54  5228.4   98.77  5281.9   95.64
  5326.6   98.77  5460.6  104.13  5667.6  110.58  5799.2  112.19  5999.3  112.85
#Mann= 5 ,-1 , 0
  3618.6      .1       0    4928     .05       0    4928     .07       0
  5187.3      .1       0  5999.3     .05       0
Bank Sta=4928,5187.3
XS Rating Curve= 0 ,0
Exp/Cntr=0.3,0.1

Type RM Length L Ch R = 1 ,5250    ,625,625,625
BEGIN DESCRIPTION:
PAISANO CREEK 5.0
END DESCRIPTION:
XS GIS Cut Line= 2
      2296703.93     13272119.79        2298771.     13271347.58
#Sta/Elev= 30
  3301.1  116.79  3322.5  115.66  3352.8  115.72  3383.1  114.79  3579.2  107.25
  3764.2  103.53  4092.5  100.61  4147.8   101.1  4208.4  100.32  4447.4  100.57
  4666.5   99.25  4812.7    99.8  4928.5   98.21  4938.4   99.33  4953.5   98.27
  4970.4   98.15  4978.5   97.19  4983.8   95.09  5002.2    92.7  5023.8   93.82
  5039.1   96.51  5055.8    97.4  5077.2  100.44  5087.9   101.1  5099.7  103.15
  5162.6  107.76    5248  110.46  5290.4  109.64  5356.3  111.31  5507.7  111.82
#Mann= 3 , 0 , 0
  3301.1      .1       0  4978.5     .07       0  5055.8      .1       0
Bank Sta=4978.5,5055.8
XS Rating Curve= 0 ,0
Exp/Cntr=0.3,0.1