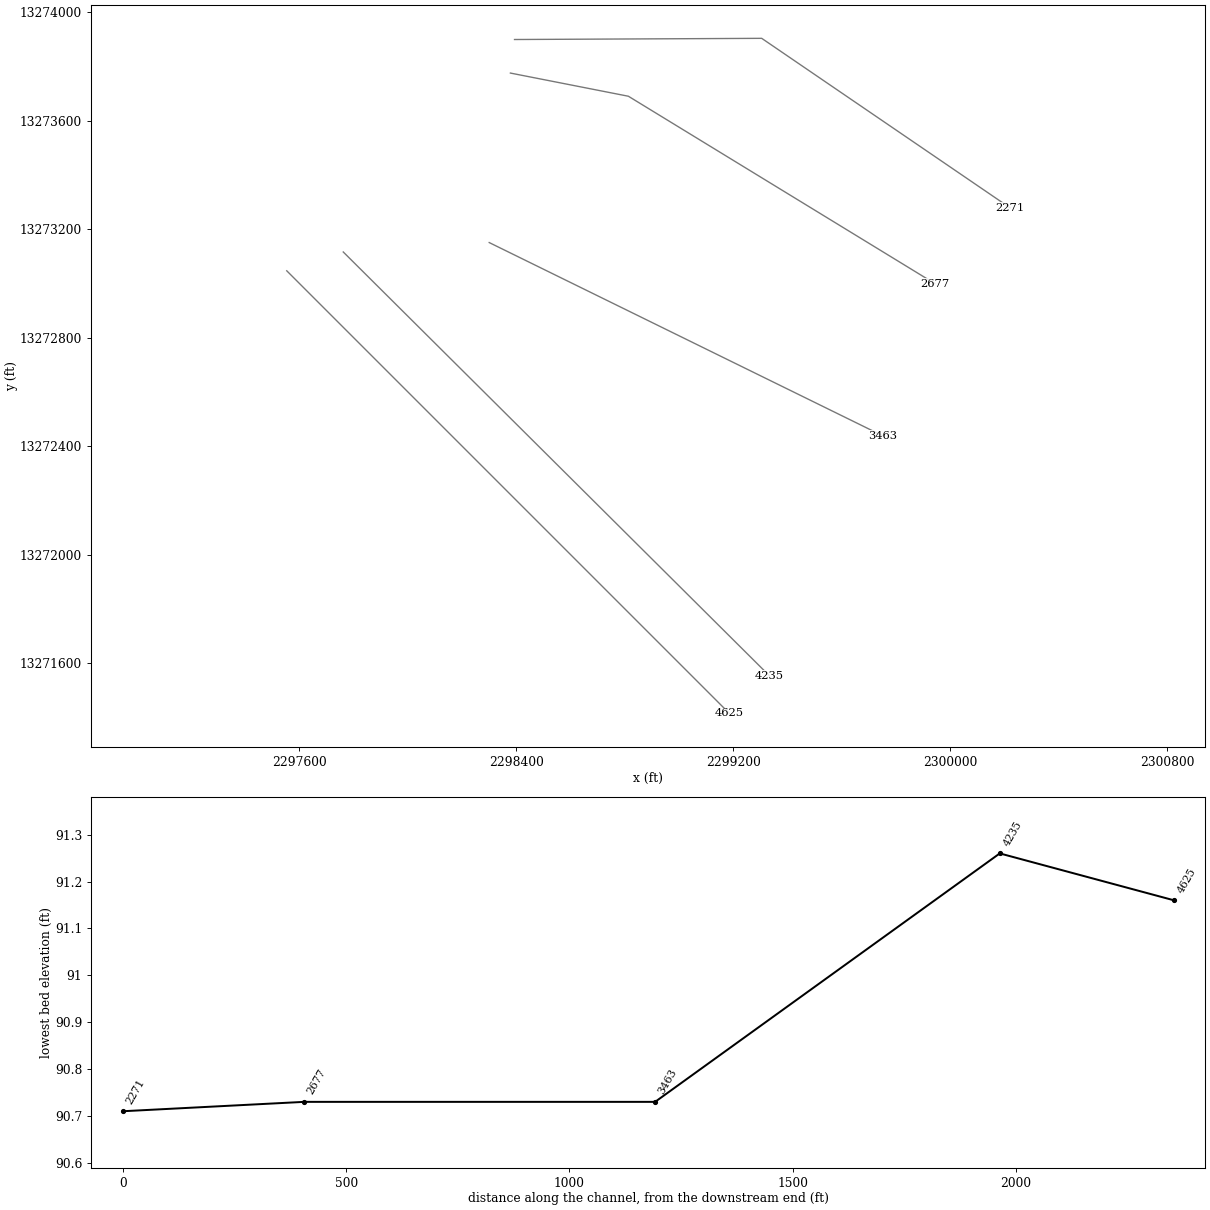
HEC-RAS study PAISANO CREEK.prj: PAISANO CREEK Base Level Engineering

--- PAISANO CREEK.g01 (geometry) --- (continued)

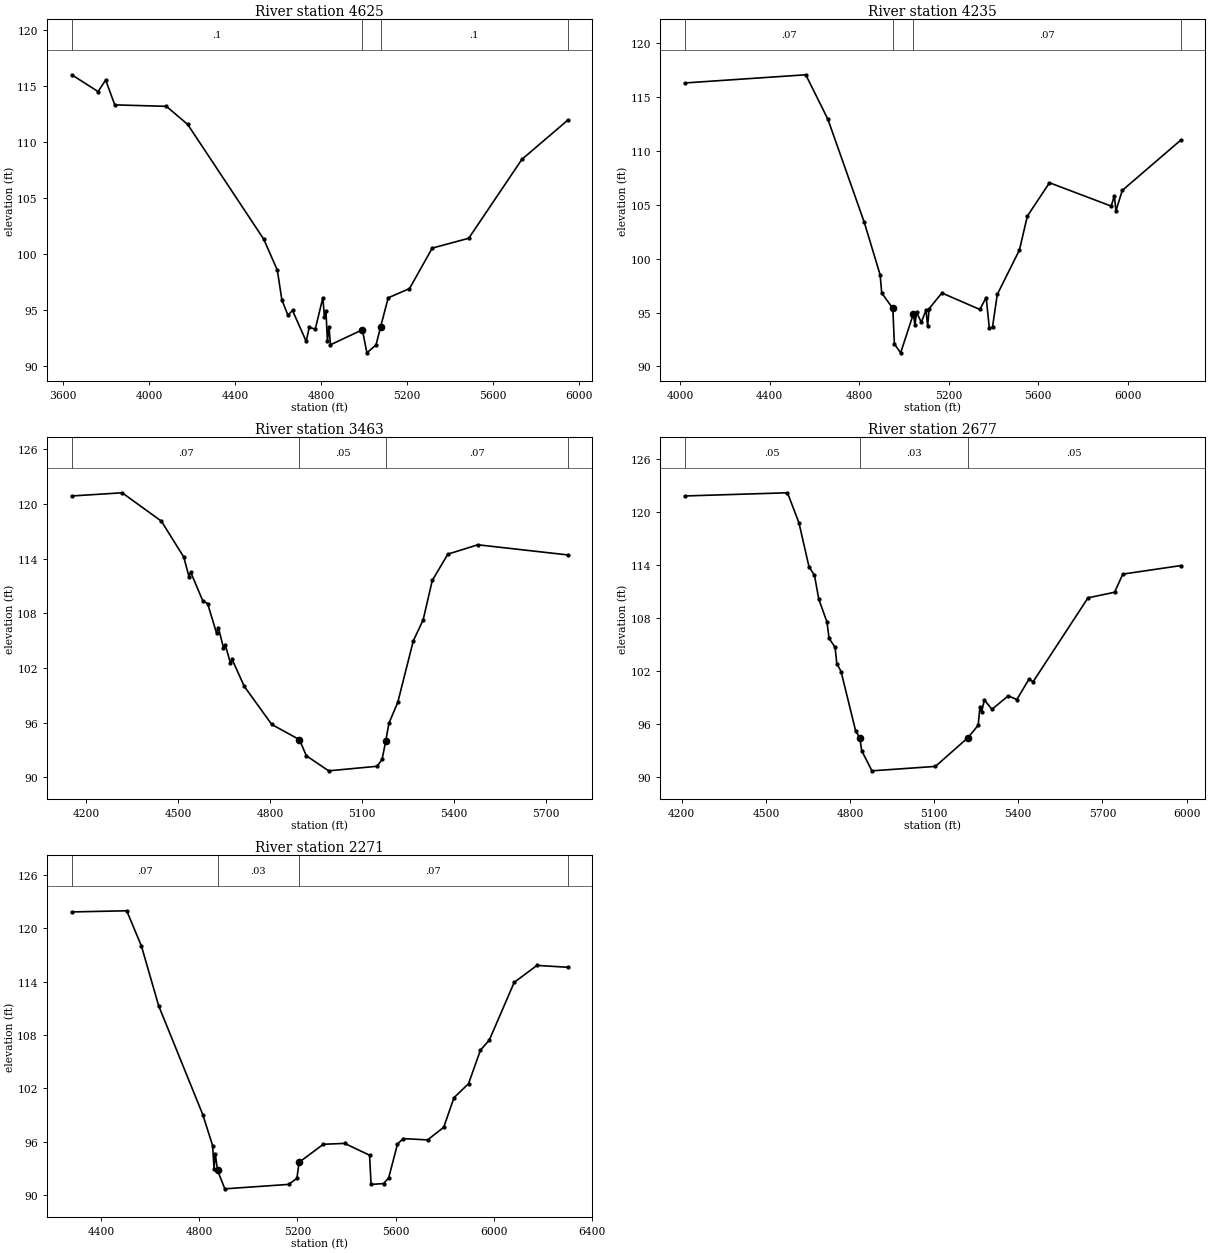
Type RM Length L Ch R = 1 ,4625    ,390,390,390
BEGIN DESCRIPTION:
PAISANO CREEK 4.0
END DESCRIPTION:
XS GIS Cut Line= 2
      2297553.95      13273046.2      2299185.88     13271414.27
#Sta/Elev= 30
  3639.2  116.01  3761.6  114.51    3797  115.54  3839.4  113.32  4079.8  113.19
  4178.8  111.57  4532.4  101.33    4596   98.55  4617.2   95.89  4645.5   94.52
  4666.7   94.95  4730.3   92.19  4744.5   93.43  4772.8   93.29  4808.1    96.1
  4815.2   94.36  4822.3   94.92  4829.3   92.21  4836.4   93.49  4843.5   91.88
    4992   93.22  5012.9   91.16  5055.6   91.87  5076.8   93.48  5112.2   96.08
  5211.2    96.9  5317.2  100.52    5487   101.4  5734.4  108.45  5947.1  111.94
#Mann= 4 ,-1 , 0
  3639.2      .1       0    4992     .07       0  5076.8      .1       0
  5947.1     .05       0
Bank Sta=4992,5076.8
XS Rating Curve= 0 ,0
Exp/Cntr=0.3,0.1

Type RM Length L Ch R = 1 ,4235    ,772,772,772
BEGIN DESCRIPTION:
Mapping XS 5fe4bd90
END DESCRIPTION:
XS GIS Cut Line= 2
      2297762.28     13273115.64      2299333.07     13271553.53
#Sta/Elev= 30
  4020.7  116.33  4561.1  117.09  4660.1  112.95  4822.7  103.37  4893.4    98.5
  4900.5   96.82    4950   95.39  4957.1   92.08  4985.1   91.26  5041.9   94.88
    5049    93.8  5056.1   95.05  5077.3   94.09  5098.5   95.23  5105.6   93.75
  5112.6   95.37  5169.2   96.82  5338.9   95.29  5367.2    96.4  5381.4   93.54
  5395.5   93.65  5416.7   96.68  5515.7  100.81  5551.1  103.96  5650.1  107.06
  5925.8  104.89    5940  105.87    5947  104.45  5975.3  106.35    6236  111.01
#Mann= 4 ,-1 , 0
  4020.7     .07       0    4950     .05       0  5041.9     .07       0
    6236     .05       0
Bank Sta=4950,5041.9
XS Rating Curve= 0 ,0
Exp/Cntr=0.3,0.1

Type RM Length L Ch R = 1 ,3463    ,786,786,786
BEGIN DESCRIPTION:
PAISANO CREEK 3.0
END DESCRIPTION:
XS GIS Cut Line= 2
      2298300.47     13273150.37      2299750.14     13272438.56
#Sta/Elev= 30
  4154.2  120.86  4318.2  121.21  4446.1   118.1  4519.1  114.16    4536  112.01
  4541.6  112.51    4581  109.36  4596.8  109.06  4625.9  105.81  4631.5  106.44
  4648.4  104.23    4654  104.56  4670.9  102.55  4676.5  102.95  4715.9     100
  4805.8   95.81  4895.8   94.15  4918.3   92.38    4991   90.73  5148.7   91.23
  5164.9   91.98  5176.7   93.96  5187.2   95.94  5216.1   98.24  5266.7  104.98
  5298.6  107.26  5328.5   111.6  5379.1  114.48  5476.9  115.51  5769.2   114.4
#Mann= 4 ,-1 , 0
  4154.2     .07       0  4895.8     .05       0  5176.7     .07       0
  5769.2     .05       0
Bank Sta=4895.8,5176.7
XS Rating Curve= 0 ,0
Exp/Cntr=0.3,0.1

Type RM Length L Ch R = 1 ,2677    ,406,406,406
BEGIN DESCRIPTION:
PAISANO CREEK 2.0
END DESCRIPTION:
XS GIS Cut Line= 3
      2298378.59     13273775.37      2298813.64     13273689.92
      2299943.68     13272999.15
#Sta/Elev= 30
    4211  121.79    4577  122.15  4617.8  118.77  4653.9  113.77  4673.3  112.83
  4688.7  110.12  4717.7  107.56  4725.5  105.69  4746.8  104.69  4752.9  102.85
  4768.1  101.95  4820.3   95.21  4834.9   94.47  4841.6   93.01  4878.1   90.73
  5104.5   91.23  5220.9   94.49  5256.9   95.88  5263.5   97.99  5269.3   97.36
  5278.9   98.75  5306.1   97.68  5364.1    99.2    5395   98.79  5437.6  101.07
  5453.1  100.81  5648.6  110.28  5743.4  110.91  5772.6  112.96  5978.8  113.92
#Mann= 3 , 0 , 0
    4211     .05       0  4834.9     .03       0  5220.9     .05       0
Bank Sta=4834.9,5220.9
XS Rating Curve= 0 ,0
Exp/Cntr=0.3,0.1

Type RM Length L Ch R = 1 ,2271    ,0,0,0
BEGIN DESCRIPTION:
PAISANO CREEK 1.0
END DESCRIPTION:
XS GIS Cut Line= 3
      2298393.84     13273899.09      2299305.26     13273903.43
      2300221.08     13273278.42
#Sta/Elev= 30
  4280.9  121.84  4504.8  121.97  4564.8     118  4634.8   111.3  4814.8   99.05
  4854.8   95.57  4860.6   92.98  4865.6   94.66  4874.8    92.8  4904.5   90.71
  5164.8   91.21  5198.2   91.89  5207.1   93.69  5305.9   95.72  5392.7   95.82
  5494.3   94.49  5500.4   91.21  5551.2    91.3  5572.2   91.95  5608.1   95.74
  5631.2   96.36  5730.7   96.21  5796.4   97.63  5838.4  100.96  5897.5  102.53
  5946.1   106.3  5982.3  107.44  6083.6  113.92  6176.4  115.83  6301.1  115.62
#Mann= 4 ,-1 , 0
  4280.9     .07       0  4874.8     .03       0  5207.1     .07       0
  6301.1      .1       0
Bank Sta=4874.8,5207.1
XS Rating Curve= 0 ,0
Exp/Cntr=0.3,0.1

Chan Stop Cuts=-1
Use User Specified Reach Order=0
Composite Channel Slope=5