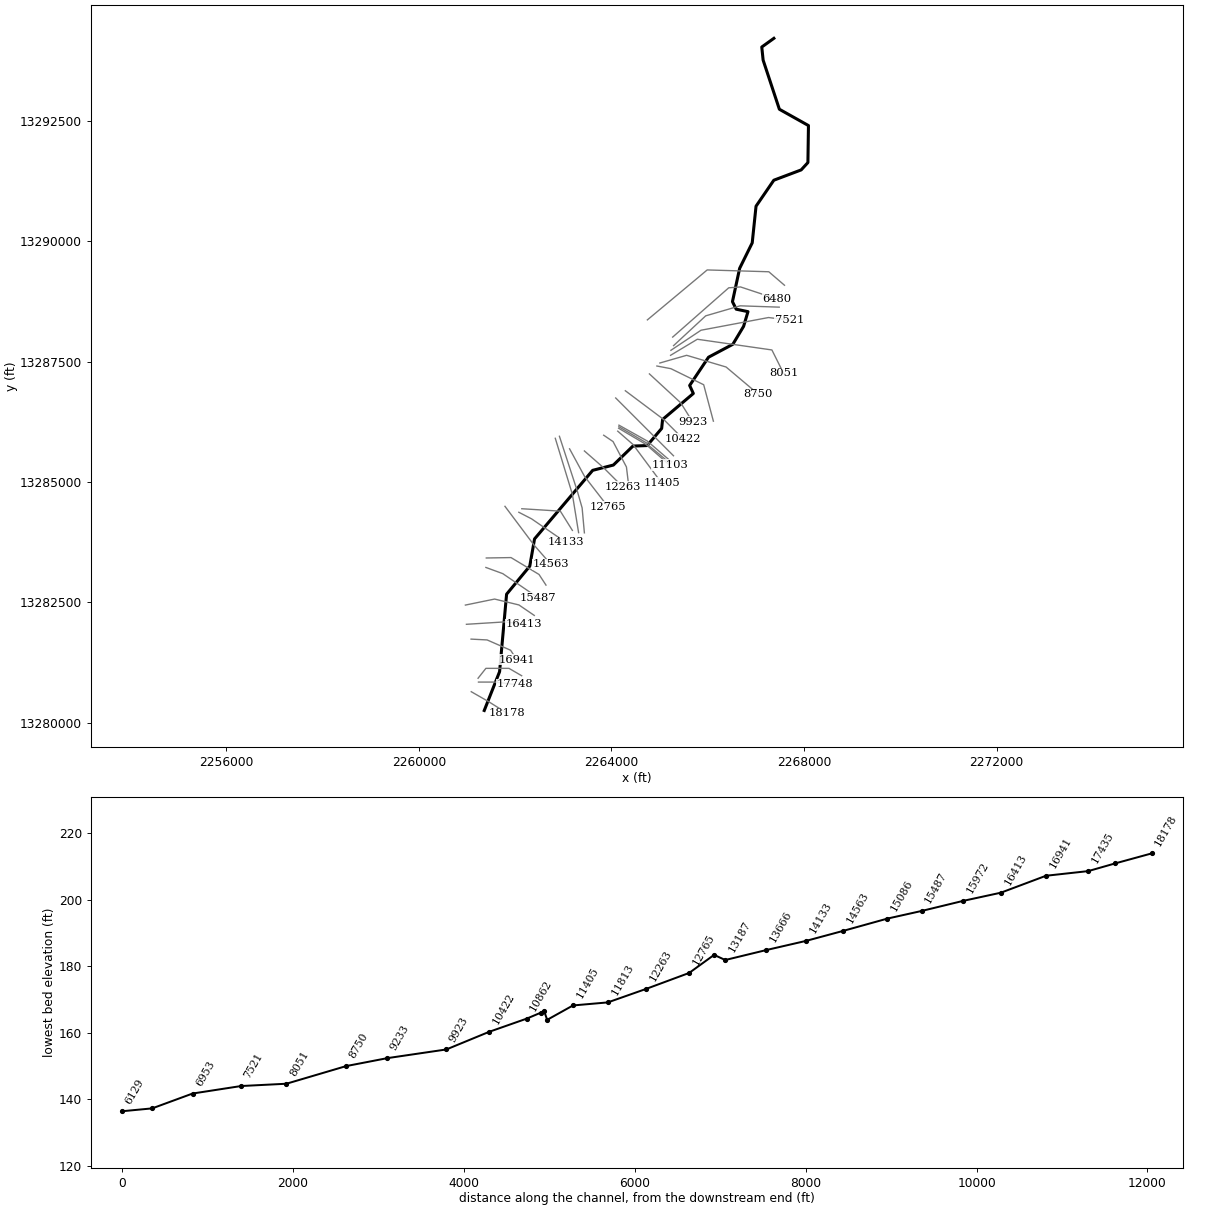
--- UNT002 IN NURI.prj (project) ---

Proj Title=UNT002 IN NURI Base Level Engineering
Current Plan=p01
Default Exp/Contr=0.3,0.1
English Units
Geom File=g01
Flow File=f01
Plan File=p01
Y Axis Title=Elevation
X Axis Title(PF)=Main Channel Distance
X Axis Title(XS)=Station
BEGIN DESCRIPTION:
UNT002 IN NURI
END DESCRIPTION:
DSS Export Rating Curves= 0
DSS Export Rating Curve Sorted= 0
DSS Export Volume Flow Curves= 0
DXF OffsetX= 0
DXF OffsetY= 0
DXF ScaleX= 1
DXF ScaleY= 10

--- UNT002 IN NURI.p01 (plan) ---

Plan Title=Multiple Run
Short Identifier=Multiple
Geom File=g01
Flow File=f01
Subcritical Flow
K Sum by GR= 0
Std Step Tol= 0.01
Critical Tol= 0.01
Num of Std Step Trials= 20
Max Error Tol= 0.3
Flow Tol Ratio= 0.001
Split Flow NTrial= 30
Split Flow Tol= 0.02
Split Flow Ratio= 0.02
Log Output Level= 0
Friction Slope Method= 1
Unsteady Friction Slope Method= 2
Unsteady Bridges Friction Slope Method= 1
Parabolic Critical Depth
Global Vel Dist=  1 , 1 , 1
Global Log Level= 0
CheckData=True
Encroach Param= -1, 0, 0, 0
BEGIN DESCRIPTION:
Multiple Run
END DESCRIPTION:

--- UNT002 IN NURI.f01 (steady flow) ---

Flow Title=Multiple
Number of Profiles=7
Profile Names=10-year,25-year,50-year,1pct_min,100-year,1pct_plu,500-year
River Rch & RM= UNT002 IN NURI,Reach-1,18178
     367     525     661     612     827    1119    1316
River Rch & RM= UNT002 IN NURI,Reach-1,13057
     477     688     869     808    1092    1477    1751
River Rch & RM= UNT002 IN NURI,Reach-1,1063
     515     746     946     882    1192    1612    1923
Boundary for River Rch & Prof#=UNT002 IN NURI,Reach-1,1
Up Type=0
Dn Type=3
Dn Slope=0.005
Boundary for River Rch & Prof#=UNT002 IN NURI,Reach-1,2
Up Type=0
Dn Type=3
Dn Slope=0.005
Boundary for River Rch & Prof#=UNT002 IN NURI,Reach-1,3
Up Type=0
Dn Type=3
Dn Slope=0.005
Boundary for River Rch & Prof#=UNT002 IN NURI,Reach-1,4
Up Type=0
Dn Type=3
Dn Slope=0.005
Boundary for River Rch & Prof#=UNT002 IN NURI,Reach-1,5
Up Type=0
Dn Type=3
Dn Slope=0.005
Boundary for River Rch & Prof#=UNT002 IN NURI,Reach-1,6
Up Type=0
Dn Type=3
Dn Slope=0.005
Boundary for River Rch & Prof#=UNT002 IN NURI,Reach-1,7
Up Type=0
Dn Type=3
Dn Slope=0.005

--- UNT002 IN NURI.g01 (geometry) ---

Geom Title=Existing Conditions
Program Version=4.10

River Reach=UNT002 IN NURI  ,Reach-1
Reach XY= 30
      2261357.72     13280256.86      2261676.03     13281062.76
      2261821.51       13282672.      2262303.07     13283254.41
      2262402.08     13283819.87      2263609.39     13285244.33
      2264039.23     13285353.96      2264445.55     13285748.31
      2264740.53     13285758.79      2265042.14     13286114.24
      2265061.27     13286299.99      2265699.68     13286840.17
      2265623.54     13287006.93      2266015.13     13287593.36
      2266520.31     13287861.86      2266743.51      13288234.2
      2266834.59     13288539.84      2266590.16     13288590.97
      2266512.18     13288747.21      2266661.77     13289439.88
      2266922.63     13289967.86      2267002.01     13290729.69
      2267371.26     13291269.16      2267939.46      13291483.5
      2268079.34     13291636.15       2268090.7     13292404.46
      2267486.73     13292743.04      2267149.48     13293762.58
       2267121.1     13294035.34      2267372.42     13294215.92

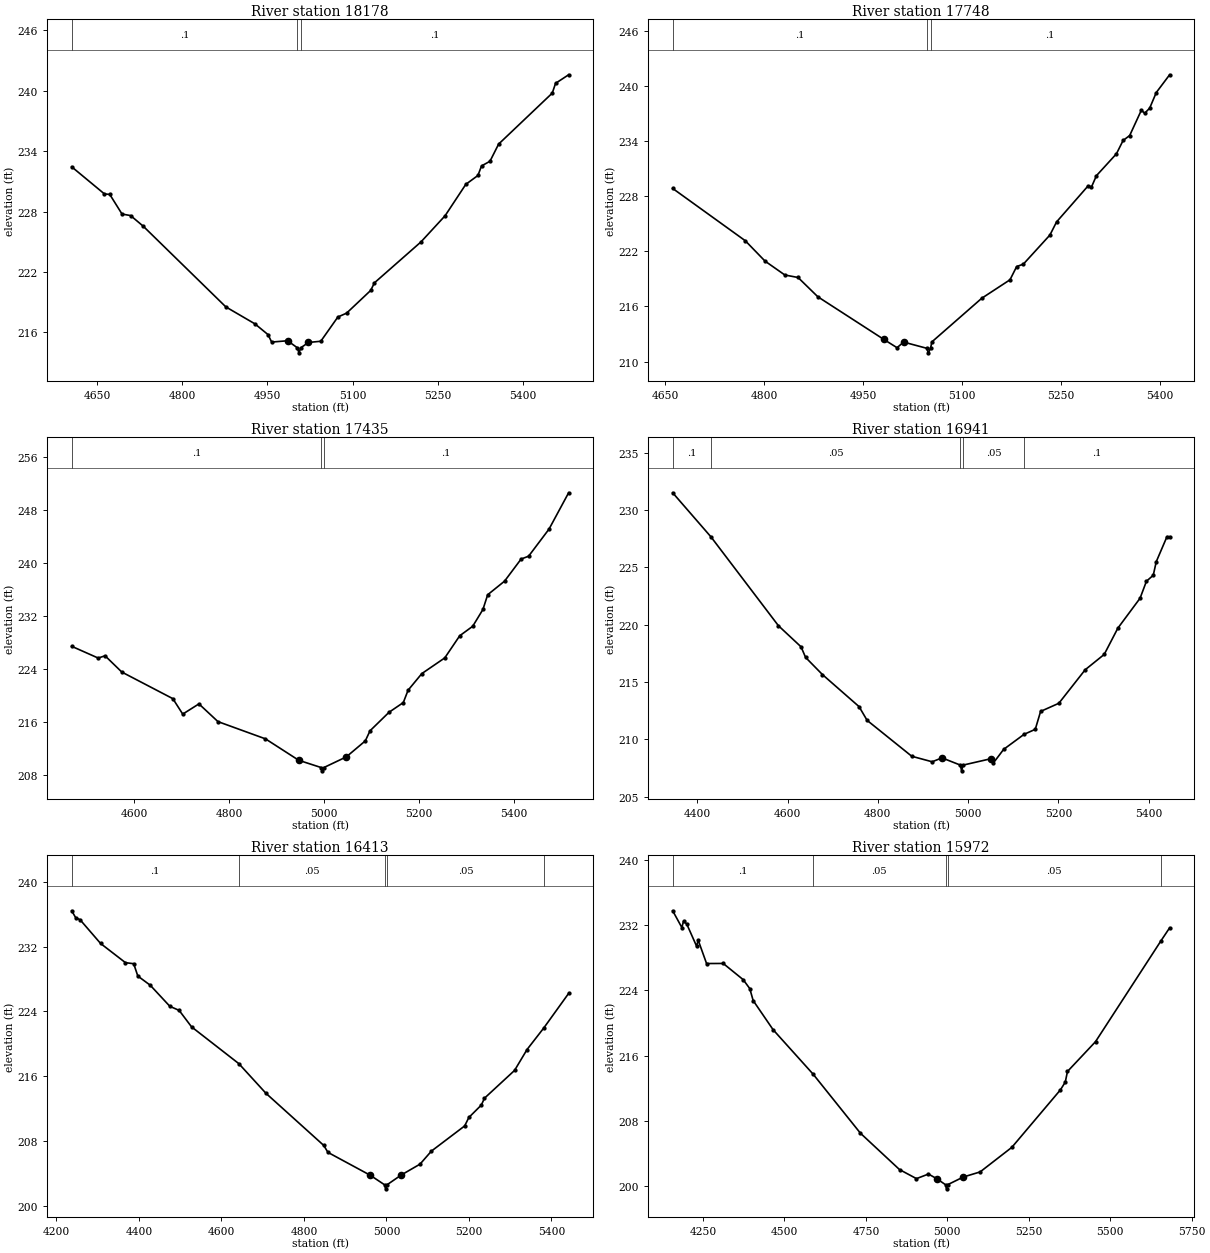
Type RM Length L Ch R = 1 ,18178   ,430,430,430
BEGIN DESCRIPTION:
UNT002 IN NURI 28.0
END DESCRIPTION:
XS GIS Cut Line= 3
      2261087.69     13280646.87      2261437.72     13280446.85
      2261837.68     13280196.88
#Sta/Elev= 30
  4605.5  232.45  4663.1  229.76  4672.5  229.71  4694.1  227.76  4709.2  227.61
  4731.5  226.55  4876.9  218.54    4928  216.86  4951.1  215.79  4957.5  215.05
  4985.6  215.18  5002.8  214.48  5005.5  213.98  5008.8  214.48  5022.2  215.01
    5044  215.13  5074.1  217.54  5089.4  217.92  5131.9  220.18  5138.4  220.93
  5220.3  224.99  5262.8  227.59  5299.3  230.71  5320.6  231.59    5327  232.54
  5341.8     233  5357.1  234.71  5451.5  239.77  5457.3  240.74  5480.3  241.59
#Mann= 3 ,-1 , 0
  4605.5      .1       0  5002.8     .07       0  5008.8      .1       0
Bank Sta=4985.6,5022.2
XS Rating Curve= 0 ,0
Exp/Cntr=0.3,0.1

Type RM Length L Ch R = 1 ,17748   ,313,313,313
BEGIN DESCRIPTION:
UNT002 IN NURI 27.0
END DESCRIPTION:
XS GIS Cut Line= 3
      2261237.73     13280846.85      2261587.72     13280846.85
      2261987.72     13280796.86
#Sta/Elev= 30
  4661.1  228.84  4771.1  223.15  4801.1  220.93  4831.1  219.42  4851.1  219.15
  4881.1  217.05  4981.1  212.41  5001.1  211.51  5011.1  212.12  5045.9  211.45
  5048.6  210.95  5051.9  211.45  5053.9  212.14  5129.5  216.89  5172.3   218.9
  5182.4  220.34  5192.5   220.6  5232.8  223.77  5242.9   225.2  5290.8  229.13
  5295.8     229  5303.3  230.23  5333.6  232.61  5343.7  234.06  5353.7   234.6
  5371.4  237.36  5376.4  237.02    5384  237.58    5394  239.28  5414.2  241.21
#Mann= 3 ,-1 , 0
  4661.1      .1       0  5045.9     .07       0  5051.9      .1       0
Bank Sta=4981.1,5011.1
XS Rating Curve= 0 ,0
Exp/Cntr=0.3,0.1

Type RM Length L Ch R = 1 ,17435   ,494,494,494
BEGIN DESCRIPTION:
UNT002 IN NURI 26.0
END DESCRIPTION:
XS GIS Cut Line= 4
       2261229.3     13280926.67      2261391.77      13281131.9
      2261870.72      13281131.9      2262134.31     13280978.84
#Sta/Elev= 30
  4469.1  227.42  4524.8  225.65  4539.3  225.99  4574.5  223.54  4681.9  219.53
  4702.7   217.2  4736.8  218.74  4776.8  216.07  4876.8  213.47  4946.8  210.24
  4993.8  209.15  4996.6  208.65  4999.8  209.15  5046.8  210.75  5086.8  213.16
  5096.8  214.69  5136.8  217.48  5166.8  218.94  5176.8   220.8  5205.8  223.31
    5254  225.67  5285.5  229.01  5312.8  230.44  5334.3  232.97  5344.3  235.19
  5379.8  237.24  5414.6  240.57  5430.4     241  5473.4  245.09  5514.6  250.56
#Mann= 3 ,-1 , 0
  4469.1      .1       0  4993.8     .07       0  4999.8      .1       0
Bank Sta=4946.8,5046.8
XS Rating Curve= 0 ,0
Exp/Cntr=0.3,0.1

Type RM Length L Ch R = 1 ,16941   ,528,528,528
BEGIN DESCRIPTION:
UNT002 IN NURI 25.0
END DESCRIPTION:
XS GIS Cut Line= 4
      2261083.84     13281739.13      2261417.43     13281722.03
      2261904.93     13281508.21      2262032.83     13281312.09
#Sta/Elev= 30
  4345.7  231.49  4430.6  227.64  4579.9   219.9    4630  218.06    4640  217.14
  4677.4  215.64  4758.4  212.85  4776.3  211.65  4875.2  208.52  4920.3  208.04
  4942.1  208.38  4982.8  207.75  4985.5  207.25  4988.8  207.75  5049.7   208.3
  5055.2   207.9  5078.6  209.12  5123.8  210.43  5148.7  210.87  5160.5  212.43
  5200.9  213.14  5259.2  216.06  5301.4   217.4  5331.6  219.69  5380.8   222.3
  5394.9  223.78    5410   224.3  5416.6  225.48  5440.3  227.66  5446.2  227.66
#Mann= 5 ,-1 , 0
  4345.7      .1       0  4430.6     .05       0  4982.8     .04       0
  4988.8     .05       0  5123.8      .1       0
Bank Sta=4942.1,5049.7
XS Rating Curve= 0 ,0
Exp/Cntr=0.3,0.1

Type RM Length L Ch R = 1 ,16413   ,441,441,441
BEGIN DESCRIPTION:
UNT002 IN NURI 24.0
END DESCRIPTION:
XS GIS Cut Line= 3
      2260987.71     13282046.85      2261787.72     13282096.85
      2262187.74     13282046.85
#Sta/Elev= 30
    4237   236.4    4247  235.52  4257.1  235.31  4307.1  232.37  4367.3  230.01
  4387.3  229.88  4397.3  228.36  4427.4  227.23    4475  224.63  4497.5  224.13
  4527.6   222.1  4642.2  217.57  4707.9  213.92  4848.2  207.49  4858.2  206.64
  4960.9  203.82  4995.5  202.65  4998.2  202.15  5001.5  202.65  5036.1  203.86
  5081.4  205.19  5109.1   206.8  5189.7   209.9  5199.8  210.94  5230.1  212.47
  5237.6  213.31  5310.7  216.74  5340.9  219.31  5381.4  221.96  5441.7  226.22
#Mann= 5 ,-1 , 0
    4237      .1       0  4642.2     .05       0  4995.5     .03       0
  5001.5     .05       0  5381.4      .1       0
Bank Sta=4960.9,5036.1
XS Rating Curve= 0 ,0
Exp/Cntr=0.3,0.1

Type RM Length L Ch R = 1 ,15972   ,485,485,485
BEGIN DESCRIPTION:
UNT002 IN NURI 23.0
END DESCRIPTION:
XS GIS Cut Line= 4
      2260965.84     13282446.04      2261572.62     13282571.04
      2262077.83     13282448.64      2262396.72     13282230.87
#Sta/Elev= 30
  4156.8  233.74  4184.9  231.69    4190  232.45  4199.6  232.15  4230.1  229.41
  4235.2  230.13  4260.8  227.28  4311.9  227.29  4373.1  225.31  4393.5  224.21
  4403.8  222.75    4465  219.18    4588  213.73  4733.2   206.5  4853.1  202.05
  4905.2  200.94  4941.9   201.5  4966.8  200.95  4994.6  200.19  4997.4  199.69
  5000.6  200.19  5049.1  201.14  5100.5  201.76  5197.9  204.77  5347.1  211.81
    5362  212.76  5368.7  214.06  5454.8  217.71  5656.4   230.1  5682.3  231.65
#Mann= 5 ,-1 , 0
  4156.8      .1       0    4588     .05       0  4994.6     .03       0
  5000.6     .05       0  5656.4      .1       0
Bank Sta=4966.8,5049.1
XS Rating Curve= 0 ,0
Exp/Cntr=0.3,0.1

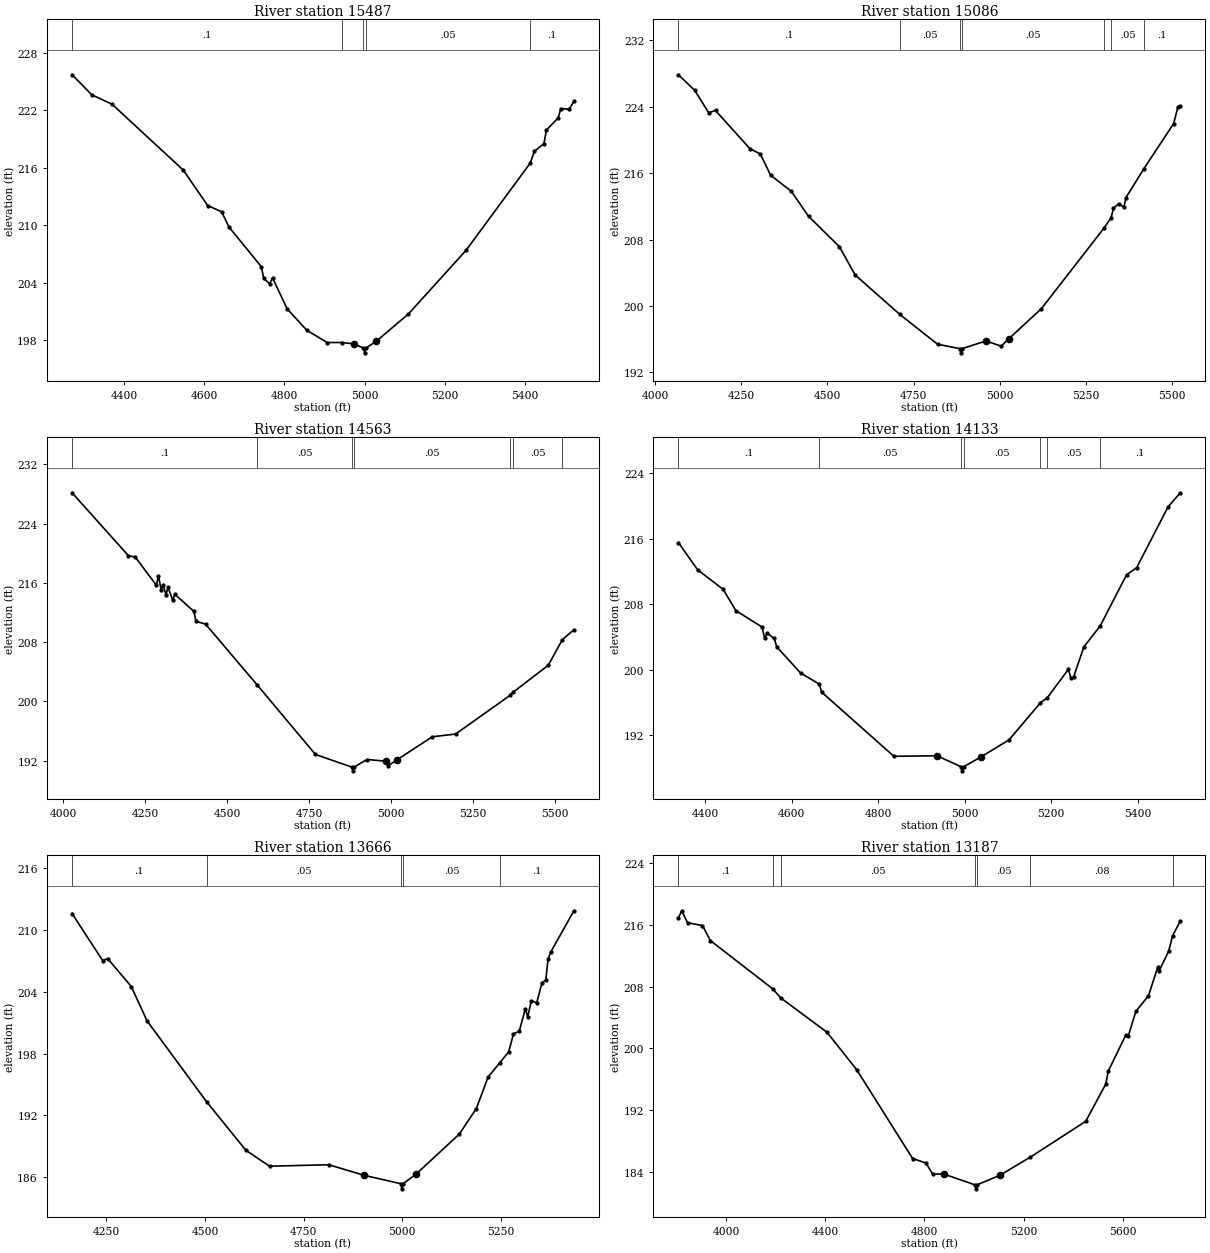
Type RM Length L Ch R = 1 ,15487   ,401,401,401
BEGIN DESCRIPTION:
UNT002 IN NURI 22.0
END DESCRIPTION:
XS GIS Cut Line= 3
      2261391.81     13283227.27      2261742.43     13283098.99
      2262469.38     13282602.96
#Sta/Elev= 30
  4269.6  225.72  4319.1  223.62  4369.5  222.64  4547.4  215.76  4608.4  212.05
  4642.9  211.41  4661.6   209.8  4742.2  205.67  4748.3  204.44  4763.2  203.88
  4770.4  204.49  4806.7  201.26    4856  199.01  4906.8  197.74  4944.2  197.74
  4972.6   197.6  4997.4  197.16  5000.2  196.66  5003.4  197.16  5029.4  197.87
  5109.4  200.71  5253.7  207.38    5414  216.49  5424.4  217.73  5448.1  218.52
  5454.2  219.93    5484  221.24  5490.1  222.18  5511.1  222.12    5523  222.93
#Mann= 5 ,-1 , 0
  4269.6      .1       0  4944.2     .05       0  4997.4     .03       0
  5003.4     .05       0    5414      .1       0
Bank Sta=4972.6,5029.4
XS Rating Curve= 0 ,0
Exp/Cntr=0.3,0.1

Type RM Length L Ch R = 1 ,15086   ,523,523,523
BEGIN DESCRIPTION:
UNT002 IN NURI 21.0
END DESCRIPTION:
XS GIS Cut Line= 4
      2261400.28     13283423.99      2261913.48     13283432.54
      2262495.06     13283081.89       2262639.7     13282860.66
#Sta/Elev= 30
  4067.7  227.84  4115.1  225.95  4155.2  223.27  4175.2  223.54  4275.2  218.93
  4305.2  218.31  4335.2  215.74  4395.2  213.81  4445.2   210.8  4534.9  207.14
  4580.6  203.73  4710.3  198.98    4820  195.39  4884.9  194.86  4887.7  194.36
  4890.9  194.86  4959.6  195.79  5004.4  195.17  5025.8  196.02  5120.9  199.67
  5303.2   209.4  5323.7  210.65  5330.4  211.78  5345.5   212.3  5360.6  211.91
  5366.6  213.06    5419  216.55  5505.1  221.97  5517.3  223.96  5524.4  224.07
#Mann= 7 ,-1 , 0
  4067.7      .1       0  4710.3     .05       0  4884.9     .03       0
  4890.9     .05       0  5303.2      .1       0  5323.7     .05       0
    5419      .1       0
Bank Sta=4959.6,5025.8
XS Rating Curve= 0 ,0
Exp/Cntr=0.3,0.1

Type RM Length L Ch R = 1 ,14563   ,430,430,430
BEGIN DESCRIPTION:
UNT002 IN NURI 20.0
END DESCRIPTION:
XS GIS Cut Line= 3
      2261787.72     13284496.85      2262387.72     13283696.85
      2262737.72     13283296.86
#Sta/Elev= 30
  4026.9  228.16  4198.8  219.67  4219.6  219.49  4284.2  215.68  4290.4  216.95
  4298.8  215.05    4305  215.75  4313.4  214.38  4319.6  215.39  4334.2  213.66
  4340.4  214.46  4398.8  212.14    4405  210.82  4434.2  210.43  4591.2  202.25
  4769.6  192.83  4881.2  191.12  4883.9  190.62  4887.2  191.12  4926.9  192.15
  4984.2  191.92  4990.4  191.26  5019.6  192.14  5126.1  195.22  5197.3  195.59
  5363.5  200.81  5373.5  201.26  5480.1  204.87  5523.4  208.35  5558.4  209.67
#Mann= 7 ,-1 , 0
  4026.9      .1       0  4591.2     .05       0  4881.2     .03       0
  4887.2     .05       0  5363.5      .1       0  5373.5     .05       0
  5523.4      .1       0
Bank Sta=4984.2,5019.6
XS Rating Curve= 0 ,0
Exp/Cntr=0.3,0.1

Type RM Length L Ch R = 1 ,14133   ,467,467,467
BEGIN DESCRIPTION:
UNT002 IN NURI 19.0
END DESCRIPTION:
XS GIS Cut Line= 3
      2262076.01     13284373.31      2262341.11     13284236.49
        2263051.     13283748.97
#Sta/Elev= 30
  4338.8  215.54  4382.8  212.23    4442  209.82  4471.5  207.22    4532  205.21
  4537.9  203.82  4543.6  204.46  4560.1  203.83  4565.8   202.8  4620.9   199.6
  4664.4  198.23  4669.4  197.27  4836.4  189.42  4936.3  189.48  4991.7  188.14
  4994.5  187.64  4997.7  188.14  5036.7  189.31  5102.3  191.42    5175  195.95
  5191.3   196.6  5239.6  200.04  5245.8  198.94  5251.8  199.13  5275.6  202.81
  5312.9  205.33  5374.3  211.62  5397.3  212.46  5469.8   219.9  5498.3  221.63
#Mann= 7 ,-1 , 0
  4338.8      .1       0  4664.4     .05       0  4991.7     .03       0
  4997.7     .05       0    5175      .1       0  5191.3     .05       0
  5312.9      .1       0
Bank Sta=4936.3,5036.7
XS Rating Curve= 0 ,0
Exp/Cntr=0.3,0.1

Type RM Length L Ch R = 1 ,13666   ,479,479,479
BEGIN DESCRIPTION:
UNT002 IN NURI 18.0
END DESCRIPTION:
XS GIS Cut Line= 3
      2262137.69     13284446.86      2262937.72     13284396.85
      2263187.73     13283996.84
#Sta/Elev= 30
  4162.7  211.61  4240.4  207.04  4252.9  207.24    4313  204.52  4353.1  201.18
  4503.8  193.34  4603.6  188.62  4663.7  187.07    4814  187.21  4904.2  186.18
  4996.7  185.37  4999.4  184.87  5002.7  185.37  5035.6   186.3  5145.3  190.19
  5188.3  192.66  5218.4  195.74  5247.9  197.11  5270.3  198.17  5282.7  199.92
  5297.4  200.19  5312.8  202.38  5318.7  201.57  5328.1  203.16  5341.6  202.94
  5355.2   204.9  5364.6  205.15  5370.5  207.18    5377  207.86    5436  211.88
#Mann= 5 ,-1 , 0
  4162.7      .1       0  4503.8     .05       0  4996.7     .03       0
  5002.7     .05       0  5247.9      .1       0
Bank Sta=4904.2,5035.6
XS Rating Curve= 0 ,0
Exp/Cntr=0.3,0.1

Type RM Length L Ch R = 1 ,13187   ,130,130,130
BEGIN DESCRIPTION:
UNT002 IN NURI 17.0
END DESCRIPTION:
XS GIS Cut Line= 3
      2262833.03     13285909.62      2263187.72     13284746.85
      2263317.15     13283950.26
#Sta/Elev= 30
  3808.5  216.91  3821.8  217.78  3844.9  216.24  3905.3  215.87  3936.8  213.94
    4188  207.71  4221.1  206.52  4407.3  202.09  4527.4  197.23  4752.3  185.79
  4805.6  185.22  4833.2  183.79  4877.8  183.79  5004.7  182.38  5007.5  181.88
  5010.7  182.38  5105.2  183.65    5227  185.98  5449.7  190.59  5530.7   195.4
  5540.8  197.08  5611.6  201.75  5621.9  201.66  5652.3  204.81  5702.9  206.81
  5739.8  210.46  5744.9  209.96    5784  212.56  5800.4  214.58  5831.2  216.46
#Mann= 7 ,-1 , 0
  3808.5      .1       0    4188     .08       0  4221.1     .05       0
  5004.7     .03       0  5010.7     .05       0    5227     .08       0
  5800.4      .1       0
Bank Sta=4877.8,5105.2
XS Rating Curve= 0 ,0
Exp/Cntr=0.3,0.1

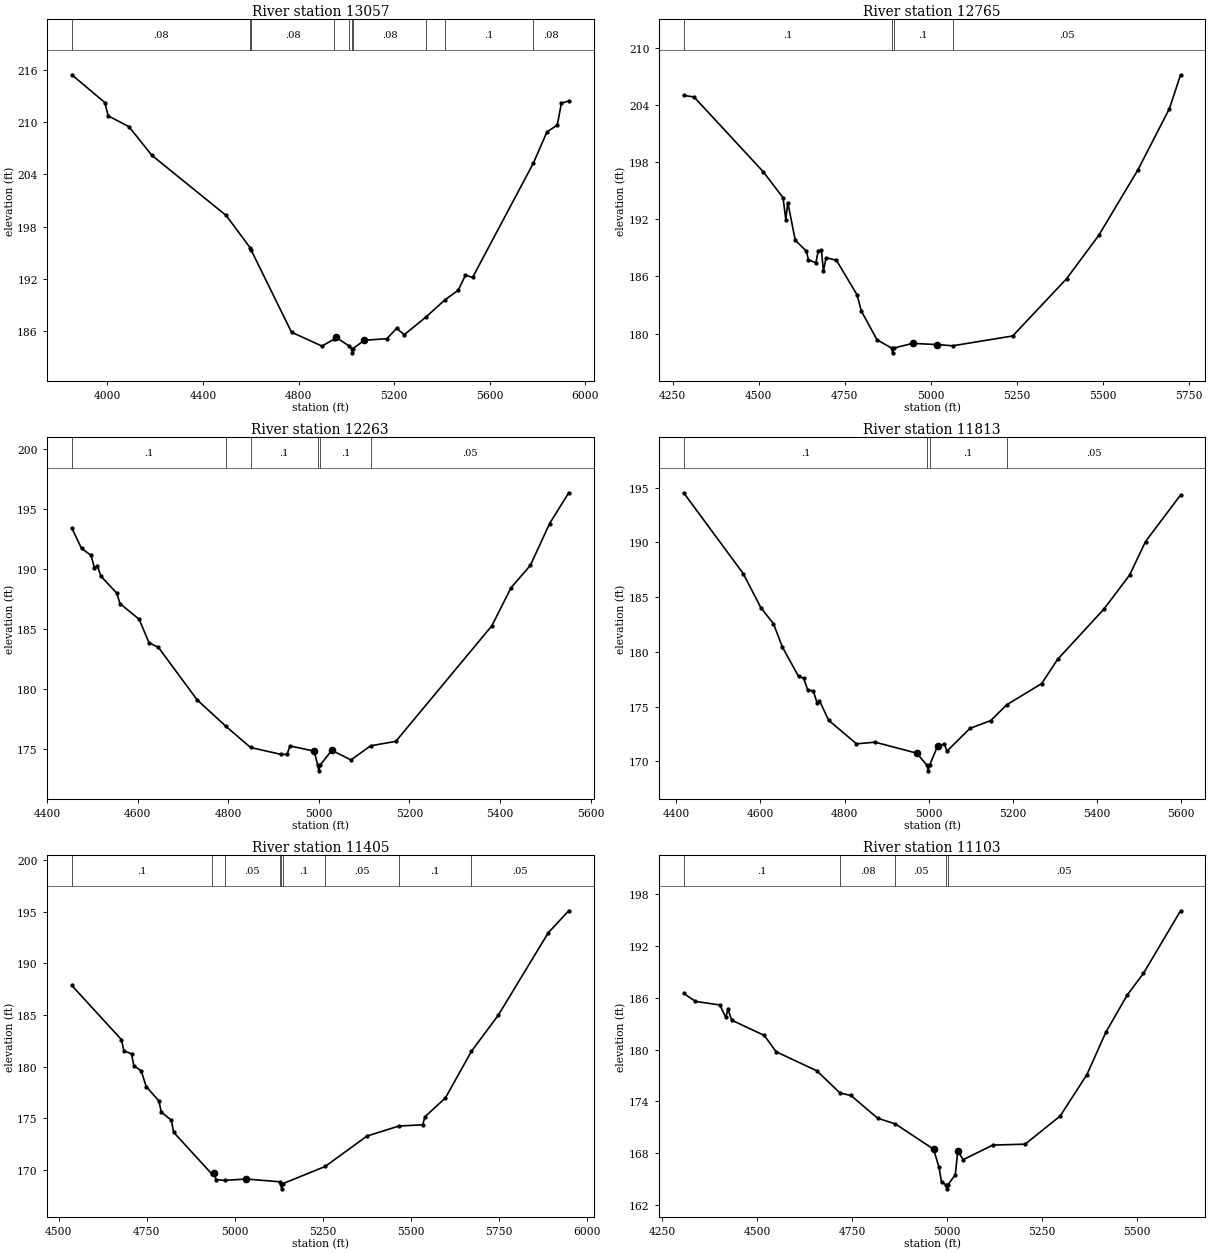
Type RM Length L Ch R = 1 ,13057   ,292,292,292
BEGIN DESCRIPTION:
Mapping XS dc804afc
END DESCRIPTION:
XS GIS Cut Line= 4
      2262918.98     13285951.23      2263288.77     13284818.43
      2263390.33     13284464.27      2263437.21     13283946.04
#Sta/Elev= 30
  3850.7   215.5  3989.2  212.29  4002.6  210.77  4090.1  209.51  4185.8  206.21
    4497  199.27  4598.6   195.5  4601.7  195.27  4770.5  185.81    4898  184.21
  4948.5     185  4956.5  185.22  5013.2   184.2  5022.5  183.93  5025.3  183.43
  5028.5  183.93  5075.2  184.88  5169.7  185.06  5210.4  186.26  5242.4  185.52
  5332.5  187.54  5411.3  189.51  5468.4  190.65  5498.5  192.38  5528.7  192.13
    5783  205.31  5839.9  208.91  5883.2   209.7  5900.2  212.21  5931.1  212.49
#Mann= 10 ,-1 , 0
  3850.7     .08       0  4598.6      .1       0  4601.7     .08       0
  4948.5     .05       0  5013.2     .08       0  5022.5     .03       0
  5028.5     .08       0  5332.5     .05       0  5411.3      .1       0
    5783     .08       0
Bank Sta=4956.5,5075.2
XS Rating Curve= 0 ,0
Exp/Cntr=0.3,0.1

Type RM Length L Ch R = 1 ,12765   ,502,502,502
BEGIN DESCRIPTION:
UNT002 IN NURI 16.0
END DESCRIPTION:
XS GIS Cut Line= 3
       2263129.9     13285690.85      2263442.41     13285115.31
      2263926.21     13284491.05
#Sta/Elev= 30
  4282.1  204.99    4312  204.84  4513.5  196.99  4571.1  194.26  4579.1  191.96
  4584.8  193.76  4606.7  189.79    4639  188.66  4644.7  187.76  4666.5  187.43
  4673.5  188.71  4682.7  188.73  4688.4  186.57  4696.3  187.98  4726.4  187.69
  4786.3  184.07  4798.7  182.37  4844.2  179.36  4886.7  178.49  4889.5  177.99
  4892.7  178.49  4947.6  178.98  5018.2  178.86  5064.1  178.73  5238.7  179.76
  5395.7  185.78    5489  190.32    5603   197.2  5694.5  203.62  5726.8  207.16
#Mann= 4 ,-1 , 0
  4282.1      .1       0  4886.7     .07       0  4892.7      .1       0
  5064.1     .05       0
Bank Sta=4947.6,5018.2
XS Rating Curve= 0 ,0
Exp/Cntr=0.3,0.1

Type RM Length L Ch R = 1 ,12263   ,450,450,450
BEGIN DESCRIPTION:
UNT002 IN NURI 15.0
END DESCRIPTION:
XS GIS Cut Line= 3
       2263437.7     13285646.87      2263837.72     13285296.85
      2264237.71     13284896.87
#Sta/Elev= 30
  4454.6  193.45    4476  191.75  4496.9  191.18  4504.5  190.14  4511.1  190.28
  4518.7  189.44  4553.8  188.02  4560.9  187.15  4603.2  185.84    4625  183.89
  4645.9  183.49  4731.3  179.12  4795.2   176.9  4849.2  175.15  4915.4  174.58
  4929.7  174.57  4936.3  175.28  4989.7  174.84  4997.3   173.7    5000   173.2
  5003.3   173.7  5028.6  174.91    5071  174.11  5114.5  175.29    5170  175.66
  5382.1   185.3  5424.5  188.48    5467  190.33  5509.4  193.81  5551.8  196.39
#Mann= 6 ,-1 , 0
  4454.6      .1       0  4795.2     .16       0  4849.2      .1       0
  4997.3     .07       0  5003.3      .1       0  5114.5     .05       0
Bank Sta=4989.7,5028.6
XS Rating Curve= 0 ,0
Exp/Cntr=0.3,0.1

Type RM Length L Ch R = 1 ,11813   ,408,408,408
BEGIN DESCRIPTION:
UNT002 IN NURI 14.0
END DESCRIPTION:
XS GIS Cut Line= 4
      2263838.46     13285973.39      2264032.88     13285841.46
      2264310.66     13285313.68      2264352.33     13284966.44
#Sta/Elev= 30
  4417.5  194.54  4559.1  187.15  4601.1  184.03    4631  182.57    4652  180.45
  4690.5  177.76  4702.9  177.57  4712.5   176.5  4725.5  176.44  4734.5  175.36
  4740.2  175.54  4762.2  173.74  4828.3  171.59  4872.4  171.74  4971.3  170.74
    4996  169.62  4998.7  169.12    5002  169.62    5021  171.39  5037.4  171.57
  5043.1  170.91  5097.9     173  5147.6  173.72  5185.4  175.16  5268.5   177.1
  5306.1   179.3  5416.9  183.93  5477.3  187.01  5515.3  190.08  5598.6  194.34
#Mann= 4 ,-1 , 0
  4417.5      .1       0    4996     .07       0    5002      .1       0
  5185.4     .05       0
Bank Sta=4971.3,5021
XS Rating Curve= 0 ,0
Exp/Cntr=0.3,0.1

Type RM Length L Ch R = 1 ,11405   ,302,302,302
BEGIN DESCRIPTION:
UNT002 IN NURI 13.0
END DESCRIPTION:
XS GIS Cut Line= 3
      2264129.92     13286057.58      2264446.32     13285781.54
      2265038.16     13284986.41
#Sta/Elev= 30
  4537.4  187.86  4678.4  182.62  4685.1  181.55  4706.9  181.25  4713.5  180.11
  4734.4   179.6  4748.7  178.08  4784.7   176.7  4791.4  175.62  4819.9  174.84
  4826.5  173.67  4935.4  169.62  4940.4  169.76  4947.1  169.09  4971.6  169.02
  5033.3  169.15  5127.8  168.88  5130.5   168.7  5133.2   168.2  5136.5   168.7
  5256.8  170.36  5375.4   173.3    5466  174.27  5533.9  174.39  5540.1  175.16
  5598.5     177  5672.1  181.49  5748.5  184.99  5890.5  192.96  5948.5  195.08
#Mann= 9 ,-1 , 0
  4537.4      .1       0  4935.4     .08       0  4971.6     .05       0
  5127.8      .1       0  5130.5     .04       0  5136.5      .1       0
  5256.8     .05       0    5466      .1       0  5672.1     .05       0
Bank Sta=4940.4,5033.3
XS Rating Curve= 0 ,0
Exp/Cntr=0.3,0.1

Type RM Length L Ch R = 1 ,11103   ,37,37,37
BEGIN DESCRIPTION:
Mapping XS 27ca5993
END DESCRIPTION:
XS GIS Cut Line= 3
      2264148.15     13286118.78      2264711.95     13285785.45
      2265204.11     13285355.62
#Sta/Elev= 30
  4306.1  186.53    4337   185.6  4401.3  185.18    4417  183.75  4422.8  184.66
  4432.6  183.42  4518.4  181.65  4549.6  179.76  4656.8  177.55    4718  174.97
  4746.6  174.69  4816.7  172.06  4863.7  171.39  4964.3  168.46  4978.5  166.35
  4985.2  164.62  4996.4  164.37  4999.2  163.87  5002.4  164.37  5021.3   165.5
  5027.9  168.25  5042.1  167.25    5120  168.94  5205.4  169.05  5297.5  172.31
  5367.7   177.1    5418  182.04    5474  186.33  5516.8  188.85  5614.5   196.1
#Mann= 5 ,-1 , 0
  4306.1      .1       0    4718     .08       0  4863.7     .05       0
  4996.4     .03       0  5002.4     .05       0
Bank Sta=4964.3,5027.9
XS Rating Curve= 0 ,0
Exp/Cntr=0.3,0.1

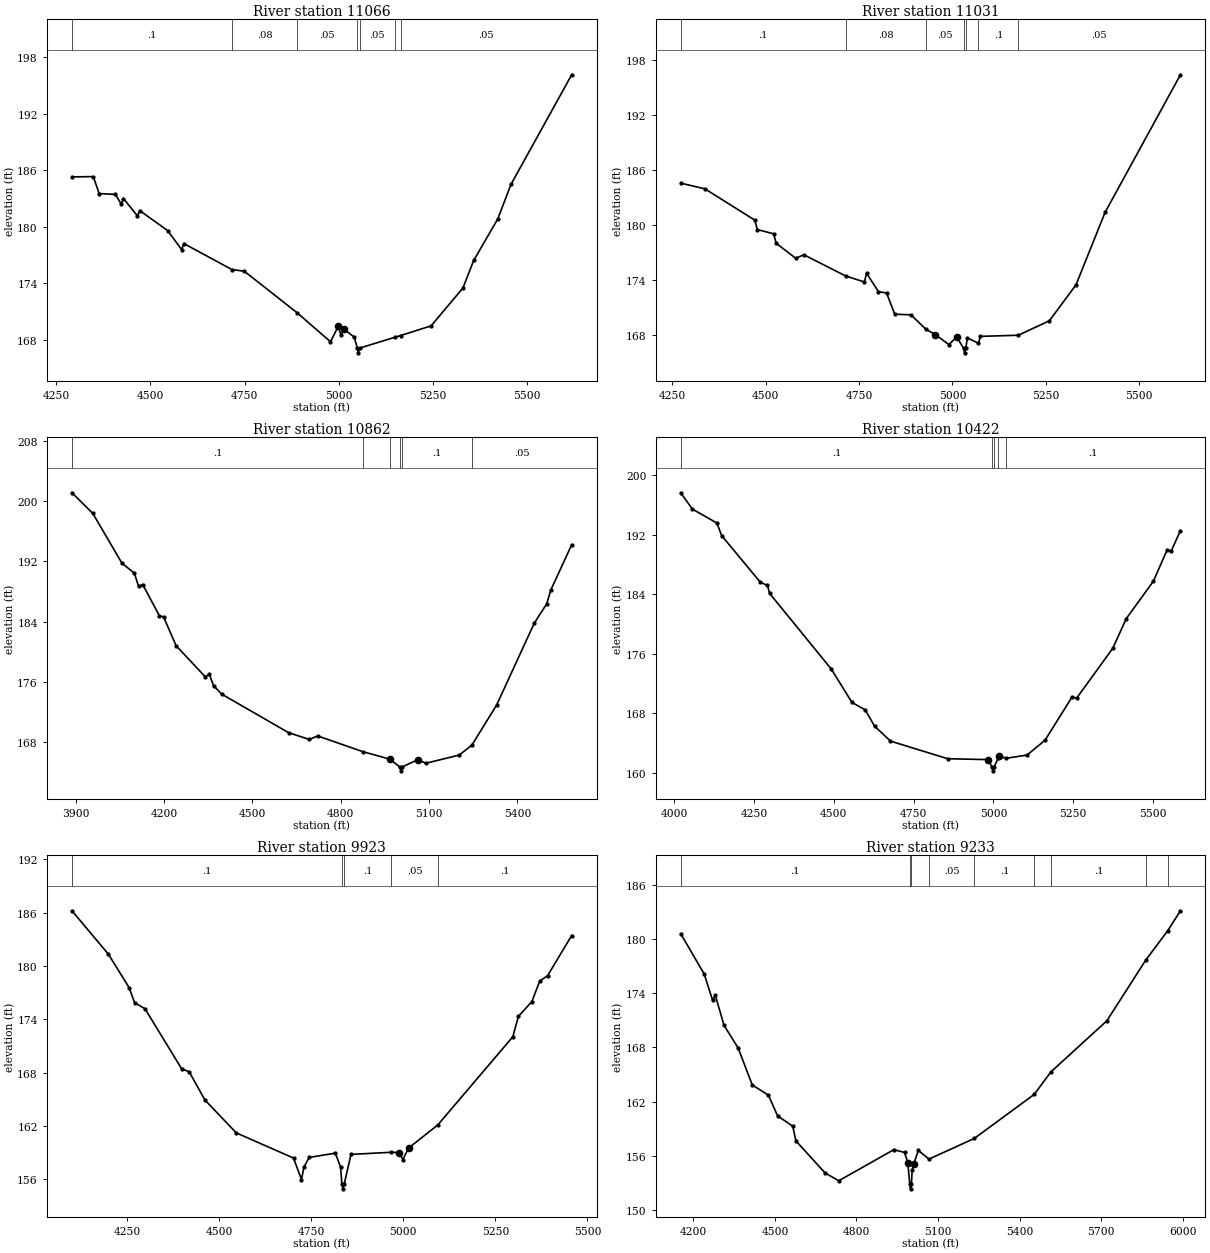
Type RM Length L Ch R = 1 ,11066   ,35,35,35
BEGIN DESCRIPTION:
Mapping XS 6f27de86
END DESCRIPTION:
XS GIS Cut Line= 5
      2264153.33     13286150.04      2264753.61     13285798.47
      2264777.05     13285776.33      2264779.65      13285755.5
      2265223.18     13285386.11
#Sta/Elev= 30
  4291.8  185.31  4348.3  185.34    4364  183.54    4407  183.45  4422.6  182.42
  4428.4  183.01  4465.6  181.17  4471.4  181.74  4545.7  179.61  4582.9  177.59
  4588.7  178.23  4716.4  175.47    4749   175.3  4889.4  170.88  4977.8  167.81
  4998.5  169.44  5005.8  168.49  5012.7  169.15  5040.7  168.31    5049  167.13
  5051.8  166.63    5055  167.13  5149.2  168.29  5163.8  168.47  5244.7  169.49
  5329.3  173.51    5358  176.45  5421.8  180.85  5456.9  184.52  5617.9  196.15
#Mann= 7 ,-1 , 0
  4291.8      .1       0  4716.4     .08       0  4889.4     .05       0
    5049     .03       0    5055     .05       0  5149.2      .1       0
  5163.8     .05       0
#XS Ineff= 2 ,-1
 4925.79 4996.37  168.71 5017.66 5232.77  168.73
Permanent Ineff=
       F       F
Bank Sta=4998.5,5012.7
XS Rating Curve= 0 ,0
Exp/Cntr=0.3,0.1

Type RM Length L Ch R = 1 ,11031   ,169,169,169
BEGIN DESCRIPTION:
Mapping XS f233b23a
END DESCRIPTION:
XS GIS Cut Line= 3
      2264154.69     13286182.56      2264740.59     13285854.46
      2265245.73     13285420.74
#Sta/Elev= 30
  4272.7  184.58  4337.4  183.96    4471  180.54  4477.8  179.51  4521.2  179.05
  4528.3  178.01  4580.5  176.37  4602.2  176.76  4714.2  174.44  4764.3  173.79
    4770  174.74    4802  172.73  4823.7  172.58  4845.4  170.27  4888.7   170.2
  4929.3  168.61  4954.2  168.04  4990.4  166.95  5011.3  167.79  5029.7  166.55
  5032.4  166.05  5035.7  166.55  5039.8  167.68  5069.4   167.1  5074.9  167.85
  5176.1  167.97  5259.3  169.55  5330.6  173.48  5408.5   181.4    5610  196.41
#Mann= 7 ,-1 , 0
  4272.7      .1       0  4714.2     .08       0  4929.3     .05       0
  5029.7     .03       0  5035.7     .05       0  5069.4      .1       0
  5176.1     .05       0
#XS Ineff= 1 ,-1
 5011.53 5197.34167.7633
Permanent Ineff=
       F
Bank Sta=4954.2,5011.3
XS Rating Curve= 0 ,0
Exp/Cntr=0.3,0.1

Type RM Length L Ch R = 1 ,10862   ,440,440,440
BEGIN DESCRIPTION:
UNT002 IN NURI 12.0
END DESCRIPTION:
XS GIS Cut Line= 3
      2264087.72     13286746.86      2264887.72     13285946.85
      2265287.75     13285546.82
#Sta/Elev= 30
  3887.4   201.1  3958.1  198.37  4057.1  191.76  4099.5  190.43  4113.7  188.67
  4127.8  188.93  4184.4  184.78  4198.5  184.63    4241  180.82  4339.9   176.7
  4354.1  177.02  4368.2  175.52  4396.5  174.38  4622.8  169.29  4693.5  168.38
  4721.8  168.85  4875.5  166.76  4965.9  165.78  5001.6  164.72  5004.4  164.22
  5007.6  164.72  5061.2  165.68  5089.5  165.23  5202.6  166.31  5245.5  167.63
  5329.9  172.97  5457.2  183.79  5499.6  186.37  5513.7  188.21  5584.5  194.21
#Mann= 6 ,-1 , 0
  3887.4      .1       0  4875.5     .08       0  4965.9      .1       0
  5001.6     .07       0  5007.6      .1       0  5245.5     .05       0
Bank Sta=4965.9,5061.2
XS Rating Curve= 0 ,0
Exp/Cntr=0.3,0.1

Type RM Length L Ch R = 1 ,10422   ,499,499,499
BEGIN DESCRIPTION:
UNT002 IN NURI 11.0
END DESCRIPTION:
XS GIS Cut Line= 3
       2264287.7     13286896.87      2265087.72     13286296.85
      2265487.71     13285896.86
#Sta/Elev= 30
  4020.3  197.65  4056.8  195.46  4133.9  193.57  4148.5  191.89  4270.3  185.59
  4292.2   185.2  4298.5  184.13  4492.2  173.93  4556.8  169.44  4598.5  168.44
  4627.6  166.26  4677.6  164.24  4856.8  161.87  4983.9  161.75  4995.5  160.74
  4998.2  160.24  5001.5  160.74  5015.7  161.97  5017.2  162.24  5039.7  161.93
  5105.2  162.36  5161.7  164.35  5246.6  170.19  5260.7  170.01  5373.9  176.72
  5416.3  180.72  5501.2  185.75  5543.6  189.89  5557.7  189.86    5586  192.56
#Mann= 5 ,-1 , 0
  4020.3      .1       0  4995.5     .07       0  5001.5      .1       0
  5015.7     .05       0  5039.7      .1       0
Bank Sta=4983.9,5017.2
XS Rating Curve= 0 ,0
Exp/Cntr=0.3,0.1

Type RM Length L Ch R = 1 ,9923    ,690,690,690
BEGIN DESCRIPTION:
UNT002 IN NURI 10.0
END DESCRIPTION:
XS GIS Cut Line= 3
      2264787.73     13287246.85      2265437.72     13286646.85
      2265687.73     13286246.83
#Sta/Elev= 30
  4100.9   186.2  4199.8  181.32  4256.5  177.53  4270.7  175.88  4299.1  175.19
  4398.3  168.46  4419.3  168.09  4461.8  164.93  4546.9  161.24  4702.2  158.41
  4723.8  155.99  4730.6  157.41  4744.8  158.48  4815.6  158.96  4829.8  157.43
  4833.6  155.45  4836.4  154.95  4839.6  155.45  4858.2  158.82    4967  159.06
  4988.4  159.03    4999  158.24  5014.4  159.53  5093.8  162.13  5297.4  172.04
  5312.7  174.34  5349.3     176  5370.5  178.31  5391.7   178.9  5457.2  183.42
#Mann= 5 ,-1 , 0
  4100.9      .1       0  4833.6     .04       0  4839.6      .1       0
    4967     .05       0  5093.8      .1       0
Bank Sta=4988.4,5014.4
XS Rating Curve= 0 ,0
Exp/Cntr=0.3,0.1

Type RM Length L Ch R = 1 ,9233    ,483,483,483
BEGIN DESCRIPTION:
UNT002 IN NURI 9.0
END DESCRIPTION:
XS GIS Cut Line= 4
      2264942.65     13287410.89      2265234.27     13287355.35
      2265914.83     13287022.01      2266116.21     13286265.11
#Sta/Elev= 30
  4153.6  180.56  4240.2   176.1  4270.7  173.21  4280.9  173.76  4312.7  170.44
  4364.8  167.92    4417  163.82  4476.1  162.71    4510  160.41  4565.7  159.27
  4577.2  157.65  4684.2  154.11  4734.7  153.23  4937.3  156.67  4976.7  156.37
  4988.8  155.25  4996.2  152.84  4998.9  152.34  5002.2  152.84  5004.8  154.43
  5011.1  155.11  5027.3  156.59  5066.8  155.63  5233.7  157.92  5453.9  162.79
  5515.2  165.28  5720.7  170.92  5864.1  177.65  5944.5  180.88  5991.5   183.1
#Mann= 9 ,-1 , 0
  4153.6      .1       0  4996.2     .07       0  5002.2      .1       0
  5066.8     .05       0  5233.7      .1       0  5453.9     .16       0
  5515.2      .1       0  5864.1     .05       0  5944.5      .1       0
Bank Sta=4988.8,5011.1
XS Rating Curve= 0 ,0
Exp/Cntr=0.3,0.1

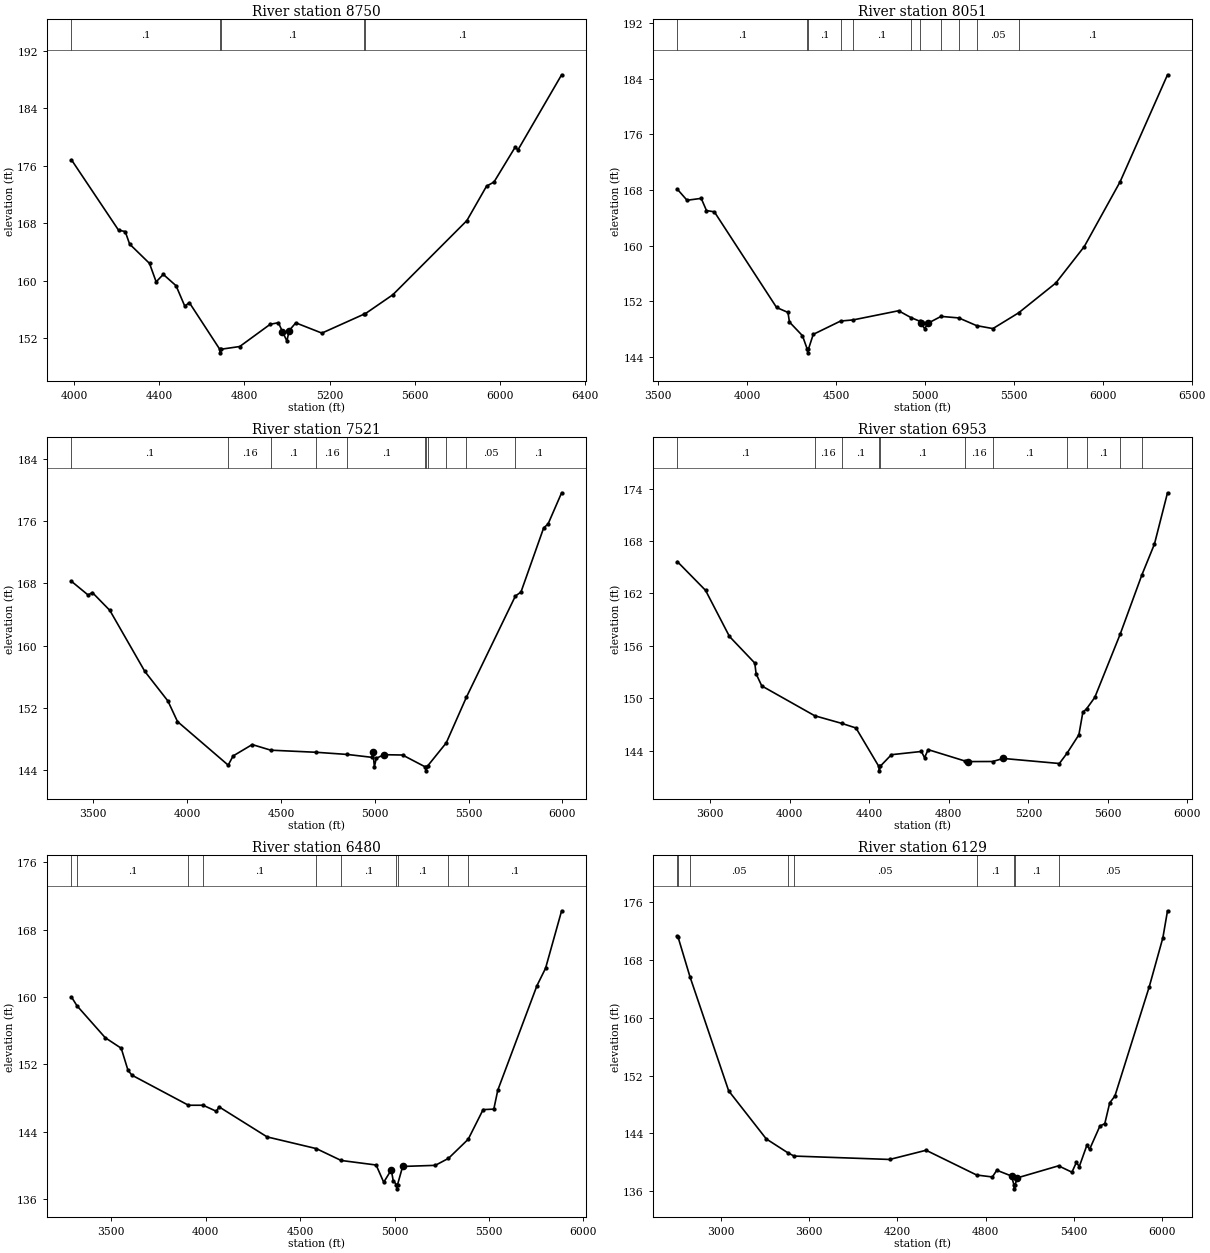
Type RM Length L Ch R = 1 ,8750    ,699,699,699
BEGIN DESCRIPTION:
UNT002 IN NURI 8.0
END DESCRIPTION:
XS GIS Cut Line= 4
      2265005.06     13287473.39      2265560.66     13287633.13
      2266380.11     13287390.07      2267046.77     13286827.57
#Sta/Elev= 30
  3986.5  176.83  4207.8  167.03  4239.2  166.84  4259.8   165.1  4353.4   162.4
  4384.7  159.83  4418.2  160.87  4478.3  159.29  4519.3  156.45  4540.7  156.94
  4683.7  150.44  4686.5  149.94  4689.7  150.44  4777.7  150.82  4921.1  153.92
  4959.5  154.14  4978.8   152.9  4999.6  151.58  5010.1  153.04  5041.3  154.12
  5164.1  152.69  5363.2  155.34  5364.7  155.32  5497.7  158.03  5846.1  168.37
  5938.4  173.16  5973.6  173.74  6072.4  178.56  6086.7  178.24  6291.6  188.68
#Mann= 5 ,-1 , 0
  3986.5      .1       0  4683.7     .07       0  4689.7      .1       0
  5363.2     .05       0  5364.7      .1       0
Bank Sta=4978.8,5010.1
XS Rating Curve= 0 ,0
Exp/Cntr=0.3,0.1

Type RM Length L Ch R = 1 ,8051    ,530,530,530
BEGIN DESCRIPTION:
Mapping XS fafc867a
END DESCRIPTION:
XS GIS Cut Line= 4
      2265227.34     13287633.13      2265782.88     13287966.46
      2267331.49     13287744.24      2267574.53     13287258.16
#Sta/Elev= 30
  3608.4  168.11  3662.8  166.53  3742.5   166.8  3772.1  165.05  3816.3  164.87
  4166.2  151.14  4230.3  150.43  4238.6  149.05  4311.7  147.09    4339  145.13
  4341.7  144.63    4345  145.13  4372.3  147.28  4525.8  149.19  4597.5  149.36
    4852  150.67  4921.9  149.69  4971.9  149.16  4978.4  148.86  4998.6  148.11
  5018.8   148.9    5091  149.86  5190.7  149.64  5290.3  148.54  5382.5  148.11
    5527  150.37  5736.1  154.65  5896.1  159.88  6097.4  169.17  6364.2  184.54
#Mann= 11 ,-1 , 0
  3608.4      .1       0    4339     .07       0    4345      .1       0
  4525.8     .16       0  4597.5      .1       0  4921.9     .16       0
  4971.9      .1       0    5091     .08       0  5190.7      .1       0
  5290.3     .05       0    5527      .1       0
Bank Sta=4978.4,5018.8
XS Rating Curve= 0 ,0
Exp/Cntr=0.3,0.1

Type RM Length L Ch R = 1 ,7521    ,568,568,568
BEGIN DESCRIPTION:
UNT002 IN NURI 7.0
END DESCRIPTION:
XS GIS Cut Line= 4
      2265234.24     13287737.27      2265859.27     13288153.96
      2267262.05     13288417.85       2267692.6     13288362.29
#Sta/Elev= 30
  3383.6  168.25  3471.9   166.5    3495  166.81  3588.1  164.52  3774.4   156.7
  3897.6   152.9  3948.7  150.26  4218.9  144.67  4245.1  145.85  4346.9  147.31
    4446  146.59  4688.6  146.32  4854.7  146.04  4985.9  145.67    4991  146.31
  4998.1  144.45  5008.3  145.55    5049  146.01  5148.4  145.97  5269.9  144.44
  5272.6  143.94  5275.9  144.44  5281.9  144.56  5381.3  147.53  5488.4  153.37
  5749.7  166.36  5779.6  166.88  5900.6  175.11  5923.7  175.59  5996.3  179.61
#Mann= 11 ,-1 , 0
  3383.6      .1       0  4218.9     .16       0    4446      .1       0
  4688.6     .16       0  4854.7      .1       0  5269.9     .07       0
  5275.9      .1       0  5281.9     .08       0  5381.3      .1       0
  5488.4     .05       0  5749.7      .1       0
Bank Sta=4991,5049
XS Rating Curve= 0 ,0
Exp/Cntr=0.3,0.1

Type RM Length L Ch R = 1 ,6953    ,473,473,473
BEGIN DESCRIPTION:
UNT002 IN NURI 6.0
END DESCRIPTION:
XS GIS Cut Line= 4
       2265289.8     13287834.49      2265956.49     13288452.57
      2266671.77      13288660.9      2267483.47     13288633.15
#Sta/Elev= 30
    3434  165.65  3575.8  162.36    3696  157.08  3823.5  154.03  3830.3  152.79
  3858.7  151.41  4125.2  147.99  4262.2  147.11  4332.7  146.59  4447.8  142.18
  4450.6  141.68  4453.8  142.18    4511  143.53  4662.2   143.9  4677.7  143.18
  4695.7  144.11  4883.4  142.79  4896.4  142.74  5020.8  142.75  5073.5   143.1
  5356.1  142.52  5394.7   143.7  5454.3  145.81  5474.3  148.39  5493.1  148.79
  5534.3  150.09  5662.3  157.35  5771.5  164.14  5834.5  167.66  5900.3  173.54
#Mann= 11 ,-1 , 0
    3434      .1       0  4125.2     .16       0  4262.2      .1       0
  4447.8     .07       0  4453.8      .1       0  4883.4     .16       0
  5020.8      .1       0  5394.7     .08       0  5493.1      .1       0
  5662.3     .05       0  5771.5      .1       0
Bank Sta=4896.4,5073.5
XS Rating Curve= 0 ,0
Exp/Cntr=0.3,0.1

Type RM Length L Ch R = 1 ,6480    ,351,351,351
BEGIN DESCRIPTION:
UNT002 IN NURI 5.0
END DESCRIPTION:
XS GIS Cut Line= 4
      2265270.94     13288011.55      2266435.04     13289035.01
      2266679.83     13289053.24      2267438.46     13288801.23
#Sta/Elev= 30
  3289.4     160  3318.3  158.96  3468.2  155.16  3552.7  153.91  3588.7  151.28
  3609.6  150.71  3908.6  147.14  3986.1  147.14  4056.5  146.42  4070.7  146.95
    4325  143.38  4585.4  141.99    4717  140.58  4902.3  140.04  4942.4  137.99
  4982.5  139.46  4992.5   138.2  5009.6  137.71  5012.3  137.21  5015.6  137.71
  5042.7  139.87  5215.3     140  5285.2  140.83  5389.7   143.1  5468.6  146.62
  5525.3  146.68  5546.3  148.93  5753.6  161.34  5799.2  163.41  5884.3  170.24
#Mann= 10 ,-1 , 0
  3289.4     .05       0  3318.3      .1       0  3908.6     .16       0
  3986.1      .1       0  4585.4     .16       0    4717      .1       0
  5009.6     .07       0  5015.6      .1       0  5285.2     .05       0
  5389.7      .1       0
Bank Sta=4982.5,5042.7
XS Rating Curve= 0 ,0
Exp/Cntr=0.3,0.1

Type RM Length L Ch R = 1 ,6129    ,756,756,756
BEGIN DESCRIPTION:
UNT002 IN NURI 4.0
END DESCRIPTION:
XS GIS Cut Line= 5
      2264745.23     13288368.57      2265797.93     13289247.08
      2265987.26     13289406.12      2267267.15     13289368.26
      2267592.77     13289088.08
#Sta/Elev= 30
  2706.2  171.28  2710.6  171.16  2791.5  165.67  3054.6  149.89  3309.8  143.25
    3455  141.35  3498.2  140.88  4147.9  140.41  4395.1  141.68  4738.4  138.26
  4845.3  137.99  4875.3  138.92  4975.3  138.12  4992.3  136.85  4995.1  136.35
  4998.3  136.85  5015.3  137.87  5294.4  139.53  5385.5  138.65  5415.5  139.99
  5435.5  139.43    5487  142.37  5505.6  141.82  5575.6  145.03  5608.7  145.36
  5642.1  148.23  5677.3  149.17    5911   164.3  6003.1  171.04  6034.6  174.77
#Mann= 9 ,-1 , 0
  2706.2     .05       0  2710.6     .08       0  2791.5     .05       0
    3455      .1       0  3498.2     .05       0  4738.4      .1       0
  4992.3     .07       0  4998.3      .1       0  5294.4     .05       0
Bank Sta=4975.3,5015.3
XS Rating Curve= 0 ,0
Exp/Cntr=0.3,0.1