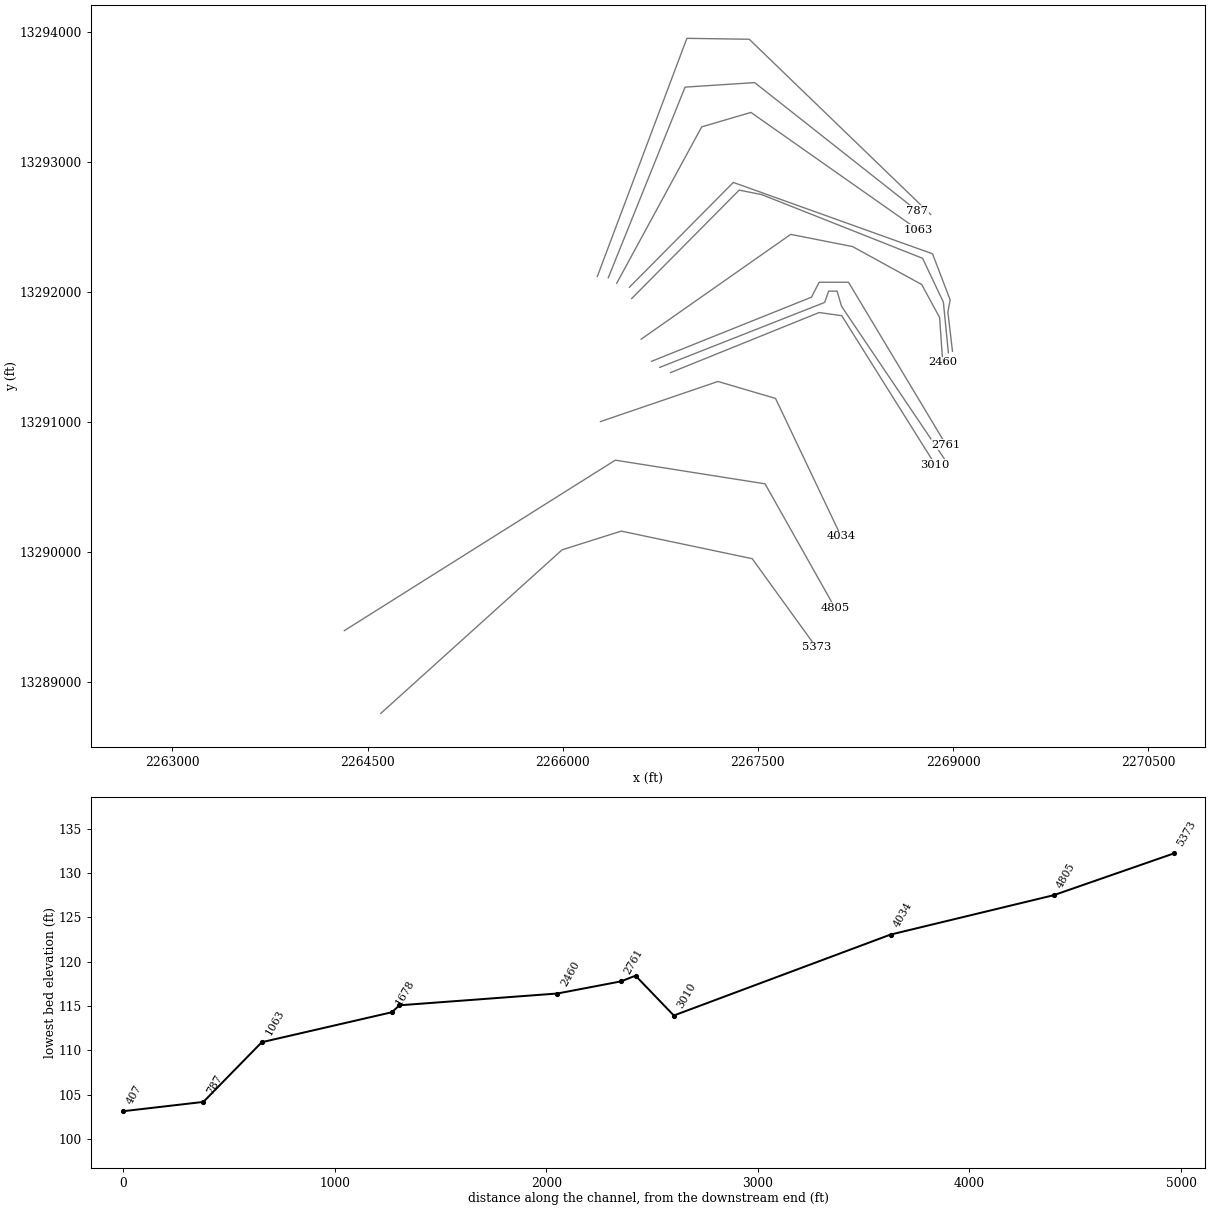
HEC-RAS study UNT002 IN NURI.prj: UNT002 IN NURI Base Level Engineering

--- UNT002 IN NURI.g01 (geometry) --- (continued)

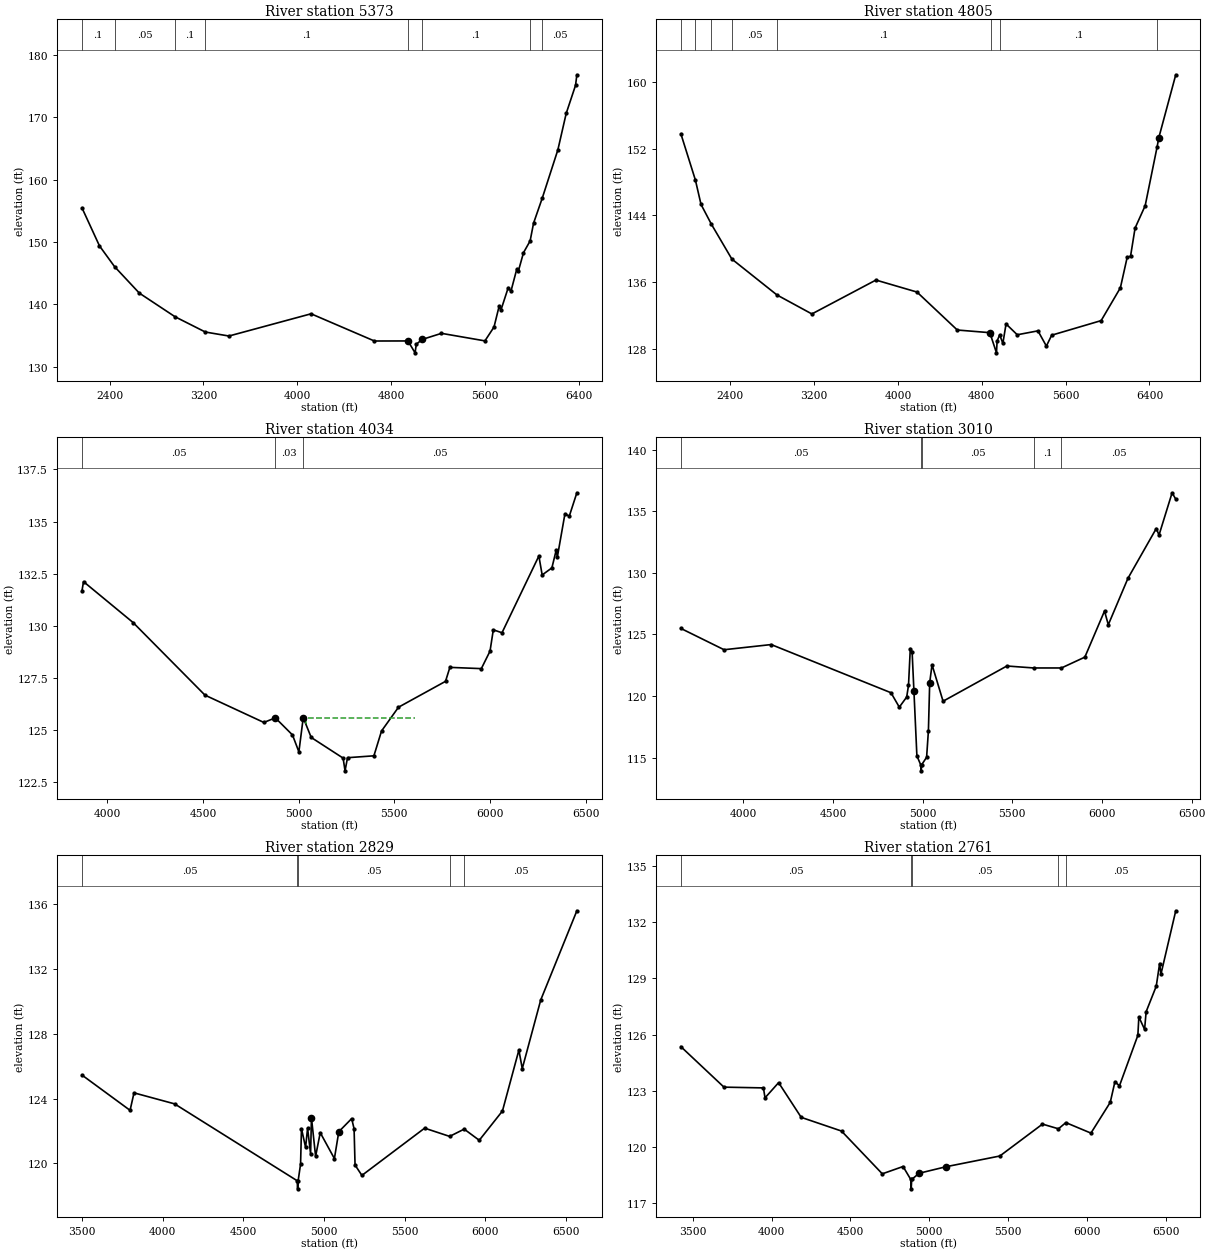
Type RM Length L Ch R = 1 ,5373    ,568,568,568
BEGIN DESCRIPTION:
UNT002 IN NURI 3.0
END DESCRIPTION:
XS GIS Cut Line= 5
      2264601.36      13288762.4      2265994.84     13290019.56
      2266449.23     13290163.45      2267456.48      13289951.4
      2267947.99     13289270.85
#Sta/Elev= 30
  2163.8  155.48    2313  149.38  2441.5  146.05  2653.1  141.79  2958.3  137.99
  3216.4  135.54  3417.6   134.9  4118.3  138.47  4658.7   134.1  4944.9  134.11
  5005.5   132.2  5016.4  133.59  5067.5  134.36    5231  135.33  5601.5  134.12
  5679.2  136.35  5723.3  139.73  5737.2  139.01  5800.6  142.68  5823.5  142.08
  5872.8  145.61  5886.5   145.3  5930.6  148.28  5987.1  150.17  6016.5  153.02
  6091.2  157.07  6223.8  164.79    6295  170.65  6374.7  175.16    6386  176.85
#Mann= 8 ,-1 , 0
  2163.8      .1       0  2441.5     .05       0  2958.3      .1       0
  3216.4      .1       0  4944.9     .07       0  5067.5      .1       0
  5987.1      .1       0  6091.2     .05       0
Bank Sta=4944.9,5067.5
XS Rating Curve= 0 ,0
Exp/Cntr=0.3,0.1

Type RM Length L Ch R = 1 ,4805    ,771,771,771
BEGIN DESCRIPTION:
UNT002 IN NURI 2.0
END DESCRIPTION:
XS GIS Cut Line= 4
      2264321.15     13289398.56       2266403.8     13290708.73
      2267554.93     13290526.97      2268092.65     13289572.72
#Sta/Elev= 30
  1929.6   153.8  2068.5  148.23    2122  145.31  2220.7  142.94  2416.2  138.75
  2846.5  134.44  3179.5  132.16  3790.6  136.23  4182.1  134.79  4566.8  130.23
    4879  129.91    4884  129.65  4940.5  127.49  4946.5  128.91  4971.1  129.65
  5001.5  128.63  5031.9  130.96  5138.8  129.66  5336.2  130.13  5416.6   128.3
  5467.2  129.61  5939.1  131.36  6122.6   135.3  6187.6  138.97  6219.4  139.08
  6262.7  142.47  6359.1  145.16  6473.1  152.23  6489.5  153.34  6650.8  160.88
#Mann= 8 ,-1 , 0
  1929.6      .1       0  2068.5     .16       0  2220.7      .1       0
  2416.2     .05       0  2846.5      .1       0    4884     .07       0
  4971.1      .1       0  6473.1     .05       0
#XS Ineff= 1 ,-1
 5052.05 6000.15130.5394
Permanent Ineff=
       F
Bank Sta=4879,6489.5
XS Rating Curve= 0 ,0
Exp/Cntr=0.3,0.1

Type RM Length L Ch R = 1 ,4034    ,1024,1024,1024
BEGIN DESCRIPTION:
Mapping XS ad4166a8
END DESCRIPTION:
XS GIS Cut Line= 4
      2266290.04     13291005.49      2267192.85     13291313.66
      2267635.56     13291183.45      2268139.02     13290124.45
#Sta/Elev= 30
  3866.7  131.68  3874.8  132.12  4133.9  130.16  4509.8  126.68  4817.8  125.37
  4877.9  125.59  4967.6  124.77    5001  123.96  5023.8   125.6  5065.5  124.65
  5232.3  123.66  5242.4  123.05  5255.3  123.68  5393.3  123.77  5433.2  124.96
  5521.9   126.1  5767.8  127.34  5790.6  128.01  5955.1  127.95  6000.6  128.79
  6017.7  129.81  6063.2  129.67    6256  133.35  6273.2  132.44  6324.1  132.78
  6346.9  133.64  6352.4  133.29  6392.3  135.37    6415  135.26  6454.7  136.38
#Mann= 3 , 0 , 0
  3866.7     .05       0  4877.9     .03       0  5023.8     .05       0
#XS Ineff= 1 ,-1
 5036.89 5607.89125.5699
Permanent Ineff=
       F
Bank Sta=4877.9,5023.8
XS Rating Curve= 0 ,0
Exp/Cntr=0.3,0.1

Type RM Length L Ch R = 1 ,3010    ,181,181,181
BEGIN DESCRIPTION:
Mapping XS 70ff6fb5
END DESCRIPTION:
XS GIS Cut Line= 4
      2266828.45     13291381.87      2267970.86     13291843.69
      2268144.47     13291819.39      2268862.99     13290673.92
#Sta/Elev= 30
  3651.7  125.49  3892.7  123.76  4155.5  124.18  4823.4  120.27  4869.8   119.1
    4911  119.92  4921.1  120.86  4931.2  123.86  4941.3  123.58  4951.4   120.4
  4967.9  115.15  4988.8  114.43  4991.6  113.93  4994.8  114.43  5022.1  115.03
  5032.2   117.2  5039.3  121.09  5052.4  122.54  5113.9  119.58  5469.7  122.44
  5619.7  122.28    5774  122.28  5904.5  123.16  6014.1   126.9  6035.3  125.79
  6144.9  129.56  6302.8   133.6  6318.1  133.07  6391.1   136.5  6411.4  135.98
#Mann= 5 ,-1 , 0
  3651.7     .05       0  4988.8    .035       0  4994.8     .05       0
  5619.7      .1       0    5774     .05       0
Bank Sta=4951.4,5039.3
XS Rating Curve= 0 ,0
Exp/Cntr=0.3,0.1

Type RM Length L Ch R = 1 ,2829    ,68,68,68
BEGIN DESCRIPTION:
Mapping XS 03675737
END DESCRIPTION:
XS GIS Cut Line= 6
      2266745.85     13291422.18      2268013.16      13291921.3
      2268043.54      13292008.1      2268108.65      13292008.1
      2268143.37     13291890.92      2268932.04     13290720.91
#Sta/Elev= 30
  3498.3  125.45  3796.7  123.27  3821.1  124.35  4072.9  123.67  4833.5  118.92
  4836.2  118.42  4839.5  118.92  4854.5  119.95  4860.1  122.14  4885.7  120.98
    4898  122.17  4916.7  120.58    4922  122.81  4947.8  120.43  4976.5  121.89
  5064.4  120.29  5091.7  121.95  5171.5  122.76  5186.5  122.13  5192.5  119.89
    5235  119.25  5624.3  122.17  5779.3  121.66  5869.6  122.11  5963.1  121.42
    6107  123.23  6208.9  126.99  6229.9  125.85  6344.5  130.09  6568.7   135.6
#Mann= 5 ,-1 , 0
  3498.3     .05       0  4833.5     .03       0  4839.5     .05       0
  5779.3      .1       0  5869.6     .05       0
Bank Sta=4922,5091.7
XS Rating Curve= 0 ,0
Exp/Cntr=0.3,0.1

Type RM Length L Ch R = 1 ,2761    ,301,301,301
BEGIN DESCRIPTION:
Mapping XS 3bf2fdd6
END DESCRIPTION:
XS GIS Cut Line= 5
      2266682.69      13291468.7      2267911.83     13291961.75
      2267970.86     13292076.33      2268196.55     13292076.33
      2268946.57     13290826.31
#Sta/Elev= 30
  3425.2  125.36  3698.4   123.2  3948.6  123.16  3958.6  122.63  4044.8  123.44
    4188  121.59  4443.4  120.86    4702  118.58  4833.6  118.97  4882.3  118.28
  4885.1  117.78  4888.3  118.28  4935.3  118.61  5106.7  118.96    5447  119.53
  5717.2  121.23  5818.5  120.98  5865.3  121.31  6024.3  120.75  6146.8  122.39
  6176.4  123.49  6205.1  123.27  6321.7  125.96    6328  126.94  6364.4  126.28
  6374.2  127.22  6438.3  128.58  6459.7  129.79    6468  129.22  6561.9   132.6
#Mann= 5 ,-1 , 0
  3425.2     .05       0  4882.3     .03       0  4888.3     .05       0
  5818.5      .1       0  5865.3     .05       0
Bank Sta=4935.3,5106.7
XS Rating Curve= 0 ,0
Exp/Cntr=0.3,0.1

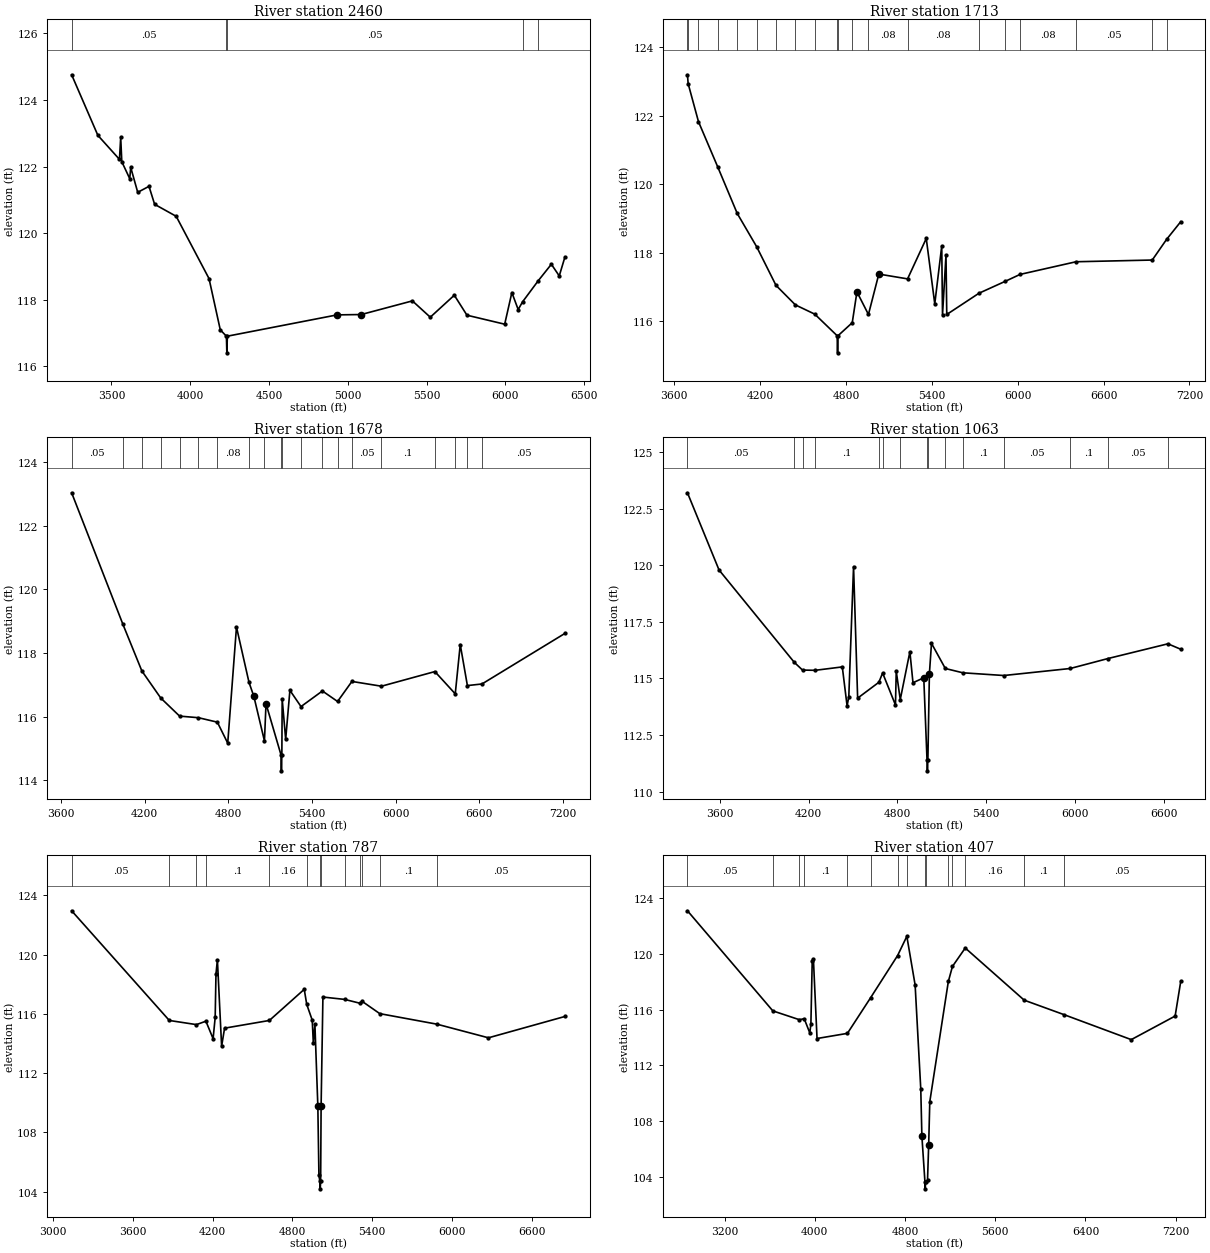
Type RM Length L Ch R = 1 ,2460    ,747,747,747
BEGIN DESCRIPTION:
Mapping XS b18a2a62
END DESCRIPTION:
XS GIS Cut Line= 6
      2266602.77     13291638.81      2267752.11     13292444.39
       2268227.8     13292350.64      2268759.05     13292058.97
      2268896.88     13291805.52      2268920.84     13291460.87
#Sta/Elev= 30
  3247.2  124.76  3413.7  122.94  3550.6  122.22  3558.5  122.88  3565.4  122.15
  3615.9  121.64    3622  121.98  3666.5  121.23    3738  121.41  3773.7  120.87
  3910.6  120.51  4118.9  118.64  4190.4   117.1  4229.2  116.91    4232  116.41
  4235.2  116.91  4931.7  117.55  5084.5  117.56  5409.3  117.97  5522.8  117.48
  5675.3  118.14  5755.6  117.54    5995  117.27  6040.5  118.22  6080.6  117.71
  6108.2  117.94    6207  118.57  6291.1  119.07  6341.2  118.72  6377.3  119.29
#Mann= 5 ,-1 , 0
  3247.2     .05       0  4229.2     .03       0  4235.2     .05       0
  6108.2      .1       0    6207     .05       0
Bank Sta=4931.7,5084.5
XS Rating Curve= 0 ,0
Exp/Cntr=0.3,0.1

Type RM Length L Ch R = 1 ,1713    ,35,35,35
BEGIN DESCRIPTION:
Mapping XS 0e9b52f8
END DESCRIPTION:
XS GIS Cut Line= 6
      2266529.89     13291951.34      2267356.27     13292784.67
      2267529.89     13292749.94        2268766.     13292260.36
      2268925.72     13291923.55      2268964.31     13291533.63
#Sta/Elev= 30
  3692.7   123.2  3697.6  122.94  3769.8  121.83  3905.2   120.5  4040.6  119.15
    4176  118.18  4311.4  117.05  4446.8  116.48  4582.2  116.21  4738.6  115.58
  4741.4  115.08  4744.6  115.58  4844.1  115.96  4876.8  116.86  4957.2   116.2
  5029.7  117.38  5230.6  117.24  5361.2  118.42  5420.6  116.51  5469.3   118.2
  5474.7  116.19    5499  117.93  5504.4   116.2  5729.3  116.82  5913.8  117.17
  6016.5  117.37  6407.8  117.74  6940.1  117.79  7039.7  118.39  7139.2  118.91
#Mann= 20 ,-1 , 0
  3692.7     .05       0  3697.6     .08       0  3769.8     .05       0
  3905.2     .05       0  4040.6     .05       0    4176     .05       0
  4311.4     .05       0  4446.8     .05       0  4582.2     .05       0
  4738.6     .07       0  4744.6     .05       0  4844.1     .08       0
  4957.2     .08       0  5230.6     .08       0  5729.3     .08       0
  5913.8      .1       0  6016.5     .08       0  6407.8     .05       0
  6940.1      .1       0  7039.7     .05       0
Bank Sta=4876.8,5029.7
XS Rating Curve= 0 ,0
Exp/Cntr=0.3,0.1

Type RM Length L Ch R = 1 ,1678    ,615,615,615
BEGIN DESCRIPTION:
Mapping XS 8ba79799
END DESCRIPTION:
XS GIS Cut Line= 6
      2266512.53     13292038.14      2267311.14     13292843.69
      2268842.39     13292295.08       2268977.8     13291940.92
      2268960.42     13291847.88      2268995.78     13291545.59
#Sta/Elev= 30
    3675  123.04  4043.4   118.9  4178.8  117.44  4314.2  116.59  4449.6  116.02
  4585.1  115.97  4720.5  115.83    4795  115.17  4857.8  118.82  4947.7  117.08
  4982.5  116.64  5058.5  115.24  5069.7  116.41  5177.4   114.8  5180.2   114.3
  5183.4   114.8  5185.7  116.56  5210.8  115.29  5241.1  116.83  5320.8  116.32
  5474.3  116.81  5583.2  116.48  5686.1  117.11    5898  116.96  6281.4  117.42
  6427.6  116.72  6463.4  118.27  6514.7  116.98  6619.2  117.03  7214.7  118.62
#Mann= 20 ,-1 , 0
    3675     .05       0  4043.4     .08       0  4178.8     .08       0
  4314.2     .08       0  4449.6     .08       0  4585.1     .08       0
  4720.5     .08       0  4947.7     .05       0  5058.5     .08       0
  5177.4    .035       0  5183.4     .05       0  5320.8     .08       0
  5474.3     .05       0  5583.2     .08       0  5686.1     .05       0
    5898      .1       0  6281.4     .08       0  6427.6      .1       0
  6514.7     .08       0  6619.2     .05       0
Bank Sta=4982.5,5069.7
XS Rating Curve= 0 ,0
Exp/Cntr=0.3,0.1

Type RM Length L Ch R = 1 ,1063    ,276,276,276
BEGIN DESCRIPTION:
Mapping XS c9597d6e
END DESCRIPTION:
XS GIS Cut Line= 4
      2266415.29     13292069.36      2267068.08     13293270.78
      2267446.55     13293381.89      2268731.23     13292479.14
#Sta/Elev= 30
    3382   123.2  3595.4  119.79  4103.8  115.71  4159.3  115.37  4245.5  115.36
  4427.9  115.51  4460.2  113.79  4471.7  114.18  4503.9  119.94  4531.5  114.13
  4674.7  114.83  4700.3  115.24    4787  113.83  4792.2  115.32  4819.4  114.07
  4884.4  116.18  4905.3  114.81  4978.2  115.03    5000  111.42  5002.7  110.92
    5006  111.42 5016.11   115.2  5030.3  116.55  5123.7  115.44  5242.1  115.25
    5519  115.13  5967.6  115.44  6222.6  115.88  6627.1  116.53  6713.9  116.29
#Mann= 15 ,-1 , 0
    3382     .05       0  4103.8      .1       0  4159.3     .05       0
  4245.5      .1       0  4674.7     .16       0  4700.3      .1       0
  4819.4     .16       0    5000     .07       0    5006     .16       0
  5123.7     .16       0  5242.1      .1       0    5519     .05       0
  5967.6      .1       0  6222.6     .05       0  6627.1      .1       0
Bank Sta=4978.2,5016.11
XS Rating Curve= 0 ,0
Exp/Cntr=0.3,0.1

Type RM Length L Ch R = 1 ,787     ,380,380,380
BEGIN DESCRIPTION:
Mapping XS 67f5ef47
END DESCRIPTION:
XS GIS Cut Line= 4
      2266349.95     13292111.04      2266940.24     13293576.35
      2267474.96     13293611.07      2268723.84     13292625.85
#Sta/Elev= 30
  3141.6  122.95  3875.4  115.55    4079  115.27  4150.4   115.5  4204.4  114.32
    4220  115.75    4226  118.68  4236.7  119.65  4268.4  113.81  4290.6  115.03
  4627.2  115.55  4889.2  117.65    4908  116.63  4949.3  115.57  4957.5     114
  4969.3  115.29 4991.32  109.79  4999.4  105.13  5006.4  104.69  5009.2  104.19
  5012.4  104.69 5015.91  109.79  5029.5  117.13  5193.1  116.97  5308.6  116.71
  5322.6  116.85  5456.7  116.01  5885.8   115.3  6273.2  114.38  6847.9  115.82
#Mann= 13 ,-1 , 0
  3141.6     .05       0  3875.4      .1       0    4079     .16       0
  4150.4      .1       0  4627.2     .16       0    4908      .1       0
  5006.4     .07       0  5012.4      .1       0  5193.1     .16       0
  5308.6      .1       0  5322.6     .16       0  5456.7      .1       0
  5885.8     .05       0
Bank Sta=4991.32,5015.91
XS Rating Curve= 0 ,0
Exp/Cntr=0.3,0.1

Type RM Length L Ch R = 1 ,407     ,0,0,0
BEGIN DESCRIPTION:
UNT002 IN NURI 1.0
END DESCRIPTION:
XS GIS Cut Line= 4
        2266266.     13292121.49      2266954.12     13293951.35
      2267433.29     13293944.41      2268828.51     13292597.16
#Sta/Elev= 30
    2871  123.08  3628.2   115.9  3862.9  115.27  3906.3  115.34  3955.8  114.32
  3965.4  114.94  3977.2  119.48  3987.8   119.6  4019.9  113.92  4289.4  114.29
  4496.1  116.86  4734.3  119.87  4816.2  121.25  4889.6  117.76  4939.6  110.31
  4949.6  106.91  4976.6  103.64  4979.3  103.14  4982.6  103.64  4999.6  103.77
  5009.6  106.25  5019.6  109.39  5184.1  118.01  5220.6  119.09    5334  120.41
  5856.6  116.67  6206.8  115.64  6805.9  113.84  7194.9  115.53  7244.7  118.02
#Mann= 15 ,-1 , 0
    2871     .05       0  3628.2      .1       0  3862.9     .16       0
  3906.3      .1       0  4289.4     .16       0  4496.1     .05       0
  4734.3     .16       0  4816.2     .05       0  4976.6    .035       0
  4982.6     .05       0  5184.1     .16       0  5220.6      .1       0
    5334     .16       0  5856.6      .1       0  6206.8     .05       0
Bank Sta=4949.6,5009.6
XS Rating Curve= 0 ,0
Exp/Cntr=0.3,0.1

Chan Stop Cuts=-1
Use User Specified Reach Order=0
Composite Channel Slope=5