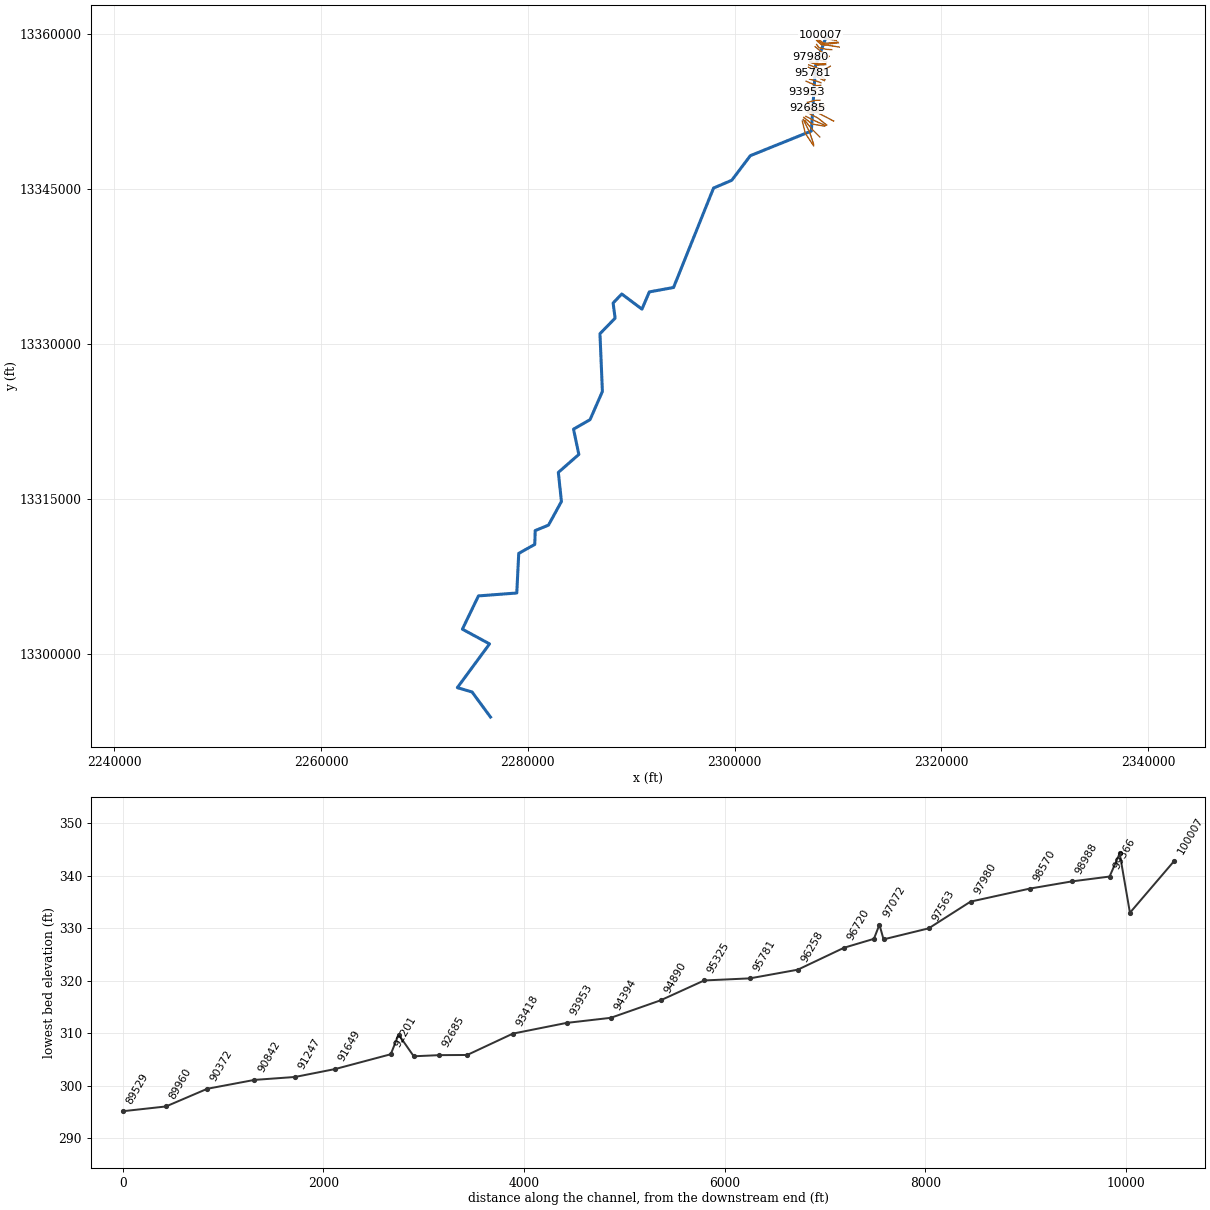
--- UNT003 IN NURI.prj (project) ---

Proj Title=UNT003 IN NURI Base Level Engineering
Current Plan=p01
Default Exp/Contr=0.3,0.1
English Units
Geom File=g01
Flow File=f01
Plan File=p01
Y Axis Title=Elevation
X Axis Title(PF)=Main Channel Distance
X Axis Title(XS)=Station
BEGIN DESCRIPTION:
UNT003 IN NURI
END DESCRIPTION:
DSS Export Rating Curves= 0
DSS Export Rating Curve Sorted= 0
DSS Export Volume Flow Curves= 0
DXF OffsetX= 0
DXF OffsetY= 0
DXF ScaleX= 1
DXF ScaleY= 10

--- UNT003 IN NURI.p01 (plan) ---

Plan Title=Multiple Run
Short Identifier=Multiple
Geom File=g01
Flow File=f01
Subcritical Flow
K Sum by GR= 0
Std Step Tol= 0.01
Critical Tol= 0.01
Num of Std Step Trials= 20
Max Error Tol= 0.3
Flow Tol Ratio= 0.001
Split Flow NTrial= 30
Split Flow Tol= 0.02
Split Flow Ratio= 0.02
Log Output Level= 0
Friction Slope Method= 1
Unsteady Friction Slope Method= 2
Unsteady Bridges Friction Slope Method= 1
Parabolic Critical Depth
Global Vel Dist=  1 , 1 , 1
Global Log Level= 0
CheckData=True
Encroach Param= -1, 0, 0, 0
BEGIN DESCRIPTION:
Multiple Run
END DESCRIPTION:

--- UNT003 IN NURI.f01 (steady flow) ---

Flow Title=Multiple
Program Version=4.10
Number of Profiles= 7
Profile Names=10-year,25-year,50-year,1pct_min,100-year,1pct_plu,500-year
River Rch & RM=UNT003 IN NURI,Reach-1         ,100007
     731    1050    1323    1218    1647    2227    2560
River Rch & RM=UNT003 IN NURI,Reach-1         ,99467
    1095    1600    2038    1893    2560    3462    4057
River Rch & RM=UNT003 IN NURI,Reach-1         ,92685
    1788    2674    3459    3256    4404    5955    7174
River Rch & RM=UNT003 IN NURI,Reach-1         ,92430
    1788    2674    3459    3256    4404    5955    7174
River Rch & RM=UNT003 IN NURI,Reach-1         ,89960
    2070    3112    4038    3813    5157    6974    8452
River Rch & RM=UNT003 IN NURI,Reach-1         ,88417
    2450    3706    4829    4576    6189    8370   10215
River Rch & RM=UNT003 IN NURI,Reach-1         ,85995
    2544    3836    4987    4712    6372    8618   10459
River Rch & RM=UNT003 IN NURI,Reach-1         ,78897
    3309    5031    6576    6243    8443   11418   13990
River Rch & RM=UNT003 IN NURI,Reach-1         ,78550
    3309    5031    6576    6243    8443   11418   13990
River Rch & RM=UNT003 IN NURI,Reach-1         ,77828
    3309    5031    6576    6243    8443   11418   13990
River Rch & RM=UNT003 IN NURI,Reach-1         ,69983
    4076    6240    8196    7813   10566   14290   17652
River Rch & RM=UNT003 IN NURI,Reach-1         ,69172
    4076    6240    8196    7813   10566   14290   17652
River Rch & RM=UNT003 IN NURI,Reach-1         ,65210
    3926    5981    7830    7439   10060   13605   16697
River Rch & RM=UNT003 IN NURI,Reach-1         ,56400
    4039    6161    8075    7687   10396   14060   17348
River Rch & RM=UNT003 IN NURI,Reach-1         ,55817
    4039    6161    8075    7687   10396   14060   17348
River Rch & RM=UNT003 IN NURI,Reach-1         ,55325
    4039    6161    8075    7687   10396   14060   17348
River Rch & RM=UNT003 IN NURI,Reach-1         ,51055
    4053    6184    8106    7719   10440   14118   17429
River Rch & RM=UNT003 IN NURI,Reach-1         ,50591
    4409    6736    8835    8411   11374   15383   18963
River Rch & RM=UNT003 IN NURI,Reach-1         ,49820
    3967    6041    7909    7523   10174   13759   16948
River Rch & RM=UNT003 IN NURI,Reach-1         ,46553
    4114    6273    8221    7827   10585   14315   17670
River Rch & RM=UNT003 IN NURI,Reach-1         ,44095
    4578    6987    9159    8714   11785   15938   19629
River Rch & RM=UNT003 IN NURI,Reach-1         ,43669
    3974    6040    7898    7505   10150   13727   16887
River Rch & RM=UNT003 IN NURI,Reach-1         ,37273
    3878    5881    7678    7285    9853   13324   16349
River Rch & RM=UNT003 IN NURI,Reach-1         ,36648
    3879    5881    7678    7286    9854   13326   16350
River Rch & RM=UNT003 IN NURI,Reach-1         ,28979
    3908    5930    7747    7357    9949   13455   16535
River Rch & RM=UNT003 IN NURI,Reach-1         ,28862
    3874    5873    7667    7276    9839   13307   16331
River Rch & RM=UNT003 IN NURI,Reach-1         ,27694
    3725    5626    7326    6936    9380   12685   15503
River Rch & RM=UNT003 IN NURI,Reach-1         ,8217
    3725    5627    7329    6944    9391   12700   15553
River Rch & RM=UNT003 IN NURI,Reach-1         ,7677
    3725    5627    7329    6944    9391   12700   15553
River Rch & RM=UNT003 IN NURI,Reach-1         ,5480
    3730    5637    7345    6962    9415   12733   15606
Boundary for River Rch & Prof#=UNT003 IN NURI,Reach-1         , 1
Up Type= 0
Dn Type= 3
Dn Slope=0.005
Boundary for River Rch & Prof#=UNT003 IN NURI,Reach-1         , 2
Up Type= 0
Dn Type= 3
Dn Slope=0.005
Boundary for River Rch & Prof#=UNT003 IN NURI,Reach-1         , 3
Up Type= 0
Dn Type= 3
Dn Slope=0.005
Boundary for River Rch & Prof#=UNT003 IN NURI,Reach-1         , 4
Up Type= 0
Dn Type= 3
Dn Slope=0.005
Boundary for River Rch & Prof#=UNT003 IN NURI,Reach-1         , 5
Up Type= 0
Dn Type= 3
Dn Slope=0.005
Boundary for River Rch & Prof#=UNT003 IN NURI,Reach-1         , 6
Up Type= 0
Dn Type= 3
Dn Slope=0.005
Boundary for River Rch & Prof#=UNT003 IN NURI,Reach-1         , 7
Up Type= 0
Dn Type= 3
Dn Slope=0.005
DSS Import GetInterval= 0
DSS Import GetPeak= 0
DSS Import FillOption= 0

--- UNT003 IN NURI.g01 (geometry) ---

Geom Title=Existing Conditions
Program Version=4.10

River Reach=UNT003 IN NURI  ,Reach-1
Reach XY= 30
      2308907.12     13359892.18      2307824.91     13356941.49
      2307417.72     13350621.69      2301517.71     13348240.63
       2299717.4     13345857.49      2297957.72     13345106.85
      2294087.72     13335486.86      2291741.66     13335058.72
      2291030.57     13333391.35      2289077.72     13334856.86
      2288241.05     13333985.47       2288434.9     13332517.95
      2286967.89     13331016.78      2287205.09     13325428.45
      2286012.76     13322704.23      2284410.03     13321780.98
      2284925.33     13319336.79       2282940.8     13317595.58
      2283242.25     13314784.34       2281987.1     13312496.22
      2280703.48     13311969.14      2280663.06     13310631.09
      2279111.07     13309765.48      2278920.96     13305930.15
      2275214.77      13305651.6      2273659.68     13302431.22
       2276286.7     13301006.67      2273171.47     13296774.49
      2274592.59     13296357.28      2276379.38     13293929.22

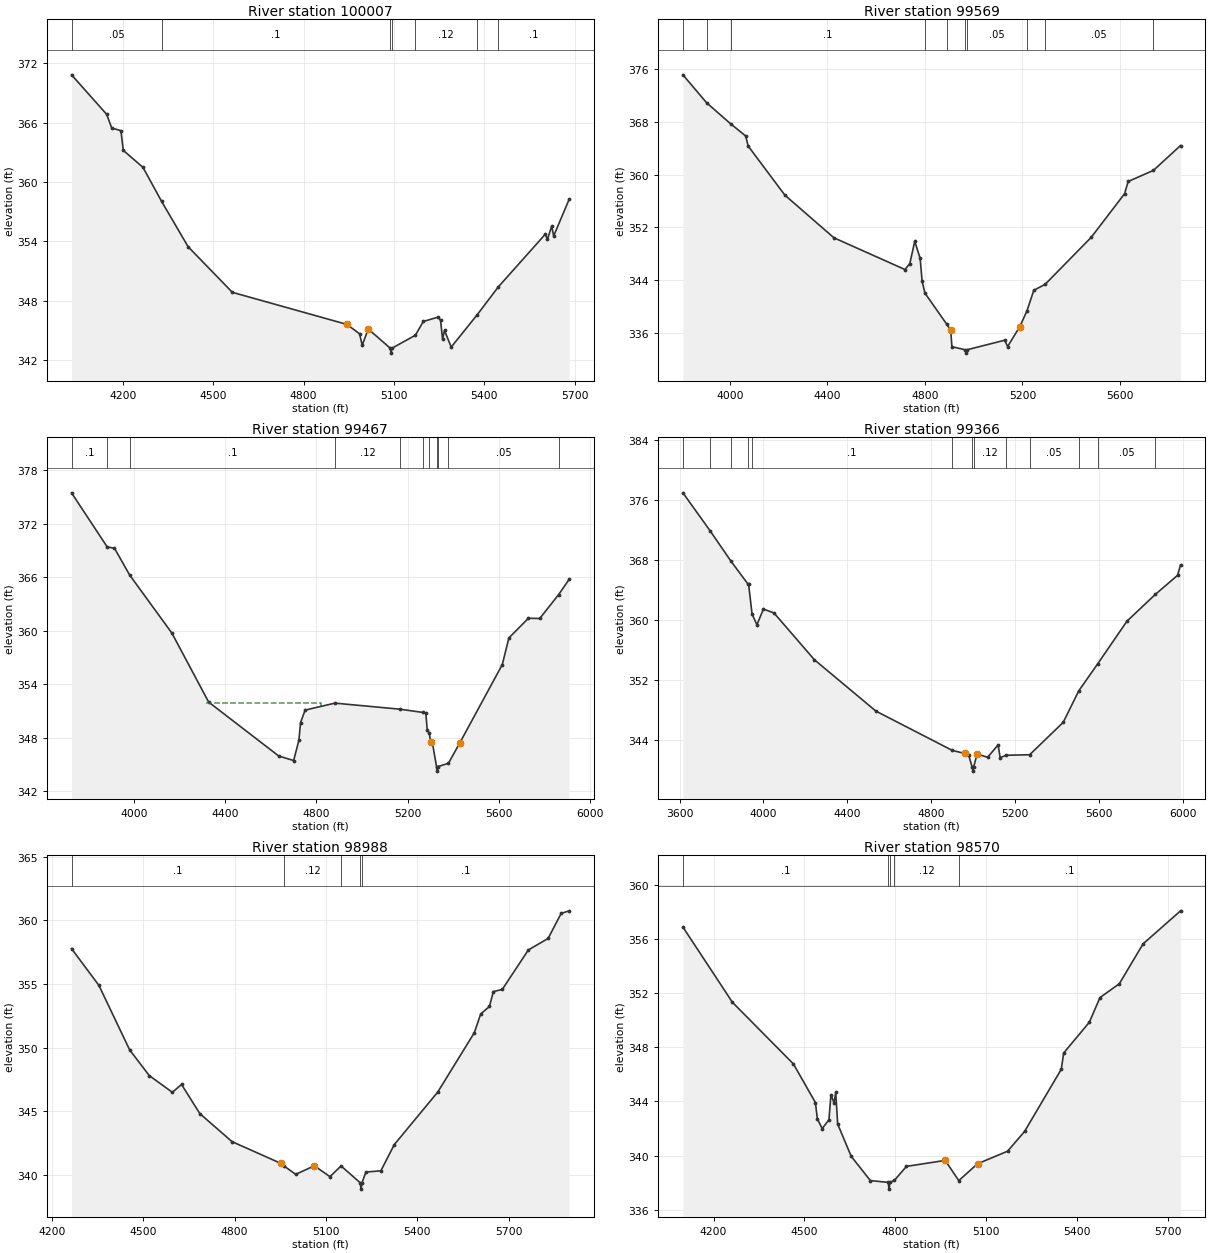
Type RM Length L Ch R = 1 ,100007  ,438,438,438
BEGIN DESCRIPTION:
UNT003 IN NURI 161.0
END DESCRIPTION:
XS GIS Cut Line= 3
       2309839.3     13359392.65      2308800.37     13359568.69
      2308337.51     13359948.22
#Sta/Elev= 30
  4029.3  370.83  4145.9  366.84  4162.8  365.46  4193.2  365.19  4201.2   363.2
  4266.6  361.48  4328.1  358.06  4416.3  353.47  4563.3  348.86  4943.7  345.62
  4985.8  344.67  4994.4  343.52  5014.7  345.15  5087.5  343.22  5090.2  342.72
  5093.5  343.22  5171.1  344.53  5197.4  345.92  5246.9  346.36  5254.6  346.03
  5261.3  344.13  5267.7  345.01    5290  343.33  5376.4   346.6  5446.4  349.41
  5602.9  354.75  5609.3   354.2  5623.7  355.55  5630.2  354.55  5681.6  358.26
#Mann= 7 ,-1 , 0
  4029.3     .05       0  4328.1      .1       0  5087.5     .07       0
  5093.5      .1       0  5171.1     .12       0  5376.4     .05       0
  5446.4      .1       0
Bank Sta=4943.7,5014.7
XS Rating Curve= 0 ,0
Exp/Cntr=0.3,0.1

Type RM Length L Ch R = 1 ,99569   ,102,102,102
BEGIN DESCRIPTION:
UNT003 IN NURI 160.0
END DESCRIPTION:
XS GIS Cut Line= 4
       2309973.8     13359223.38      2308966.86      13359127.9
      2308580.58     13359145.26      2308055.43     13359514.16
#Sta/Elev= 30
  3808.3  375.16  3905.3  370.92  4003.7  367.73  4065.5  365.88  4075.6  364.36
  4226.2   356.9  4427.1  350.43  4718.4  345.61  4738.5  346.52  4758.6  349.89
  4780.8   347.3  4788.8  343.86  4800.2  342.04  4889.4  337.33    4906   336.4
    4911   333.9    4966  333.42  4968.8  332.92    4972  333.42  5127.4  334.88
  5139.2  333.92  5189.3  336.94  5218.8  339.35  5246.6  342.45    5293  343.36
  5481.9  350.49  5618.7  357.11  5633.5  358.97  5737.2  360.66  5848.2  364.43
#Mann= 10 ,-1 , 0
  3808.3      .1       0  3905.3     .05       0  4003.7      .1       0
  4800.2     .12       0  4889.4     .05       0    4966     .03       0
    4972     .05       0  5218.8     .12       0    5293     .05       0
  5737.2      .1       0
Bank Sta=4906,5189.3
XS Rating Curve= 0 ,0
Exp/Cntr=0.3,0.1

Type RM Length L Ch R = 1 ,99467   ,101,101,101
BEGIN DESCRIPTION:
UNT003 IN NURI 159.0
END DESCRIPTION:
XS GIS Cut Line= 4
      2310034.58     13359158.28      2308966.86     13359032.41
       2308506.8     13359041.09      2307991.53     13359430.79
#Sta/Elev= 30
  3726.8  375.46  3883.1  369.39    3915  369.24  3981.7  366.23  4166.7  359.72
  4327.8  351.98  4635.4  345.92  4700.4  345.42  4723.4  347.69  4730.6  349.67
  4750.7  351.08  4881.5  351.86  5166.2  351.18  5265.3  350.82  5279.8  350.75
  5286.1  348.79  5295.6  348.49  5300.6  347.46  5308.9  347.37  5326.8  344.73
  5329.5  344.23  5332.8  344.73  5379.2  345.12  5429.6  347.44  5614.9  356.18
    5644  359.18  5729.3  361.38  5779.2  361.36    5862  364.04  5908.1  365.75
#Mann= 11 ,-1 , 0
  3726.8      .1       0  3883.1     .05       0  3981.7      .1       0
  4881.5     .12       0  5166.2      .1       0  5265.3     .05       0
  5295.6      .1       0  5326.8     .07       0  5332.8      .1       0
  5379.2     .05       0    5862      .1       0
#XS Ineff= 1 ,-1
  4315.2 4819.03  351.88
Permanent Ineff=
       F
Bank Sta=5300.6,5429.6
XS Rating Curve= 0 ,0
Exp/Cntr=0.3,0.1

Type RM Length L Ch R = 1 ,99366   ,378,378,378
BEGIN DESCRIPTION:
Mapping XS 24e96b5a
END DESCRIPTION:
XS GIS Cut Line= 4
      2310117.08     13358745.94      2308992.91      13358923.9
      2308419.99     13358954.28      2307922.21     13359391.47
#Sta/Elev= 30
  3615.9  376.99    3746   371.9  3845.9  367.83  3924.9  364.86  3929.1  364.82
  3945.8  360.79    3969  359.37    4000  361.47  4050.6  360.94    4243   354.7
  4536.6  347.84  4901.6  342.58  4959.5  342.19  4979.6  341.92  4996.6  340.32
  4999.3  339.82  5002.6  340.32  5019.6  342.11  5069.7  341.67  5119.8  343.32
  5129.8  341.62  5158.3  341.94  5270.3  342.01  5430.4  346.33  5504.6  350.54
  5594.7  354.14    5735  359.86  5869.9  363.42    5976  365.97  5990.3  367.36
#Mann= 13 ,-1 , 0
  3615.9      .1       0    3746     .05       0  3845.9      .1       0
  3924.9     .05       0  3945.8      .1       0  4901.6     .12       0
  4996.6     .07       0  5002.6     .12       0  5158.3      .1       0
  5270.3     .05       0  5504.6      .1       0  5594.7     .05       0
  5869.9      .1       0
Bank Sta=4959.5,5019.6
XS Rating Curve= 0 ,0
Exp/Cntr=0.3,0.1

Type RM Length L Ch R = 1 ,98988   ,418,418,418
BEGIN DESCRIPTION:
UNT003 IN NURI 158.0
END DESCRIPTION:
XS GIS Cut Line= 4
      2309388.28       13358496.      2308861.83      13358528.9
      2308166.14     13358679.33      2307931.93     13358997.85
#Sta/Elev= 30
  4264.1  357.77  4353.9  354.89    4455  349.82  4519.2  347.81  4595.3  346.49
  4625.4  347.11  4685.5  344.82  4791.1  342.62  4950.9  340.92  4961.3  340.72
  5000.4  340.05  5061.8  340.72  5112.9  339.87  5149.5  340.71  5212.3  339.39
    5215  338.89  5218.3  339.39    5231  340.23  5280.2  340.33  5324.4  342.39
    5467  346.51  5587.2  351.17  5608.1  352.64  5636.8  353.23  5649.8   354.4
  5679.1  354.57  5764.7  357.67  5829.5  358.57  5872.6  360.54  5898.7  360.74
#Mann= 5 ,-1 , 0
  4264.1      .1       0  4961.3     .12       0  5149.5      .1       0
  5212.3     .07       0  5218.3      .1       0
Bank Sta=4950.9,5061.8
XS Rating Curve= 0 ,0
Exp/Cntr=0.3,0.1

Type RM Length L Ch R = 1 ,98570   ,590,590,590
BEGIN DESCRIPTION:
UNT003 IN NURI 157.0
END DESCRIPTION:
XS GIS Cut Line= 3
      2309134.52     13357856.69      2308579.79     13358134.05
      2307790.07     13358782.75
#Sta/Elev= 30
  4099.1  356.86  4262.4  351.31  4463.7  346.76  4536.3  343.91  4542.7  342.71
  4558.7  341.99    4581  342.64  4587.5  344.48  4597.8  343.89  4603.4  344.66
  4609.8  342.32  4654.5  339.94  4717.7  338.15  4776.5  338.02  4779.3  337.52
  4782.5  338.02  4796.7  338.16  4836.9   339.2  4964.7  339.64  5009.4  338.15
  5071.4  339.39  5170.6  340.32  5226.7  341.78  5347.8  346.37  5355.7  347.57
  5440.4  349.84  5475.5  351.66  5539.4  352.68  5617.6  355.62  5741.3  358.06
#Mann= 5 ,-1 , 0
  4099.1      .1       0  4776.5     .07       0  4782.5      .1       0
  4796.7     .12       0  5009.4      .1       0
Bank Sta=4964.7,5071.4
XS Rating Curve= 0 ,0
Exp/Cntr=0.3,0.1

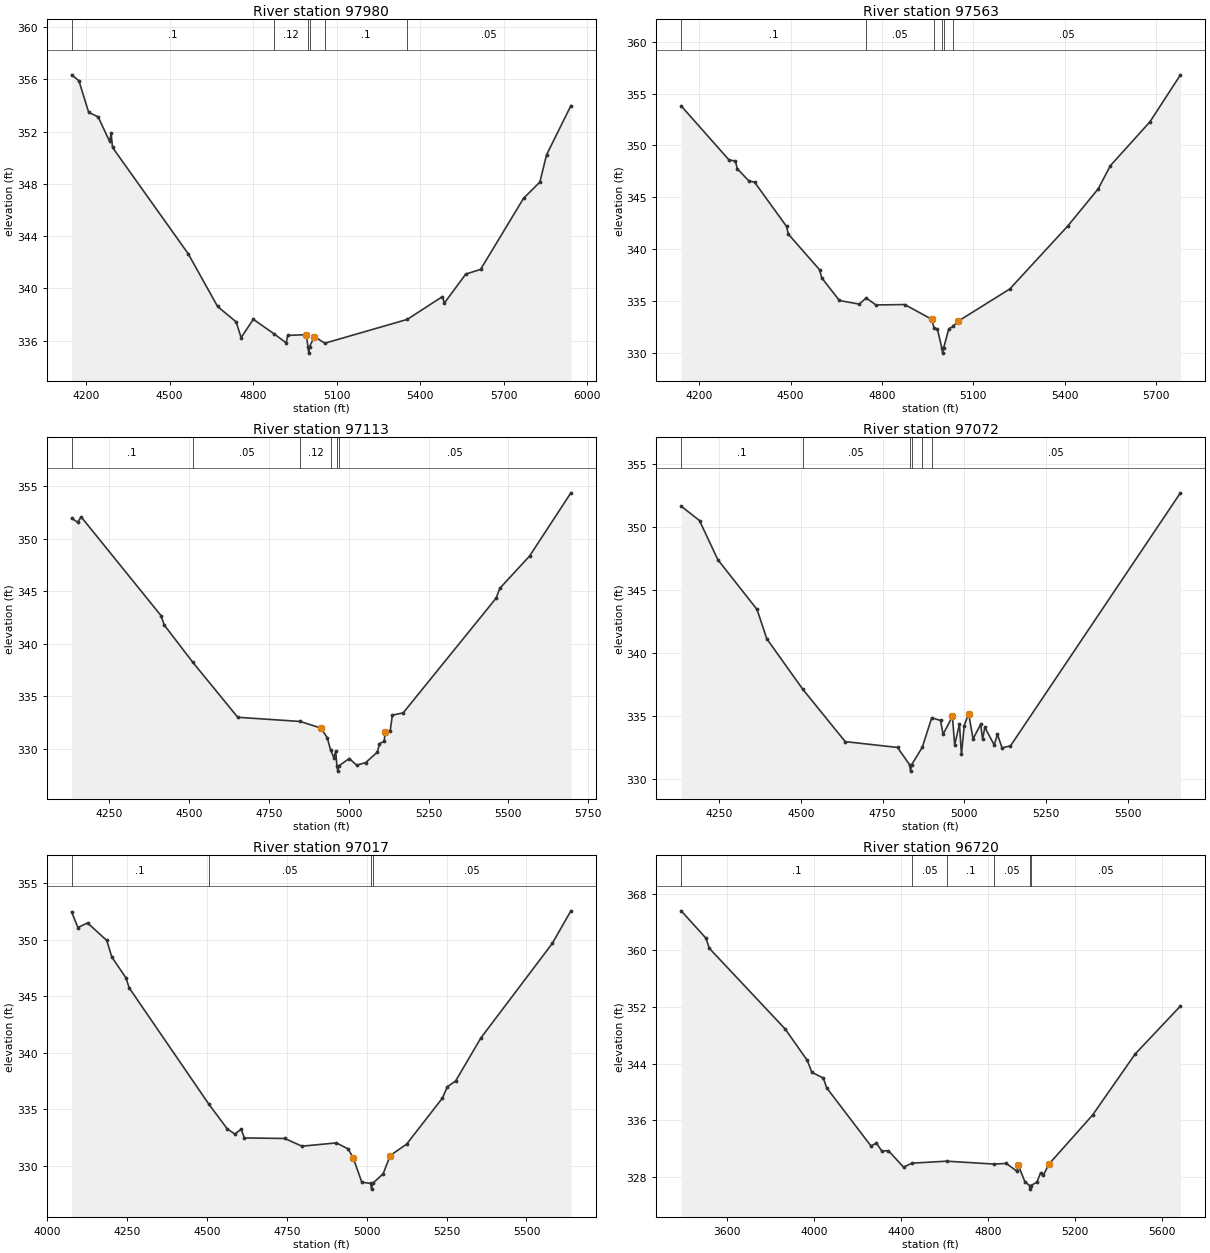
Type RM Length L Ch R = 1 ,97980   ,417,417,417
BEGIN DESCRIPTION:
UNT003 IN NURI 156.0
END DESCRIPTION:
XS GIS Cut Line= 4
      2309049.85     13357715.69       2308622.1     13357828.51
      2307808.89     13357960.12      2307321.38     13357758.56
#Sta/Elev= 30
  4147.8  356.34  4173.9  355.89    4209  353.47  4243.1  353.12  4284.4  351.24
  4289.6  351.85  4294.8  350.78  4566.5  342.65  4672.2  338.61  4738.9  337.43
  4756.7  336.23  4800.6  337.63  4876.2   336.5  4918.8  335.82    4924   336.4
  4990.7  336.45  4996.8  335.54  4999.6  335.04  5002.8  335.54  5020.1   336.3
  5057.6   335.8  5353.4  337.62  5480.2  339.37  5486.8  338.87  5563.9  341.09
  5617.1  341.45  5771.4  346.89    5830  348.13  5853.9  350.21  5941.5  353.98
#Mann= 6 ,-1 , 0
  4147.8      .1       0  4876.2     .12       0  4996.8     .07       0
  5002.8     .12       0  5057.6      .1       0  5353.4     .05       0
Bank Sta=4990.7,5020.1
XS Rating Curve= 0 ,0
Exp/Cntr=0.3,0.1

Type RM Length L Ch R = 1 ,97563   ,450,450,450
BEGIN DESCRIPTION:
UNT003 IN NURI 155.0
END DESCRIPTION:
XS GIS Cut Line= 3
      2308887.71     13357296.86      2308087.72     13357546.85
      2307287.76     13357546.85
#Sta/Elev= 30
  4141.2  353.81  4298.3  348.59  4319.3  348.49  4325.1  347.75  4362.8  346.59
  4382.2  346.44  4486.9  342.18  4492.7  341.44  4595.4  337.99  4602.2  337.22
  4660.3  335.03  4725.3  334.68  4748.2  335.27  4780.3   334.6  4874.6  334.64
  4963.1  333.22  4971.1  332.36  4981.8  332.29  4996.3  330.45  4999.1  329.95
  5002.3  330.45  5019.3   332.3  5032.5  332.52  5049.3  333.02  5219.3  336.14
  5409.3  342.21  5509.3   345.8  5549.3  348.04  5679.3  352.28  5779.3  356.81
#Mann= 6 ,-1 , 0
  4141.2      .1       0  4748.2     .05       0  4971.1     .12       0
  4996.3     .07       0  5002.3     .12       0  5032.5     .05       0
Bank Sta=4963.1,5049.3
XS Rating Curve= 0 ,0
Exp/Cntr=0.3,0.1

Type RM Length L Ch R = 1 ,97113   ,41,41,41
BEGIN DESCRIPTION:
Mapping XS 1569f9b6
END DESCRIPTION:
XS GIS Cut Line= 4
      2308797.47     13357142.65      2307984.99     13357114.87
      2307842.62     13357205.15      2307283.62     13357364.87
#Sta/Elev= 30
  4132.7  351.94  4151.7  351.56  4162.5  352.07  4412.6  342.66  4422.6  341.77
  4511.7  338.23  4652.7  332.98  4848.5  332.58  4912.9  331.95  4932.9  331.03
  4943.5  329.85  4953.5  329.14  4959.4  329.73  4963.1  328.35  4965.8  327.85
  4969.1  328.35  5001.8  329.05  5025.3  328.41  5053.5  328.67  5089.9  329.67
  5096.4  330.46  5111.1  330.69  5114.2  331.54  5129.7  331.66  5136.8  333.19
  5170.6   333.4  5461.8  344.34  5472.9  345.26  5566.5  348.35  5695.6  354.36
#Mann= 6 ,-1 , 0
  4132.7      .1       0  4511.7     .05       0  4848.5     .12       0
  4943.5     .05       0  4963.1     .03       0  4969.1     .05       0
Bank Sta=4912.9,5114.2
XS Rating Curve= 0 ,0
Exp/Cntr=0.3,0.1

Type RM Length L Ch R = 1 ,97072   ,55,55,55
BEGIN DESCRIPTION:
UNT003 IN NURI 154.0
END DESCRIPTION:
XS GIS Cut Line= 4
      2308769.74     13357094.04      2307981.51     13357062.79
      2307839.15     13357166.96      2307297.48     13357323.21
#Sta/Elev= 30
    4133  351.68  4189.1  350.54  4245.1  347.44  4365.2  343.49  4395.2  341.16
  4505.2  337.16  4635.4     333  4795.5  332.54  4832.6  331.16  4835.3  330.66
  4838.6  331.16  4871.3  332.55  4900.2  334.89  4927.3  334.68    4935  333.58
  4963.7     335  4970.5  332.73  4985.2  334.39  4991.3  331.98  4999.8  334.28
  5013.3  335.22  5026.9  333.22    5050  334.37  5056.2  333.19  5062.8  334.14
  5091.7  332.73  5101.6  333.58  5115.6  332.51  5141.4  332.66    5662  352.74
#Mann= 6 ,-1 , 0
    4133      .1       0  4505.2     .05       0  4832.6     .03       0
  4838.6     .05       0  4871.3     .12       0  4900.2     .05       0
Bank Sta=4963.7,5013.3
XS Rating Curve= 0 ,0
Exp/Cntr=0.3,0.1

Type RM Length L Ch R = 1 ,97017   ,297,297,297
BEGIN DESCRIPTION:
UNT003 IN NURI 153.0
END DESCRIPTION:
XS GIS Cut Line= 4
      2308797.45      13357048.9      2307984.99     13357003.76
      2307787.07     13357125.29      2307291.66     13357270.79
#Sta/Elev= 30
  4076.8  352.47  4096.6  351.09  4126.6   351.5  4186.7  349.95  4202.8  348.47
  4246.8  346.64  4256.8  345.76  4505.6  335.49  4563.3   333.3  4587.3  332.82
  4607.3  333.25  4617.4  332.48  4743.6  332.43  4797.6  331.75  4905.4  332.04
  4942.2   331.5  4957.6  330.74  4984.7  328.57  5012.6  328.45  5015.3  327.95
  5018.6  328.45  5051.6  329.31  5073.6  330.92    5125  331.93  5236.7  335.99
  5252.4     337  5278.4  337.52  5357.8  341.34  5580.7  349.68  5639.1  352.57
#Mann= 4 ,-1 , 0
  4076.8      .1       0  4505.6     .05       0  5012.6     .03       0
  5018.6     .05       0
Bank Sta=4957.6,5073.6
XS Rating Curve= 0 ,0
Exp/Cntr=0.3,0.1

Type RM Length L Ch R = 1 ,96720   ,462,462,462
BEGIN DESCRIPTION:
Mapping XS 0d0698cf
END DESCRIPTION:
XS GIS Cut Line= 3
      2309252.32     13356899.58      2308578.74     13356493.35
      2307165.59     13357024.58
#Sta/Elev= 30
    3390  365.58    3504  361.71  3519.6  360.28    3869  348.86    3970  344.44
  3991.3  342.75  4043.7  341.96  4059.2  340.57  4263.1  332.35  4287.9  332.77
  4312.8  331.64  4343.1  331.69  4412.7  329.37    4452  329.93  4610.6  330.21
  4830.4   329.8  4885.5  329.89  4935.3  328.77  4940.6  329.62  4970.8  327.31
  4992.7  326.76  4995.5  326.26  4998.7  326.76    5026  327.26    5043  328.55
  5056.2  328.25  5081.1  329.79    5282  336.72  5477.7  345.34  5686.3  352.13
#Mann= 6 ,-1 , 0
    3390      .1       0    4452     .05       0  4610.6      .1       0
  4830.4     .05       0  4992.7     .03       0  4998.7     .05       0
Bank Sta=4940.6,5081.1
XS Rating Curve= 0 ,0
Exp/Cntr=0.3,0.1

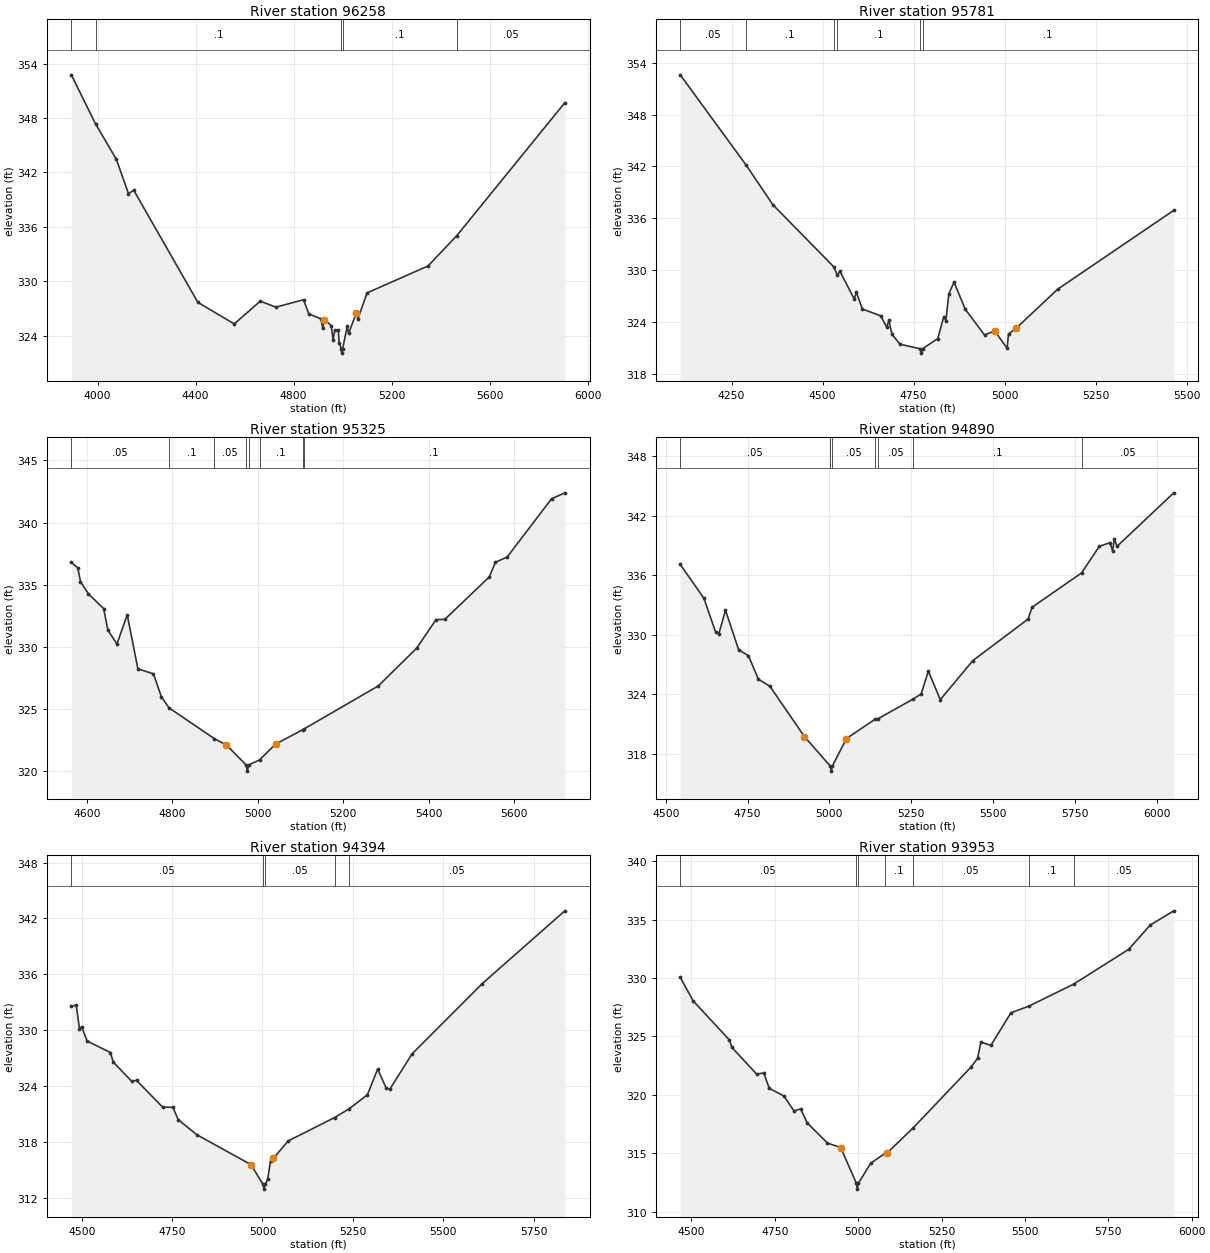
Type RM Length L Ch R = 1 ,96258   ,477,477,477
BEGIN DESCRIPTION:
UNT003 IN NURI 152.0
END DESCRIPTION:
XS GIS Cut Line= 3
       2308737.7     13355596.87      2307937.72     13356346.85
      2307137.75     13356796.84
#Sta/Elev= 30
  3892.6  352.76  3991.4  347.35  4076.5  343.44  4125.8  339.66  4147.3  340.03
  4409.1  327.67  4557.6  325.29  4663.6   327.8  4727.6  327.14  4840.4  327.96
  4861.9  326.39  4911.3  325.86  4918.6  324.84  4925.4  325.77  4953.7   325.1
  4961.1  323.48  4967.9  324.63  4982.1  324.61  4985.7  323.21  4994.1  322.57
  4996.9  322.07  5000.1  322.57  5018.8  325.04  5024.5  324.24  5056.4  326.55
  5062.1  325.84  5099.7  328.71  5348.3  331.68  5465.8  335.02    5907  349.69
#Mann= 5 ,-1 , 0
  3892.6     .05       0  3991.4      .1       0  4994.1     .07       0
  5000.1      .1       0  5465.8     .05       0
Bank Sta=4925.4,5056.4
XS Rating Curve= 0 ,0
Exp/Cntr=0.3,0.1

Type RM Length L Ch R = 1 ,95781   ,456,456,456
BEGIN DESCRIPTION:
UNT003 IN NURI 151.0
END DESCRIPTION:
XS GIS Cut Line= 3
      2308687.73     13355496.85      2307887.72     13355896.85
      2307537.73     13356196.85
#Sta/Elev= 30
  4108.9   352.6  4289.4  342.19  4363.3  337.58  4530.1  330.42  4540.5  329.44
  4547.7  329.87  4586.9  326.66  4592.5  327.47  4609.2  325.52  4659.5  324.74
  4676.3   323.4  4681.9  324.26  4690.3  322.61  4712.6  321.45  4768.3  320.92
  4771.1  320.42  4774.3  320.92  4816.1   322.1  4832.8  324.65  4838.4  324.19
  4846.8   327.3  4860.8  328.63  4891.5  325.51  4944.6  322.52  4972.6  322.99
  5006.6  320.98  5010.5  322.63  5031.3  323.29  5145.5  327.81  5464.3  336.93
#Mann= 6 ,-1 , 0
  4108.9     .05       0  4289.4      .1       0  4530.1     .05       0
  4540.5      .1       0  4768.3     .07       0  4774.3      .1       0
Bank Sta=4972.6,5031.3
XS Rating Curve= 0 ,0
Exp/Cntr=0.3,0.1

Type RM Length L Ch R = 1 ,95325   ,435,435,435
BEGIN DESCRIPTION:
UNT003 IN NURI 150.0
END DESCRIPTION:
XS GIS Cut Line= 3
      2308337.73     13355296.85      2307937.72     13355446.85
      2307237.74     13355646.85
#Sta/Elev= 30
  4563.8   336.8  4578.9  336.36  4585.2  335.26  4603.9  334.27  4639.5  333.09
  4649.3  331.36  4670.6  330.24  4694.6  332.59  4719.6  328.25  4756.1  327.84
  4774.7  325.98  4792.5  325.11  4898.6  322.63  4926.9  322.12  4972.9  320.52
  4975.6  320.02  4978.9  320.52  5004.3  320.92  5041.7  322.19  5105.9  323.36
  5107.3  323.39  5282.2  326.87  5371.9   329.9  5417.4   332.2  5438.2  332.23
  5542.2  335.64  5556.5  336.82  5583.8  337.23  5687.8  341.92    5719   342.4
#Mann= 8 ,-1 , 0
  4563.8     .05       0  4792.5      .1       0  4898.6     .05       0
  4972.9     .03       0  4978.9     .05       0  5004.3      .1       0
  5105.9     .05       0  5107.3      .1       0
Bank Sta=4926.9,5041.7
XS Rating Curve= 0 ,0
Exp/Cntr=0.3,0.1

Type RM Length L Ch R = 1 ,94890   ,496,496,496
BEGIN DESCRIPTION:
UNT003 IN NURI 149.0
END DESCRIPTION:
XS GIS Cut Line= 3
      2308325.31     13355048.91      2307920.78     13355008.72
      2306908.62     13355444.73
#Sta/Elev= 30
  4544.1   337.1  4616.2   333.7  4652.2  330.28  4662.3  330.12  4682.4  332.48
  4722.6  328.49  4752.7  327.88  4782.9  325.51  4817.9  324.81  4923.7  319.72
    5003  316.73  5005.8  316.23    5009  316.73    5052  319.52  5140.7  321.49
  5148.3  321.51  5256.7  323.52  5280.6  324.02  5302.4  326.33  5339.1  323.45
  5438.6  327.39  5607.3  331.58  5619.7  332.78  5770.9  336.24    5825  338.92
  5857.7   339.3  5865.8  338.49  5871.3  339.64  5879.5  338.93  6052.7  344.33
#Mann= 7 ,-1 , 0
  4544.1     .05       0    5003     .03       0    5009     .05       0
  5140.7      .1       0  5148.3     .05       0  5256.7      .1       0
  5770.9     .05       0
Bank Sta=4923.7,5052
XS Rating Curve= 0 ,0
Exp/Cntr=0.3,0.1

Type RM Length L Ch R = 1 ,94394   ,441,441,441
BEGIN DESCRIPTION:
UNT003 IN NURI 148.0
END DESCRIPTION:
XS GIS Cut Line= 3
      2308187.71     13354846.85      2307737.72     13354546.85
      2306937.76     13354746.85
#Sta/Elev= 30
  4471.2  332.56  4484.7  332.68  4493.7  330.14  4499.7  330.35  4514.8  328.82
  4579.4  327.58  4586.9  326.57  4637.9   324.5  4651.5  324.59  4723.6  321.72
  4752.1  321.69  4767.1  320.36  4818.2  318.75  4968.5  315.53  5001.5   313.4
  5004.3   312.9  5007.5   313.4  5014.6  314.01  5022.3  315.93  5030.1  316.21
  5071.3  318.08  5199.4  320.59  5239.3  321.52  5290.3  323.04  5318.7   325.8
  5341.9   323.8  5352.2  323.63    5414  327.44  5607.3  334.96  5836.6  342.81
#Mann= 5 ,-1 , 0
  4471.2     .05       0  5001.5     .03       0  5007.5     .05       0
  5199.4      .1       0  5239.3     .05       0
Bank Sta=4968.5,5030.1
XS Rating Curve= 0 ,0
Exp/Cntr=0.3,0.1

Type RM Length L Ch R = 1 ,93953   ,535,535,535
BEGIN DESCRIPTION:
UNT003 IN NURI 147.0
END DESCRIPTION:
XS GIS Cut Line= 4
      2308243.35     13354242.38      2307995.64     13354105.49
      2307141.74     13354138.08      2306965.75      13354431.4
#Sta/Elev= 30
  4466.7  330.07  4505.4  328.05  4614.2   324.7  4621.7  324.06  4695.6  321.78
  4717.3  321.88  4733.4  320.57  4777.7   319.9  4807.7  318.62  4827.7   318.8
  4847.7  317.59  4907.8  315.88  4947.8  315.49  4994.8  312.43  4997.6  311.93
  5000.8  312.43  5037.8  314.15    5081     315  5087.9  315.05  5165.6  317.19
  5338.1  322.37  5358.1  323.13  5368.1  324.52  5398.1  324.24  5458.2  327.03
  5512.2   327.6  5646.7  329.49  5811.5  332.47  5875.7  334.54  5946.3  335.76
#Mann= 7 ,-1 , 0
  4466.7     .05       0  4994.8     .03       0  5000.8     .05       0
    5081      .1       0  5165.6     .05       0  5512.2      .1       0
  5646.7     .05       0
Bank Sta=4947.8,5087.9
XS Rating Curve= 0 ,0
Exp/Cntr=0.3,0.1

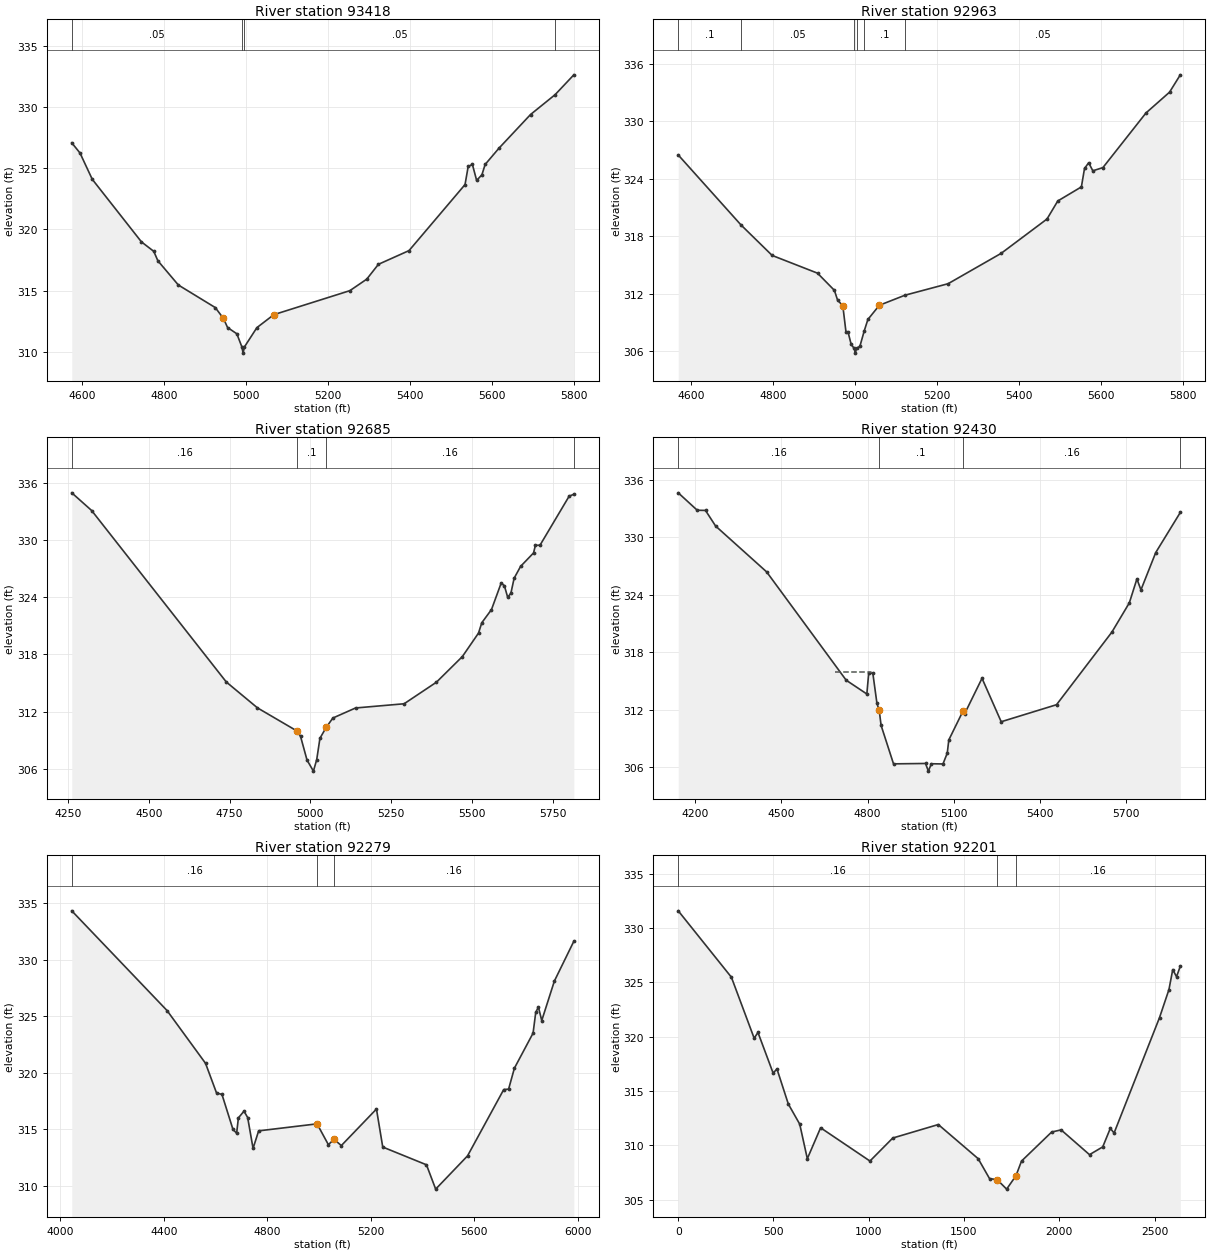
Type RM Length L Ch R = 1 ,93418   ,455,455,455
BEGIN DESCRIPTION:
UNT003 IN NURI 146.0
END DESCRIPTION:
XS GIS Cut Line= 3
      2308237.71     13353596.85      2307837.72     13353596.85
      2307037.74     13353396.86
#Sta/Elev= 30
    4575  327.06    4595  326.23    4625  324.08    4745  318.97    4775   318.2
    4785  317.43    4835  315.45    4925  313.61    4945  312.72    4955  311.98
  4977.6  311.47    4990  310.39  4992.8  309.89    4996  310.39  5026.5  311.97
  5067.8  313.03  5253.3  314.99  5294.5  315.93  5322.9  317.14  5397.6  318.26
  5534.2  323.65  5541.9  325.13  5552.2  325.29  5562.5  323.99  5575.4  324.45
  5583.2  325.29  5616.7  326.61    5694  329.37  5753.9  330.99  5799.6  332.61
#Mann= 4 ,-1 , 0
    4575     .05       0    4990     .03       0    4996     .05       0
  5753.9      .1       0
Bank Sta=4945,5067.8
XS Rating Curve= 0 ,0
Exp/Cntr=0.3,0.1

Type RM Length L Ch R = 1 ,92963   ,278,278,278
BEGIN DESCRIPTION:
UNT003 IN NURI 145.0
END DESCRIPTION:
XS GIS Cut Line= 3
      2308237.76     13353246.86      2307837.72     13353146.85
      2307037.71     13352996.85
#Sta/Elev= 30
    4568  326.49  4721.3  319.19  4797.4  316.01  4908.2  314.16  4949.4  312.37
  4957.2  311.35    4970  310.76  4977.8  307.99  4982.9  307.99  4990.5  306.72
  4997.7  306.32  5000.4  305.82  5003.7  306.32  5011.7  306.53  5022.3  308.14
  5031.2  309.33  5059.2  310.81  5121.7  311.86  5227.1  313.06  5356.8  316.23
  5468.7  319.81    5495  321.69  5552.7  323.16  5560.3  325.08  5570.5  325.68
  5580.6  324.84  5605.2  325.17  5710.4  330.87    5768  333.04  5794.3  334.85
#Mann= 6 ,-1 , 0
    4568      .1       0  4721.3     .05       0  4997.7     .03       0
  5003.7     .05       0  5022.3      .1       0  5121.7     .05       0
Bank Sta=4970,5059.2
XS Rating Curve= 0 ,0
Exp/Cntr=0.3,0.1

Type RM Length L Ch R = 1 ,92685   ,255,255,255
BEGIN DESCRIPTION:
UNT003 IN NURI 144.0
END DESCRIPTION:
XS GIS Cut Line= 3
      2308512.75     13353142.64       2307971.1     13352875.29
       2307023.2      13352837.1
#Sta/Elev= 30
    4262  334.92  4323.4  333.07  4739.9  315.12  4836.3  312.41  4959.5  309.97
  4969.5  309.43  4989.5  306.95  5009.3  305.79  5019.5  306.99  5029.5  309.23
  5049.6  310.41  5069.6  311.35  5139.6   312.4  5289.8  312.84  5389.8   315.1
  5469.9  317.78  5519.9  320.24    5530  321.32    5560   322.7    5590  325.48
    5600  325.19    5610  323.99    5620  324.41    5630  325.98    5650  327.22
  5690.1  328.63  5695.8  329.42  5710.1  329.44  5800.2  334.57  5814.7  334.77
#Mann= 4 ,-1 , 0
    4262     .16       0  4959.5      .1       0  5049.6     .16       0
  5814.7     .05       0
Bank Sta=4959.5,5049.6
XS Rating Curve= 0 ,0
Exp/Cntr=0.3,0.1

Type RM Length L Ch R = 1 ,92430   ,151,151,151
BEGIN DESCRIPTION:
Mapping XS 6fa441af
END DESCRIPTION:
XS GIS Cut Line= 3
      2308624.87     13353122.77      2308005.06     13352627.97
      2307062.54     13352786.79
#Sta/Elev= 30
  4140.5  334.65  4206.7  332.83  4235.5  332.81  4270.7  331.18  4448.4  326.39
  4725.5  315.07  4797.5  313.63  4803.9  315.79  4818.3  315.81  4832.7  312.64
  4840.6  311.92  4847.1  310.35  4890.4  306.33  5001.9  306.37  5011.8  305.57
  5022.2  306.34  5062.7  306.32  5077.6  307.45    5083  308.83  5133.1  311.89
  5138.2  311.57  5198.7  315.27  5265.5  310.73  5458.2  312.51  5650.9  320.09
  5711.8  323.15  5738.2  325.65  5752.3  324.51  5803.8  328.41  5889.4   332.6
#Mann= 4 ,-1 , 0
  4140.5     .16       0  4840.6      .1       0  5133.1     .16       0
  5889.4     .05       0
#XS Ineff= 2 ,-1
 4685.47 4811.79  315.94    5200  5562.5  315.08
Permanent Ineff=
       T       T
Bank Sta=4840.6,5133.1
XS Rating Curve= 0 ,0
Exp/Cntr=0.3,0.1

Type RM Length L Ch R = 1 ,92279   ,78,78,78
BEGIN DESCRIPTION:
UNT003 IN NURI 143.0
END DESCRIPTION:
XS GIS Cut Line= 5
      2308700.35     13353104.51      2308137.87      13352588.9
      2307898.29      13352458.7      2307804.54     13352565.47
      2307064.95     13352752.97
#Sta/Elev= 30
  4044.6  334.32  4413.1   325.5  4561.7  320.84  4604.2  318.22  4625.2  318.09
  4667.7     315  4681.9  314.66  4688.7  316.02  4710.3  316.61  4724.5  316.05
  4745.4  313.32    4767  314.87  4992.8  315.49  5036.5  313.65  5058.3  314.12
  5086.6  313.57  5222.4   316.8  5246.7  313.44  5415.7  311.87  5451.3  309.72
  5574.5  312.66  5714.3  318.52  5733.2  318.56  5755.6  320.41  5827.8  323.51
  5838.1  325.34  5848.4  325.82  5861.3  324.62  5910.3  328.12  5985.4  331.63
#Mann= 3 , 0 , 0
  4044.6     .16       0  4992.8      .1       0  5058.3     .16       0
#XS Ineff= 2 ,-1
  4612.5 4706.82  316.44 5220.45  5985.4  316.59
Permanent Ineff=
       T       T
Bank Sta=4992.8,5058.3
XS Rating Curve= 0 ,0
Exp/Cntr=0.3,0.1

Type RM Length L Ch R = 1 ,92201   ,552,552,552
BEGIN DESCRIPTION:
Mapping XS 50e9cca9
END DESCRIPTION:
XS GIS Cut Line= 4
     2309572.658    13351590.419     2307972.968    13352422.071
     2307708.075    13352392.502     2307058.079    13352489.012
#Sta/Elev= 30
       0 331.601278.9879 325.485 398.554319.8614418.4818320.3967498.1926316.6435
518.1203317.0361577.9034313.7971637.6865311.9467677.5419308.7623747.2889311.6117
1006.349308.54721125.915310.66561365.048311.91021574.289308.76561634.072306.9267
1673.927306.83371723.746305.9591 1772.63 307.188 1801.82308.54241960.102  311.22
2009.753311.41822158.706309.13472228.218309.85252267.938311.55572287.799311.1321
2526.124321.75782575.775 324.3492595.635326.18662615.496325.52962635.356326.4998
#Mann= 3 , 0 , 0
       0     .16       01673.927      .1       0 1772.63     .16       0
Bank Sta=1673.927,1772.63
XS Rating Curve= 0 ,0
Exp/Cntr=0.3,0.1

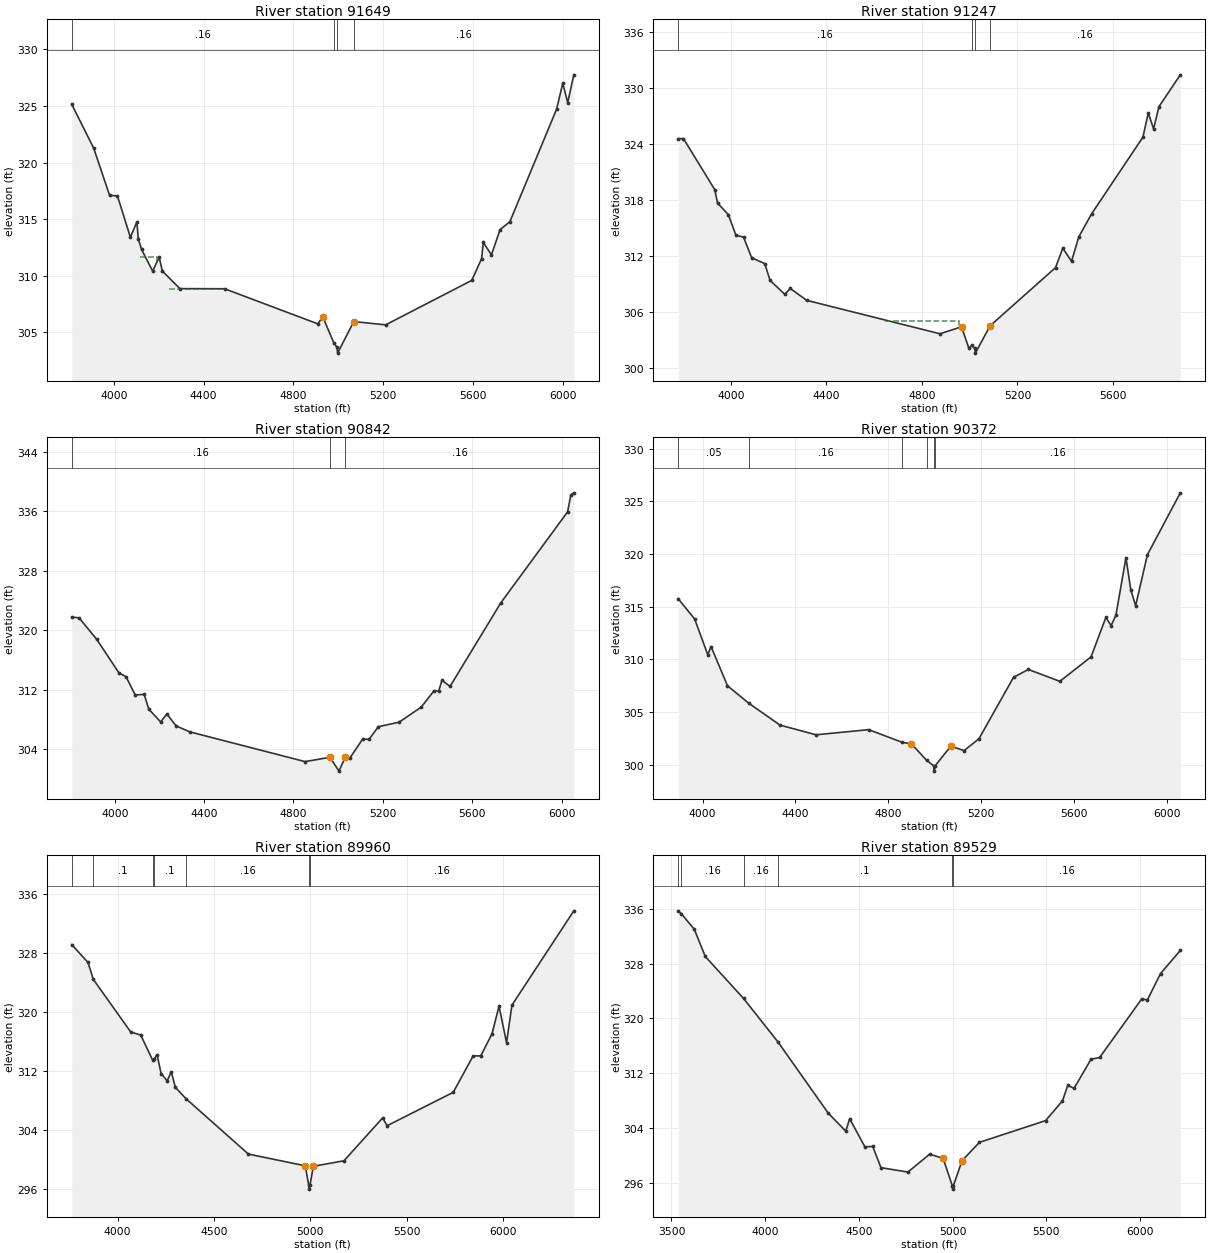
Type RM Length L Ch R = 1 ,91649   ,402,402,402
BEGIN DESCRIPTION:
UNT003 IN NURI 142.0
END DESCRIPTION:
XS GIS Cut Line= 3
      2308906.09     13351198.29      2308079.78     13351860.93
      2307042.13      13352416.7
#Sta/Elev= 30
  3813.2  325.14    3911  321.26  3981.4  317.11  4016.7  317.04  4074.3  313.39
  4103.1  314.75  4109.5  313.26  4123.9  312.32  4173.5   310.4  4202.3  311.63
  4216.7   310.4  4295.1  308.85  4493.6  308.84  4908.8  305.74  4931.4  306.34
  4981.4  304.02  4994.6  303.65  4997.4  303.15  5069.1  305.94  5211.3  305.65
  5594.8  309.58  5638.6   311.5  5646.1  312.93  5682.5  311.84  5720.7  314.06
  5764.6  314.77  5972.6  324.71  6000.2  327.01  6022.1   325.3  6049.5  327.75
#Mann= 4 ,-1 , 0
  3813.2     .16       0  4981.4     .07       0  4994.6    .016       0
  5069.1     .16       0
#XS Ineff= 3 ,-1
 4119.29 4194.74  311.68 4248.32 4494.34  308.85 5073.85 5304.57  305.87
Permanent Ineff=
       T       T       T
Bank Sta=4931.4,5069.1
XS Rating Curve= 0 ,0
Exp/Cntr=0.3,0.1

Type RM Length L Ch R = 1 ,91247   ,405,405,405
BEGIN DESCRIPTION:
UNT003 IN NURI 141.0
END DESCRIPTION:
XS GIS Cut Line= 3
      2308787.76     13351146.84      2307687.72     13351646.85
       2306887.7     13352046.87
#Sta/Elev= 30
  3779.3  324.59  3801.3  324.59    3932  319.14  3944.1  317.69  3989.1  316.46
    4021  314.24  4052.9  314.05  4086.9  311.83  4141.8  311.21  4163.8  309.42
  4225.3  307.93  4248.4  308.55  4317.6  307.28  4875.6   303.7  4965.7  304.45
    4996  302.19    5010  302.45    5021  302.13  5023.7  301.63  5085.5  304.56
  5359.4  310.78  5390.1  312.86  5426.5  311.46  5457.2  314.09  5510.3  316.53
  5725.5  324.75  5747.9  327.33  5770.3  325.64  5792.6  328.01  5882.1  331.42
#Mann= 4 ,-1 , 0
  3779.3     .16       0    5010     .07       0    5021     .16       0
  5085.5     .16       0
#XS Ineff= 1 ,-1
 4645.09 4955.37  305.07
Permanent Ineff=
       T
Bank Sta=4965.7,5085.5
XS Rating Curve= 0 ,0
Exp/Cntr=0.3,0.1

Type RM Length L Ch R = 1 ,90842   ,470,470,470
BEGIN DESCRIPTION:
UNT003 IN NURI 140.0
END DESCRIPTION:
XS GIS Cut Line= 3
      2308687.69     13351096.86      2307487.72     13351296.85
      2306687.72     13351946.86
#Sta/Elev= 30
  3807.8  321.79  3840.7  321.68  3919.3   318.8  4018.1  314.32  4051.1  313.75
  4091.6  311.32  4132.2  311.38  4152.5   309.4  4205.7  307.69  4233.6  308.76
  4274.1  307.17  4334.9  306.36    4852  302.35  4963.5  302.93  5003.8  301.07
  5031.5  302.92  5052.3  302.82  5109.8  305.38  5138.5  305.35  5180.2  307.05
  5272.8  307.65  5372.2  309.68  5429.4  311.89  5450.3  311.83  5464.6  313.28
  5501.1  312.47  5728.3  323.71  6027.1  335.94  6041.5  338.19  6055.1   338.5
#Mann= 3 , 0 , 0
  3807.8     .16       0  4963.5      .1       0  5031.5     .16       0
Bank Sta=4963.5,5031.5
XS Rating Curve= 0 ,0
Exp/Cntr=0.3,0.1

Type RM Length L Ch R = 1 ,90372   ,412,412,412
BEGIN DESCRIPTION:
UNT003 IN NURI 139.0
END DESCRIPTION:
XS GIS Cut Line= 3
       2308237.7     13350046.87      2307437.72     13350846.85
      2306787.73     13351646.84
#Sta/Elev= 30
  3895.4  315.76  3966.1  313.83  4022.7  310.43  4036.8  311.21  4107.5  307.49
  4199.1  305.83  4333.8  303.75  4489.3  302.83  4715.6  303.32  4860.8  302.11
  4899.5  301.98  4964.9  300.41  4995.5  299.88  4998.2  299.38  5001.5  299.88
  5069.1  301.75  5126.6  301.33  5190.5  302.46  5339.2  308.29  5403.1  309.04
  5538.9  307.91  5673.2  310.24  5737.1  313.99  5759.4   313.2  5780.3   314.2
  5823.4  319.66  5844.2  316.62    5865  315.09  5915.8  319.94  6057.5  325.82
#Mann= 6 ,-1 , 0
  3895.4     .05       0  4199.1     .16       0  4860.8     .05       0
  4964.9      .1       0  4995.5     .07       0  5001.5     .16       0
Bank Sta=4899.5,5069.1
XS Rating Curve= 0 ,0
Exp/Cntr=0.3,0.1

Type RM Length L Ch R = 1 ,89960   ,431,431,431
BEGIN DESCRIPTION:
UNT003 IN NURI 138.0
END DESCRIPTION:
XS GIS Cut Line= 3
      2307637.71     13349346.88      2307237.72     13350546.85
      2306637.73     13351746.83
#Sta/Elev= 30
  3762.1  329.15  3846.4  326.73  3873.7  324.45  4067.8  317.32  4120.5  316.88
  4181.7   313.5  4187.6  313.58  4204.8  314.23  4225.9  311.68  4257.5  310.68
  4278.6  311.93  4299.7  309.81  4355.5  308.26  4679.1  300.76  4974.3  299.17
  4992.4  296.51  4995.1  296.01  4998.4  296.51  5016.4  299.11  5175.1  299.85
  5376.4  305.68  5398.7   304.6  5742.5  309.13  5845.9  314.07  5885.1  314.07
  5943.8  317.06  5980.1  320.81  6019.2  315.86  6047.2  320.95  6368.6  333.73
#Mann= 7 ,-1 , 0
  3762.1     .05       0  3873.7      .1       0  4181.7     .05       0
  4187.6      .1       0  4355.5     .16       0  4992.4     .03       0
  4998.4     .16       0
Bank Sta=4974.3,5016.4
XS Rating Curve= 0 ,0
Exp/Cntr=0.3,0.1

Type RM Length L Ch R = 1 ,89529   ,456,456,456
BEGIN DESCRIPTION:
UNT003 IN NURI 137.0
END DESCRIPTION:
XS GIS Cut Line= 3
      2307637.74     13349196.83      2306837.72     13350396.85
      2306537.72     13351596.87
#Sta/Elev= 30
  3536.2  335.69  3553.2  335.25  3621.9     333  3680.5  329.03  3884.7  322.91
  4067.5   316.6    4337  306.17  4430.1  303.56  4451.1  305.36  4532.3  301.27
  4574.3  301.32  4617.9  298.23  4762.1  297.59  4877.8   300.2  4949.9  299.58
  4998.6   295.6  5001.4   295.1  5004.6   295.6  5050.6  299.25  5143.4  301.92
  5496.4  305.09  5586.6  307.97    5615  310.24  5648.5   309.8  5738.6  314.03
    5785   314.3  6009.2  322.83  6040.1  322.71  6109.7  326.54  6215.4  329.91
#Mann= 6 ,-1 , 0
  3536.2      .1       0  3553.2     .16       0  3884.7     .16       0
  4067.5      .1       0  4998.6     .03       0  5004.6     .16       0
Bank Sta=4949.9,5050.6
XS Rating Curve= 0 ,0
Exp/Cntr=0.3,0.1