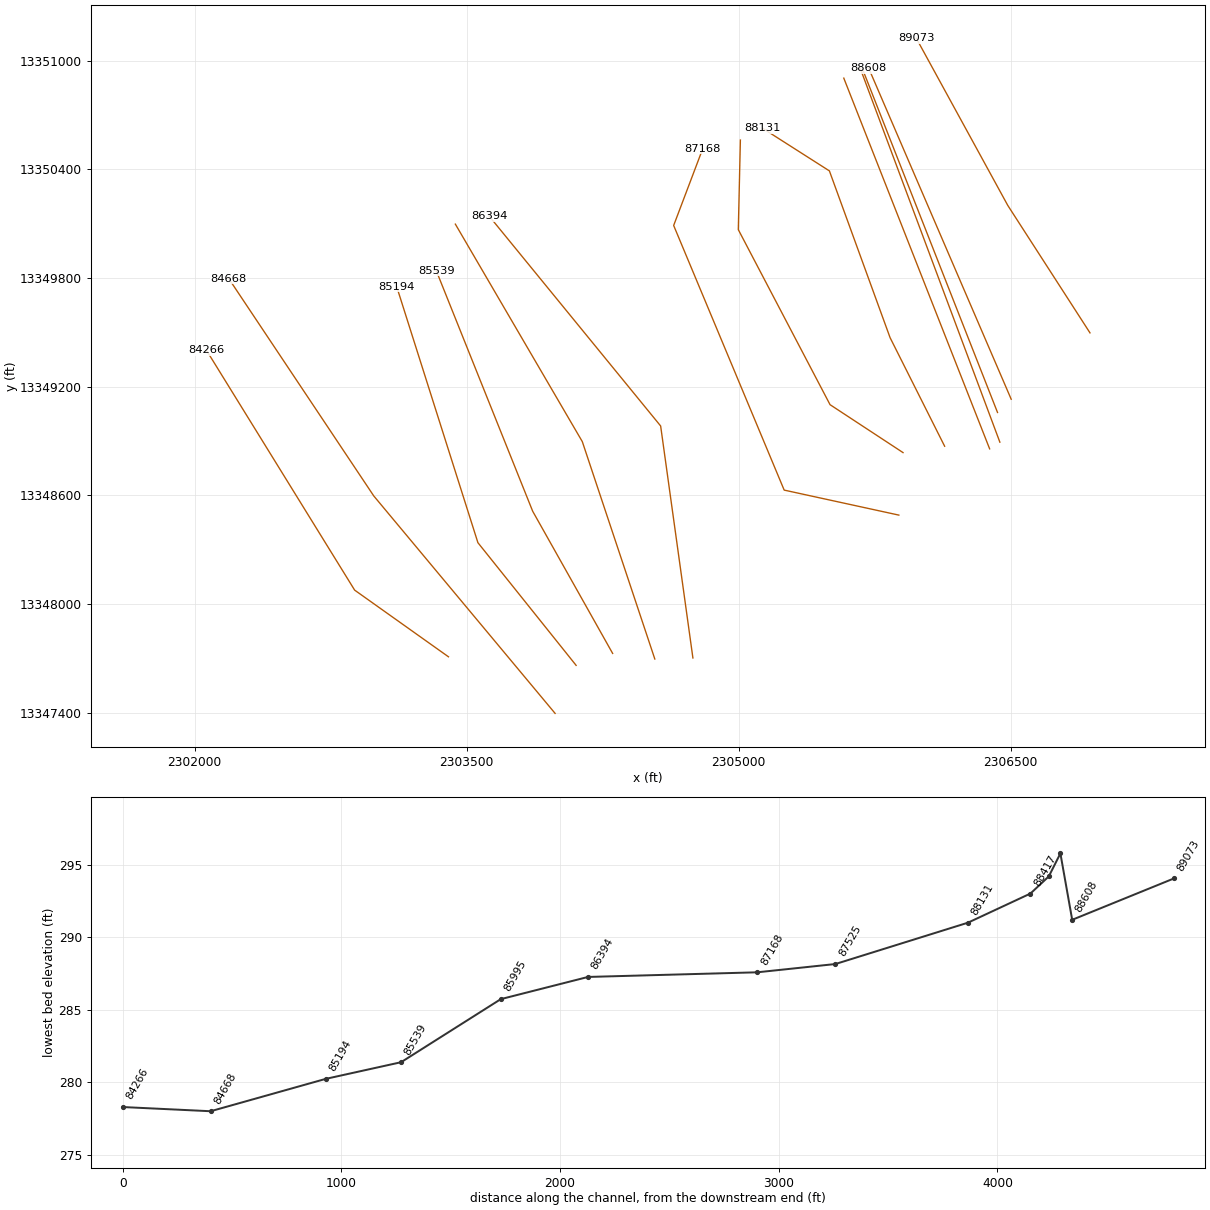
HEC-RAS study UNT003 IN NURI.prj: UNT003 IN NURI Base Level Engineering

--- UNT003 IN NURI.g01 (geometry) --- (continued)

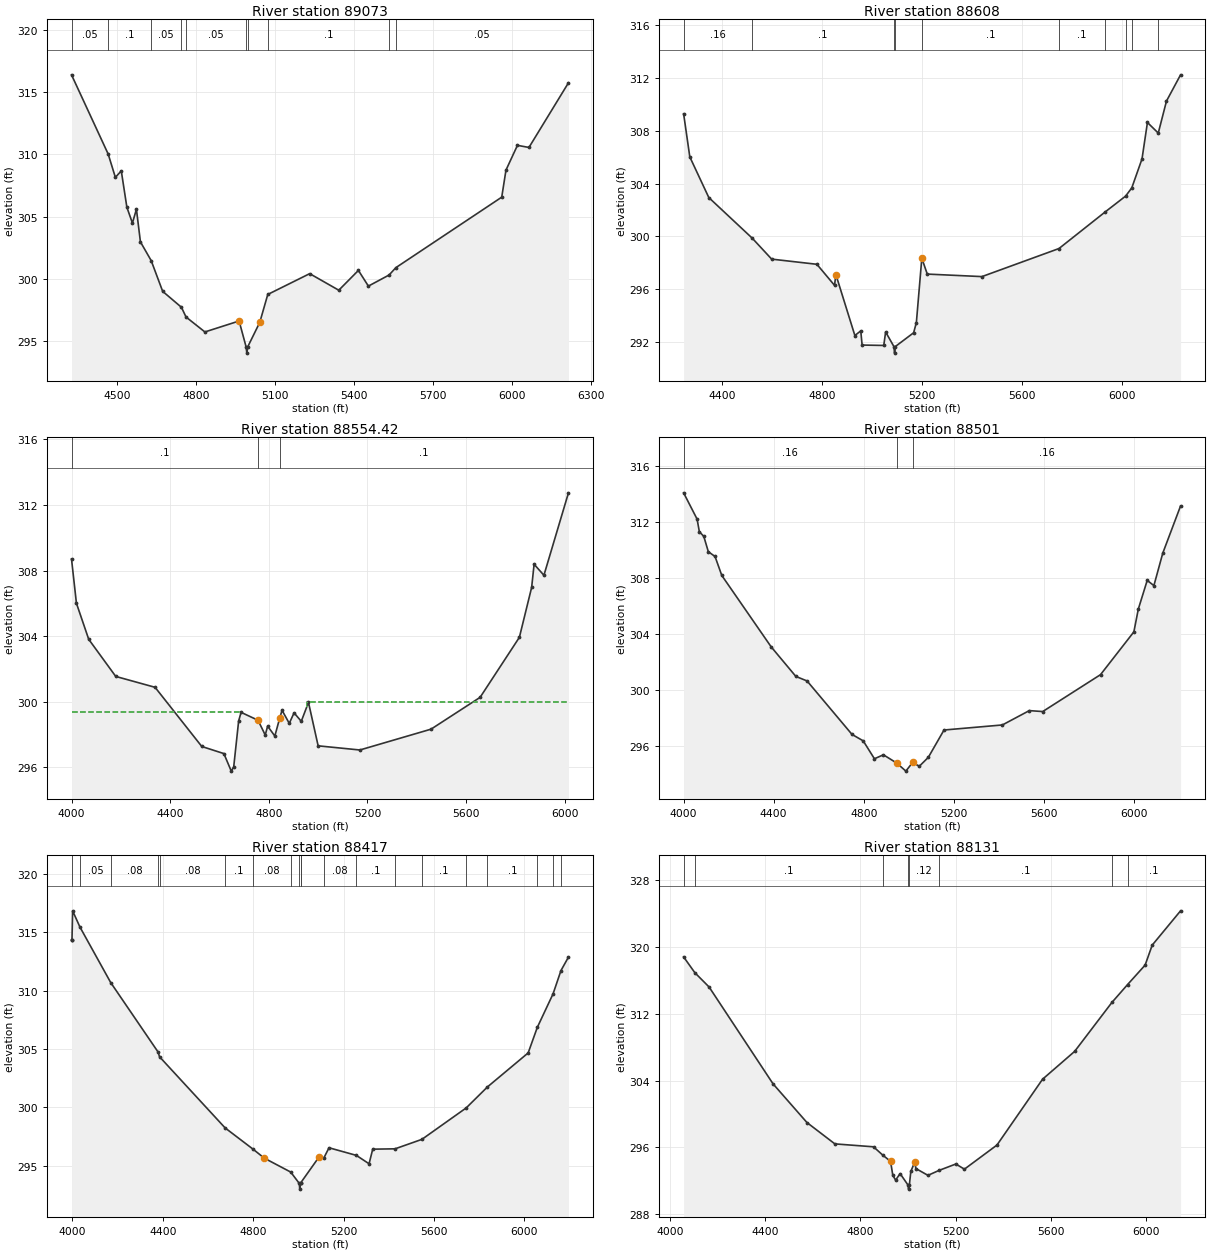
Type RM Length L Ch R = 1 ,89073   ,465,465,465
BEGIN DESCRIPTION:
UNT003 IN NURI 136.0
END DESCRIPTION:
XS GIS Cut Line= 3
      2306937.74     13349496.82      2306484.34     13350200.24
        2305980.     13351122.35
#Sta/Elev= 30
  4327.1  316.38  4466.4  310.02  4493.7  308.15  4516.2  308.67  4537.4  305.75
  4558.5  304.48  4573.7  305.59  4588.9  302.97  4629.7  301.47  4673.4     299
  4744.7  297.72  4762.1  296.94  4833.8  295.74  4963.8  296.62  4990.4  294.54
  4993.1  294.04  4996.4  294.54  5042.3  296.51  5072.7  298.75    5232  300.42
  5342.5  299.09    5417  300.68  5454.9  299.42  5533.5  300.31  5559.2   300.9
  5961.5  306.56  5977.6  308.73  6021.2  310.72  6064.9  310.55    6215  315.74
#Mann= 10 ,-1 , 0
  4327.1     .05       0  4466.4      .1       0  4629.7     .05       0
  4744.7      .1       0  4762.1     .05       0  4990.4     .03       0
  4996.4     .05       0  5072.7      .1       0  5533.5      .1       0
  5559.2     .05       0
Bank Sta=4963.8,5042.3
XS Rating Curve= 0 ,0
Exp/Cntr=0.3,0.1

Type RM Length L Ch R = 1 ,88608   ,54,54,54
BEGIN DESCRIPTION:
Mapping XS 83613112
END DESCRIPTION:
XS GIS Cut Line= 2
       2306503.2      13349130.6      2305716.75     13350958.71
#Sta/Elev= 30
  4245.1  309.27  4269.9  306.01    4346  302.94    4520  299.87  4597.7  298.29
  4778.8   297.9  4849.4  296.31  4854.9  297.12  4930.9  292.52  4954.5  292.87
  4959.9   291.8  5046.6  291.77  5054.1  292.79  5087.1  291.69  5089.9  291.19
  5093.1  291.69  5166.3  292.73  5177.2   293.5    5199  298.36  5220.8  297.16
  5439.8  296.97  5748.3  299.09  5933.7  301.86  6015.1  303.05  6039.8  303.67
  6080.8  305.86  6102.5  308.61  6145.9  307.81  6178.8  310.23  6235.2  312.21
#Mann= 10 ,-1 , 0
  4245.1     .16       0    4520      .1       0  5087.1     .03       0
  5093.1     .05       0    5199      .1       0  5748.3      .1       0
  5933.7     .05       0  6015.1     .08       0  6039.8      .1       0
  6145.9     .05       0
Bank Sta=4854.9,5199
XS Rating Curve= 0 ,0
Exp/Cntr=0.3,0.1

Type RM Length L Ch R = 1 ,88554.42,53,53,53
BEGIN DESCRIPTION:
Mapping XS 17785876
END DESCRIPTION:
XS GIS Cut Line= 2
       2306427.7     13349057.64      2305683.23     13350952.65
#Sta/Elev= 30
    4000308.7026 4019.93306.0061 4069.76303.8069 4179.38301.5429 4338.84300.8797
 4528.19297.2717 4617.88296.8376 4647.78295.7682 4657.74296.0284 4677.67298.8241
 4687.64299.3527 4756.29298.8706 4785.52297.9694 4795.26298.5122 4824.49297.9079
 4843.98298.9878 4853.72299.4779 4882.95298.6813 4902.44299.3211 4931.67298.8064
  4960.9299.9588 5000.08297.3104 5169.25297.0573 5457.84298.3265 5656.87300.2677
 5816.09303.9269 5865.84306.9724 5875.79308.3831  5915.6307.7115 6015.11 312.739
#Mann= 3 , 0 , 0
    4000      .1       0 4756.29     .08       0 4843.98      .1       0
#XS Ineff= 2 , 0
       0 4688.92  299.36 4953.12       0  300.01
Permanent Ineff=
       T       T
Bank Sta=4756.29,4843.98
XS Rating Curve= 0 ,0
Exp/Cntr=0.3,0.1

Type RM Length L Ch R = 1 ,88501   ,84,84,84
BEGIN DESCRIPTION:
Mapping XS 353b8b76
END DESCRIPTION:
XS GIS Cut Line= 2
       2306440.7     13348893.62       2305669.9     13350958.65
#Sta/Elev= 30
    4000 314.097 4059.83312.2165 4069.81311.3228 4089.75 310.975  4109.7 309.885
 4139.61309.5411 4169.53308.1853 4388.92303.0747 4498.62300.9596 4548.48300.6347
 4747.93296.8116 4797.79 296.349 4847.65295.0675 4887.54295.3509 4947.37294.7542
 4987.26294.1827 5017.18 294.801  5047.1294.5324 5086.99295.1667 5156.79297.1245
 5416.08297.4864 5535.74298.5126 5595.29 298.446  5852.1301.0866 6000.26304.1491
 6020.02305.7803 6059.52307.8312 6089.16307.4585 6128.67 309.782 6207.68313.1572
#Mann= 3 , 0 , 0
    4000     .16       0 4947.37     .08       0 5017.18     .16       0
Bank Sta=4947.37,5017.18
XS Rating Curve= 0 ,0
Exp/Cntr=0.3,0.1

Type RM Length L Ch R = 1 ,88417   ,286,286,286
BEGIN DESCRIPTION:
UNT003 IN NURI 135.0
END DESCRIPTION:
XS GIS Cut Line= 2
      2306384.28     13348856.72      2305579.95     13350902.69
#Sta/Elev= 30
  3996.1  314.34  3998.2  314.34    4001  316.82  4033.4  315.43  4169.5  310.68
  4379.2  304.73  4385.4  304.33  4675.6  298.24  4798.5  296.43  4849.1  295.65
  4965.8  294.46  5003.3   293.5    5006     293  5009.3   293.5  5010.8  293.56
  5090.3  295.73    5113  295.69  5135.2  296.54    5256  295.89  5312.4  295.17
  5328.6  296.42  5427.5  296.45  5546.2  297.26  5742.1  299.95  5836.3  301.75
  6016.3  304.66  6056.6  306.84  6126.5  309.72  6161.4  311.71  6194.5  312.86
#Mann= 20 ,-1 , 0
  3996.1      .1       0  4033.4     .05       0  4169.5     .08       0
  4379.2      .1       0  4385.4     .08       0  4675.6      .1       0
  4798.5     .08       0  4965.8     .12       0  5003.3     .07       0
  5009.3     .12       0  5010.8      .1       0    5113     .08       0
    5256      .1       0  5427.5     .08       0  5546.2      .1       0
  5742.1     .08       0  5836.3      .1       0  6056.6     .08       0
  6126.5     .05       0  6161.4      .1       0
Bank Sta=4849.1,5090.3
XS Rating Curve= 0 ,0
Exp/Cntr=0.3,0.1

Type RM Length L Ch R = 1 ,88131   ,606,606,606
BEGIN DESCRIPTION:
UNT003 IN NURI 134.0
END DESCRIPTION:
XS GIS Cut Line= 4
      2306136.12     13348871.16      2305835.33     13349470.13
      2305500.55     13350390.77      2305132.25     13350625.85
#Sta/Elev= 30
  4058.1  318.81  4105.2  316.92  4165.2   315.2  4433.7   303.6  4575.9  298.97
  4693.2  296.41  4855.5  296.06  4894.5  295.06    4927  294.32  4936.6  292.64
  4948.3  292.07  4967.2  292.85  5000.1  291.49  5002.8  290.99  5006.1  291.49
  5012.2  293.11  5028.4  294.22  5033.7  293.45  5084.2  292.64  5130.4  293.23
  5201.3     294  5237.2  293.38  5373.9  296.27  5565.5  304.16  5700.1  307.49
  5856.5  313.35  5922.2  315.49  5996.1  317.83  6025.8  320.22  6144.9  324.33
#Mann= 8 ,-1 , 0
  4058.1     .05       0  4105.2      .1       0  4894.5     .12       0
  5000.1     .07       0  5006.1     .12       0  5130.4      .1       0
  5856.5     .05       0  5922.2      .1       0
Bank Sta=4927,5028.4
XS Rating Curve= 0 ,0
Exp/Cntr=0.3,0.1

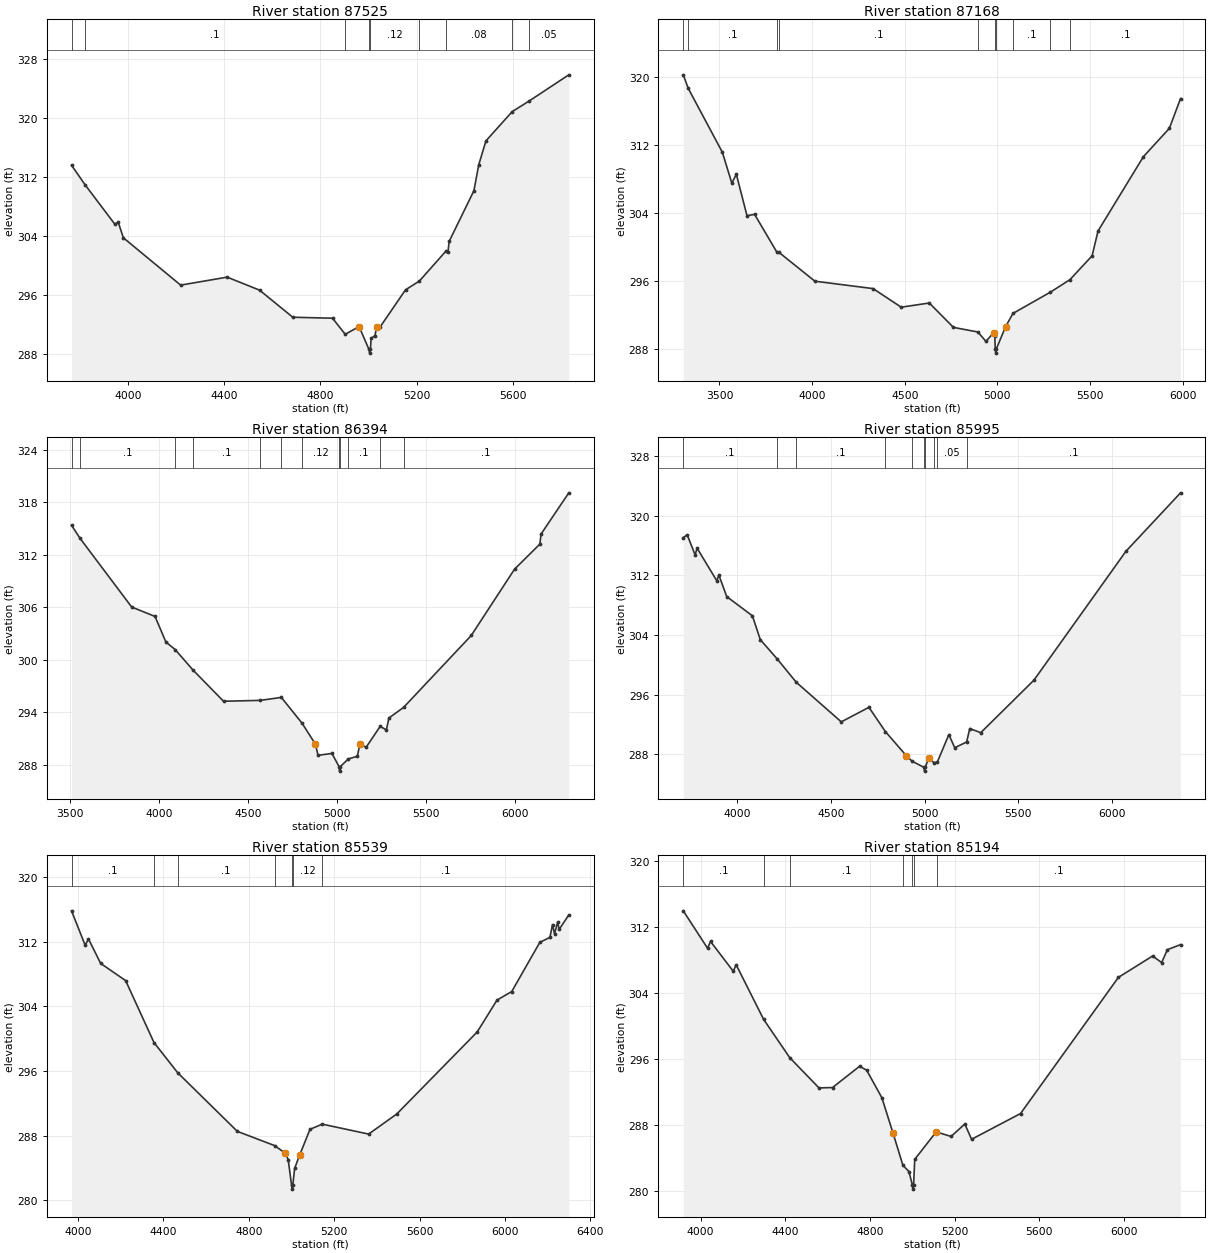
Type RM Length L Ch R = 1 ,87525   ,357,357,357
BEGIN DESCRIPTION:
UNT003 IN NURI 132.0
END DESCRIPTION:
XS GIS Cut Line= 4
      2305906.62     13348836.08      2305504.14     13349100.56
      2304998.15     13350066.54      2305009.65     13350561.03
#Sta/Elev= 30
  3766.1  313.59  3822.8  310.92  3945.4  305.63  3960.5  305.84  3981.5  303.76
  4219.6  297.35  4412.9  298.43  4547.6  296.67  4685.6     293  4850.8  292.87
  4903.6  290.69  4961.2  291.74  5002.3  288.64    5005  288.14  5008.3  288.64
  5011.2  290.14  5027.4  290.52  5033.7  291.69  5049.4  291.72  5154.1  296.71
    5212  297.91    5323  301.99  5330.6  301.82  5335.5  303.27  5438.5  310.14
  5458.5  313.65  5488.5  316.89  5597.3  320.84  5667.3  322.27  5832.8  325.83
#Mann= 9 ,-1 , 0
  3766.1     .05       0  3822.8      .1       0  4903.6     .12       0
  5002.3     .07       0  5008.3     .12       0    5212      .1       0
    5323     .08       0  5597.3      .1       0  5667.3     .05       0
Bank Sta=4961.2,5033.7
XS Rating Curve= 0 ,0
Exp/Cntr=0.3,0.1

Type RM Length L Ch R = 1 ,87168   ,774,774,774
BEGIN DESCRIPTION:
UNT003 IN NURI 131.0
END DESCRIPTION:
XS GIS Cut Line= 4
      2305883.66     13348491.07      2305251.15     13348629.08
      2304641.66     13350089.54      2304802.07     13350513.47
#Sta/Elev= 30
  3304.9  320.22  3331.9  318.62  3515.7  311.14  3566.9  307.51  3591.2  308.56
  3648.7  303.69  3689.7  303.85  3808.4  299.47  3820.2  299.41  4014.9  296.01
  4329.1  295.14  4480.8  292.96  4632.5  293.45  4762.6  290.59  4894.4  290.05
  4938.1  288.95  4979.3  289.96  4985.8  289.61  4988.2  288.07  4990.9  287.57
  4994.2  288.07  5044.3  290.69  5083.9  292.23  5285.6  294.72  5391.3  296.19
  5510.9  298.99  5542.9   301.9  5787.7  310.62  5927.6  313.94  5988.1  317.44
#Mann= 10 ,-1 , 0
  3304.9     .05       0  3331.9      .1       0  3808.4     .05       0
  3820.2      .1       0  4894.4     .12       0  4988.2     .07       0
  4994.2     .12       0  5083.9      .1       0  5285.6     .08       0
  5391.3      .1       0
Bank Sta=4979.3,5044.3
XS Rating Curve= 0 ,0
Exp/Cntr=0.3,0.1

Type RM Length L Ch R = 1 ,86394   ,399,399,399
BEGIN DESCRIPTION:
UNT003 IN NURI 130.0
END DESCRIPTION:
XS GIS Cut Line= 3
      2304747.79     13347702.65      2304569.84       13348983.
      2303623.67     13350141.84
#Sta/Elev= 30
  3511.2  315.36  3558.8  313.87  3848.6  306.01  3979.3  304.94  4040.4  302.01
  4092.3  301.15  4191.5  298.83  4363.5  295.24  4570.6  295.34  4687.7  295.68
    4804  292.73  4879.1  290.33  4893.5  289.06  4971.7  289.27  5011.8  287.75
  5014.6  287.25  5017.8  287.75  5063.1  288.64  5113.9  288.95  5128.2  290.33
  5163.4  289.98  5242.1  292.37  5276.8  291.96  5291.2  293.33  5373.1  294.53
  5752.9  302.76  5995.5  310.34  6137.7  313.21  6144.1  314.35  6299.9  319.07
#Mann= 12 ,-1 , 0
  3511.2     .05       0  3558.8      .1       0  4092.3     .05       0
  4191.5      .1       0  4570.6     .05       0  4687.7      .1       0
    4804     .12       0  5011.8     .07       0  5017.8     .12       0
  5063.1      .1       0  5242.1     .05       0  5373.1      .1       0
Bank Sta=4879.1,5128.2
XS Rating Curve= 0 ,0
Exp/Cntr=0.3,0.1

Type RM Length L Ch R = 1 ,85995   ,456,456,456
BEGIN DESCRIPTION:
UNT003 IN NURI 129.0
END DESCRIPTION:
XS GIS Cut Line= 3
      2304537.73     13347696.84      2304137.72     13348896.85
      2303437.71     13350096.88
#Sta/Elev= 30
  3711.4  317.06  3732.5  317.42  3774.7  314.73  3785.2  315.63  3890.6  311.25
  3901.2  312.04  3943.3  309.14  4080.3  306.56  4122.5  303.36  4211.1  300.82
  4314.2  297.65  4554.7  292.33  4702.3  294.28  4790.4  291.02  4902.5  287.77
  4932.3  287.06  4996.5  286.22  4999.2  285.72  5002.5  286.22  5021.4  287.48
  5050.1  286.83  5068.1  286.98  5128.9  290.62  5160.3  288.86  5223.8  289.63
  5240.5  291.43  5299.2  290.88  5582.9  297.92  6074.1  315.22  6365.6  323.06
#Mann= 10 ,-1 , 0
  3711.4      .1       0  4211.1     .05       0  4314.2      .1       0
  4790.4     .05       0  4932.3     .12       0  4996.5     .07       0
  5002.5     .12       0  5050.1      .1       0  5068.1     .05       0
  5223.8      .1       0
Bank Sta=4902.5,5021.4
XS Rating Curve= 0 ,0
Exp/Cntr=0.3,0.1

Type RM Length L Ch R = 1 ,85539   ,345,345,345
BEGIN DESCRIPTION:
UNT003 IN NURI 128.0
END DESCRIPTION:
XS GIS Cut Line= 3
      2304305.09     13347727.78      2303864.11     13348512.52
      2303332.85     13349838.93
#Sta/Elev= 30
  3969.5   315.8  4033.5  311.53  4048.7  312.33  4106.1  309.29  4222.9  307.17
  4355.6  299.51    4467  295.76  4746.4  288.51  4920.4  286.76  4971.3   285.8
  4984.2  285.03    5000  281.87  5002.8  281.37    5006  281.87  5014.4  283.94
    5038  285.59  5086.5  288.77  5143.8  289.41    5361  288.18  5492.9  290.67
  5869.6  300.82  5962.3  304.76  6031.1  305.81    6163  311.91  6210.1  312.51
  6222.2   314.1  6231.6  312.97  6246.4  314.42  6253.2   313.5  6298.5  315.29
#Mann= 7 ,-1 , 0
  3969.5      .1       0  4355.6     .05       0    4467      .1       0
  4920.4     .12       0    5000     .07       0    5006     .12       0
  5143.8      .1       0
Bank Sta=4971.3,5038
XS Rating Curve= 0 ,0
Exp/Cntr=0.3,0.1

Type RM Length L Ch R = 1 ,85194   ,526,526,526
BEGIN DESCRIPTION:
UNT003 IN NURI 127.0
END DESCRIPTION:
XS GIS Cut Line= 3
      2304103.69     13347661.82      2303562.03      13348338.9
      2303114.16     13349751.93
#Sta/Elev= 30
  3917.9  313.98  4032.4  309.45  4046.8  310.26    4154  306.65  4167.7  307.44
  4297.6  300.81  4421.1  296.16    4559   292.5    4623  292.54  4751.1  295.13
  4784.4  294.64  4856.3   291.3  4908.7  287.03  4955.5  283.12  4984.3  282.34
  5000.1  280.72  5002.9  280.22  5006.1  280.72  5011.4  283.83  5113.5  287.19
  5116.9  287.13  5183.3  286.61  5247.9  288.12  5280.1  286.27  5511.4  289.39
  5973.8  305.91  6135.3   308.5    6178   307.7  6205.1  309.27  6267.3  309.88
#Mann= 7 ,-1 , 0
  3917.9      .1       0  4297.6     .05       0  4421.1      .1       0
  4955.5     .12       0  5000.1     .07       0  5006.1     .12       0
  5116.9      .1       0
Bank Sta=4908.7,5113.5
XS Rating Curve= 0 ,0
Exp/Cntr=0.3,0.1

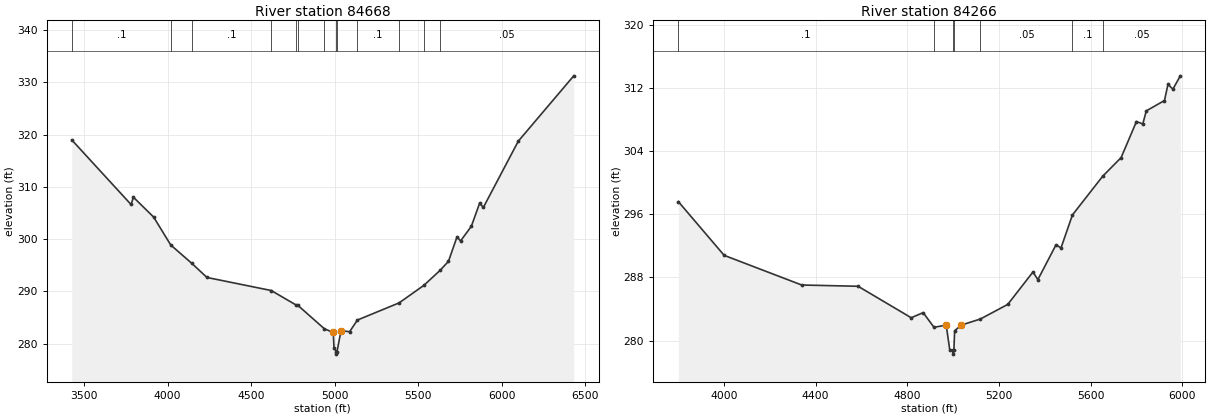
Type RM Length L Ch R = 1 ,84668   ,402,402,402
BEGIN DESCRIPTION:
UNT003 IN NURI 126.0
END DESCRIPTION:
XS GIS Cut Line= 3
      2303987.72     13347396.86      2302987.72     13348596.85
       2302187.7     13349796.88
#Sta/Elev= 30
  3426.7  318.98  3781.4  306.62  3795.7  308.01  3916.8  304.21  4019.1  298.87
  4144.5  295.38  4235.7  292.66  4620.5  290.16  4771.5  287.35  4779.6  287.33
  4938.6  282.84  4991.7  282.13  4996.3  279.21  5008.3  278.49    5011  277.99
  5014.3  278.49  5038.3   282.5  5089.4  282.27  5136.2  284.51  5385.4  287.79
  5533.3  291.13  5630.9  294.01  5681.3  295.75  5732.4  300.43  5753.4  299.64
    5818  302.44  5867.6  306.85  5890.1  306.06    6099  318.73    6431  331.24
#Mann= 13 ,-1 , 0
  3426.7      .1       0  4019.1     .05       0  4144.5      .1       0
  4620.5     .05       0  4771.5      .1       0  4779.6     .05       0
  4938.6     .12       0  5008.3     .07       0  5014.3     .12       0
  5136.2      .1       0  5385.4     .05       0  5533.3      .1       0
  5630.9     .05       0
Bank Sta=4991.7,5038.3
XS Rating Curve= 0 ,0
Exp/Cntr=0.3,0.1

Type RM Length L Ch R = 1 ,84266   ,487,487,487
BEGIN DESCRIPTION:
UNT003 IN NURI 125.0
END DESCRIPTION:
XS GIS Cut Line= 3
      2303399.69     13347709.11      2302882.21     13348077.09
      2302065.72     13349399.57
#Sta/Elev= 30
  3801.8  297.61  4001.5   290.8  4339.7  287.04  4585.7  286.88  4817.5  282.89
  4869.5  283.54  4916.8  281.68    4970  281.96  4985.4  278.84  4997.6  278.78
  5000.4  278.28  5003.6  278.78  5006.7  281.24  5035.9  281.96    5119  282.73
  5238.4  284.58  5348.4  288.69  5369.7  287.72  5448.9  292.13  5470.7  291.74
  5520.5  295.92  5652.9  300.84  5732.7  303.18  5799.8  307.76  5827.3  307.45
  5842.7  309.11  5921.9  310.42  5937.3  312.49  5958.5  311.85    5991  313.55
#Mann= 7 ,-1 , 0
  3801.8      .1       0  4916.8     .12       0  4997.6     .07       0
  5003.6     .12       0    5119     .05       0  5520.5      .1       0
  5652.9     .05       0
Bank Sta=4970,5035.9
XS Rating Curve= 0 ,0
Exp/Cntr=0.3,0.1