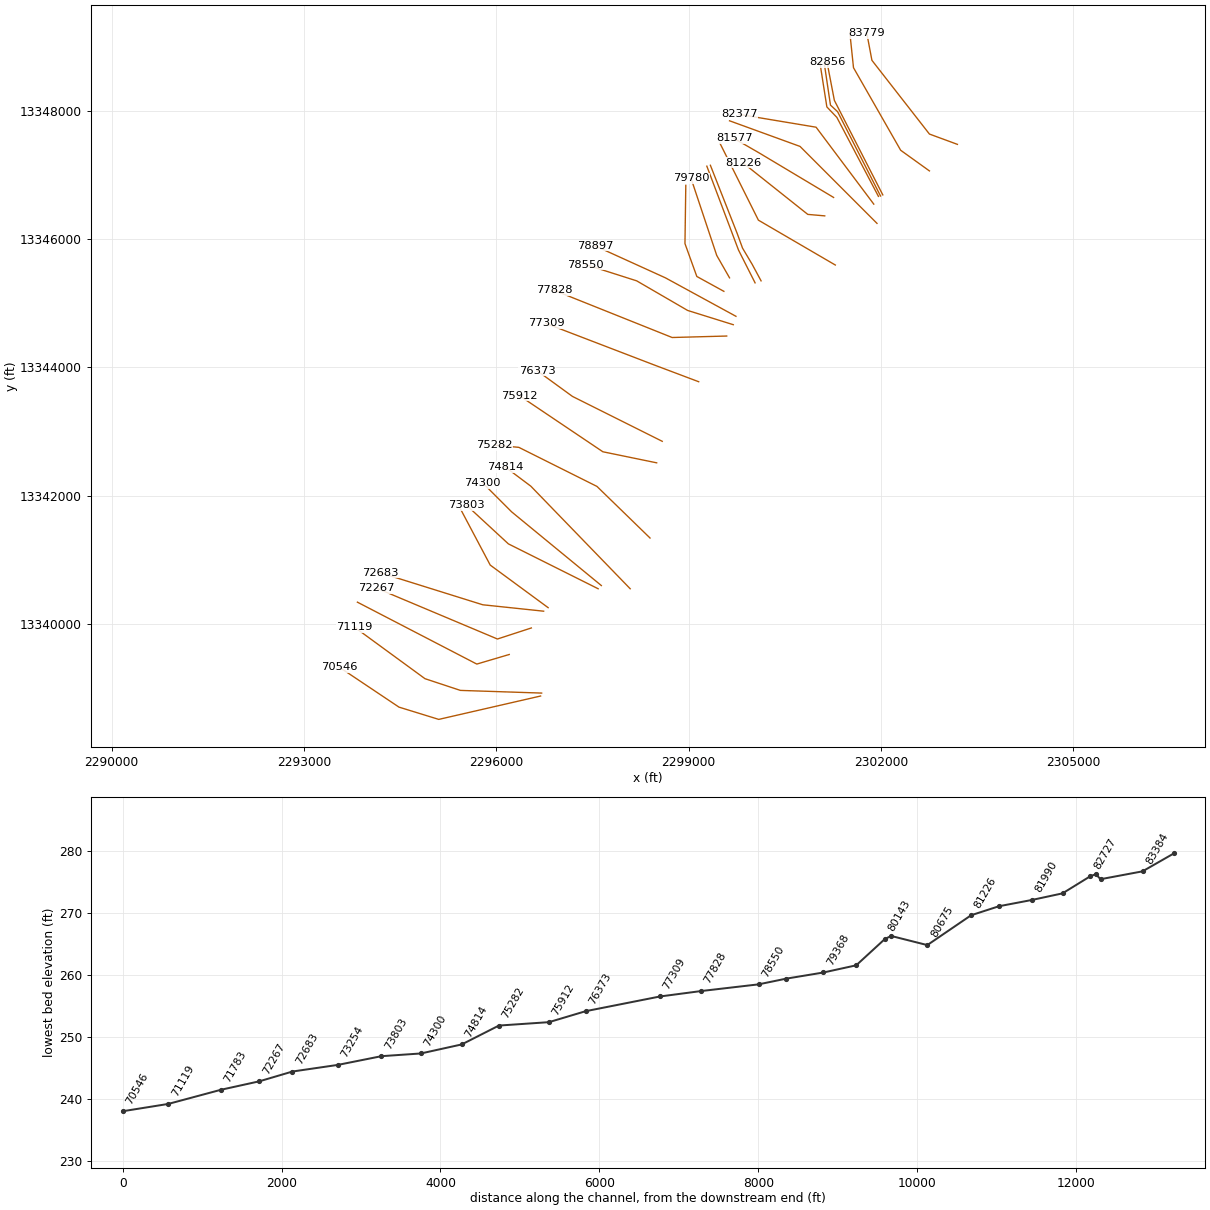
HEC-RAS study UNT003 IN NURI.prj: UNT003 IN NURI Base Level Engineering

--- UNT003 IN NURI.g01 (geometry) --- (continued)

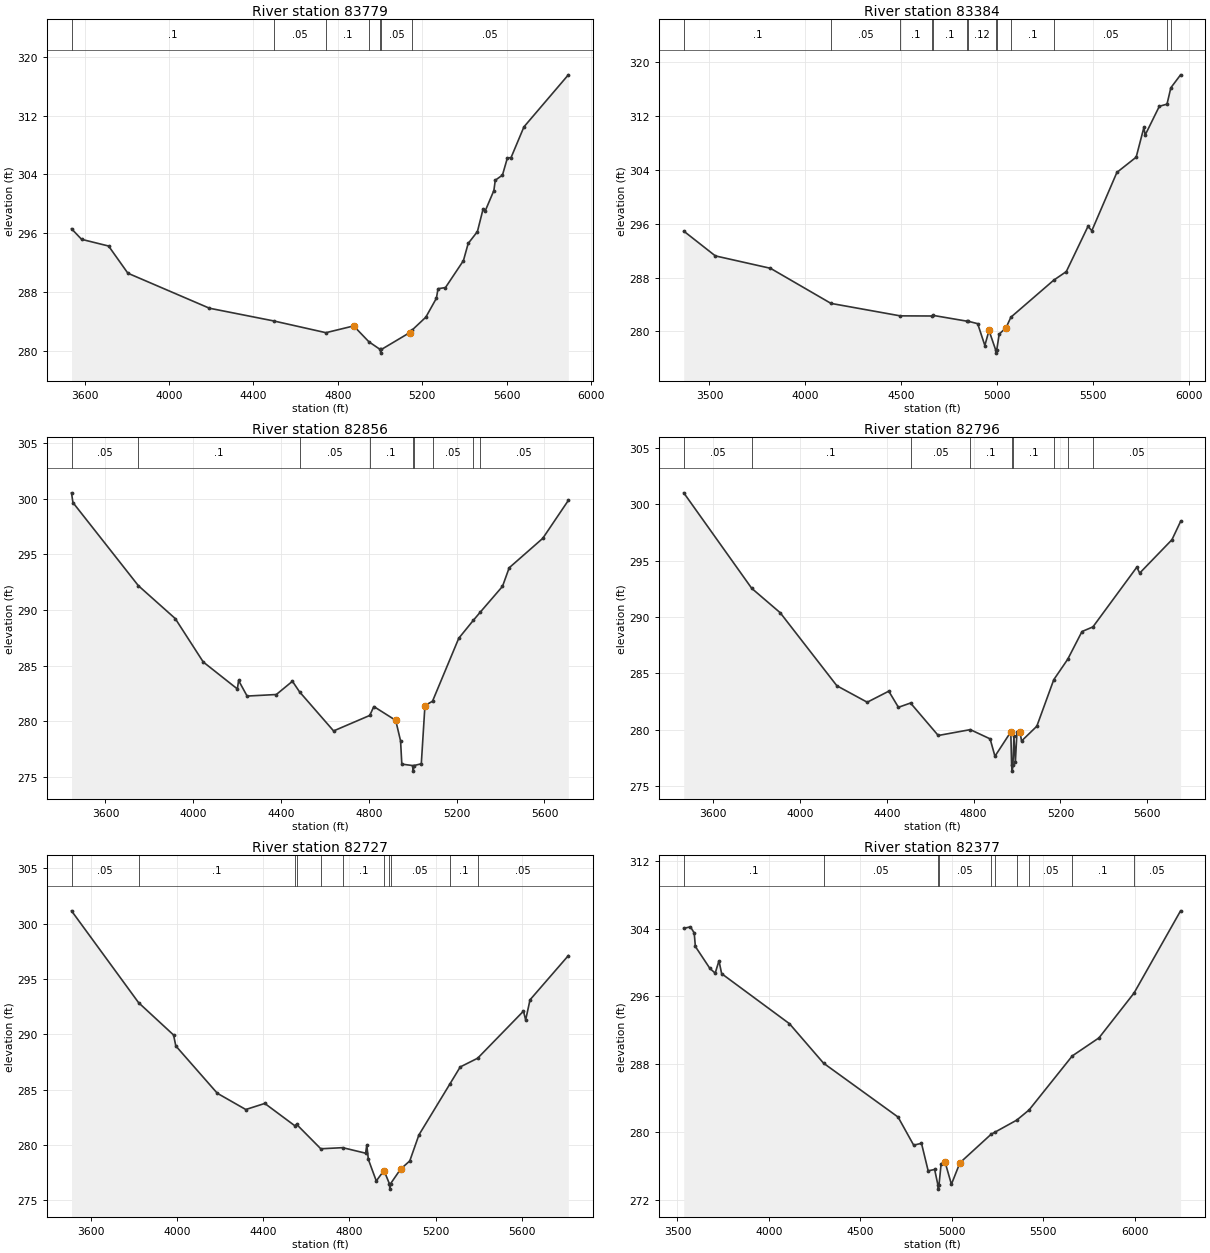
Type RM Length L Ch R = 1 ,83779   ,395,395,395
BEGIN DESCRIPTION:
UNT003 IN NURI 124.0
END DESCRIPTION:
XS GIS Cut Line= 4
      2303192.67     13347479.12      2302755.71      13347640.1
      2301858.74     13348790.07       2301778.6     13349213.67
#Sta/Elev= 30
  3537.6  296.61  3585.5  295.17  3713.4  294.26  3804.9  290.56  4191.4   285.8
    4496  284.07  4743.6  282.47  4875.2  283.39  4947.5  281.23  5000.7  280.19
  5003.4  279.69  5006.7  280.19  5140.2  282.47  5151.2   282.8  5217.2  284.58
  5267.4  287.16    5275  288.45  5310.3  288.61  5395.4  292.27    5418  294.61
  5461.7  296.22  5488.9  299.32  5499.1  299.06  5539.8  301.81  5546.4  303.21
  5580.5  303.91  5603.8  306.24  5621.2  306.29  5682.3  310.47  5892.8  317.55
#Mann= 7 ,-1 , 0
  3537.6      .1       0    4496     .05       0  4743.6      .1       0
  4947.5     .05       0  5000.7     .03       0  5006.7     .05       0
  5151.2     .05       0
Bank Sta=4875.2,5140.2
XS Rating Curve= 0 ,0
Exp/Cntr=0.3,0.1

Type RM Length L Ch R = 1 ,83384   ,528,528,528
BEGIN DESCRIPTION:
UNT003 IN NURI 123.0
END DESCRIPTION:
XS GIS Cut Line= 4
      2302755.71     13347065.12      2302307.23     13347387.11
      2301571.25     13348675.08      2301513.75     13349227.07
#Sta/Elev= 30
    3366   294.9  3530.8  291.22  3818.1  289.38  4133.7  284.17  4494.7  282.32
  4661.1   282.3  4666.1  282.39  4840.8  281.54  4848.1  281.53  4898.6  281.16
    4936  277.92  4957.6  280.15  4992.1  277.29  4994.8  276.79  4998.1  277.29
  5010.9  279.61  5046.5  280.56  5071.7  282.12  5295.3  287.62  5360.7  288.89
  5473.7   295.6  5493.8  294.96  5624.5  303.61    5725  305.87  5765.3  310.29
  5771.8  309.15  5845.7  313.42  5885.7  313.74  5905.8  316.17  5956.5  318.09
#Mann= 13 ,-1 , 0
    3366      .1       0  4133.7     .05       0  4494.7      .1       0
  4661.1     .05       0  4666.1      .1       0  4840.8     .05       0
  4848.1     .12       0  4992.1     .07       0  4998.1     .12       0
  5071.7      .1       0  5295.3     .05       0  5885.7      .1       0
  5905.8     .05       0
Bank Sta=4957.6,5046.5
XS Rating Curve= 0 ,0
Exp/Cntr=0.3,0.1

Type RM Length L Ch R = 1 ,82856   ,60,60,60
BEGIN DESCRIPTION:
Mapping XS d5351c67
END DESCRIPTION:
XS GIS Cut Line= 3
      2302028.17     13346691.11      2301272.95     13348165.09
      2301158.36     13348761.49
#Sta/Elev= 30
  3445.4  300.51  3451.8  299.64  3750.1  292.17    3918  289.22  4045.6  285.32
    4201   282.9  4206.6  283.66  4245.4  282.26  4378.6   282.4  4451.9  283.59
  4484.3  282.64  4639.4  279.13  4804.1  280.52  4822.7  281.32  4922.4  280.08
  4944.6  278.23  4950.2  276.15  4999.5  276.02  5002.2  275.52  5005.5  276.02
    5039  276.18  5055.6   281.4  5090.1   281.8  5209.6  287.45  5276.8  289.08
    5307  289.78  5408.9  292.11  5439.4  293.78  5592.2  296.42  5708.9  299.83
#Mann= 9 ,-1 , 0
  3445.4     .05       0  3750.1      .1       0  4484.3     .05       0
  4804.1      .1       0  4999.5     .07       0  5005.5      .1       0
  5090.1     .05       0  5276.8      .1       0    5307     .05       0
Bank Sta=4922.4,5055.6
XS Rating Curve= 0 ,0
Exp/Cntr=0.3,0.1

Type RM Length L Ch R = 1 ,82796   ,69,69,69
BEGIN DESCRIPTION:
UNT003 IN NURI 122.0
END DESCRIPTION:
XS GIS Cut Line= 4
      2301993.07     13346673.28       2301323.3     13347988.88
      2301212.18     13348091.31      2301114.61     13348746.17
#Sta/Elev= 30
  3464.3  301.01  3777.6  292.54  3908.7  290.38    4170   283.9  4309.9  282.44
  4409.1  283.42  4453.6  281.99  4509.4  282.37  4637.1  279.49  4784.8  280.01
  4876.2  279.19  4898.4  277.65  4971.5  279.81  4975.3  276.83  4978.1  276.33
  4981.3  276.83  4985.7  279.42  4992.5  277.11  4999.9  279.81  5014.1  279.79
  5020.9     279  5091.3  280.31  5169.5  284.44  5233.7  286.25  5299.5  288.71
  5349.9  289.12  5552.3  294.42  5565.3  293.89    5714  296.85  5753.8  298.47
#Mann= 9 ,-1 , 0
  3464.3     .05       0  3777.6      .1       0  4509.4     .05       0
  4784.8      .1       0  4975.3     .07       0  4981.3      .1       0
  5169.5     .05       0  5233.7      .1       0  5349.9     .05       0
Bank Sta=4971.5,5014.1
XS Rating Curve= 0 ,0
Exp/Cntr=0.3,0.1

Type RM Length L Ch R = 1 ,82727   ,350,350,350
BEGIN DESCRIPTION:
Mapping XS d4d9f581
END DESCRIPTION:
XS GIS Cut Line= 4
      2301960.43     13346667.73      2301312.01     13347899.47
      2301155.76     13348063.53      2301049.09     13348742.55
#Sta/Elev= 30
  3510.1  301.17  3821.6  292.86  3983.8  289.94  3994.2  288.95  4186.8  284.67
    4319   283.2  4407.2  283.75    4546  281.74  4554.7  281.86    4667  279.65
  4768.9  279.75    4875  279.25  4880.6  279.99  4887.8  278.69  4924.6  276.74
  4959.8  277.67  4961.8  277.62  4985.2   276.5  4987.9     276  4991.2   276.5
  5037.5  277.81    5080  278.55  5122.4   280.9  5265.9   285.5  5314.2  287.05
  5395.1  287.84  5607.8   292.1  5617.9   291.3  5638.1  293.12    5816  297.12
#Mann= 11 ,-1 , 0
  3510.1     .05       0  3821.6      .1       0    4546     .05       0
  4554.7      .1       0    4667     .05       0  4768.9      .1       0
  4961.8     .05       0  4985.2     .03       0  4991.2     .05       0
  5265.9      .1       0  5395.1     .05       0
Bank Sta=4959.8,5037.5
XS Rating Curve= 0 ,0
Exp/Cntr=0.3,0.1

Type RM Length L Ch R = 1 ,82377   ,387,387,387
BEGIN DESCRIPTION:
UNT003 IN NURI 121.0
END DESCRIPTION:
XS GIS Cut Line= 3
      2301887.74     13346546.82      2300987.72     13347746.85
      2299787.71     13347946.86
#Sta/Elev= 30
  3534.4  304.02  3570.9   304.2  3591.7  303.48    3598  301.88  3677.1   299.3
  3706.3  298.73  3727.1  300.19  3741.7  298.67  4112.6  292.76    4299   288.1
  4706.3  281.74  4791.7  278.42  4834.4  278.64  4870.9  275.39  4906.3  275.55
  4924.1  273.73  4926.9  273.23  4930.1  273.73  4941.7  276.19  4962.6  276.48
    4998   273.8  5044.6  276.34  5214.7   279.7  5238.1  279.98  5355.3  281.38
  5422.7  282.58  5658.9  288.96  5804.9  291.09  5996.5  296.38    6251  306.09
#Mann= 10 ,-1 , 0
  3534.4      .1       0    4299     .05       0  4924.1     .03       0
  4930.1     .05       0  5214.7      .1       0  5238.1     .05       0
  5355.3      .1       0  5422.7     .05       0  5658.9      .1       0
  5996.5     .05       0
Bank Sta=4962.6,5044.6
XS Rating Curve= 0 ,0
Exp/Cntr=0.3,0.1

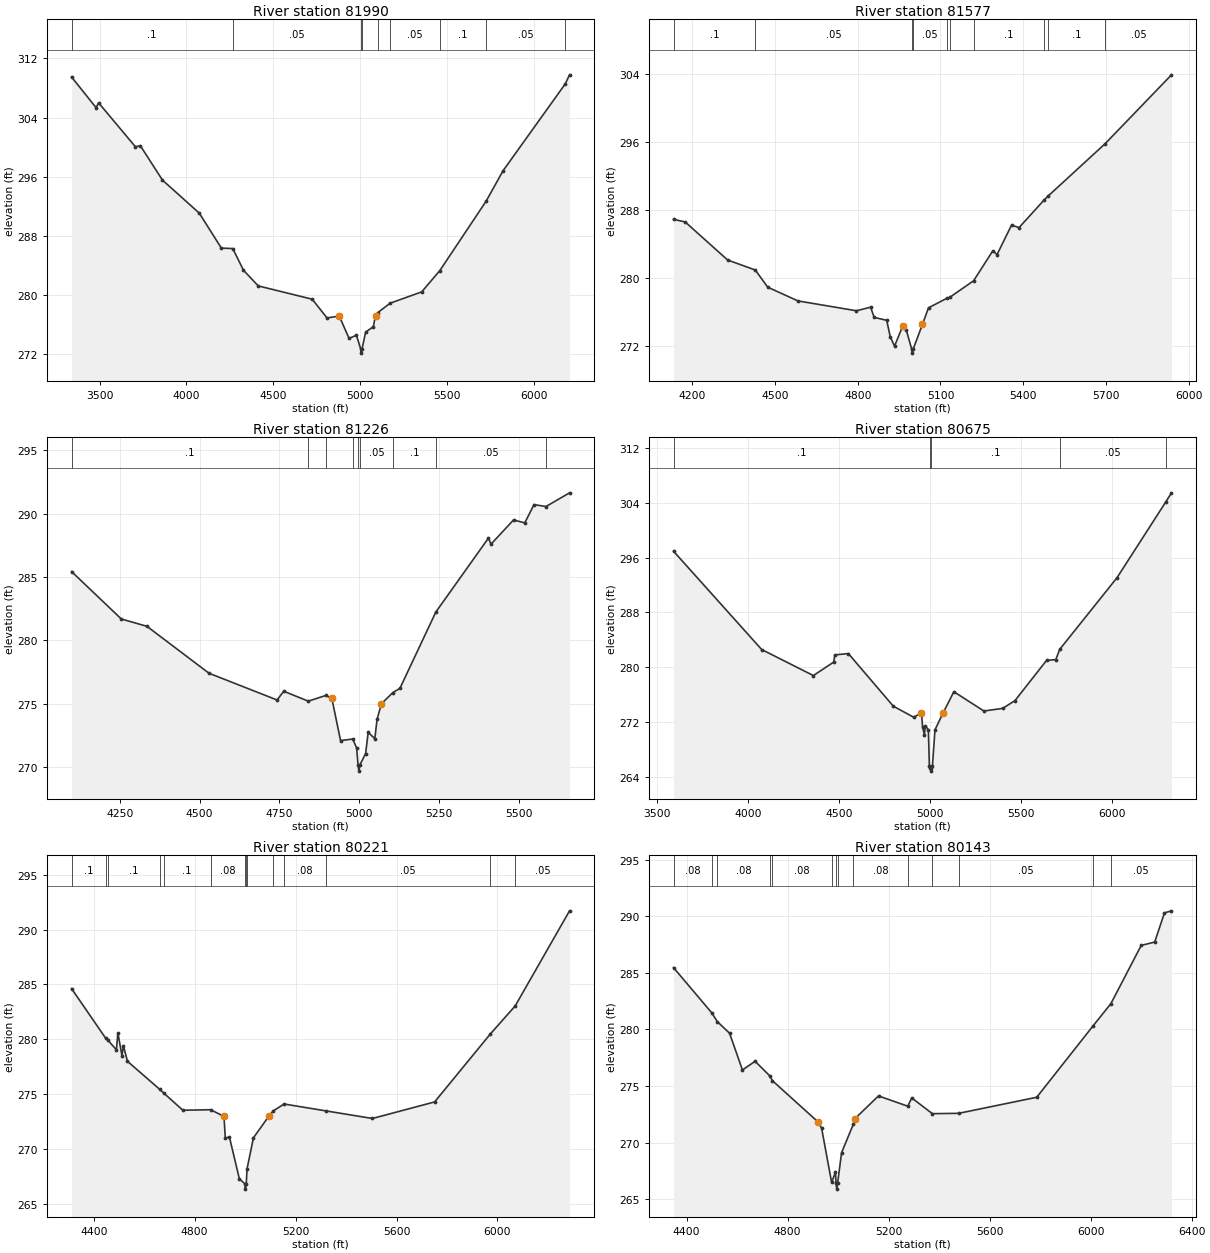
Type RM Length L Ch R = 1 ,81990   ,413,413,413
BEGIN DESCRIPTION:
UNT003 IN NURI 120.0
END DESCRIPTION:
XS GIS Cut Line= 3
      2301937.75     13346246.83      2300737.72     13347446.85
      2299637.69     13347846.87
#Sta/Elev= 30
  3338.3   309.5  3479.8  305.34  3493.9  306.01    3706  300.06  3734.3  300.21
  3861.6  295.56  4073.7  291.09    4201  286.36  4266.6   286.3  4328.3  283.37
  4413.1  281.25  4724.3  279.45  4809.1  276.92  4879.8  277.17  4936.4  274.15
  4978.8  274.58  5004.1  272.66  5006.9  272.16  5010.1  272.66  5031.9     275
    5076  275.74  5088.6  277.22  5100.2  277.61  5172.6  278.91  5354.6  280.44
  5459.3  283.33  5725.9  292.72  5822.8  296.81  6181.4  308.57  6205.9  309.79
#Mann= 9 ,-1 , 0
  3338.3      .1       0  4266.6     .05       0  5004.1     .03       0
  5010.1     .05       0  5100.2      .1       0  5172.6     .05       0
  5459.3      .1       0  5725.9     .05       0  6181.4      .1       0
Bank Sta=4879.8,5088.6
XS Rating Curve= 0 ,0
Exp/Cntr=0.3,0.1

Type RM Length L Ch R = 1 ,81577   ,351,351,351
BEGIN DESCRIPTION:
UNT003 IN NURI 119.0
END DESCRIPTION:
XS GIS Cut Line= 3
      2301260.77     13346651.12      2300087.79     13347352.61
      2299708.33     13347571.09
#Sta/Elev= 30
  4132.5  286.88  4174.9  286.57  4328.5   282.1  4428.9  280.92    4474   278.9
  4583.4  277.29  4795.4  276.13  4846.8  276.55  4859.6  275.35  4905.1  275.01
  4917.9  273.07  4933.5  271.97  4963.3  274.36  4976.3  273.84  4995.3  271.65
    4998  271.15  5001.3  271.65  5034.6  274.53  5056.6  276.48    5124  277.61
  5133.2   277.7  5220.1  279.66  5289.6  283.18    5305  282.74  5357.5   286.2
  5384.7  285.91  5474.6  289.12  5490.1  289.62  5697.2  295.79  5937.1  303.87
#Mann= 10 ,-1 , 0
  4132.5      .1       0  4428.9     .05       0  4995.3     .03       0
  5001.3     .05       0    5124      .1       0  5133.2     .05       0
  5220.1      .1       0  5474.6     .05       0  5490.1      .1       0
  5697.2     .05       0
Bank Sta=4963.3,5034.6
XS Rating Curve= 0 ,0
Exp/Cntr=0.3,0.1

Type RM Length L Ch R = 1 ,81226   ,551,551,551
BEGIN DESCRIPTION:
UNT003 IN NURI 118.0
END DESCRIPTION:
XS GIS Cut Line= 3
      2301122.79     13346363.64      2300858.27     13346386.64
       2299846.3     13347191.61
#Sta/Elev= 30
  4099.3  285.43    4255  281.69  4335.3  281.11  4529.5  277.41  4742.6   275.3
  4763.4  275.99  4840.2  275.21  4895.5  275.66    4914  275.42  4941.2   272.1
  4979.3  272.22  4991.6  271.52  4995.9  270.19  4998.6  269.69  5001.9  270.19
  5019.7  271.08  5027.7  272.75  5048.5  272.25  5055.5  273.78  5069.3  275.01
  5104.6  275.88    5127  276.22  5239.5  282.24  5404.1  288.07  5412.1  287.59
  5482.6   289.5  5517.8  289.27  5546.7  290.71  5584.2  290.56  5657.9  291.64
#Mann= 9 ,-1 , 0
  4099.3      .1       0  4840.2     .05       0  4895.5      .1       0
  4979.3     .05       0  4995.9    .035       0  5001.9     .05       0
  5104.6      .1       0  5239.5     .05       0  5584.2      .1       0
Bank Sta=4914,5069.3
XS Rating Curve= 0 ,0
Exp/Cntr=0.3,0.1

Type RM Length L Ch R = 1 ,80675   ,454,454,454
BEGIN DESCRIPTION:
UNT003 IN NURI 117.0
END DESCRIPTION:
XS GIS Cut Line= 3
      2301287.72     13345596.85      2300087.72     13346296.85
      2299487.71     13347496.87
#Sta/Elev= 30
  3592.7  296.93    4076   282.6  4359.7   278.8  4471.3  280.77  4477.1  281.81
  4551.5  282.01    4798  274.34  4909.6  272.73  4952.6  273.34  4958.8  271.27
  4968.3  270.19  4974.1  271.47  4990.3   270.9  4995.9  265.62  5001.3  265.37
  5004.1  264.87  5007.3  265.37  5012.7  265.67  5026.7   270.9  5071.4  273.36
  5130.1  276.45    5295  273.63  5398.4  274.02  5465.5  275.16  5638.8  281.02
  5689.1  281.12  5710.3  282.61  6024.5  293.05  6291.7  304.09  6323.6  305.44
#Mann= 5 ,-1 , 0
  3592.7      .1       0  5001.3     .07       0  5007.3      .1       0
  5710.3     .05       0  6291.7      .1       0
Bank Sta=4952.6,5071.4
XS Rating Curve= 0 ,0
Exp/Cntr=0.3,0.1

Type RM Length L Ch R = 1 ,80221   ,78,78,78
BEGIN DESCRIPTION:
UNT003 IN NURI 116.0
END DESCRIPTION:
XS GIS Cut Line= 5
       2300129.7     13345350.03      2299989.09      13345610.4
      2299840.66     13345859.75      2299754.72     13346094.78
       2299338.6     13347153.28
#Sta/Elev= 30
  4312.1  284.62  4446.6  280.12  4455.9  279.92  4489.9  279.04  4495.6  280.59
  4511.8  278.52  4517.5  279.41  4533.7  277.99  4660.9  275.45  4678.3  275.08
  4753.3  273.53  4862.9  273.58  4916.2  272.97  4921.5  270.99  4937.7  271.09
  4977.3  267.27  4998.6  266.84  5001.3  266.34  5004.6  266.84  5007.6  268.19
    5033  271.02  5094.1  272.99  5111.5  273.47  5154.5   274.1  5320.9  273.47
  5504.6  272.78  5751.1  274.29  5971.8  280.48  6070.4  283.04  6285.8  291.71
#Mann= 14 ,-1 , 0
  4312.1      .1       0  4446.6     .08       0  4455.9      .1       0
  4660.9     .08       0  4678.3      .1       0  4862.9     .08       0
  4998.6     .07       0  5004.6     .08       0  5007.6     .05       0
  5111.5      .1       0  5154.5     .08       0  5320.9     .05       0
  5971.8      .1       0  6070.4     .05       0
Bank Sta=4916.2,5094.1
XS Rating Curve= 0 ,0
Exp/Cntr=0.3,0.1

Type RM Length L Ch R = 1 ,80143   ,363,363,363
BEGIN DESCRIPTION:
Mapping XS 053cf15c
END DESCRIPTION:
XS GIS Cut Line= 3
      2300035.99      13345318.7      2299778.16     13345829.15
      2299283.37     13347139.04
#Sta/Elev= 30
    4348  285.46  4498.8  281.48  4521.4  280.69    4570  279.66  4620.9  276.41
  4671.1  277.18  4730.2  275.87  4739.3  275.47  4919.9  271.83  4934.4  271.28
  4974.1  266.48  4989.4  267.38  4991.7  266.38  4994.5  265.88  4997.7  266.38
  5013.6   269.1    5060  271.61  5067.1  272.12  5159.8  274.12  5275.6  273.21
  5291.6  273.94  5373.1  272.55  5477.4  272.58  5786.4     274  6009.5  280.31
    6080  282.27  6200.2  287.42  6253.6  287.72  6292.3   290.3  6320.1  290.48
#Mann= 14 ,-1 , 0
    4348     .08       0  4498.8      .1       0  4521.4     .08       0
  4730.2      .1       0  4739.3     .08       0  4974.1     .05       0
  4991.7     .03       0  4997.7     .05       0    5060     .08       0
  5275.6     .05       0  5373.1     .08       0  5477.4     .05       0
  6009.5      .1       0    6080     .05       0
Bank Sta=4919.9,5067.1
XS Rating Curve= 0 ,0
Exp/Cntr=0.3,0.1

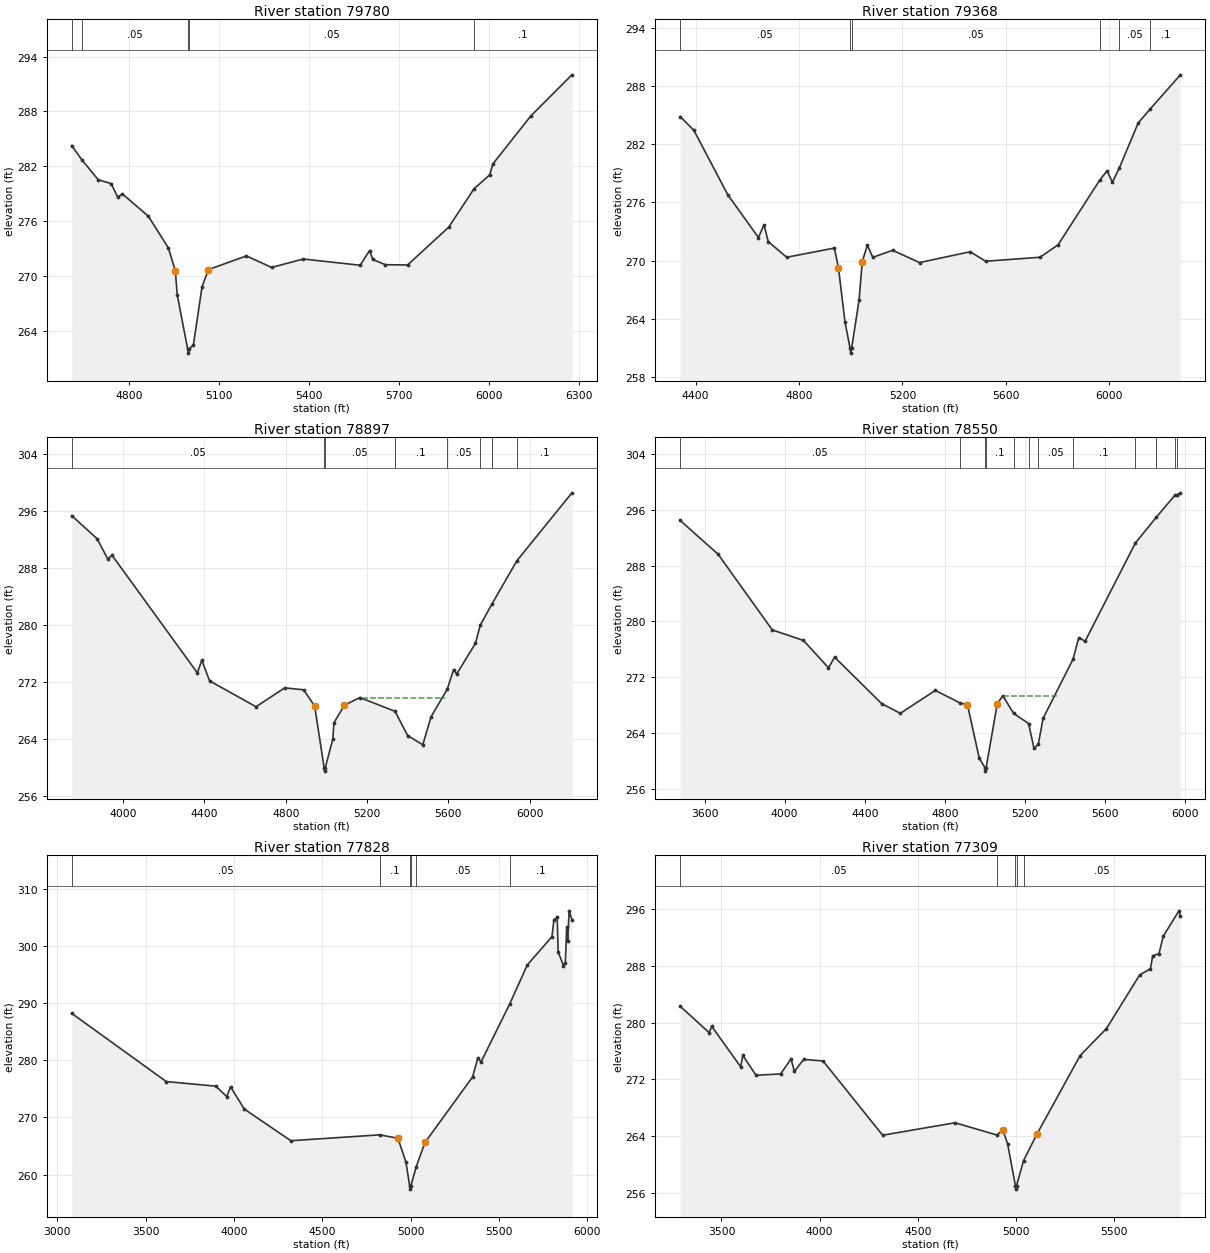
Type RM Length L Ch R = 1 ,79780   ,412,412,412
BEGIN DESCRIPTION:
UNT003 IN NURI 115.0
END DESCRIPTION:
XS GIS Cut Line= 3
      2299637.71     13345396.87      2299437.72     13345746.85
      2299037.72     13346946.85
#Sta/Elev= 30
  4607.8  284.27  4641.9  282.71  4696.3  280.54  4739.5  280.12  4761.1  278.64
  4776.9  278.99  4863.3  276.56  4930.3  273.09  4953.3   270.6  4959.8  267.97
  4994.2   262.1    4997   261.6  5000.2   262.1  5013.5  262.47  5042.5  268.85
  5063.6  270.72  5190.1  272.22  5274.4  270.96  5379.8  271.88  5569.6   271.2
  5601.2  272.81  5611.7  271.83  5653.9  271.26  5727.7  271.23  5864.7  275.35
  5949.2  279.54  6001.7  281.08  6012.3  282.27  6138.8  287.51  6275.8     292
#Mann= 5 ,-1 , 0
  4607.8      .1       0  4641.9     .05       0  4994.2    .035       0
  5000.2     .05       0  5949.2      .1       0
Bank Sta=4953.3,5063.6
XS Rating Curve= 0 ,0
Exp/Cntr=0.3,0.1

Type RM Length L Ch R = 1 ,79368   ,471,471,471
BEGIN DESCRIPTION:
UNT003 IN NURI 114.0
END DESCRIPTION:
XS GIS Cut Line= 4
      2299549.01     13345186.56      2299127.11     13345418.35
      2298942.22     13345931.37      2298955.24     13346840.18
#Sta/Elev= 30
    4340  284.87  4392.7  283.47    4524  276.81  4642.8  272.38  4664.6   273.7
  4680.7  271.96  4752.2  270.34  4936.7  271.29  4952.5  269.26  4977.9  263.64
  4997.5  260.94  5000.2  260.44  5003.5  260.94  5032.4  265.94  5044.6  269.88
  5064.3  271.59  5085.5  270.33    5162  271.06  5266.2  269.79  5462.2  270.91
  5522.2  269.93  5732.2  270.34  5802.2  271.62  5964.8  278.36  5992.3  279.27
  6012.3  278.09  6039.8  279.59  6112.3  284.21  6159.7  285.68  6275.6  289.18
#Mann= 6 ,-1 , 0
    4340     .05       0  4997.5     .03       0  5003.5     .05       0
  5964.8     .08       0  6039.8     .05       0  6159.7      .1       0
Bank Sta=4952.5,5044.6
XS Rating Curve= 0 ,0
Exp/Cntr=0.3,0.1

Type RM Length L Ch R = 1 ,78897   ,347,347,347
BEGIN DESCRIPTION:
UNT003 IN NURI 113.0
END DESCRIPTION:
XS GIS Cut Line= 3
      2299737.74     13344796.84      2298637.72     13345396.85
      2297537.74     13345896.85
#Sta/Elev= 30
  3746.9  295.32  3872.2  292.07    3924  289.24  3945.8  289.74  4365.4  273.23
  4387.2  275.02  4425.2  272.12  4653.9  268.48  4794.9  271.13  4888.4  270.86
  4942.5  268.56  4988.8  259.94  4991.6  259.44  4994.8  259.94  5031.8  263.96
  5037.3  266.24  5088.9   268.7  5164.7  269.77  5337.9  267.84  5399.8  264.43
  5474.5  263.14  5515.1  267.08  5594.8  270.94    5626  273.69  5641.4  273.09
  5733.7  277.39  5756.8  279.92  5813.5  282.85  5937.6  288.99  6208.2  298.52
#Mann= 8 ,-1 , 0
  3746.9     .05       0  4988.8     .03       0  4994.8     .05       0
  5337.9      .1       0  5594.8     .05       0  5756.8      .1       0
  5813.5     .05       0  5937.6      .1       0
#XS Ineff= 1 ,-1
 5174.88 5585.61  269.67
Permanent Ineff=
       F
Bank Sta=4942.5,5088.9
XS Rating Curve= 0 ,0
Exp/Cntr=0.3,0.1

Type RM Length L Ch R = 1 ,78550   ,722,722,722
BEGIN DESCRIPTION:
UNT003 IN NURI 112.0
END DESCRIPTION:
XS GIS Cut Line= 4
       2299696.1     13344665.94      2298984.28     13344888.17
      2298189.14     13345349.97      2297393.98     13345603.45
#Sta/Elev= 30
  3477.8  294.49  3667.7  289.63  3938.1  278.78  4094.2  277.27  4219.1  273.34
  4249.6  274.87  4484.7  268.21    4578  266.81  4752.9   270.1  4878.6  268.27
  4913.5  268.05  4972.3  260.39  5000.7  259.02  5003.5  258.52  5006.7  259.02
  5062.5  268.17  5089.8  269.35  5144.4   266.8  5218.8  265.35  5246.1  261.79
  5267.5  262.37  5291.4  266.09  5440.5  274.55  5469.9  277.67  5501.4  277.16
  5752.8  291.26  5856.8  294.93  5951.8  298.16    5959  298.12  5977.6  298.45
#Mann= 12 ,-1 , 0
  3477.8     .05       0  4878.6      .1       0  5000.7     .07       0
  5006.7      .1       0  5144.4     .05       0  5218.8      .1       0
  5267.5     .05       0  5440.5      .1       0  5752.8     .05       0
  5856.8      .1       0  5951.8     .05       0    5959      .1       0
#XS Ineff= 1 ,-1
 5089.96 5361.69  269.36
Permanent Ineff=
       F
Bank Sta=4913.5,5062.5
XS Rating Curve= 0 ,0
Exp/Cntr=0.3,0.1

Type RM Length L Ch R = 1 ,77828   ,519,519,519
BEGIN DESCRIPTION:
UNT003 IN NURI 110.0
END DESCRIPTION:
XS GIS Cut Line= 3
      2299593.28     13344489.19      2298742.32     13344466.19
      2296902.98     13345201.93
#Sta/Elev= 30
  3081.4  288.24  3617.2  276.28  3897.3  275.48  3959.2  273.66  3980.7  275.37
  4058.6  271.47  4322.4  265.92  4824.5  266.95  4928.5  266.36    4974  262.16
  4995.3  257.94    4998  257.44  5001.3  257.94  5031.2  261.29  5081.7  265.61
    5351  277.09  5380.8  280.37  5399.5  279.75  5562.6  289.96  5660.9  296.71
  5800.7  301.69  5811.7  304.61  5830.3  305.05  5835.7  299.02  5865.5   296.6
  5876.3  297.13  5884.1  303.33  5889.5  300.95  5897.8   306.2  5913.7  304.66
#Mann= 6 ,-1 , 0
  3081.4     .05       0  4824.5      .1       0  4995.3     .07       0
  5001.3      .1       0  5031.2     .05       0  5562.6      .1       0
Bank Sta=4928.5,5081.7
XS Rating Curve= 0 ,0
Exp/Cntr=0.3,0.1

Type RM Length L Ch R = 1 ,77309   ,936,936,936
BEGIN DESCRIPTION:
UNT003 IN NURI 109.0
END DESCRIPTION:
XS GIS Cut Line= 3
      2299156.29     13343776.22      2298454.83      13344040.7
      2296775.86     13344684.69
#Sta/Elev= 30
  3289.7   282.3  3437.8  278.58  3450.6  279.47  3598.1  273.77  3608.8  275.38
  3676.2  272.59  3801.2  272.77  3854.6  274.88  3871.6  273.12  3918.7  274.82
  4017.3   274.6    4321  264.15  4689.9   265.9  4902.3  264.18  4933.4  264.83
  4957.4  262.96  4997.2  257.06  4999.9  256.56  5003.2  257.06  5038.6  260.57
  5108.2  264.37    5327  275.36  5460.7  279.15  5630.5  286.72  5685.2  287.56
  5696.4  289.41  5728.5  289.71  5750.6  292.17    5830  295.73  5837.6  294.98
#Mann= 5 ,-1 , 0
  3289.7     .05       0  4902.3      .1       0  4997.2     .07       0
  5003.2      .1       0  5038.6     .05       0
Bank Sta=4933.4,5108.2
XS Rating Curve= 0 ,0
Exp/Cntr=0.3,0.1

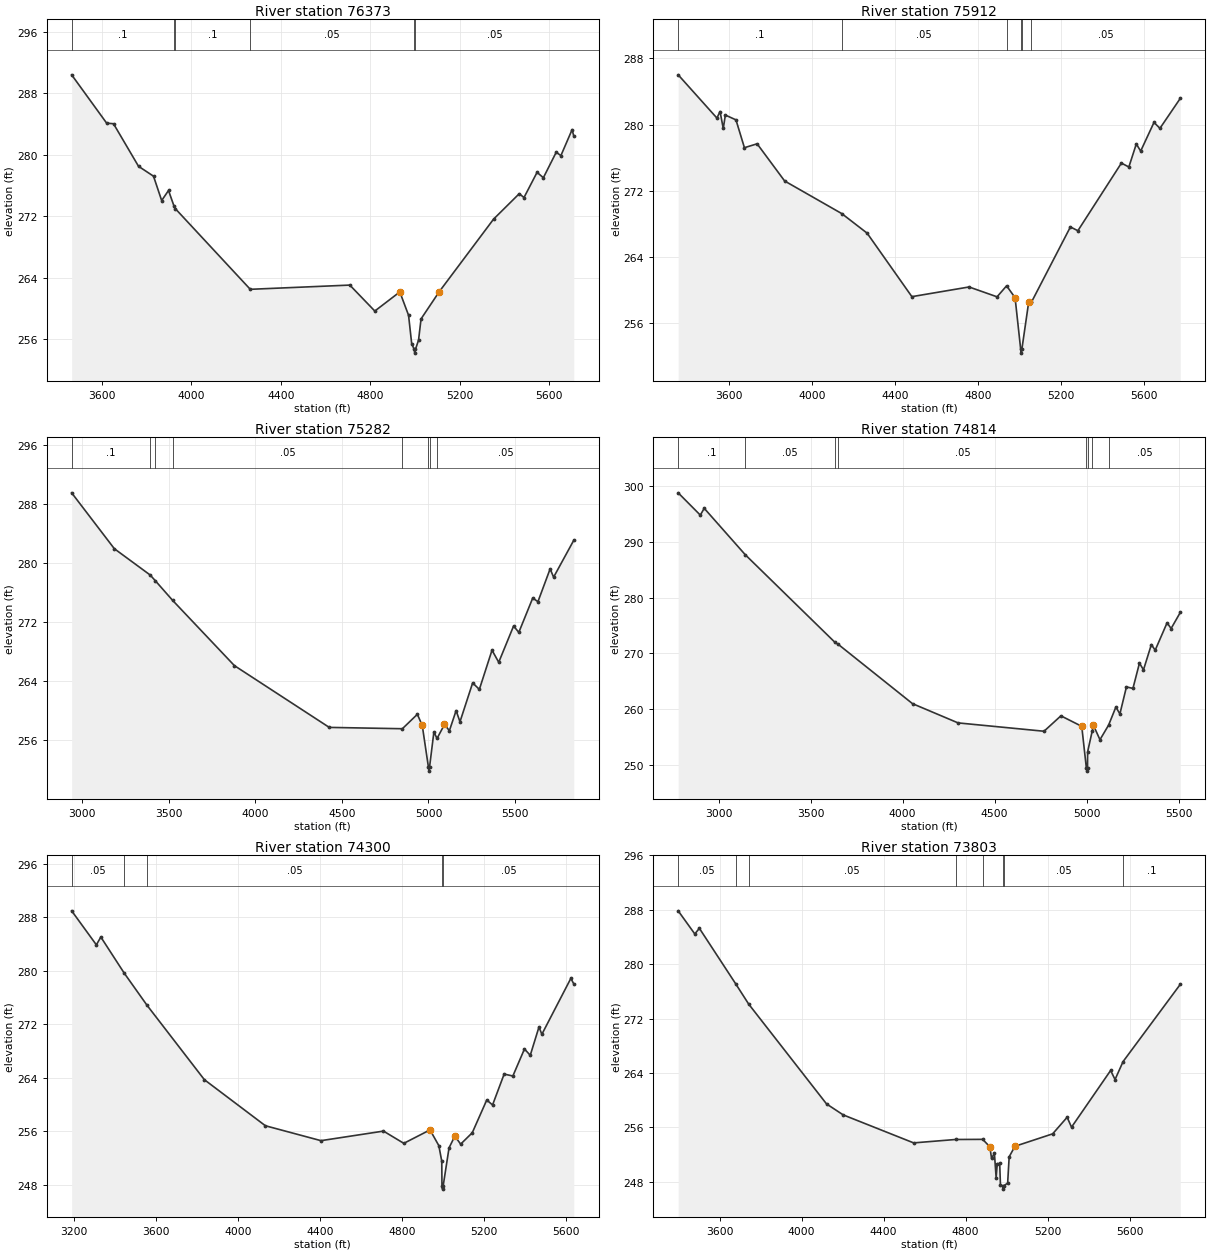
Type RM Length L Ch R = 1 ,76373   ,461,461,461
BEGIN DESCRIPTION:
UNT003 IN NURI 108.0
END DESCRIPTION:
XS GIS Cut Line= 3
      2298587.69     13342846.87      2297187.72     13343546.85
      2296637.71     13343946.86
#Sta/Elev= 30
  3464.8  290.42  3621.3  284.13    3652  284.05  3763.8  278.51  3830.9  277.22
  3867.3  274.05    3898  275.36  3922.8   273.3  3929.1  272.97  4263.5  262.49
  4708.6  263.04  4820.4  259.66  4932.2  262.15  4971.3  259.11  4985.3  255.41
  4996.3  254.68    4999  254.18  5002.3  254.68    5016  255.88  5027.2  258.64
  5108.5  262.18  5351.5  271.63  5466.3  274.94  5487.5  274.44  5545.9  277.72
  5574.1  277.02  5631.6  280.34  5652.5   279.9  5702.7  283.29  5710.1  282.43
#Mann= 6 ,-1 , 0
  3464.8      .1       0  3922.8     .05       0  3929.1      .1       0
  4263.5     .05       0  4996.3     .03       0  5002.3     .05       0
Bank Sta=4932.2,5108.5
XS Rating Curve= 0 ,0
Exp/Cntr=0.3,0.1

Type RM Length L Ch R = 1 ,75912   ,630,630,630
BEGIN DESCRIPTION:
UNT003 IN NURI 107.0
END DESCRIPTION:
XS GIS Cut Line= 3
       2298500.8     13342511.25      2297661.35     13342683.74
      2296362.31     13343557.43
#Sta/Elev= 30
  3352.8  286.02  3539.7   280.8  3554.8  281.59  3570.3  279.54  3580.5  281.16
  3631.6  280.58  3672.4  277.22  3733.7  277.69  3866.4   273.2  4142.1  269.26
  4264.3   266.9  4480.3  259.23  4756.2   260.4  4891.2  259.21  4937.3  260.54
  4978.2   259.1  5005.1  252.91  5007.9  252.41  5011.1  252.91  5044.1  258.62
  5056.6  258.54  5245.1  267.65  5281.1  267.19  5491.1  275.36  5527.1  274.89
    5563  277.67  5584.1  276.81  5648.3  280.27  5677.1  279.56  5775.3  283.18
#Mann= 6 ,-1 , 0
  3352.8      .1       0  4142.1     .05       0  4937.3      .1       0
  5005.1     .07       0  5011.1      .1       0  5056.6     .05       0
Bank Sta=4978.2,5044.1
XS Rating Curve= 0 ,0
Exp/Cntr=0.3,0.1

Type RM Length L Ch R = 1 ,75282   ,468,468,468
BEGIN DESCRIPTION:
UNT003 IN NURI 106.0
END DESCRIPTION:
XS GIS Cut Line= 4
      2298397.33     13341338.28      2297569.35     13342143.25
      2296350.39     13342752.74      2295971.78     13342787.16
#Sta/Elev= 30
  2940.7  289.47    3187  281.92    3394  278.36  3422.8  277.61  3523.7  274.93
  3879.9  266.12  4427.4  257.77  4849.3  257.59  4935.8  259.54  4964.1  258.03
  4999.9  252.36  5002.7  251.86  5005.9  252.36  5031.2  257.15  5049.3  256.27
  5092.4  258.17  5120.6  257.32  5159.4  260.04  5181.8  258.53  5254.8  263.78
  5293.6  262.91  5366.6   268.2  5405.4  266.57  5491.1  271.47  5521.3  270.61
  5601.6  275.25  5631.7  274.76    5702  279.19  5722.1  278.07  5838.5  283.06
#Mann= 8 ,-1 , 0
  2940.7      .1       0    3394     .05       0  3422.8      .1       0
  3523.7     .05       0  4849.3      .1       0  4999.9     .07       0
  5005.9      .1       0  5049.3     .05       0
Bank Sta=4964.1,5092.4
XS Rating Curve= 0 ,0
Exp/Cntr=0.3,0.1

Type RM Length L Ch R = 1 ,74814   ,514,514,514
BEGIN DESCRIPTION:
UNT003 IN NURI 105.0
END DESCRIPTION:
XS GIS Cut Line= 3
      2298087.72     13340546.86      2296537.72     13342146.85
      2296137.69     13342446.88
#Sta/Elev= 30
  2780.8  298.84  2901.1  294.83  2922.2  296.06    3145  287.72  3632.5  271.96
  3650.7  271.59  4053.7  260.94  4301.2  257.48  4768.1  255.98  4859.9  258.75
  4973.1  256.86  4998.4  249.31  5001.1  248.81  5004.4  249.31    5005  252.28
    5030  256.02  5036.6  257.05    5072  254.46  5118.8  257.07  5158.5  260.33
  5180.3  259.09  5215.8  263.95  5251.2  263.68  5286.6  268.23  5308.5  267.02
  5351.2  271.56    5372  270.55  5436.6  275.47  5458.5  274.45  5508.5  277.34
#Mann= 8 ,-1 , 0
  2780.8      .1       0    3145     .05       0  3632.5      .1       0
  3650.7     .05       0  4998.4    .035       0  5004.4     .05       0
    5030      .1       0  5118.8     .05       0
Bank Sta=4973.1,5036.6
XS Rating Curve= 0 ,0
Exp/Cntr=0.3,0.1

Type RM Length L Ch R = 1 ,74300   ,497,497,497
BEGIN DESCRIPTION:
UNT003 IN NURI 104.0
END DESCRIPTION:
XS GIS Cut Line= 3
      2297637.72     13340596.86      2296237.72     13341746.85
      2295787.69     13342196.89
#Sta/Elev= 30
  3189.9  288.98  3310.4  283.89  3332.2  285.06    3446  279.67  3557.2  274.86
    3837  263.72  4134.6  256.83  4405.4   254.6  4710.3  256.03  4809.4   254.2
  4937.1  256.21  4980.1  253.86  4994.5  251.52  4995.4  247.85  4998.2  247.35
  5001.4  247.85  5029.9  253.52  5058.2  255.28  5086.5  254.08  5143.1  255.78
  5213.8  260.68  5242.1  259.94  5298.6  264.56  5341.1  264.27  5397.6  268.31
  5425.9  267.37  5468.4   271.6  5482.5  270.51  5623.9  278.88  5638.1  278.05
#Mann= 5 ,-1 , 0
  3189.9     .05       0    3446      .1       0  3557.2     .05       0
  4995.4    .035       0  5001.4     .05       0
Bank Sta=4937.1,5058.2
XS Rating Curve= 0 ,0
Exp/Cntr=0.3,0.1

Type RM Length L Ch R = 1 ,73803   ,549,549,549
BEGIN DESCRIPTION:
UNT003 IN NURI 103.0
END DESCRIPTION:
XS GIS Cut Line= 3
      2297587.74     13340546.85      2296187.72     13341246.85
      2295537.69     13341846.88
#Sta/Elev= 30
  3397.7  287.84  3478.8  284.44  3501.1  285.27    3678  277.12  3741.8  274.12
  4121.6  259.44  4202.7  257.83  4546.5  253.71    4751  254.21  4883.4  254.23
  4918.2  253.14  4926.6  251.45  4940.6  252.18    4949  248.62  4954.6  250.65
  4966.4  250.68  4970.1  247.49  4981.2  247.41    4984  246.91  4987.2  247.41
  5005.2   247.8  5012.6  251.67  5040.9  253.21  5224.7  255.04  5295.5  257.48
  5316.8  256.02  5507.6  264.36  5529.2  263.03  5568.4  265.67  5847.6  277.03
#Mann= 8 ,-1 , 0
  3397.7     .05       0    3678      .1       0  3741.8     .05       0
    4751      .1       0  4883.4     .05       0  4981.2    .035       0
  4987.2     .05       0  5568.4      .1       0
Bank Sta=4918.2,5040.9
XS Rating Curve= 0 ,0
Exp/Cntr=0.3,0.1

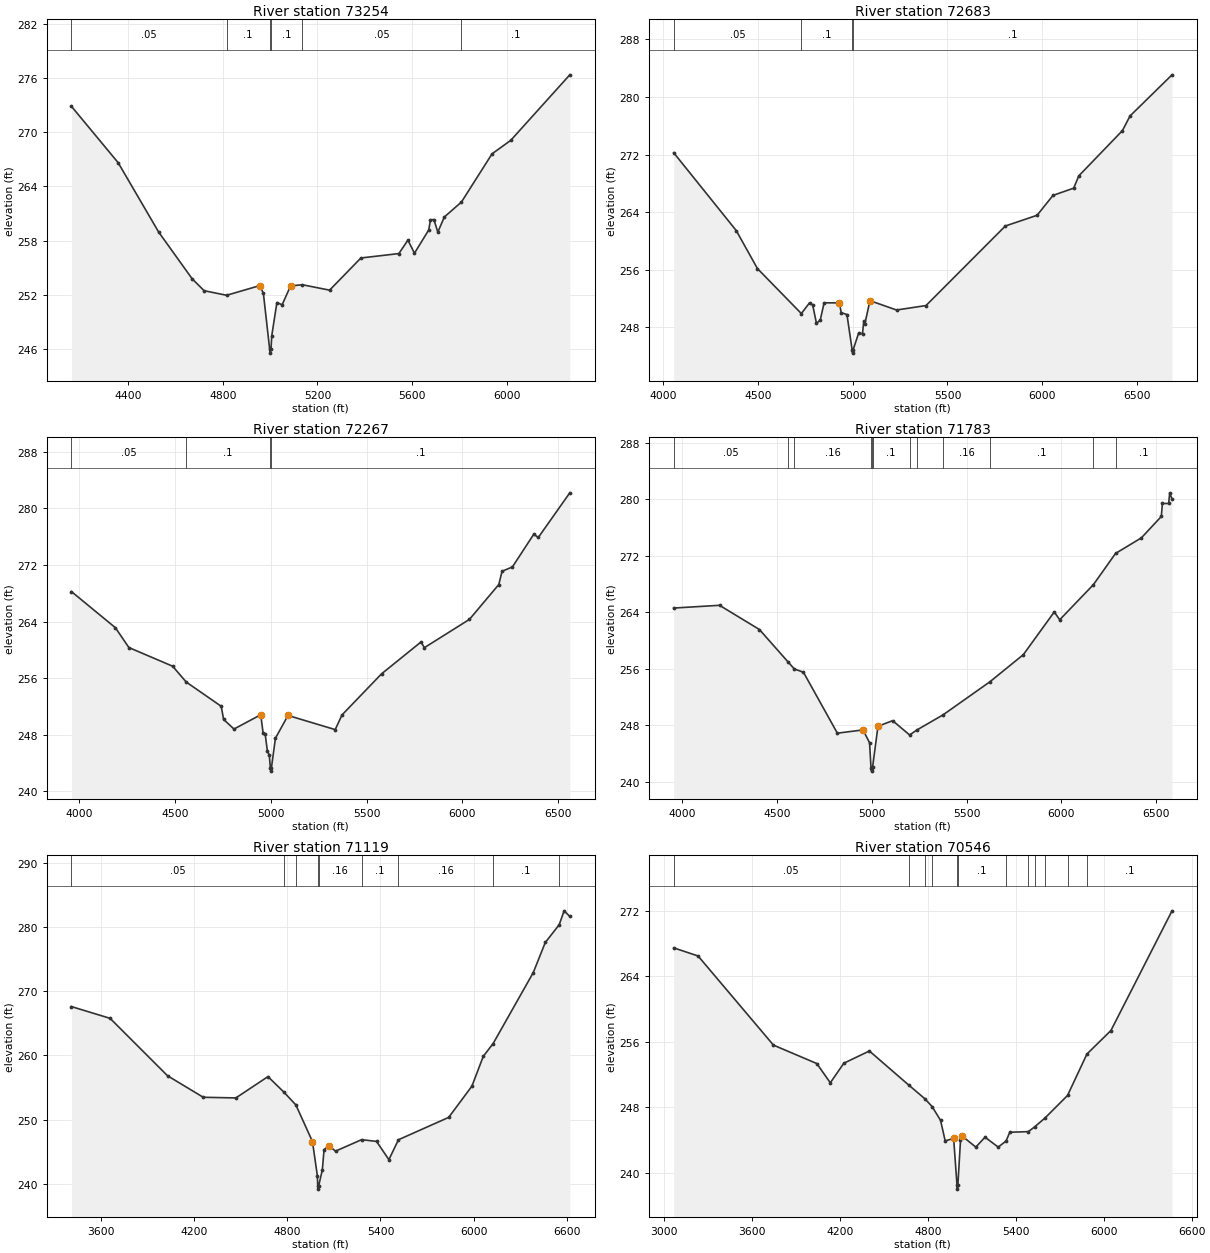
Type RM Length L Ch R = 1 ,73254   ,571,571,571
BEGIN DESCRIPTION:
UNT003 IN NURI 102.0
END DESCRIPTION:
XS GIS Cut Line= 3
      2296807.64     13340251.91      2295904.42     13340915.94
      2295442.64     13341787.41
#Sta/Elev= 30
  4159.8  272.89  4357.2  266.64  4528.5  258.94  4670.5  253.74  4720.6  252.43
  4815.9  251.92  4956.7     253  4971.4  252.13  4997.7     246  5000.4   245.5
  5003.7     246  5006.9  247.45  5028.5  251.11  5050.8  250.87  5086.3  252.96
  5136.2  253.09  5251.4  252.49  5383.7  256.06  5544.3  256.55  5582.6  258.04
  5610.3  256.59  5670.6  259.17    5678   260.3  5692.6  260.32    5709  258.93
  5736.6  260.61  5808.9  262.27  5938.3  267.62  6017.5  269.12  6267.1  276.39
#Mann= 6 ,-1 , 0
  4159.8     .05       0  4815.9      .1       0  4997.7     .07       0
  5003.7      .1       0  5136.2     .05       0  5808.9      .1       0
Bank Sta=4956.7,5086.3
XS Rating Curve= 0 ,0
Exp/Cntr=0.3,0.1

Type RM Length L Ch R = 1 ,72683   ,416,416,416
BEGIN DESCRIPTION:
UNT003 IN NURI 101.0
END DESCRIPTION:
XS GIS Cut Line= 3
      2296737.67     13340196.86      2295787.72     13340296.85
      2294187.73     13340796.85
#Sta/Elev= 30
  4054.1  272.27  4384.6  261.45  4496.5  256.17  4728.1  249.93  4771.7  251.42
  4788.1  251.12  4808.2  248.55  4828.3  249.05  4848.4  251.42  4928.9  251.41
  4938.9  250.05  4969.1  249.79  4996.2  244.93    4999  244.43  5002.2  244.93
  5030.8  247.22  5051.2  247.12    5058  248.92  5063.3  248.46  5090.5  251.72
  5230.9  250.42  5386.5  251.04  5805.5  262.09  5973.2  263.58    6057  266.34
  6166.5  267.35  6193.2  269.05  6423.7  275.34    6464  277.38  6685.6  283.09
#Mann= 4 ,-1 , 0
  4054.1     .05       0  4728.1      .1       0  4996.2     .07       0
  5002.2      .1       0
Bank Sta=4928.9,5090.5
XS Rating Curve= 0 ,0
Exp/Cntr=0.3,0.1

Type RM Length L Ch R = 1 ,72267   ,484,484,484
BEGIN DESCRIPTION:
UNT003 IN NURI 100.0
END DESCRIPTION:
XS GIS Cut Line= 3
      2296545.89     13339935.32       2296016.9     13339762.82
      2294131.85     13340555.92
#Sta/Elev= 30
  3959.6  268.23  4189.1  263.12  4259.3  260.32  4487.9  257.68  4558.5  255.45
  4741.6  252.01  4753.8  250.16    4808   248.8  4947.8  250.82  4959.9  248.27
  4970.8  248.11  4982.4  245.69  4992.5  245.12  4997.7  243.35  5000.4  242.85
  5003.7  243.35  5024.4   247.5  5090.1  250.72  5336.4  248.72  5372.2   250.8
  5578.3   256.6  5784.5  261.11  5801.8   260.3  6037.2   264.3  6190.5  269.23
  6207.6   271.1  6261.7  271.72  6372.9  276.33  6396.7  275.88  6561.1  282.19
#Mann= 4 ,-1 , 0
  3959.6     .05       0  4558.5      .1       0  4997.7     .07       0
  5003.7      .1       0
Bank Sta=4947.8,5090.1
XS Rating Curve= 0 ,0
Exp/Cntr=0.3,0.1

Type RM Length L Ch R = 1 ,71783   ,664,664,664
BEGIN DESCRIPTION:
UNT003 IN NURI 99.0
END DESCRIPTION:
XS GIS Cut Line= 3
      2296200.89     13339521.33      2295694.91     13339371.83
      2293832.32     13340337.62
#Sta/Elev= 30
  3956.9  264.59  4198.5  264.98  4408.6  261.55    4560  256.94  4592.5  255.96
  4640.7  255.49  4819.3  246.86  4954.4  247.32    4989   245.5  4996.5  241.98
  4999.2  241.48  5002.5  241.98  5004.7     242  5033.3  247.84  5110.5  248.63
  5200.3   246.6  5236.4  247.28  5376.5  249.46    5623  254.14  5799.3  257.99
  5962.2  264.04  5990.8  262.93  6168.5  267.91    6285  272.33  6421.2  274.54
  6526.2  277.57  6531.9  279.41  6564.8  279.41  6570.5  280.92  6582.6  280.03
#Mann= 12 ,-1 , 0
  3956.9     .05       0    4560      .1       0  4592.5     .16       0
  4996.5     .07       0  5002.5     .16       0  5004.7      .1       0
  5200.3     .16       0  5236.4      .1       0  5376.5     .16       0
    5623      .1       0  6168.5     .16       0    6285      .1       0
Bank Sta=4954.4,5033.3
XS Rating Curve= 0 ,0
Exp/Cntr=0.3,0.1

Type RM Length L Ch R = 1 ,71119   ,573,573,573
BEGIN DESCRIPTION:
UNT003 IN NURI 98.0
END DESCRIPTION:
XS GIS Cut Line= 4
      2296706.55     13338919.42      2295439.14     13338961.08
      2294886.55     13339143.87      2293787.71     13339946.86
#Sta/Elev= 30
  3408.9  267.61  3657.9  265.78  4028.1  256.84  4258.2  253.49  4468.3  253.39
  4675.2  256.71  4775.7  254.34  4854.8  252.31  4961.8   246.6  4993.5  241.27
  4995.8  239.69  4998.6  239.19  5001.8  239.69  5025.3  242.17  5036.6  245.34
  5068.2  245.96  5110.3   245.1  5278.2  246.89  5374.7  246.62  5454.3  243.78
    5516  246.88  5839.7  250.36  5989.5  255.23  6062.6  259.87  6126.1  261.86
  6384.7  272.91  6462.1  277.59  6551.9  280.36  6583.3  282.52    6620  281.65
#Mann= 9 ,-1 , 0
  3408.9     .05       0  4775.7      .1       0  4854.8     .16       0
  4995.8     .07       0  5001.8     .16       0  5278.2      .1       0
    5516     .16       0  6126.1      .1       0  6551.9     .05       0
Bank Sta=4961.8,5068.2
XS Rating Curve= 0 ,0
Exp/Cntr=0.3,0.1

Type RM Length L Ch R = 1 ,70546   ,563,563,563
BEGIN DESCRIPTION:
UNT003 IN NURI 97.0
END DESCRIPTION:
XS GIS Cut Line= 4
      2296689.96      13338873.4      2295101.46     13338508.83
      2294481.01     13338700.21      2293547.61     13339324.82
#Sta/Elev= 30
  3063.7  267.46  3230.2  266.47  3744.7  255.59  4040.7  253.34    4133  250.99
  4225.4  253.38  4399.8  254.87  4668.7  250.71  4777.3  249.06  4827.9  248.09
  4885.8   246.4  4917.2   243.9    4975   244.2  4997.9  238.51  5000.6  238.01
  5003.9  238.51  5021.8  243.95  5032.3   244.5  5126.5  243.14  5189.3  244.35
  5279.4  243.14  5332.8  243.88  5358.3  244.95  5484.9  245.03  5528.1  245.61
  5599.8  246.71  5752.4  249.44    5885   254.5  6048.8  257.37  6465.9  271.98
#Mann= 12 ,-1 , 0
  3063.7     .05       0  4668.7      .1       0  4777.3     .16       0
  4827.9      .1       0  4997.9     .07       0  5003.9      .1       0
  5332.8     .05       0  5484.9      .1       0  5528.1     .05       0
  5599.8      .1       0  5752.4     .05       0    5885      .1       0
Bank Sta=4975,5032.3
XS Rating Curve= 0 ,0
Exp/Cntr=0.3,0.1