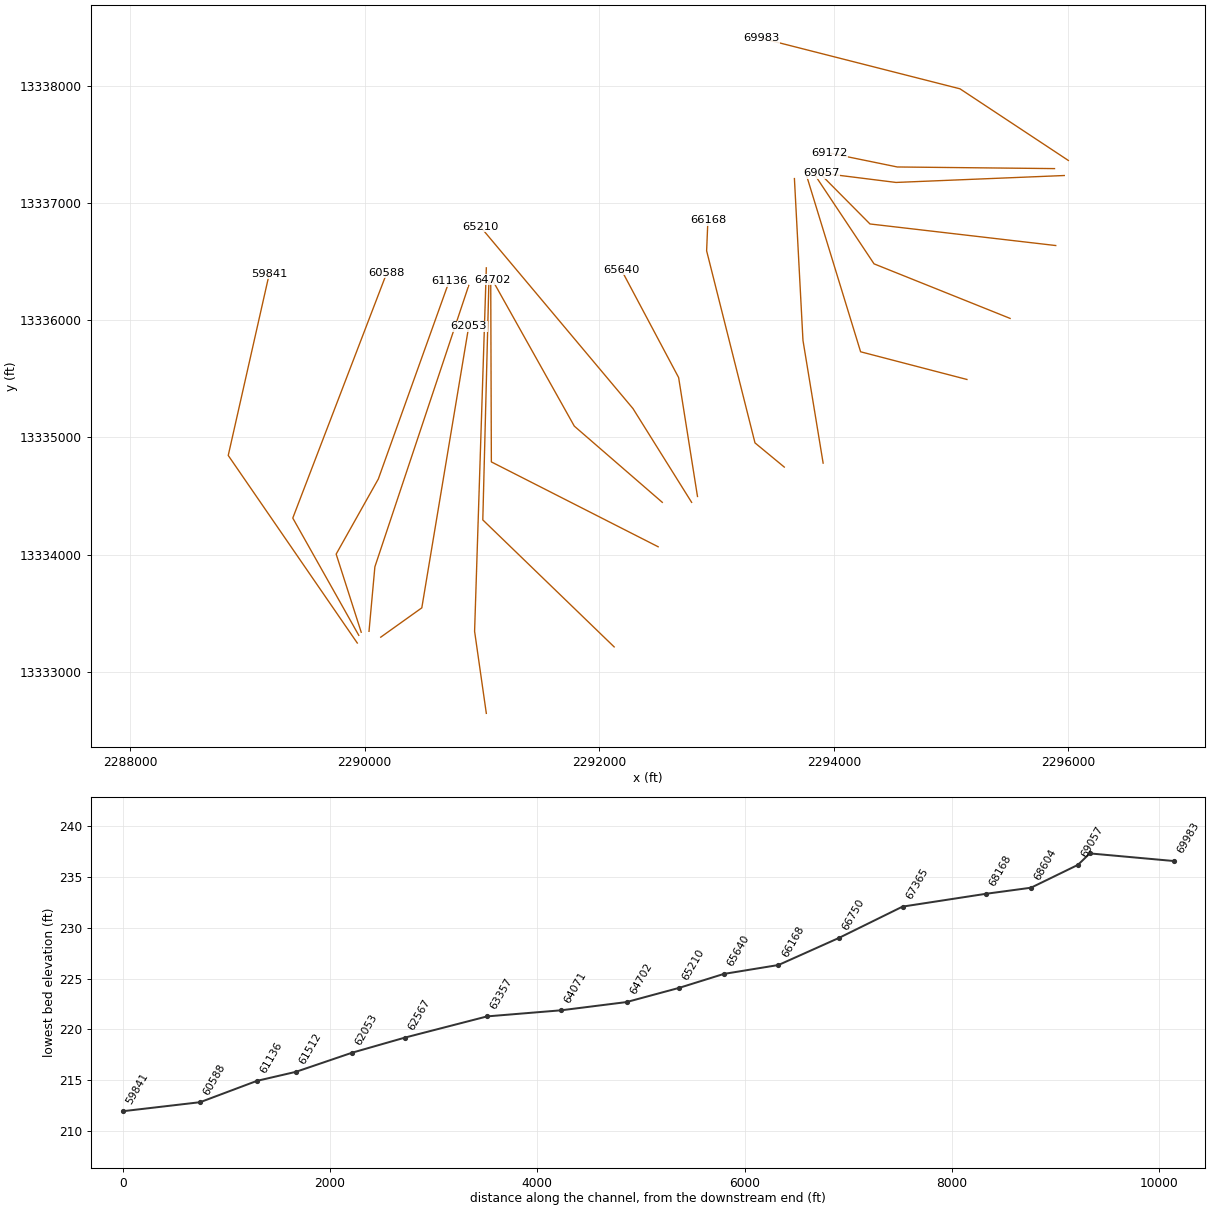
HEC-RAS study UNT003 IN NURI.prj: UNT003 IN NURI Base Level Engineering

--- UNT003 IN NURI.g01 (geometry) --- (continued)

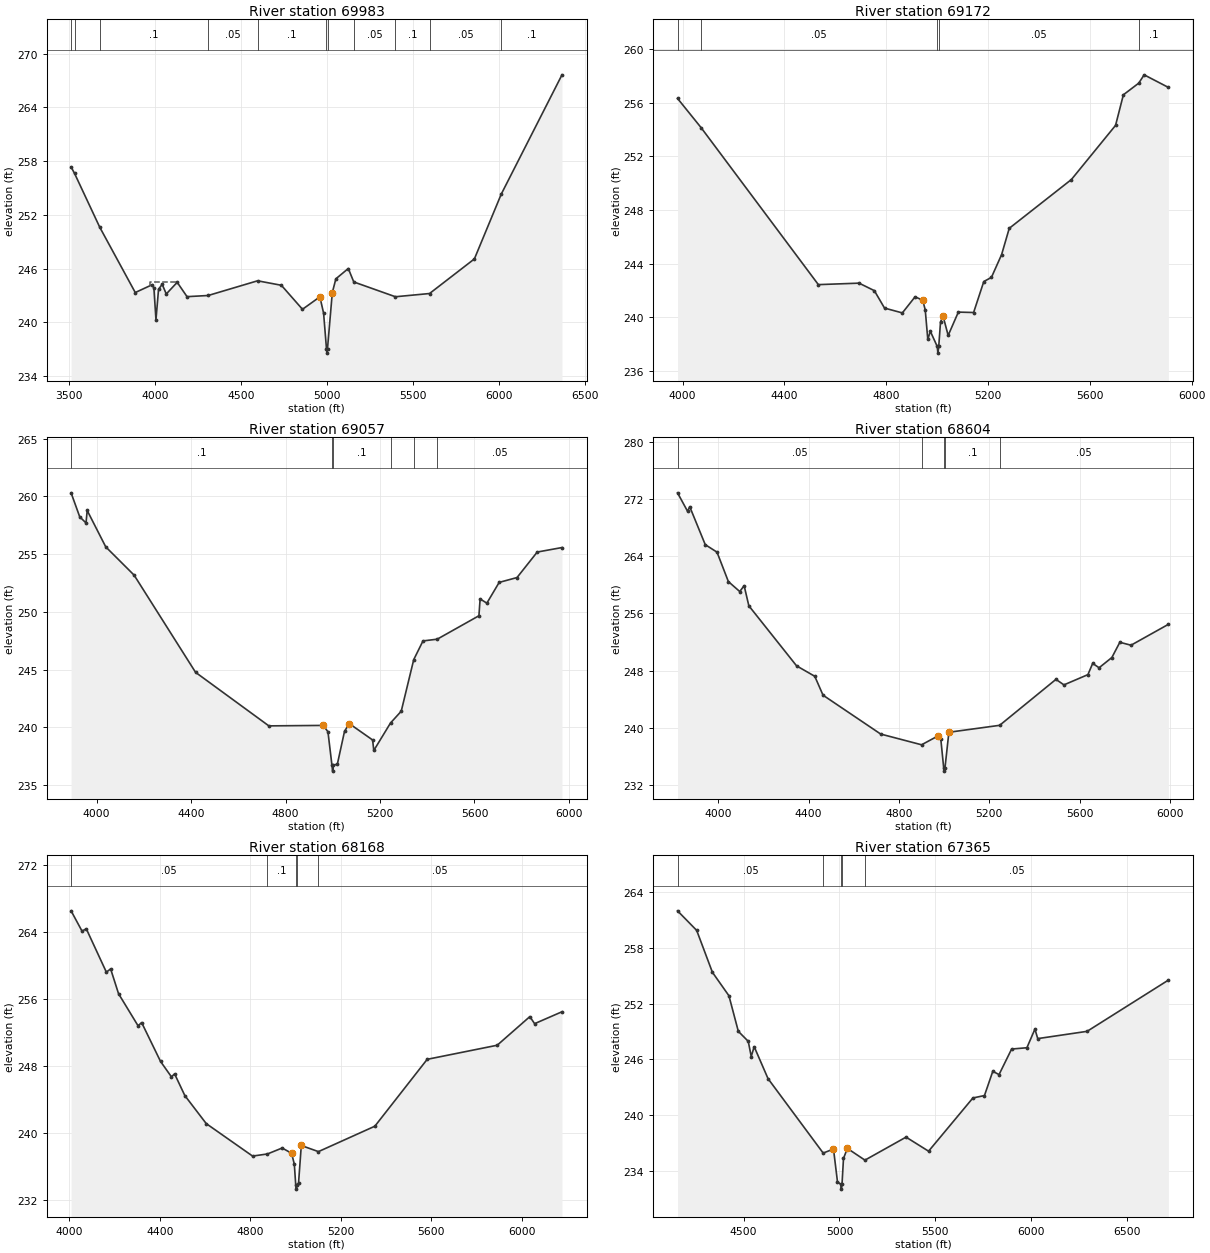
Type RM Length L Ch R = 1 ,69983   ,811,811,811
BEGIN DESCRIPTION:
UNT003 IN NURI 96.0
END DESCRIPTION:
XS GIS Cut Line= 3
      2295999.01     13337363.01      2295075.42      13337974.1
      2293384.42     13338404.67
#Sta/Elev= 30
  3512.9  257.35  3532.8  256.64  3679.6  250.62  3885.8  243.34    3985  244.22
  3994.1  243.83  4006.1  240.31  4021.1   243.7  4042.2  244.26    4066  243.18
  4129.5  244.48  4186.6  242.88  4309.4  243.01  4596.6  244.65  4734.7  244.15
  4857.4  241.47  4958.5  242.86  4980.1  241.04  4996.8  237.08  4999.5  236.58
  5002.8  237.08  5030.7  243.33  5051.4  244.87  5123.6  246.02  5155.5  244.52
  5397.5  242.87  5595.8  243.23  5856.3  247.09  6012.4  254.32  6365.3  267.63
#Mann= 11 ,-1 , 0
  3512.9     .08       0  3532.8     .05       0  3679.6      .1       0
  4309.4     .05       0  4596.6      .1       0  4996.8     .07       0
  5002.8      .1       0  5155.5     .05       0  5397.5      .1       0
  5595.8     .05       0  6012.4      .1       0
#XS Ineff= 1 ,-1
 3973.44 4130.47  244.56
Permanent Ineff=
       F
Bank Sta=4958.5,5030.7
XS Rating Curve= 0 ,0
Exp/Cntr=0.3,0.1

Type RM Length L Ch R = 1 ,69172   ,115,115,115
BEGIN DESCRIPTION:
UNT003 IN NURI 95.0
END DESCRIPTION:
XS GIS Cut Line= 3
      2295880.95     13337293.55       2294540.7     13337307.44
      2293964.29      13337425.5
#Sta/Elev= 30
    3980  256.33  4072.6  254.15  4533.3  242.44  4693.3  242.55  4753.3  241.99
  4793.3  240.69  4863.3  240.33  4913.3  241.53  4943.3  241.28  4953.3  240.55
  4963.3  238.35  4973.3  238.96  5000.3  237.83    5003  237.33  5006.3  237.83
  5013.3  239.66  5023.3  240.09  5043.3  238.65  5083.3  240.39  5143.3  240.36
  5183.3  242.67  5213.3  242.98  5253.3  244.68  5283.3  246.64  5527.5  250.28
    5701  254.32  5731.7   256.6  5792.1  257.47  5813.3  258.09  5908.7  257.15
#Mann= 5 ,-1 , 0
    3980     .08       0  4072.6     .05       0  5000.3     .04       0
  5006.3     .05       0  5792.1      .1       0
Bank Sta=4943.3,5023.3
XS Rating Curve= 0 ,0
Exp/Cntr=0.3,0.1

Type RM Length L Ch R = 1 ,69057   ,453,453,453
BEGIN DESCRIPTION:
UNT003 IN NURI 94.0
END DESCRIPTION:
XS GIS Cut Line= 3
      2295964.31     13337234.52      2294530.28     13337175.49
      2293892.09     13337255.27
#Sta/Elev= 30
  3892.2  260.31  3928.8  258.23  3955.4   257.7  3960.4  258.78  4038.9  255.63
    4159  253.18  4419.2  244.76  4729.5  240.12  4959.7  240.16  4979.7  239.61
  4996.7   236.7  4999.5   236.2  5002.7   236.7  5019.7  236.82  5049.8  239.64
  5069.8  240.32  5168.8   238.9  5173.8  237.99  5244.6  240.37    5290  241.39
  5342.9  245.86  5382.1  247.48  5442.3  247.63  5618.9  249.66    5624  251.12
  5652.5  250.75  5704.6  252.55  5780.2  252.97  5865.8  255.18  5970.6  255.57
#Mann= 6 ,-1 , 0
  3892.2      .1       0  4996.7     .07       0  5002.7      .1       0
  5244.6     .05       0  5342.9      .1       0  5442.3     .05       0
Bank Sta=4959.7,5069.8
XS Rating Curve= 0 ,0
Exp/Cntr=0.3,0.1

Type RM Length L Ch R = 1 ,68604   ,436,436,436
BEGIN DESCRIPTION:
Mapping XS 0b025cd8
END DESCRIPTION:
XS GIS Cut Line= 3
      2295891.43     13336637.29      2294308.06     13336821.33
      2293899.69     13337233.16
#Sta/Elev= 30
  3819.5  272.83  3863.8  270.26  3873.6  270.89  3942.3  265.59  3994.4  264.54
  4044.7  260.43  4095.1  259.04  4114.5  259.86  4135.3  257.05  4346.7  248.66
  4427.3   247.2  4463.9  244.56  4719.2  239.13  4900.3  237.63  4970.9  238.83
  4985.5  238.42  4998.1  234.45  5000.9  233.95  5004.1  234.45  5021.2  239.38
  5246.1  240.35  5495.4  246.77  5530.8     246  5636.9  247.43  5658.1     249
  5686.4  248.39    5743  249.82  5778.3  251.95  5827.8  251.54  5993.5  254.46
#Mann= 5 ,-1 , 0
  3819.5     .05       0  4900.3      .1       0  4998.1     .07       0
  5004.1      .1       0  5246.1     .05       0
Bank Sta=4970.9,5021.2
XS Rating Curve= 0 ,0
Exp/Cntr=0.3,0.1

Type RM Length L Ch R = 1 ,68168   ,803,803,803
BEGIN DESCRIPTION:
Mapping XS c474fe4c
END DESCRIPTION:
XS GIS Cut Line= 3
      2295502.49     13336015.78      2294342.78     13336481.05
      2293832.57      13337248.1
#Sta/Elev= 30
  4007.2  266.52  4055.6   264.1  4074.4  264.38  4163.2  259.21    4182   259.6
  4217.1  256.64  4303.3  252.82  4319.2   253.2  4402.6  248.58    4451  246.73
  4464.9  247.09  4510.2   244.5  4604.9  241.16  4809.7  237.29  4875.4  237.54
  4940.5  238.25  4982.1  237.63  4994.3  236.34  5000.6  233.85  5003.4  233.35
  5006.6  233.85  5013.1   234.1  5025.2  238.55  5100.9  237.82  5350.5  240.85
  5581.9  248.82  5891.5   250.5  6035.8  253.91  6056.9  253.07    6178  254.49
#Mann= 5 ,-1 , 0
  4007.2     .05       0  4875.4      .1       0  5000.6     .07       0
  5006.6      .1       0  5100.9     .05       0
Bank Sta=4982.1,5025.2
XS Rating Curve= 0 ,0
Exp/Cntr=0.3,0.1

Type RM Length L Ch R = 1 ,67365   ,615,615,615
BEGIN DESCRIPTION:
UNT003 IN NURI 93.0
END DESCRIPTION:
XS GIS Cut Line= 3
      2295134.41     13335494.95       2294228.2     13335731.05
       2293752.8     13337282.17
#Sta/Elev= 30
    4156  261.95  4255.9  259.85  4337.7  255.36  4423.9  252.84  4472.9  249.02
  4524.6  247.95  4540.2  246.32  4555.6  247.37  4627.9  243.94  4915.2  235.96
    4969  236.39  4989.6   232.9  5007.3  232.59    5010  232.09  5013.3  232.59
  5021.1  235.38  5041.3  236.46  5132.9   235.2  5347.2  237.67  5464.6  236.16
  5695.6  241.87  5755.9  242.13  5799.3  244.73  5831.9  244.38  5897.4  247.12
  5977.1  247.26  6018.9  249.26  6033.6  248.24  6290.9  249.02  6714.8  254.52
#Mann= 5 ,-1 , 0
    4156     .05       0  4915.2      .1       0  5007.3     .07       0
  5013.3      .1       0  5132.9     .05       0
Bank Sta=4969,5041.3
XS Rating Curve= 0 ,0
Exp/Cntr=0.3,0.1

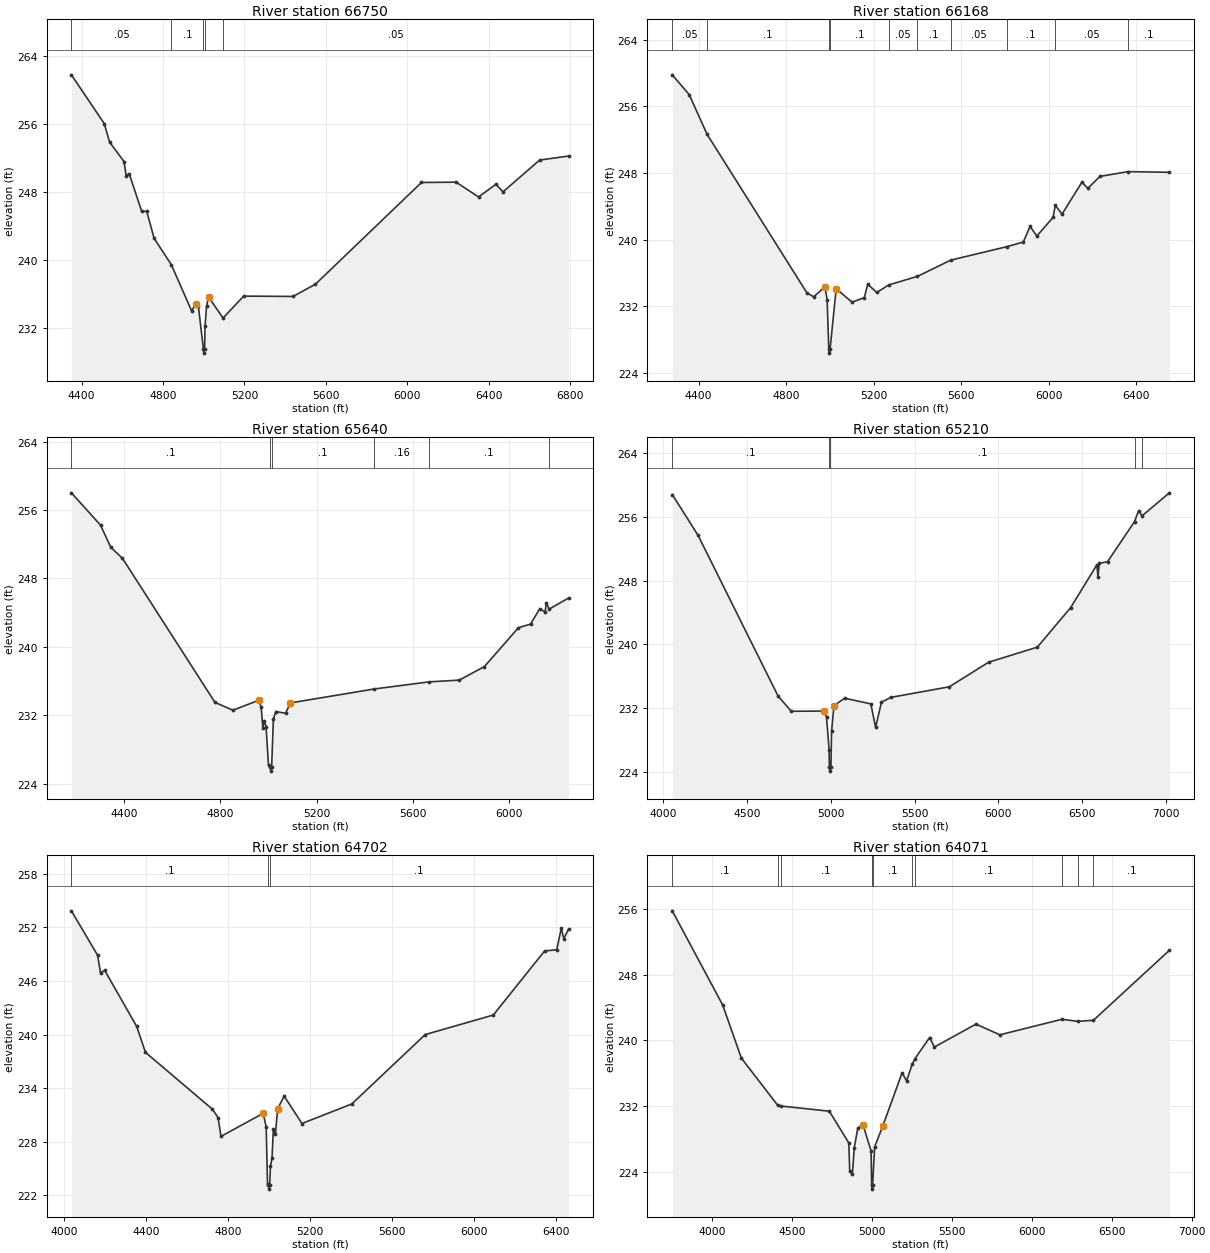
Type RM Length L Ch R = 1 ,66750   ,582,582,582
BEGIN DESCRIPTION:
UNT003 IN NURI 92.0
END DESCRIPTION:
XS GIS Cut Line= 3
      2293908.75     13334781.43      2293736.88     13335828.27
      2293663.96     13337208.49
#Sta/Elev= 30
  4349.9  261.75  4511.5  256.01  4537.8  253.82  4608.7  251.54  4618.9   249.9
    4634  250.12  4695.3  245.69  4720.2  245.68  4756.6   242.5  4840.8  239.42
  4940.4  233.99  4963.4  234.81  4973.6  234.59  4998.6   229.5  5001.4     229
  5004.6   229.5  5006.7  232.14  5014.1  234.55  5024.2   235.6  5095.2  233.13
  5196.5  235.71  5439.4  235.67  5549.5  237.12  6070.3  249.08  6240.5  249.12
  6350.6  247.38  6436.6  248.87  6470.8  247.97  6651.1  251.72  6792.9  252.19
#Mann= 5 ,-1 , 0
  4349.9     .05       0  4840.8      .1       0  4998.6     .07       0
  5004.6      .1       0  5095.2     .05       0
Bank Sta=4963.4,5024.2
XS Rating Curve= 0 ,0
Exp/Cntr=0.3,0.1

Type RM Length L Ch R = 1 ,66168   ,528,528,528
BEGIN DESCRIPTION:
UNT003 IN NURI 91.0
END DESCRIPTION:
XS GIS Cut Line= 4
       2293577.5     13334747.69      2293327.93     13334953.86
       2292915.6     13336592.32      2292926.44     13336852.33
#Sta/Elev= 30
  4279.3   259.8  4356.8  257.42  4438.9  252.63  4894.8   233.6  4925.8  233.11
  4977.3  234.31  4987.6  232.77  4995.1  226.84  4997.9  226.34  5001.1  226.84
  5028.9  234.09  5101.1  232.47  5157.4  233.01  5173.3  234.62  5214.5  233.63
  5269.2  234.54  5400.6  235.57  5552.9  237.52  5808.1  239.13  5884.8   239.7
  5915.7  241.57  5946.6  240.42  6020.8  242.66    6031   244.1  6061.9  243.06
  6152.9  246.89    6180  246.16  6235.4  247.59  6363.8  248.16  6552.8  248.08
#Mann= 10 ,-1 , 0
  4279.3     .05       0  4438.9      .1       0  4995.1     .07       0
  5001.1      .1       0  5269.2     .05       0  5400.6      .1       0
  5552.9     .05       0  5808.1      .1       0    6031     .05       0
  6363.8      .1       0
Bank Sta=4977.3,5028.9
XS Rating Curve= 0 ,0
Exp/Cntr=0.3,0.1

Type RM Length L Ch R = 1 ,65640   ,430,430,430
BEGIN DESCRIPTION:
UNT003 IN NURI 90.0
END DESCRIPTION:
XS GIS Cut Line= 3
      2292837.72     13334496.86      2292676.96      13335511.2
      2292188.39     13336430.77
#Sta/Elev= 30
  4180.2  258.02  4301.7  254.23  4343.6  251.67  4392.8  250.35  4777.6   233.5
  4852.2  232.59  4959.8  233.75  4969.9  232.94  4976.9  230.47  4981.9  231.38
  4990.2  230.67  5000.3  226.12  5007.4  225.96  5010.2  225.46  5013.4  225.96
  5020.6  231.59  5030.7  232.43  5071.2  232.23  5091.4  233.44  5440.1  235.07
  5667.4   235.9  5794.2  236.11  5898.5  237.69  6040.2  242.24  6090.6  242.66
  6128.9  244.46  6150.9  244.07  6156.6  245.14  6168.3  244.42  6248.5  245.71
#Mann= 6 ,-1 , 0
  4180.2      .1       0  5007.4     .07       0  5013.4      .1       0
  5440.1     .16       0  5667.4      .1       0  6168.3     .05       0
Bank Sta=4959.8,5091.4
XS Rating Curve= 0 ,0
Exp/Cntr=0.3,0.1

Type RM Length L Ch R = 1 ,65210   ,508,508,508
BEGIN DESCRIPTION:
UNT003 IN NURI 89.0
END DESCRIPTION:
XS GIS Cut Line= 3
      2292787.72     13334446.85      2292287.72     13335246.85
      2290987.72     13336796.86
#Sta/Elev= 30
  4054.2   258.8  4207.5   253.7  4685.7  233.51  4764.7   231.6  4962.2  231.63
  4974.6  230.91  4989.9  226.79  4991.7  224.59  4994.4  224.09  4997.7  224.59
  5000.9  224.59  5004.8  229.07  5019.1  232.31  5082.8  233.24  5238.9  232.53
  5267.5   229.6  5302.7  232.75  5359.9  233.35  5707.3  234.67  5941.5  237.75
  6232.9  239.65  6431.9  244.62    6588  249.97  6594.5  248.46  6602.3  250.16
  6651.8  250.37  6812.7   255.4  6836.5  256.76  6858.1  256.13  7020.6  259.01
#Mann= 5 ,-1 , 0
  4054.2      .1       0  4991.7     .07       0  4997.7      .1       0
  6812.7     .08       0  6858.1      .1       0
Bank Sta=4962.2,5019.1
XS Rating Curve= 0 ,0
Exp/Cntr=0.3,0.1

Type RM Length L Ch R = 1 ,64702   ,631,631,631
BEGIN DESCRIPTION:
UNT003 IN NURI 88.0
END DESCRIPTION:
XS GIS Cut Line= 3
      2292537.69     13334446.88      2291787.72     13335096.85
      2291087.71     13336346.87
#Sta/Elev= 30
  4037.3  253.86    4165  248.89  4179.3  246.92  4200.1  247.18  4355.9  240.91
  4398.6  238.01  4725.4  231.64  4752.9   230.7  4767.1   228.6  4973.2  231.18
  4987.5  229.64  4994.1   223.3  4998.7  223.19  5001.5  222.69  5004.7  223.19
  5008.4  225.26    5016  226.17  5022.6  229.43  5032.6  228.82  5043.4  231.69
  5075.4   233.1  5162.1  230.04  5405.3  232.23  5763.3     240  6095.6  242.19
  6345.9  249.37  6405.1   249.5    6427   251.9  6439.5  250.74  6462.4   251.8
#Mann= 3 ,-1 , 0
  4037.3      .1       0  4998.7     .07       0  5004.7      .1       0
Bank Sta=4973.2,5043.4
XS Rating Curve= 0 ,0
Exp/Cntr=0.3,0.1

Type RM Length L Ch R = 1 ,64071   ,714,714,714
BEGIN DESCRIPTION:
Mapping XS b42150c1
END DESCRIPTION:
XS GIS Cut Line= 3
      2292502.46     13334067.88      2291080.63     13334791.81
      2291075.42     13336307.48
#Sta/Elev= 30
  3749.3   255.8  4064.9  244.32  4181.7  237.85  4409.8  232.08  4428.5  232.01
  4732.2  231.38  4854.3  227.51    4860  224.06  4876.6   223.7    4888  226.89
  4910.4  229.33  4943.3   229.7  4993.4  226.56  4997.2  222.38    5000  221.88
  5003.2  222.38  5015.7  227.02  5067.5  229.61    5188  236.07  5215.9  235.07
  5250.4  237.07  5268.5  237.79  5359.9  240.36  5389.9   239.2  5649.9  241.99
  5799.9  240.69  6187.8  242.58  6286.6  242.33  6385.3  242.46  6860.5  250.99
#Mann= 10 ,-1 , 0
  3749.3      .1       0  4409.8     .16       0  4428.5      .1       0
  4997.2     .07       0  5003.2      .1       0  5250.4     .05       0
  5268.5      .1       0  6187.8     .08       0  6286.6     .05       0
  6385.3      .1       0
Bank Sta=4943.3,5067.5
XS Rating Curve= 0 ,0
Exp/Cntr=0.3,0.1

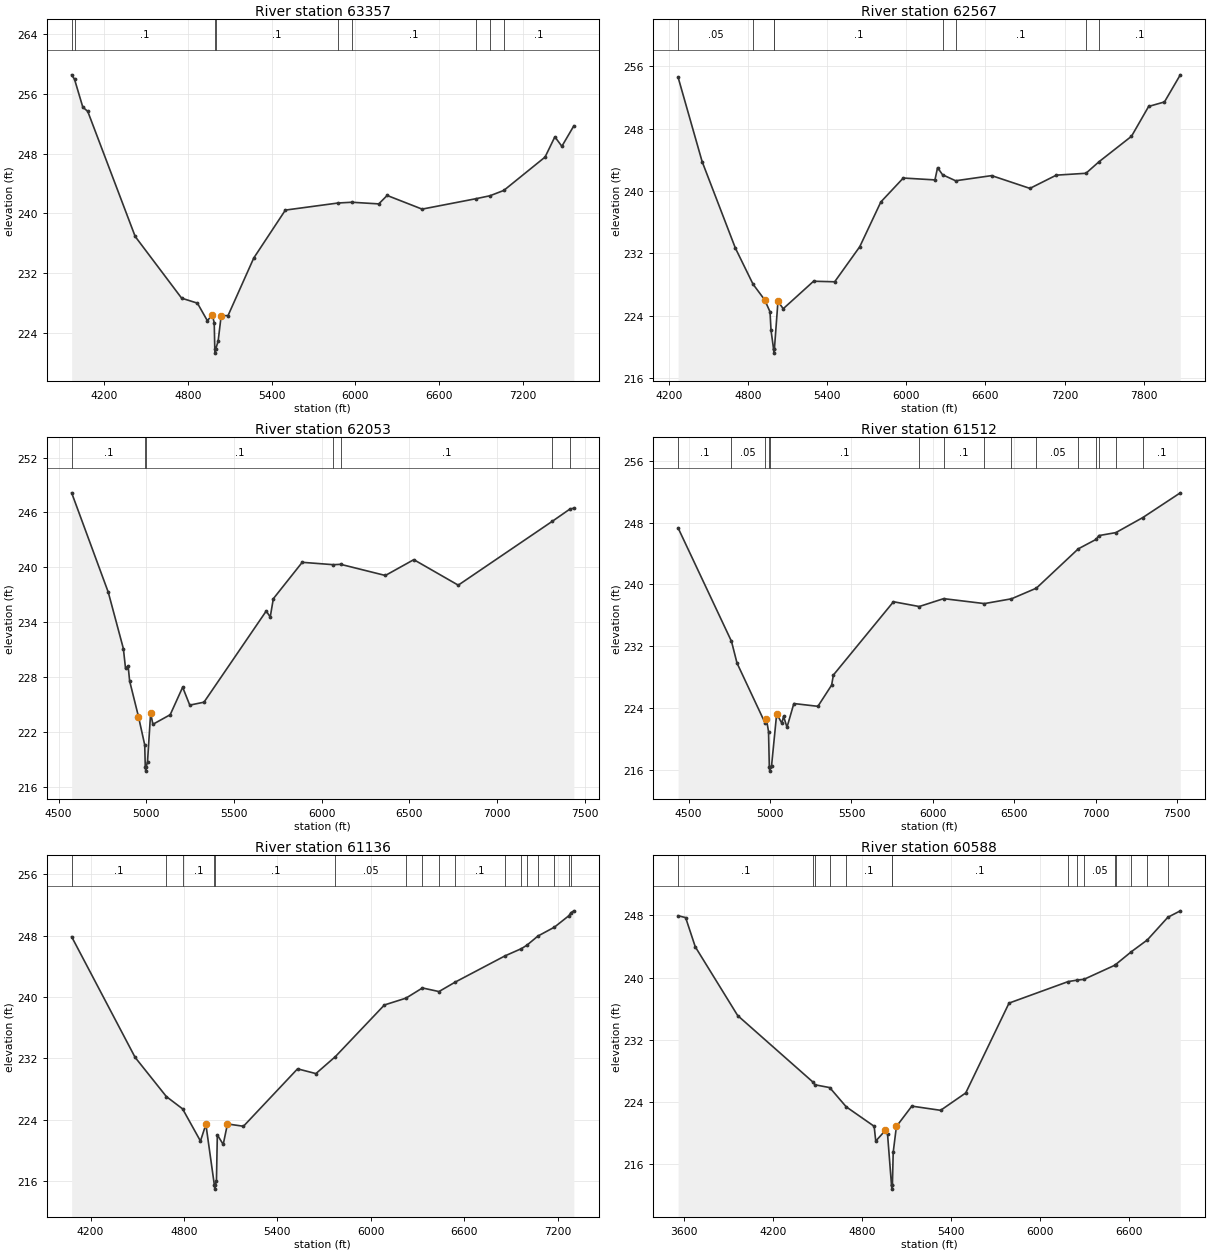
Type RM Length L Ch R = 1 ,63357   ,790,790,790
BEGIN DESCRIPTION:
Mapping XS 0f0aa469
END DESCRIPTION:
XS GIS Cut Line= 3
      2292127.47     13333213.72      2291007.71     13334297.02
      2291059.78     13336332.64
#Sta/Elev= 30
  3969.2  258.54  3989.7  257.95  4049.1  254.21  4084.3  253.65  4423.9   236.9
  4756.3  228.64  4869.4  227.97  4940.2  225.63  4975.4  226.36  4989.6  225.38
  4993.8  221.78  4996.5  221.28  4999.8  221.78  5017.9  222.92  5039.2  226.27
  5088.6  226.31  5272.5  234.01  5498.9  240.43  5876.2  241.38    5975  241.48
  6167.3  241.26  6227.3  242.39  6477.4  240.56  6864.4  241.96  6963.2  242.35
    7062  243.06  7357.6  247.53  7427.7  250.24  7477.7  248.97  7563.5  251.71
#Mann= 9 ,-1 , 0
  3969.2     .05       0  3989.7      .1       0  4993.8     .07       0
  4999.8      .1       0  5876.2     .05       0    5975      .1       0
  6864.4     .08       0  6963.2     .05       0    7062      .1       0
Bank Sta=4975.4,5039.2
XS Rating Curve= 0 ,0
Exp/Cntr=0.3,0.1

Type RM Length L Ch R = 1 ,62567   ,514,514,514
BEGIN DESCRIPTION:
UNT003 IN NURI 87.0
END DESCRIPTION:
XS GIS Cut Line= 3
      2291037.73     13332646.81      2290937.72     13333346.85
      2291037.72     13336446.89
#Sta/Elev= 30
  4268.7  254.61  4450.6   243.8  4703.1  232.68    4837  228.05  4925.3  226.04
  4965.7   224.5  4973.3  222.14  4992.9   219.7  4995.6   219.2  4998.9   219.7
  5025.9  225.84  5065.9   224.9    5296  228.43  5456.1  228.36  5646.2  232.86
  5806.3  238.61  5976.4  241.68  6216.5  241.44  6236.5  243.01  6274.4   242.1
  6373.3  241.33  6646.7  241.99  6936.9  240.35    7137  242.05  7361.9  242.29
  7460.8  243.77  7707.3  247.04  7837.3  250.87  7957.4  251.45  8077.5  254.93
#Mann= 8 ,-1 , 0
  4268.7     .05       0    4837      .1       0  4992.9     .07       0
  4998.9      .1       0  6274.4     .05       0  6373.3      .1       0
  7361.9     .05       0  7460.8      .1       0
Bank Sta=4925.3,5025.9
XS Rating Curve= 0 ,0
Exp/Cntr=0.3,0.1

Type RM Length L Ch R = 1 ,62053   ,541,541,541
BEGIN DESCRIPTION:
UNT003 IN NURI 86.0
END DESCRIPTION:
XS GIS Cut Line= 3
      2290137.73     13333296.86      2290487.72     13333546.85
      2290887.72     13335946.85
#Sta/Elev= 30
  4574.2  248.14  4783.1  237.26  4869.1   231.1  4881.4  228.94  4896.2   229.2
  4904.8  227.56  4955.1  223.67  4990.8  220.57  4993.9   218.2  4996.7   217.7
  4999.9   218.2  5006.8  218.74  5024.6  224.06  5037.3  222.82  5136.1  223.87
  5207.1  226.88  5247.6  224.92  5328.7  225.24  5683.5  235.21  5706.4  234.56
  5724.1  236.56  5888.8  240.54  6066.4  240.28    6108  240.32  6362.8   239.1
    6525  240.83  6778.4  238.04  7314.9  245.03  7415.5  246.37  7437.4  246.46
#Mann= 7 ,-1 , 0
  4574.2      .1       0  4993.9     .07       0  4999.9      .1       0
  6066.4     .05       0    6108      .1       0  7314.9     .05       0
  7415.5      .1       0
Bank Sta=4955.1,5024.6
XS Rating Curve= 0 ,0
Exp/Cntr=0.3,0.1

Type RM Length L Ch R = 1 ,61512   ,376,376,376
BEGIN DESCRIPTION:
UNT003 IN NURI 85.0
END DESCRIPTION:
XS GIS Cut Line= 3
      2290037.72      13333346.9      2290087.72     13333896.85
      2290887.71     13336296.81
#Sta/Elev= 30
    4436   247.3  4763.6  232.62  4797.4  229.81  4969.5  222.06  4978.2  222.53
  4990.9  220.94  4995.8  216.32  4998.5  215.82  5001.8  216.32  5009.3  216.47
  5040.9  223.25  5072.5  222.02  5083.1  222.92  5104.2   221.5  5146.3  224.57
  5293.9  224.21  5378.2  226.96  5388.8  228.26  5757.7  237.75  5915.7  237.13
  6065.6  238.15  6315.9  237.51  6481.9  238.13  6634.8  239.51  6891.9   244.6
  7002.7  245.84  7017.4  246.31  7122.5   246.7    7288  248.65    7518  251.85
#Mann= 15 ,-1 , 0
    4436      .1       0  4763.6     .05       0  4969.5      .1       0
  4995.8     .07       0  5001.8      .1       0  5915.7     .05       0
  6065.6      .1       0  6315.9     .16       0  6481.9      .1       0
  6634.8     .05       0  6891.9      .1       0  7002.7     .05       0
  7017.4      .1       0  7122.5     .05       0    7288      .1       0
Bank Sta=4978.2,5040.9
XS Rating Curve= 0 ,0
Exp/Cntr=0.3,0.1

Type RM Length L Ch R = 1 ,61136   ,548,548,548
BEGIN DESCRIPTION:
Mapping XS dbf58059
END DESCRIPTION:
XS GIS Cut Line= 4
      2289971.25      13333338.7      2289757.71     13334005.35
      2290117.09     13334645.98      2290720.97     13336332.67
#Sta/Elev= 30
  4078.4  247.85    4486  232.12    4687     227    4791   225.4  4905.9   221.2
  4940.7  223.38  4995.4  215.43  4998.1  214.93  5001.4  215.43  5008.6  216.01
  5014.3  222.01    5052  220.76  5079.4  223.43  5182.1  223.13  5529.7  230.62
  5647.5     230  5772.3  232.21  6087.5  238.95    6226  239.84    6332  241.17
    6438   240.7  6543.9  241.95  6861.9  245.35  6967.9   246.3  7003.2  246.75
  7073.8  247.94  7179.8   249.1  7272.4  250.59  7285.8  250.98  7304.5  251.23
#Mann= 17 ,-1 , 0
  4078.4      .1       0    4687     .08       0    4791      .1       0
  4995.4     .07       0  5001.4      .1       0  5772.3     .05       0
    6226     .16       0    6332      .1       0    6438     .16       0
  6543.9      .1       0  6861.9     .08       0  6967.9     .05       0
  7003.2     .08       0  7073.8     .05       0  7179.8      .1       0
  7272.4     .08       0  7285.8      .1       0
Bank Sta=4940.7,5079.4
XS Rating Curve= 0 ,0
Exp/Cntr=0.3,0.1

Type RM Length L Ch R = 1 ,60588   ,747,747,747
BEGIN DESCRIPTION:
Mapping XS d0d2b349
END DESCRIPTION:
XS GIS Cut Line= 3
      2289950.43     13333312.62      2289387.92     13334312.65
      2290190.01      13336406.4
#Sta/Elev= 30
  3558.7  247.94  3609.4   247.7  3674.5  243.95  3960.7  235.12  4470.5  226.55
    4482  226.23  4581.9  225.87  4693.3   223.4  4881.9   220.9  4892.6     219
  4956.9  220.36    4972  219.93    4999  213.33  5001.8  212.83    5005  213.33
  5010.4  217.55  5032.1  220.88  5136.2  223.49  5330.4  222.95  5499.9  225.18
  5792.2  236.72  6190.8  239.48  6250.9  239.67  6297.7  239.77  6505.8  241.58
  6511.6  241.67  6618.5  243.33  6725.5  244.83    6864  247.74  6948.2  248.57
#Mann= 15 ,-1 , 0
  3558.7      .1       0  4470.5     .08       0    4482      .1       0
  4581.9     .08       0  4693.3      .1       0    4999     .07       0
    5005      .1       0  6190.8     .05       0  6250.9      .1       0
  6297.7     .05       0  6505.8     .16       0  6511.6     .05       0
  6618.5      .1       0  6725.5     .05       0    6864      .1       0
Bank Sta=4956.9,5032.1
XS Rating Curve= 0 ,0
Exp/Cntr=0.3,0.1

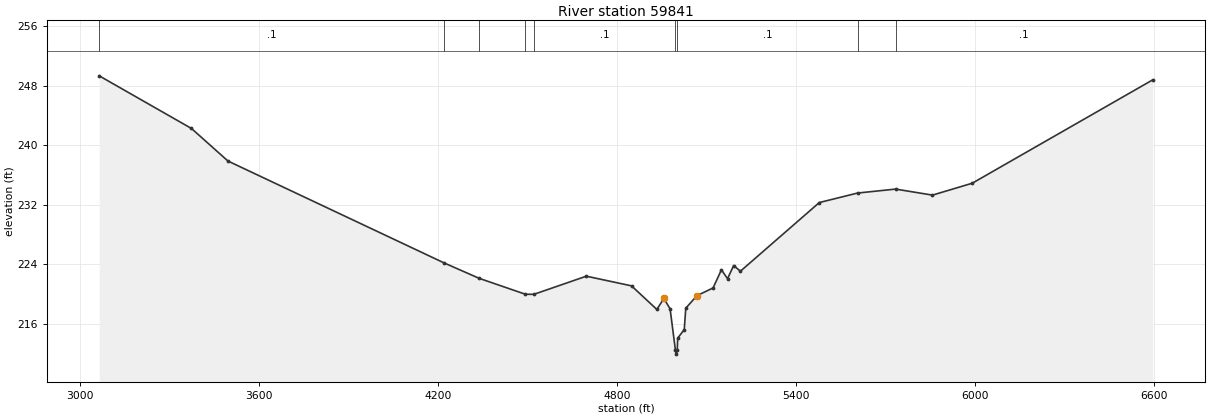
Type RM Length L Ch R = 1 ,59841   ,570,570,570
BEGIN DESCRIPTION:
UNT003 IN NURI 84.0
END DESCRIPTION:
XS GIS Cut Line= 3
      2289937.71     13333246.86      2288837.72     13334846.85
      2289187.73     13336396.89
#Sta/Elev= 30
  3063.6  249.36  3372.8  242.28  3495.2   237.9  4219.6   224.2    4337  222.13
    4492  219.99  4520.2  219.98  4696.1  222.42  4847.5  221.12  4932.4  217.95
  4955.9  219.42  4976.8  218.03  4994.8  212.44  4997.5  211.94  5000.8  212.44
  5002.2  214.08  5024.3  215.25  5029.4  218.12  5066.7   219.8  5120.9  220.84
  5148.8  223.28  5169.3  222.08  5189.8  223.85  5212.5  223.09  5476.8  232.32
  5605.2   233.6  5732.6  234.13  5856.1  233.32  5989.4  234.92  6594.3  248.82
#Mann= 9 ,-1 , 0
  3063.6      .1       0  4219.6     .08       0    4337      .1       0
    4492     .05       0  4520.2      .1       0  4994.8     .07       0
  5000.8      .1       0  5605.2     .08       0  5732.6      .1       0
Bank Sta=4955.9,5066.7
XS Rating Curve= 0 ,0
Exp/Cntr=0.3,0.1