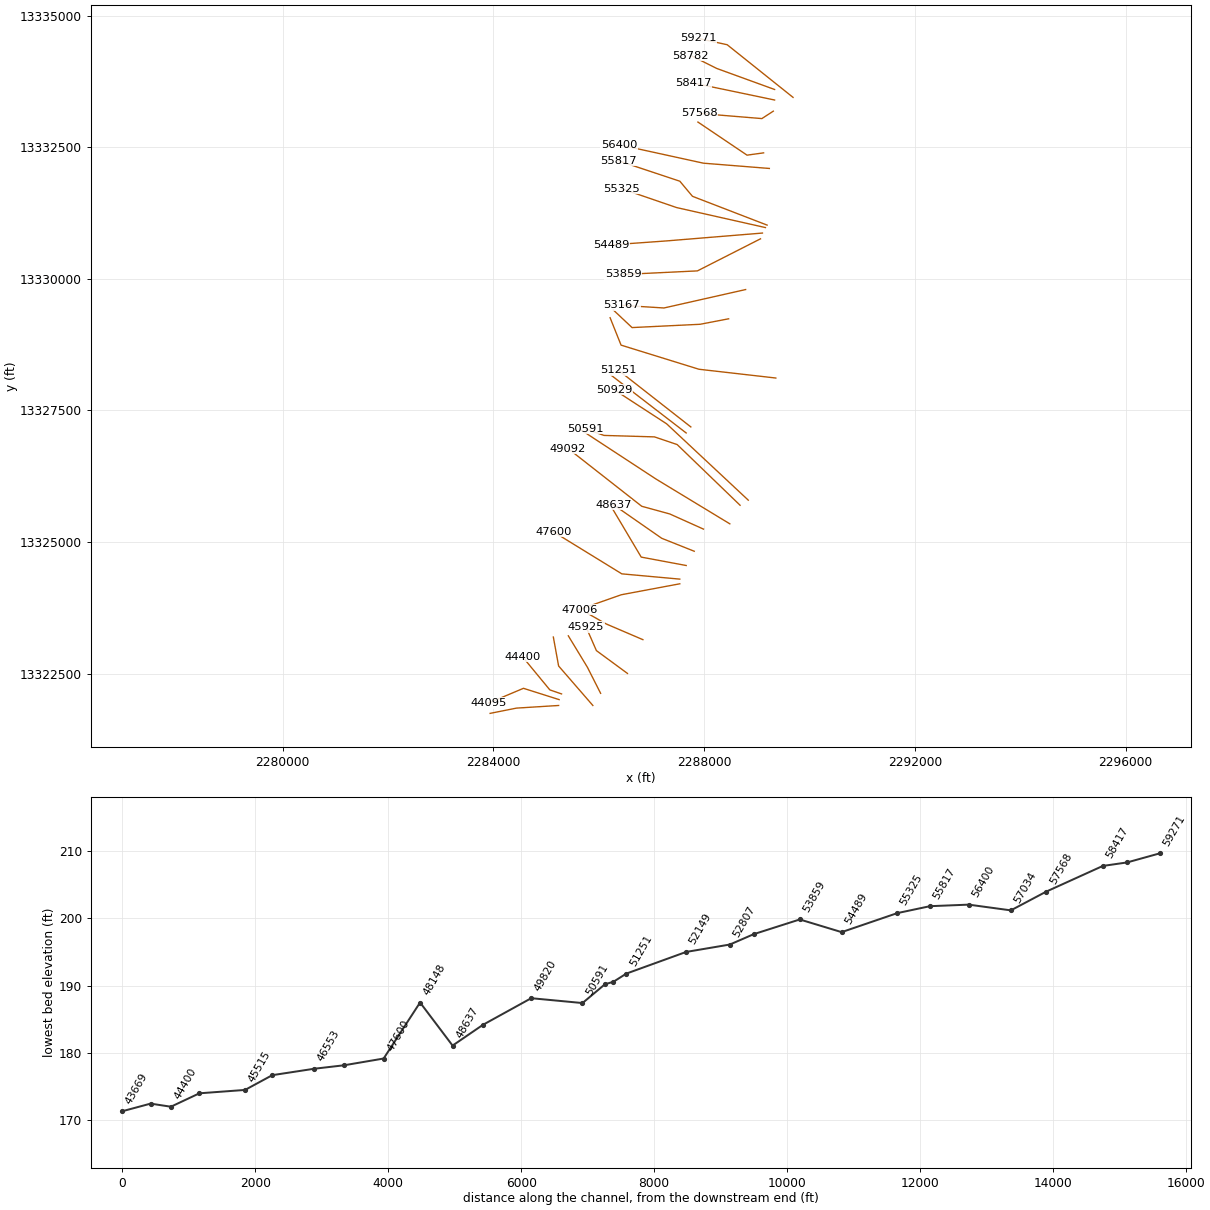
HEC-RAS study UNT003 IN NURI.prj: UNT003 IN NURI Base Level Engineering

--- UNT003 IN NURI.g01 (geometry) --- (continued)

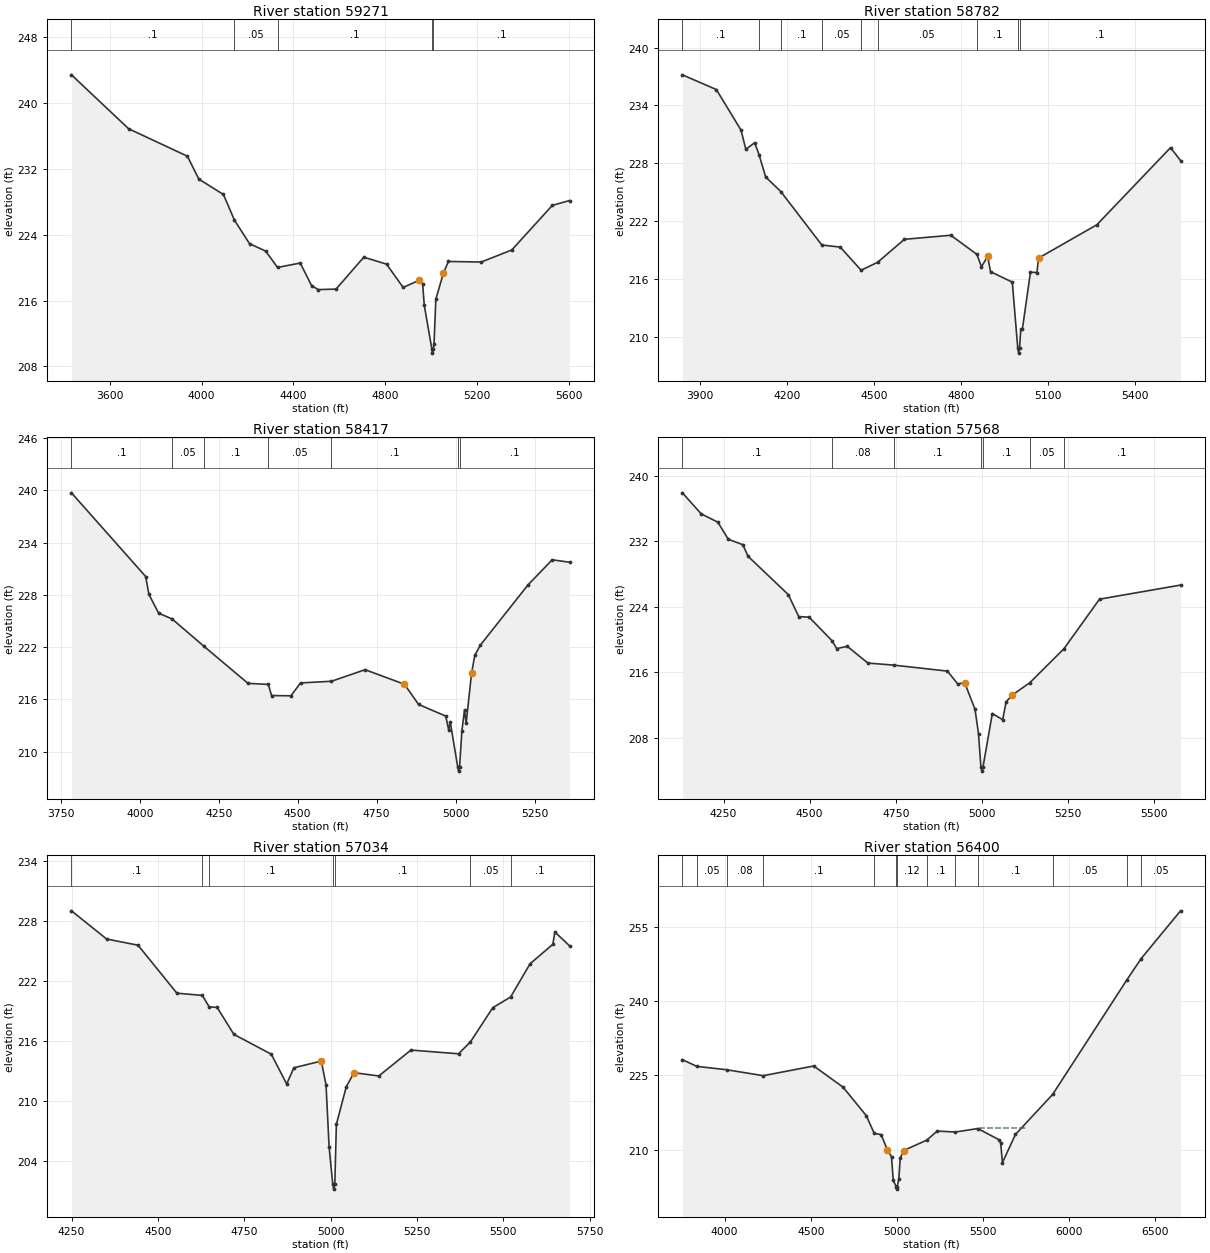
Type RM Length L Ch R = 1 ,59271   ,489,489,489
BEGIN DESCRIPTION:
UNT003 IN NURI 83.0
END DESCRIPTION:
XS GIS Cut Line= 3
      2289687.71     13333446.87      2288437.72     13334446.85
      2287882.22     13334568.37
#Sta/Elev= 30
  3432.9  243.44  3681.8  236.89  3937.9  233.55  3987.6  230.77  4094.8   228.9
  4142.7  225.79  4208.5  222.92  4278.9  222.02  4330.6  220.03  4429.4  220.57
    4479  217.82  4507.8  217.34  4585.4   217.4  4706.3  221.28  4805.6  220.43
  4877.6   217.6    4948  218.48  4962.4  218.07  4969.6  215.46  5002.7  210.12
  5005.4  209.62  5008.7  210.12  5012.1  210.71  5020.1  216.19    5053  219.33
  5074.6  220.76  5217.9  220.69    5351  222.16  5527.6  227.58  5602.3  228.16
#Mann= 5 ,-1 , 0
  3432.9      .1       0  4142.7     .05       0  4330.6      .1       0
  5002.7     .07       0  5008.7      .1       0
Bank Sta=4948,5053
XS Rating Curve= 0 ,0
Exp/Cntr=0.3,0.1

Type RM Length L Ch R = 1 ,58782   ,365,365,365
BEGIN DESCRIPTION:
UNT003 IN NURI 82.0
END DESCRIPTION:
XS GIS Cut Line= 3
      2289337.77     13333596.84      2288237.72     13333996.85
      2287746.97     13334242.23
#Sta/Elev= 30
  3838.8  237.18  3955.9  235.65    4041  231.44  4057.6  229.45  4088.2  230.13
  4103.6  228.85  4126.1  226.57  4178.4  225.06  4319.8  219.51  4383.5  219.29
  4455.5  216.89  4512.4  217.71    4605   220.1  4765.2  220.52  4855.3  218.53
    4871  217.25  4892.3  218.33  4902.2  216.74  4977.4  215.65  4996.3  208.78
  4999.1  208.28  5002.3  208.78  5006.7  210.76  5012.1  210.76  5040.1  216.69
  5062.4  216.65    5068  218.15  5269.3  221.61  5523.6  229.62    5558  228.28
#Mann= 9 ,-1 , 0
  3838.8      .1       0  4103.6     .05       0  4178.4      .1       0
  4319.8     .05       0  4455.5      .1       0  4512.4     .05       0
  4855.3      .1       0  4996.3     .07       0  5002.3      .1       0
Bank Sta=4892.3,5068
XS Rating Curve= 0 ,0
Exp/Cntr=0.3,0.1

Type RM Length L Ch R = 1 ,58417   ,849,849,849
BEGIN DESCRIPTION:
UNT003 IN NURI 81.0
END DESCRIPTION:
XS GIS Cut Line= 3
      2289337.73     13333396.85      2288471.26     13333578.27
      2287794.02     13333718.69
#Sta/Elev= 30
  3783.9  239.72  4018.9  230.11  4029.1  228.07  4059.8   225.9  4102.4  225.24
  4203.3   222.1  4342.9  217.84  4407.2  217.72  4417.4  216.44  4478.7  216.41
  4509.3  217.89  4607.2  218.08  4713.6  219.41  4837.9  217.74    4883  215.42
  4968.9  214.08  4978.2  212.51  4983.3  213.38  5006.8  208.26  5009.5  207.76
  5012.8  208.26    5020  212.36  5028.4  214.81  5033.5  213.26  5050.6  218.98
  5060.9  221.06  5078.5  222.23    5229  229.13    5306  232.03  5360.8  231.75
#Mann= 7 ,-1 , 0
  3783.9      .1       0  4102.4     .05       0  4203.3      .1       0
  4407.2     .05       0  4607.2      .1       0  5006.8     .07       0
  5012.8      .1       0
Bank Sta=4837.9,5050.6
XS Rating Curve= 0 ,0
Exp/Cntr=0.3,0.1

Type RM Length L Ch R = 1 ,57568   ,534,534,534
BEGIN DESCRIPTION:
UNT003 IN NURI 80.0
END DESCRIPTION:
XS GIS Cut Line= 3
      2289313.15     13333185.18      2289096.16     13333044.14
      2287913.38      13333141.8
#Sta/Elev= 30
  4130.7  237.93  4184.9  235.37  4233.5  234.35  4263.8  232.26    4306   231.6
  4321.2  230.18  4438.1   225.5  4468.2  222.82  4498.3  222.76  4564.3   219.9
  4578.6  218.92  4609.2  219.19  4668.9  217.15    4744   216.9  4899.7  216.17
  4929.8   214.6  4949.8  214.75  4979.9  211.51    4990  208.53    4997  204.46
  4999.8  203.96    5003  204.46  5030.1  210.99  5060.2  210.24  5070.2  212.43
  5088.1  213.25  5139.2  214.76    5238   218.9  5341.2  224.95  5576.3  226.67
#Mann= 7 ,-1 , 0
  4130.7      .1       0  4564.3     .08       0    4744      .1       0
    4997     .07       0    5003      .1       0  5139.2     .05       0
    5238      .1       0
Bank Sta=4949.8,5088.1
XS Rating Curve= 0 ,0
Exp/Cntr=0.3,0.1

Type RM Length L Ch R = 1 ,57034   ,634,634,634
BEGIN DESCRIPTION:
UNT003 IN NURI 79.0
END DESCRIPTION:
XS GIS Cut Line= 3
      2289128.67     13332393.09      2288814.04     13332349.69
      2287881.84     13332978.39
#Sta/Elev= 30
  4249.5  229.01  4351.4  226.19  4442.3  225.57  4554.8  220.77  4628.5  220.55
  4648.2   219.4  4671.2  219.35  4719.8  216.65    4828  214.67  4872.6  211.69
  4893.6  213.31  4972.8  213.98  4986.6  211.59  4995.5  205.39    5006  201.67
  5008.7  201.17    5012  201.67  5016.5  207.65  5045.1   211.4  5067.5  212.82
  5139.4  212.49  5232.4  215.08  5370.3  214.71  5404.7   215.9  5469.3  219.32
    5521  220.39  5577.2  223.71  5643.1  225.66  5649.2  226.89  5691.5  225.51
#Mann= 7 ,-1 , 0
  4249.5      .1       0  4628.5     .08       0  4648.2      .1       0
    5006     .07       0    5012      .1       0  5404.7     .05       0
    5521      .1       0
Bank Sta=4972.8,5067.5
XS Rating Curve= 0 ,0
Exp/Cntr=0.3,0.1

Type RM Length L Ch R = 1 ,56400   ,583,583,583
BEGIN DESCRIPTION:
UNT003 IN NURI 78.0
END DESCRIPTION:
XS GIS Cut Line= 3
      2289237.72     13332096.86      2287987.72     13332196.85
      2286387.74     13332546.85
#Sta/Elev= 30
  3754.9  228.18  3838.1  226.82  4012.6  226.14  4223.6  224.94  4517.3   226.9
  4687.9  222.61    4822  216.88  4868.6  213.28  4908.6  213.04  4944.9  209.94
  4968.8  208.55  4978.8  203.82  4995.9  202.52  4998.6  202.02  5001.9  202.52
  5011.4   204.1  5019.1  208.24  5039.6  209.82  5173.2  211.92  5234.1  213.75
  5339.5  213.56  5469.9  214.26  5595.7  211.95  5602.6   211.4  5612.8  207.38
  5688.5  213.07    5905  221.19  6336.4  244.36  6418.2   248.6  6646.7  258.25
#Mann= 13 ,-1 , 0
  3754.9      .1       0  3838.1     .05       0  4012.6     .08       0
  4223.6      .1       0  4868.6     .12       0  4995.9     .07       0
  5001.9     .12       0  5173.2      .1       0  5339.5     .05       0
  5469.9      .1       0    5905     .05       0  6336.4      .1       0
  6418.2     .05       0
#XS Ineff= 1 ,-1
 5479.84 5755.69  214.31
Permanent Ineff=
       F
Bank Sta=4944.9,5039.6
XS Rating Curve= 0 ,0
Exp/Cntr=0.3,0.1

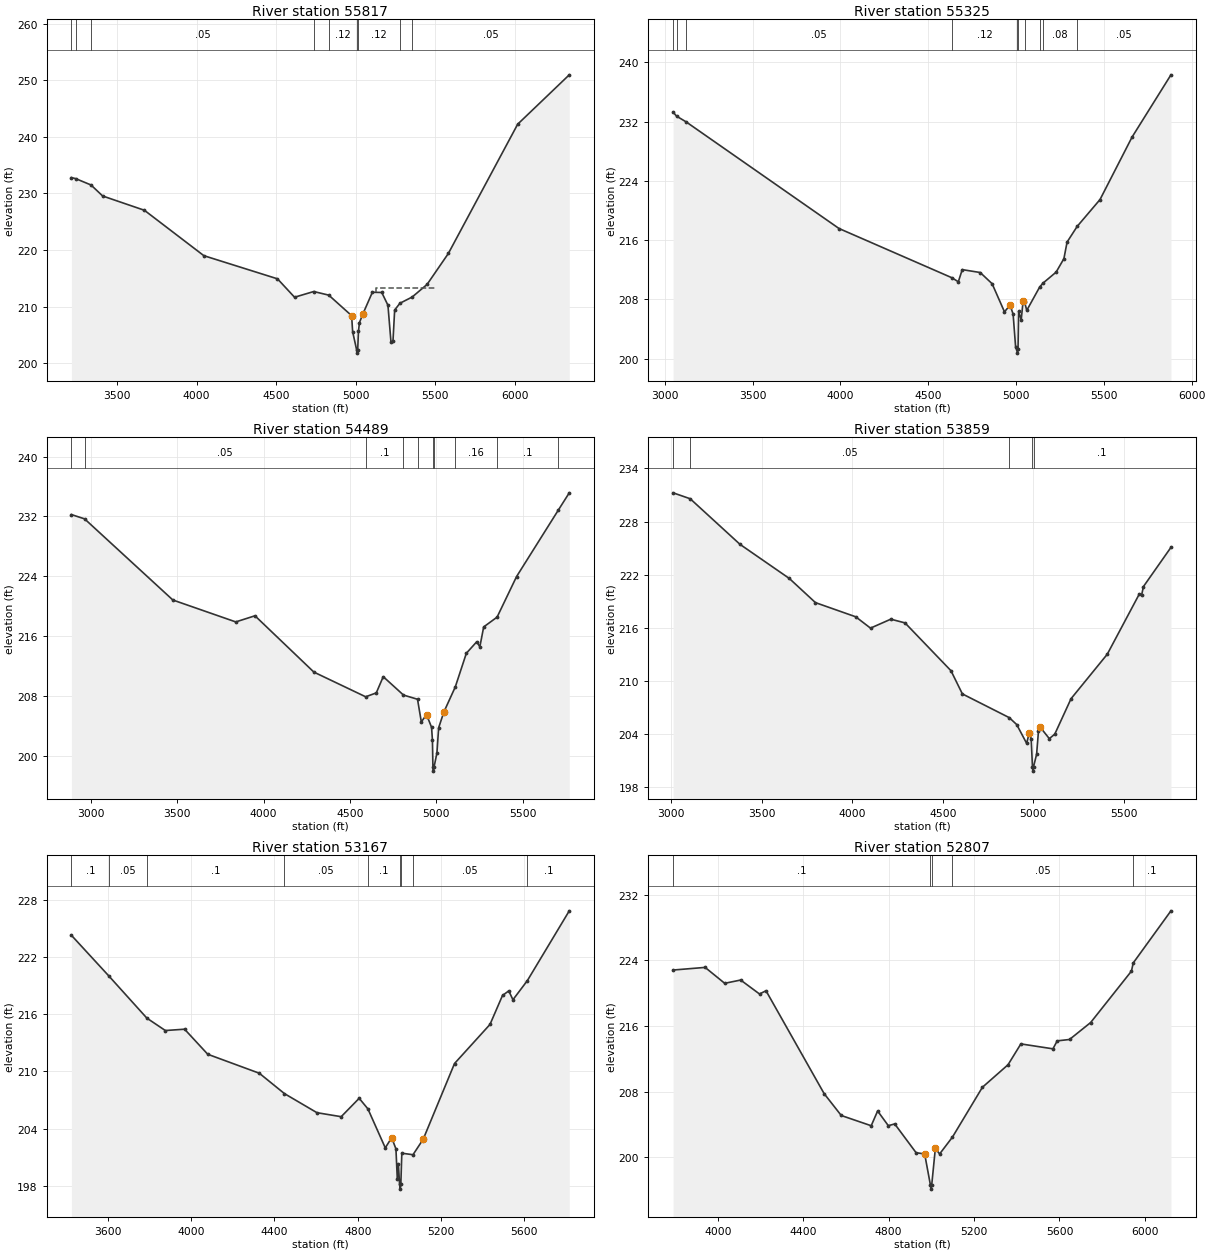
Type RM Length L Ch R = 1 ,55817   ,492,492,492
BEGIN DESCRIPTION:
Mapping XS 22930f16
END DESCRIPTION:
XS GIS Cut Line= 4
      2289195.23     13331020.97      2287778.55     13331567.85
      2287538.96     13331854.31      2286367.07     13332244.94
#Sta/Elev= 30
    3214  232.79  3240.6  232.61  3336.8  231.49  3410.2  229.54  3672.3  227.02
  4045.8     219  4508.4  214.91  4615.6  211.66  4736.1  212.67  4830.5  212.03
    4974  208.41  4980.5  205.58  5006.1  202.29  5008.8  201.79  5012.1  202.29
  5016.9  205.63  5023.4  207.19  5044.2  208.67  5104.4  212.54  5163.4   212.5
  5202.2  210.25  5221.4  203.71  5233.8  203.88  5244.4   209.4  5277.6   210.6
  5354.5   211.7    5448  213.92  5581.7  219.39  6017.2  242.22  6341.3  250.94
#Mann= 9 ,-1 , 0
    3214     .05       0  3240.6      .1       0  3336.8     .05       0
  4736.1      .1       0  4830.5     .12       0  5006.1     .07       0
  5012.1     .12       0  5277.6     .08       0  5354.5     .05       0
#XS Ineff= 1 ,-1
 5130.08 5501.95  213.28
Permanent Ineff=
       F
Bank Sta=4974,5044.2
XS Rating Curve= 0 ,0
Exp/Cntr=0.3,0.1

Type RM Length L Ch R = 1 ,55325   ,836,836,836
BEGIN DESCRIPTION:
Mapping XS 5f017252
END DESCRIPTION:
XS GIS Cut Line= 3
      2289163.94     13330974.11      2287476.46     13331354.31
      2286431.12     13331713.16
#Sta/Elev= 30
  3047.1  233.29  3066.8  232.74  3120.6  231.98  3991.8  217.58    4634  210.94
  4671.3  210.39  4693.6  212.03  4795.8  211.64  4863.6  210.13  4934.1  206.33
  4965.9  207.24  4983.3  206.02  4997.6  201.55  5005.2  201.26  5007.9  200.76
  5011.2  201.26  5014.6  206.43  5029.3  205.24  5039.9  207.74  5048.6  207.65
    5061  206.53  5134.2  209.67  5153.5  210.21  5228.1  211.69  5272.5  213.51
  5290.6  215.75    5348  217.86  5478.2  221.49  5660.4  229.91  5882.1  238.32
#Mann= 10 ,-1 , 0
  3047.1     .05       0  3066.8      .1       0  3120.6     .05       0
    4634     .12       0  5005.2     .07       0  5011.2     .12       0
  5048.6     .16       0  5134.2     .12       0  5153.5     .08       0
    5348     .05       0
Bank Sta=4965.9,5039.9
XS Rating Curve= 0 ,0
Exp/Cntr=0.3,0.1

Type RM Length L Ch R = 1 ,54489   ,630,630,630
BEGIN DESCRIPTION:
UNT003 IN NURI 77.0
END DESCRIPTION:
XS GIS Cut Line= 3
      2289106.64     13330869.94      2287290.17       13330721.
      2286233.47     13330644.86
#Sta/Elev= 30
  2887.9  232.24    2964  231.67    3475  220.82  3839.2  217.89  3950.4  218.71
  4291.5  211.18  4591.2  207.88  4652.7   208.4  4692.9  210.57  4810.1  208.11
  4891.4  207.55  4913.4  204.52  4943.5   205.5  4972.7   203.8  4977.7   202.1
  4980.6  198.44  4983.4  197.94  4986.6  198.44  5003.7  200.36  5013.7  203.74
  5043.8  205.84  5109.9  209.19  5174.1   213.7  5234.3  215.24  5252.2  214.56
  5274.4  217.22    5352  218.53  5464.9  223.96  5707.3  232.87  5769.9  235.15
#Mann= 10 ,-1 , 0
  2887.9      .1       0    2964     .05       0  4591.2      .1       0
  4810.1     .12       0  4891.4      .1       0  4980.6     .07       0
  4986.6      .1       0  5109.9     .16       0    5352      .1       0
  5707.3     .05       0
Bank Sta=4943.5,5043.8
XS Rating Curve= 0 ,0
Exp/Cntr=0.3,0.1

Type RM Length L Ch R = 1 ,53859   ,692,692,692
BEGIN DESCRIPTION:
UNT003 IN NURI 76.0
END DESCRIPTION:
XS GIS Cut Line= 3
      2289070.21     13330760.56       2287872.3     13330151.19
      2286466.03     13330083.48
#Sta/Elev= 30
  3009.6  231.25  3104.1  230.58  3379.4  225.43  3651.9  221.58  3796.4  218.85
  4018.9  217.25  4100.7  215.97  4212.9  216.98  4291.5  216.56  4545.5  211.16
  4608.5  208.54  4867.7  205.86  4908.8  205.08  4963.7  202.96  4978.9  204.17
  4988.9  203.45  4995.9  200.32  4998.7  199.82  5001.9  200.32  5018.9  201.73
    5029   204.3    5039  204.78    5089  203.49  5119.1  203.99  5209.2     208
  5409.4  213.02    5586   219.8  5599.6  219.74  5609.6  220.67  5761.5  225.09
#Mann= 5 ,-1 , 0
  3009.6      .1       0  3104.1     .05       0  4867.7      .1       0
  4995.9     .07       0  5001.9      .1       0
Bank Sta=4978.9,5039
XS Rating Curve= 0 ,0
Exp/Cntr=0.3,0.1

Type RM Length L Ch R = 1 ,53167   ,360,360,360
BEGIN DESCRIPTION:
UNT003 IN NURI 75.0
END DESCRIPTION:
XS GIS Cut Line= 3
      2288787.68     13329796.85      2287237.72     13329446.85
      2286437.76     13329496.85
#Sta/Elev= 30
  3425.2  224.27  3606.7  219.96  3787.5  215.58  3876.2  214.28  3968.5  214.42
  4079.8  211.79  4327.3   209.8  4448.2  207.66  4604.1  205.66  4720.5  205.24
  4806.9  207.17  4848.8  206.06  4932.2  201.97  4962.9  203.04  4983.4  201.86
    4990  198.68  4995.1  200.26  5000.9  198.14  5003.7  197.64  5006.9  198.14
  5011.6  201.41  5065.3  201.25  5114.4  202.88  5264.7  210.82    5435  214.92
  5495.1  217.96  5525.2  218.44  5545.2  217.51  5614.5  219.52  5815.7  226.84
#Mann= 9 ,-1 , 0
  3425.2      .1       0  3606.7     .05       0  3787.5      .1       0
  4448.2     .05       0  4848.8      .1       0  5000.9     .07       0
  5006.9      .1       0  5065.3     .05       0  5614.5      .1       0
Bank Sta=4962.9,5114.4
XS Rating Curve= 0 ,0
Exp/Cntr=0.3,0.1

Type RM Length L Ch R = 1 ,52807   ,658,658,658
BEGIN DESCRIPTION:
UNT003 IN NURI 74.0
END DESCRIPTION:
XS GIS Cut Line= 4
      2288464.93     13329241.28      2287923.23      13329137.1
      2286631.56      13329074.6      2286277.37     13329407.96
#Sta/Elev= 30
  3790.8  222.82  3940.7  223.14  4032.4   221.2  4107.1   221.6  4195.3   219.9
  4225.8  220.29  4498.1  207.74  4578.2  205.08  4718.4  203.83  4748.4  205.63
  4798.5  203.84  4828.5  204.05  4928.6  200.54  4968.7  200.39  4995.7   196.6
  4998.5   196.1  5001.7   196.6  5018.7  201.06  5038.8  200.39  5098.9  202.45
    5239  208.52  5359.1  211.27  5419.2  213.81  5569.4  213.21  5589.4  214.18
    5647  214.35  5746.1  216.42  5937.1  222.69  5945.2  223.68    6122  230.04
#Mann= 5 ,-1 , 0
  3790.8      .1       0  4995.7     .07       0  5001.7      .1       0
  5098.9     .05       0  5945.2      .1       0
Bank Sta=4968.7,5018.7
XS Rating Curve= 0 ,0
Exp/Cntr=0.3,0.1

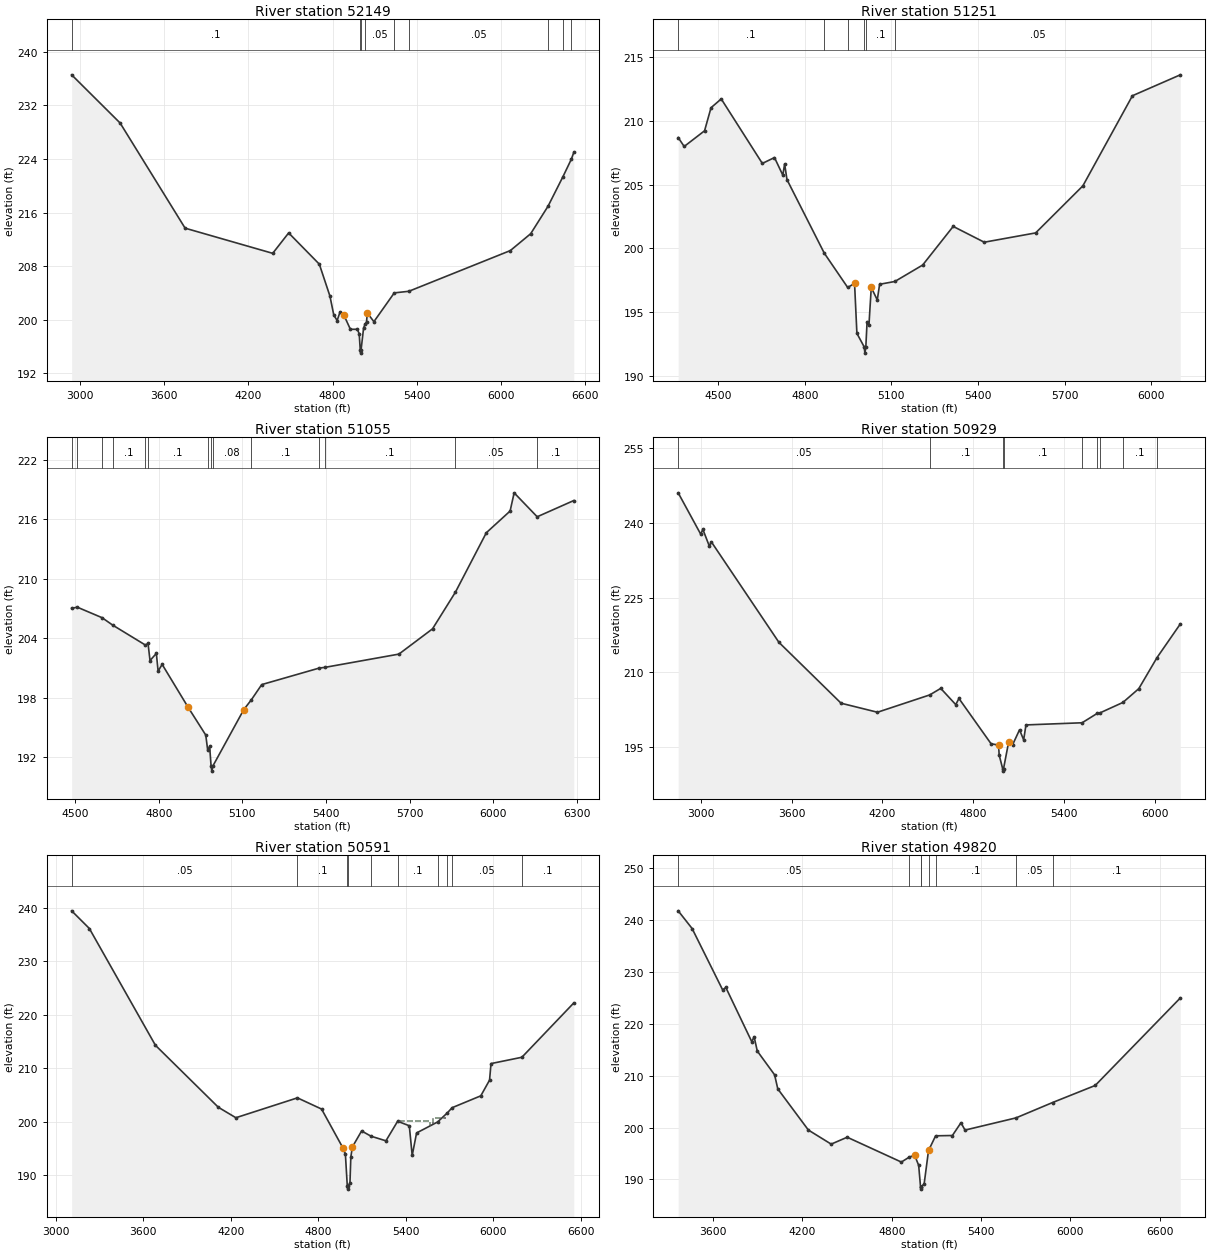
Type RM Length L Ch R = 1 ,52149   ,898,898,898
BEGIN DESCRIPTION:
UNT003 IN NURI 73.0
END DESCRIPTION:
XS GIS Cut Line= 4
      2289360.77     13328116.27       2287902.4     13328282.94
      2286423.23     13328741.27      2286214.96     13329261.94
#Sta/Elev= 30
  2941.2  236.58  3286.5  229.38  3749.5  213.67  4373.5  209.91  4487.2  212.96
  4705.7  208.29  4781.3  203.52  4808.7  200.69  4832.7  199.87  4853.7  201.18
  4879.1  200.75    4927  198.56  4976.9  198.56  4989.8  197.88  4997.2   195.5
    5000     195  5003.2   195.5  5021.2  198.78  5031.7   199.3  5042.1  199.69
  5047.4     201  5094.5   199.7  5239.6     204  5343.4  204.24  6066.3  210.32
  6211.4  212.84  6334.8  216.94    6441  221.35  6500.7  223.96  6518.4  224.98
#Mann= 9 ,-1 , 0
  2941.2      .1       0  4997.2     .07       0  5003.2      .1       0
  5031.7     .05       0  5239.6      .1       0  5343.4     .05       0
  6334.8      .1       0    6441     .05       0  6500.7      .1       0
Bank Sta=4879.1,5047.4
XS Rating Curve= 0 ,0
Exp/Cntr=0.3,0.1

Type RM Length L Ch R = 1 ,51251   ,196,196,196
BEGIN DESCRIPTION:
UNT003 IN NURI 72.0
END DESCRIPTION:
XS GIS Cut Line= 2
      2287747.32     13327187.63       2286377.5     13328260.56
#Sta/Elev= 30
  4361.3   208.7  4382.1     208  4452.7  209.23  4475.1  211.04  4510.5  211.73
  4652.9  206.67    4695  207.13  4723.9  205.75  4730.2  206.63  4738.3   205.4
  4867.6  199.63  4948.7  196.94  4972.5  197.26  4980.6  193.34  5005.6  192.29
  5008.4  191.79  5011.6  192.29  5015.9  194.26  5022.3  193.98  5030.4  196.94
  5051.2  195.96  5059.3  197.19  5112.1  197.41  5208.5   198.7  5314.3  201.73
  5421.9  200.49    5600  201.22  5763.6  204.91  5935.4  211.98  6101.3  213.62
#Mann= 6 ,-1 , 0
  4361.3      .1       0  4867.6     .08       0  4948.7      .1       0
  5005.6     .07       0  5011.6      .1       0  5112.1     .05       0
Bank Sta=4972.5,5030.4
XS Rating Curve= 0 ,0
Exp/Cntr=0.3,0.1

Type RM Length L Ch R = 1 ,51055   ,126,126,126
BEGIN DESCRIPTION:
Mapping XS 65221d82
END DESCRIPTION:
XS GIS Cut Line= 2
      2287658.76     13327073.06       2286232.3     13328171.54
#Sta/Elev= 30
  4487.7  207.01  4507.9  207.13  4596.6  206.07  4634.8  205.32  4752.4   203.3
  4761.6  203.47  4768.7  201.74  4791.4  202.46  4797.7  200.67  4812.2  201.35
  4905.5  197.01  4968.6  194.21  4975.6  192.66  4982.5  193.07  4987.7  191.07
  4990.4  190.57  4993.7  191.07  5104.8  196.78  5132.2  197.78  5169.2  199.31
  5375.5  200.98  5395.8  201.05  5661.1  202.39  5781.6  204.94  5863.6  208.64
  5974.6  214.65  6059.8  216.84  6074.3  218.68  6156.9  216.26  6288.1   217.9
#Mann= 14 ,-1 , 0
  4487.7     .08       0  4507.9      .1       0  4596.6     .08       0
  4634.8      .1       0  4752.4     .08       0  4761.6      .1       0
  4975.6     .08       0  4987.7     .07       0  4993.7     .08       0
  5132.2      .1       0  5375.5     .08       0  5395.8      .1       0
  5863.6     .05       0  6156.9      .1       0
Bank Sta=4905.5,5104.8
XS Rating Curve= 0 ,0
Exp/Cntr=0.3,0.1

Type RM Length L Ch R = 1 ,50929   ,338,338,338
BEGIN DESCRIPTION:
UNT003 IN NURI 71.0
END DESCRIPTION:
XS GIS Cut Line= 3
      2288837.75     13325796.83      2287287.72     13327246.85
      2286287.74     13327896.84
#Sta/Elev= 30
  2851.7  245.98  3000.5  237.69  3014.6  238.66  3057.1  235.32  3070.8  236.15
  3516.8  216.02  3927.2  203.82  4167.5  202.01  4512.4  205.48  4585.2  206.79
  4684.3  203.54  4705.3  204.77  4917.8  195.68  4967.2  195.45  4970.8  193.45
  4993.9  190.71  4996.7  190.21  4999.9  190.71  5033.2  195.99  5060.3  195.54
  5105.4  198.49  5132.7  196.48  5147.9  199.47  5518.5   199.9  5619.9  201.81
  5637.1  201.89  5787.7  203.97  5892.6  206.73  6013.3  212.97  6166.9   219.7
#Mann= 9 ,-1 , 0
  2851.7     .05       0  4512.4      .1       0  4993.9     .07       0
  4999.9      .1       0  5518.5     .05       0  5619.9      .1       0
  5637.1     .05       0  5787.7      .1       0  6013.3     .05       0
Bank Sta=4967.2,5033.2
XS Rating Curve= 0 ,0
Exp/Cntr=0.3,0.1

Type RM Length L Ch R = 1 ,50591   ,771,771,771
BEGIN DESCRIPTION:
UNT003 IN NURI 70.0
END DESCRIPTION:
XS GIS Cut Line= 5
      2288682.44      13325699.8      2287487.99     13326852.58
      2287057.44     13326998.42       2286099.1     13327026.19
      2285752.31     13327151.04
#Sta/Elev= 30
  3109.1  239.38  3230.5  236.08  3683.3  214.28  4114.7   202.7  4234.8  200.75
  4656.7  204.46  4822.2  202.37    4970  195.04  4985.4     194  4998.7  187.92
  5001.4  187.42  5004.7  187.92  5016.9  188.61  5022.8  193.41  5033.3  195.29
  5096.7  198.28  5161.2   197.3  5263.4  196.44  5343.6  200.09  5423.5  199.25
  5443.5  193.71  5473.5  197.91  5617.7  199.96  5684.2  201.65  5716.8  202.62
  5913.7  204.84  5973.7  207.77  5983.7  210.86  6195.3  212.04    6551  222.18
#Mann= 10 ,-1 , 0
  3109.1     .05       0  4656.7      .1       0  4998.7     .07       0
  5004.7      .1       0  5161.2     .05       0  5343.6      .1       0
  5617.7     .05       0  5684.2      .1       0  5716.8     .05       0
  6195.3      .1       0
#XS Ineff= 2 ,-1
  5362.3 5566.41  200.14 5584.96 5675.42  200.72
Permanent Ineff=
       F       F
Bank Sta=4970,5033.3
XS Rating Curve= 0 ,0
Exp/Cntr=0.3,0.1

Type RM Length L Ch R = 1 ,49820   ,728,728,728
BEGIN DESCRIPTION:
UNT003 IN NURI 69.0
END DESCRIPTION:
XS GIS Cut Line= 3
      2288487.76     13325346.83      2287087.72     13326196.85
       2285637.7     13327146.87
#Sta/Elev= 30
  3366.4   241.7    3460  238.29  3664.9  226.49  3686.3  226.95  3860.7   216.5
  3876.2  217.47  3897.5  214.71  4013.8  210.14  4035.2  207.43  4240.6  199.51
  4393.7   196.8  4501.2  198.13  4864.8  193.35  4918.5  194.31  4953.9  194.66
  4981.1  192.72  4993.5  188.64  4996.3  188.14  4999.5  188.64  5017.8  189.13
    5048  195.73  5050.7  195.77  5094.9   198.4  5207.5  198.46  5265.1  200.92
  5292.2   199.5  5634.6  201.85  5880.5  204.81  6166.4  208.09  6737.8  224.93
#Mann= 8 ,-1 , 0
  3366.4     .05       0  4918.5      .1       0  4993.5     .07       0
  4999.5      .1       0  5050.7     .05       0  5094.9      .1       0
  5634.6     .05       0  5880.5      .1       0
Bank Sta=4953.9,5048
XS Rating Curve= 0 ,0
Exp/Cntr=0.3,0.1

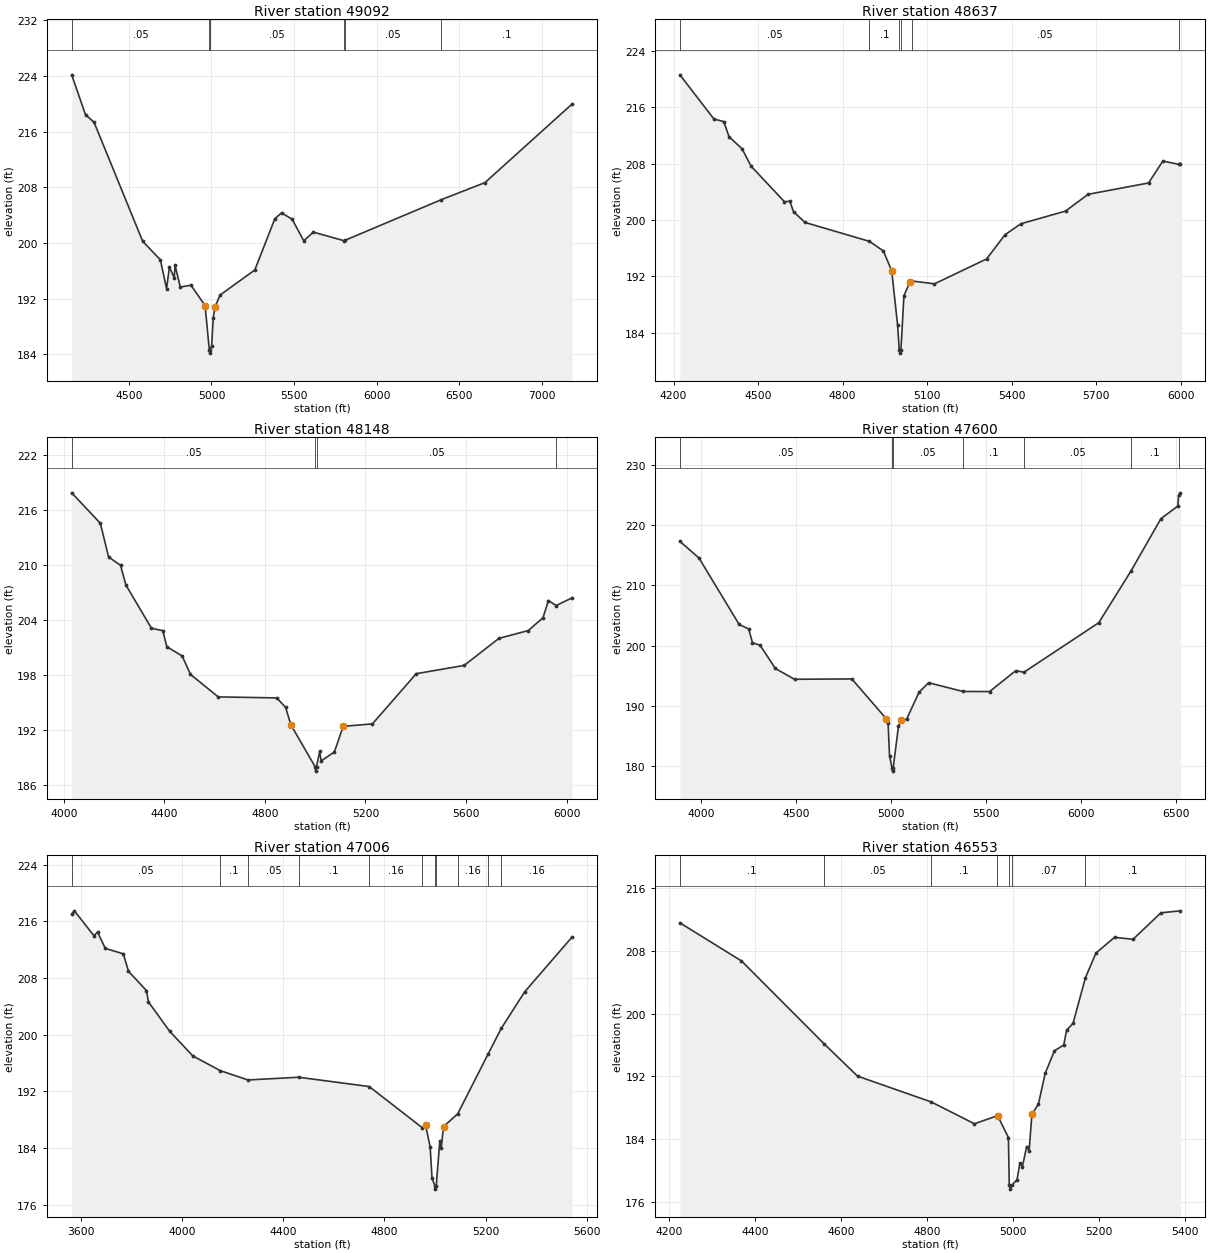
Type RM Length L Ch R = 1 ,49092   ,455,455,455
BEGIN DESCRIPTION:
UNT003 IN NURI 68.0
END DESCRIPTION:
XS GIS Cut Line= 4
      2287987.72     13325246.86      2287347.23     13325534.56
      2286815.98      13325680.4       2285416.7      13326777.6
#Sta/Elev= 30
  4153.4  224.15  4237.2  218.41    4289  217.33  4583.4  200.24  4690.6  197.58
  4727.9  193.45  4745.4  196.53  4774.2  195.02  4779.7  196.78  4811.2  193.67
  4875.8  193.94  4961.3  191.01  4986.8  184.68  4989.6  184.18  4992.8  184.68
  5000.9   185.2  5010.6  189.21    5021  190.79  5052.1  192.52  5262.7  196.13
  5383.9  203.49  5424.2  204.32  5488.3  203.42  5558.9  200.31  5616.7  201.56
  5802.1  200.33  5809.4  200.39    6390   206.2  6656.3  208.67  7184.6  219.97
#Mann= 6 ,-1 , 0
  4153.4     .05       0  4986.8     .03       0  4992.8     .05       0
  5802.1      .1       0  5809.4     .05       0    6390      .1       0
Bank Sta=4961.3,5021
XS Rating Curve= 0 ,0
Exp/Cntr=0.3,0.1

Type RM Length L Ch R = 1 ,48637   ,489,489,489
BEGIN DESCRIPTION:
UNT003 IN NURI 67.0
END DESCRIPTION:
XS GIS Cut Line= 3
      2287812.55     13324826.21      2287194.45     13325072.76
      2286281.97     13325707.68
#Sta/Elev= 30
  4222.3  220.59    4343  214.33  4378.2  213.95  4396.9   211.8  4442.8  210.11
  4475.1  207.63  4593.7  202.58  4612.5  202.66  4625.8  201.17  4666.5  199.65
    4895  196.97  4944.7  195.61  4974.4  192.79  4995.4  185.04  5001.1  181.61
  5003.9  181.11  5007.1  181.61  5017.8  189.25  5039.9  191.26  5044.7  191.35
  5126.3  190.94  5311.3  194.47  5376.8  197.91  5433.5  199.47  5591.5  201.26
  5671.8  203.64  5886.5  205.25  5937.1  208.36  5994.7  207.88  5999.4  208.01
#Mann= 6 ,-1 , 0
  4222.3     .05       0    4895      .1       0  5001.1     .07       0
  5007.1      .1       0  5044.7     .05       0  5994.7      .1       0
Bank Sta=4974.4,5039.9
XS Rating Curve= 0 ,0
Exp/Cntr=0.3,0.1

Type RM Length L Ch R = 1 ,48148   ,548,548,548
BEGIN DESCRIPTION:
UNT003 IN NURI 66.0
END DESCRIPTION:
XS GIS Cut Line= 3
      2287659.74      13324555.4      2286805.57     13324715.12
      2286232.69     13325680.34
#Sta/Elev= 30
  4031.1  217.83  4145.1  214.51  4177.9  210.84  4225.4  209.93  4246.8  207.78
  4348.5  203.07  4393.5  202.81  4409.6  201.06  4470.6  200.05  4503.8  198.04
  4614.2  195.59    4847  195.48  4882.5  194.44  4902.9  192.56  4999.3     188
    5002   187.5  5005.3     188  5017.9  189.64  5023.7  188.61  5076.3  189.59
  5111.4  192.38  5227.7  192.65  5402.1  198.12  5592.7  199.02    5731  201.97
    5848  202.82  5906.4  204.22  5927.9  206.09  5958.9  205.55  6022.5  206.39
#Mann= 4 ,-1 , 0
  4031.1     .05       0  4999.3     .03       0  5005.3     .05       0
  5958.9      .1       0
Bank Sta=4902.9,5111.4
XS Rating Curve= 0 ,0
Exp/Cntr=0.3,0.1

Type RM Length L Ch R = 1 ,47600   ,594,594,594
BEGIN DESCRIPTION:
UNT003 IN NURI 65.0
END DESCRIPTION:
XS GIS Cut Line= 3
       2287537.7     13324296.86      2286437.72     13324396.85
      2285137.68     13325196.88
#Sta/Elev= 30
  3890.7  217.32  3991.1  214.55    4202  203.54  4252.2  202.77  4272.2  200.51
  4312.4  200.07  4392.7  196.22  4493.2  194.43  4794.4  194.49  4975.1   187.9
  4985.2   187.1  4992.7  181.77  5005.8  179.69  5008.5  179.19  5011.8  179.69
  5039.6  186.63  5053.9  187.61  5082.2  187.79  5147.9  192.28  5198.1  193.86
  5378.3  192.41  5518.8  192.39  5656.1  195.86  5699.4   195.6  6092.7  203.82
  6261.8  212.39  6419.3  221.08  6508.1  223.17  6512.3  224.98  6521.7  225.37
#Mann= 7 ,-1 , 0
  3890.7     .05       0  5005.8     .03       0  5011.8     .05       0
  5378.3      .1       0  5699.4     .05       0  6261.8      .1       0
  6512.3     .05       0
Bank Sta=4975.1,5053.9
XS Rating Curve= 0 ,0
Exp/Cntr=0.3,0.1

Type RM Length L Ch R = 1 ,47006   ,453,453,453
BEGIN DESCRIPTION:
UNT003 IN NURI 64.0
END DESCRIPTION:
XS GIS Cut Line= 3
      2287538.17     13324208.17      2286427.09     13323999.84
      2285628.51      13323718.6
#Sta/Elev= 30
  3564.7  217.03  3575.3  217.47  3652.4  213.96  3666.9  214.46  3697.4  212.17
  3768.6   211.4    3789  208.94  3860.2  206.21  3867.8  204.62  3951.8  200.47
  4043.4  196.99  4151.6  194.91  4261.1   193.6  4461.6  193.98  4739.8  192.67
    4950  186.85  4962.4  187.23  4980.7  184.18  4988.1  179.76  4998.9  178.69
  5001.7  178.19  5004.9  178.69    5019  185.04  5024.3  183.99  5033.7  187.02
  5089.6  188.82  5209.1  197.22  5261.6  200.88  5354.2  206.04  5541.8  213.79
#Mann= 11 ,-1 , 0
  3564.7     .05       0  4151.6      .1       0  4261.1     .05       0
  4461.6      .1       0  4739.8     .16       0    4950      .1       0
  4998.9     .07       0  5004.9      .1       0  5089.6     .16       0
  5209.1      .1       0  5261.6     .16       0
Bank Sta=4962.4,5033.7
XS Rating Curve= 0 ,0
Exp/Cntr=0.3,0.1

Type RM Length L Ch R = 1 ,46553   ,628,628,628
BEGIN DESCRIPTION:
UNT003 IN NURI 63.0
END DESCRIPTION:
XS GIS Cut Line= 3
      2286837.74     13323146.85      2286137.72     13323446.85
      2285787.73     13323646.85
#Sta/Elev= 30
  4224.9  211.53  4368.2  206.69    4561  196.12  4638.3  192.04  4809.7  188.76
  4910.3  185.98  4961.9  186.97  4964.7  186.97  4989.4  184.23  4991.4  178.17
  4994.2  177.67  4997.4  178.17  5009.5  178.87    5016  180.97  5021.8  180.49
  5031.8  183.09  5037.6  182.58  5044.1  187.19  5059.2  188.48    5075   192.4
  5096.6  195.27  5118.2     196  5124.7  197.87  5139.8  198.75  5168.6  204.55
  5193.1  207.69  5236.3  209.69  5279.5  209.44  5344.3  212.81  5389.6  213.06
#Mann= 7 ,-1 , 0
  4224.9      .1       0    4561     .05       0  4809.7      .1       0
  4961.9     .07       0  4991.4     .07       0  4997.4     .07       0
  5168.6      .1       0
Bank Sta=4964.7,5044.1
XS Rating Curve= 0 ,0
Exp/Cntr=0.3,0.1

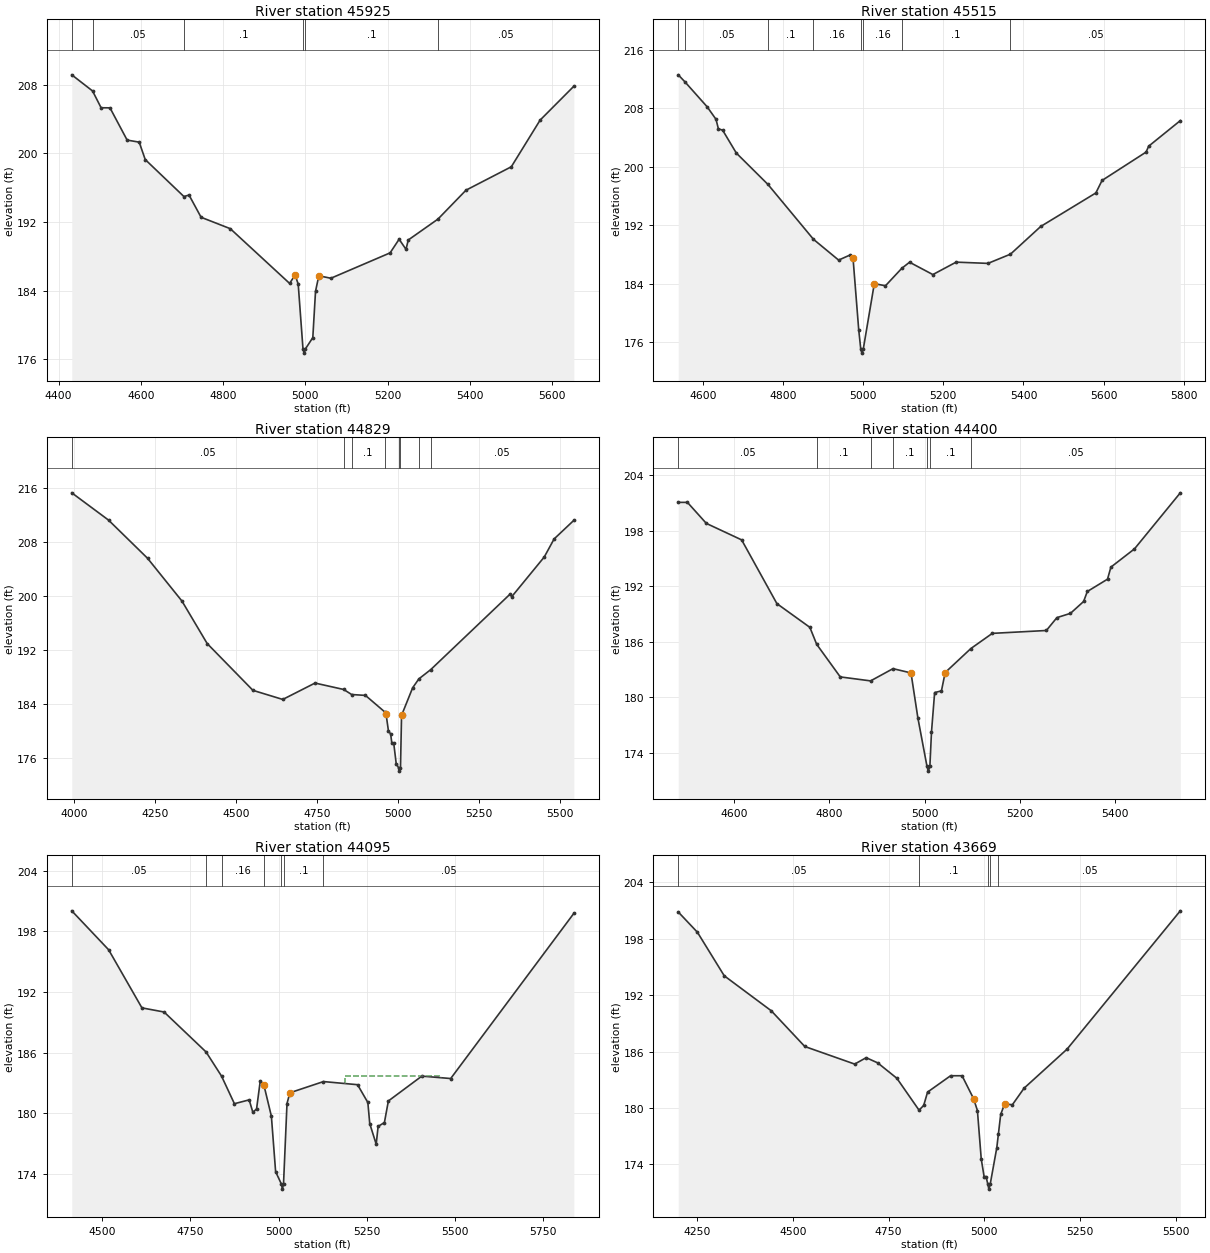
Type RM Length L Ch R = 1 ,45925   ,410,410,410
BEGIN DESCRIPTION:
UNT003 IN NURI 62.0
END DESCRIPTION:
XS GIS Cut Line= 3
      2286545.18     13322505.02      2285954.87     13322939.08
      2285759.55     13323386.16
#Sta/Elev= 30
  4432.1  209.17  4482.6  207.29  4503.4  205.33    4525  205.32  4566.7  201.56
    4596  201.32  4610.7  199.29  4704.7  194.98  4717.2  195.15  4746.5  192.56
  4817.5  191.23  4961.7  184.85  4975.1  185.83  4982.6  184.76  4994.2  177.22
    4997  176.72  5000.2  177.22  5018.1  178.53  5024.7  183.93  5032.7  185.74
    5062  185.45    5206  188.41  5227.9     190  5244.7  188.82  5250.1  189.91
  5322.4  192.35  5390.5  195.72  5500.7  198.45  5570.7  203.89  5652.7  207.84
#Mann= 6 ,-1 , 0
  4432.1      .1       0  4482.6     .05       0  4704.7      .1       0
  4994.2     .07       0  5000.2      .1       0  5322.4     .05       0
Bank Sta=4975.1,5032.7
XS Rating Curve= 0 ,0
Exp/Cntr=0.3,0.1

Type RM Length L Ch R = 1 ,45515   ,686,686,686
BEGIN DESCRIPTION:
UNT003 IN NURI 61.0
END DESCRIPTION:
XS GIS Cut Line= 3
      2286035.17     13322127.44      2285783.43     13322624.41
      2285421.85     13323219.83
#Sta/Elev= 30
    4538  212.58  4554.4  211.64    4610  208.22  4632.3   206.5  4638.2  205.21
    4649     205  4683.1  201.88  4762.1  197.59  4875.7  190.09  4938.5  187.25
  4966.4  187.93  4974.5   187.5  4988.7   177.7  4993.9  175.03  4996.7  174.53
  4999.9  175.03  5027.6  184.03  5055.5  183.74  5096.1  186.12  5115.6  186.96
  5173.8  185.27  5231.9  186.97  5311.4   186.8  5367.6  188.06  5443.2  191.85
  5580.8  196.43  5596.3  198.14  5706.3  202.02  5712.6  202.82  5791.7  206.32
#Mann= 8 ,-1 , 0
    4538      .1       0  4554.4     .05       0  4762.1      .1       0
  4875.7     .16       0  4993.9     .07       0  4999.9     .16       0
  5096.1      .1       0  5367.6     .05       0
Bank Sta=4974.5,5027.6
XS Rating Curve= 0 ,0
Exp/Cntr=0.3,0.1

Type RM Length L Ch R = 1 ,44829   ,429,429,429
BEGIN DESCRIPTION:
UNT003 IN NURI 60.0
END DESCRIPTION:
XS GIS Cut Line= 3
      2285887.71     13321896.86      2285237.72     13322646.85
      2285137.72     13323196.88
#Sta/Elev= 30
  3991.8   215.3  4105.3  211.26  4225.9   205.6  4332.3  199.25  4410.2  192.95
  4551.6  186.01  4643.8  184.66  4743.5  187.09  4831.9  186.14  4856.7  185.39
  4899.3  185.26  4959.2   182.8  4962.9  182.52  4970.5  179.96  4977.1  179.55
    4981  178.14  4986.8  178.14  4994.4  175.13  5001.6  174.53  5004.3  174.03
  5007.6  174.53  5010.9   182.3  5045.2  186.39  5064.4  187.71    5101  189.08
  5346.3  200.28  5351.4   199.9  5451.8  205.78  5482.3  208.46  5543.3  211.22
#Mann= 8 ,-1 , 0
  3991.8     .05       0  4831.9     .16       0  4856.7      .1       0
  4959.2     .16       0  5001.6     .07       0  5007.6     .16       0
  5064.4      .1       0    5101     .05       0
Bank Sta=4962.9,5010.9
XS Rating Curve= 0 ,0
Exp/Cntr=0.3,0.1

Type RM Length L Ch R = 1 ,44400   ,305,305,305
BEGIN DESCRIPTION:
UNT003 IN NURI 59.0
END DESCRIPTION:
XS GIS Cut Line= 3
      2285293.55     13322116.47      2285071.32     13322192.86
       2284550.5      13322824.8
#Sta/Elev= 30
  4482.9  201.05  4502.2  201.05  4541.9  198.78    4616     197    4690  190.12
  4759.2  187.56  4773.5  185.73    4823  182.21  4886.7  181.78  4933.7   183.1
  4971.5  182.64  4985.9  177.79  5005.1  172.54  5007.8  172.04  5011.1  172.54
  5014.5  176.26  5021.1  180.52  5035.4   180.7  5043.2  182.68  5097.1  185.27
  5142.2  186.91  5255.6  187.22  5277.8  188.61  5306.2  189.07  5333.8  190.35
  5341.6  191.43    5384  192.76  5391.1  194.06  5440.6  196.03  5536.8  202.08
#Mann= 7 ,-1 , 0
  4482.9     .05       0  4773.5      .1       0  4886.7     .16       0
  4933.7      .1       0  5005.1     .07       0  5011.1      .1       0
  5097.1     .05       0
Bank Sta=4971.5,5043.2
XS Rating Curve= 0 ,0
Exp/Cntr=0.3,0.1

Type RM Length L Ch R = 1 ,44095   ,426,426,426
BEGIN DESCRIPTION:
Mapping XS 078fedfe
END DESCRIPTION:
XS GIS Cut Line= 3
      2285247.37      13322008.1      2284570.32     13322222.93
       2283912.8     13321945.17
#Sta/Elev= 30
  4413.4  200.03  4517.9  196.18  4612.4  190.43  4675.3  190.02  4794.3  186.07
  4838.2  183.68  4874.7  180.95  4916.6  181.33  4927.1  180.09  4937.6  180.44
  4948.1  183.22  4958.3   182.8  4979.6  179.71  4991.6  174.23    5008     173
  5010.8   172.5    5014     173  5023.9  180.97    5032  182.03  5127.4  183.14
    5224  182.83  5253.2  181.07  5258.6  178.98  5276.9  176.94  5282.3   178.7
  5300.2  179.09  5311.4  181.22  5406.3  183.68  5488.2  183.44  5837.5  199.78
#Mann= 7 ,-1 , 0
  4413.4     .05       0  4794.3      .1       0  4838.2     .16       0
  4958.3      .1       0    5008     .07       0    5014      .1       0
  5127.4     .05       0
#XS Ineff= 1 ,-1
 5188.75 5461.25  183.74
Permanent Ineff=
       F
Bank Sta=4958.3,5032
XS Rating Curve= 0 ,0
Exp/Cntr=0.3,0.1

Type RM Length L Ch R = 1 ,43669   ,509,509,509
BEGIN DESCRIPTION:
UNT003 IN NURI 58.0
END DESCRIPTION:
XS GIS Cut Line= 3
      2285237.71     13321896.85      2284437.72     13321846.85
      2283937.68     13321746.85
#Sta/Elev= 30
  4200.4  200.85  4250.5  198.69  4320.6  194.06  4443.4  190.34    4531  186.54
  4661.3  184.67  4691.3  185.35  4721.4   184.8  4771.5  183.16  4829.4  179.77
  4841.6  180.27  4851.7  181.69  4911.8  183.43  4941.8  183.43  4971.9  180.99
  4981.9  179.73  4991.9  174.57  4999.4   172.7  5004.5   172.7  5009.2  171.87
  5011.9  171.37  5015.2  171.87  5032.5  175.77  5036.6  177.19  5042.7  179.31
  5052.9  180.42  5073.3  180.35  5103.9  182.11  5216.1  186.26  5511.9  200.97
#Mann= 5 ,-1 , 0
  4200.4     .05       0  4829.4      .1       0  5009.2     .07       0
  5015.2      .1       0  5036.6     .05       0
Bank Sta=4971.9,5052.9
XS Rating Curve= 0 ,0
Exp/Cntr=0.3,0.1