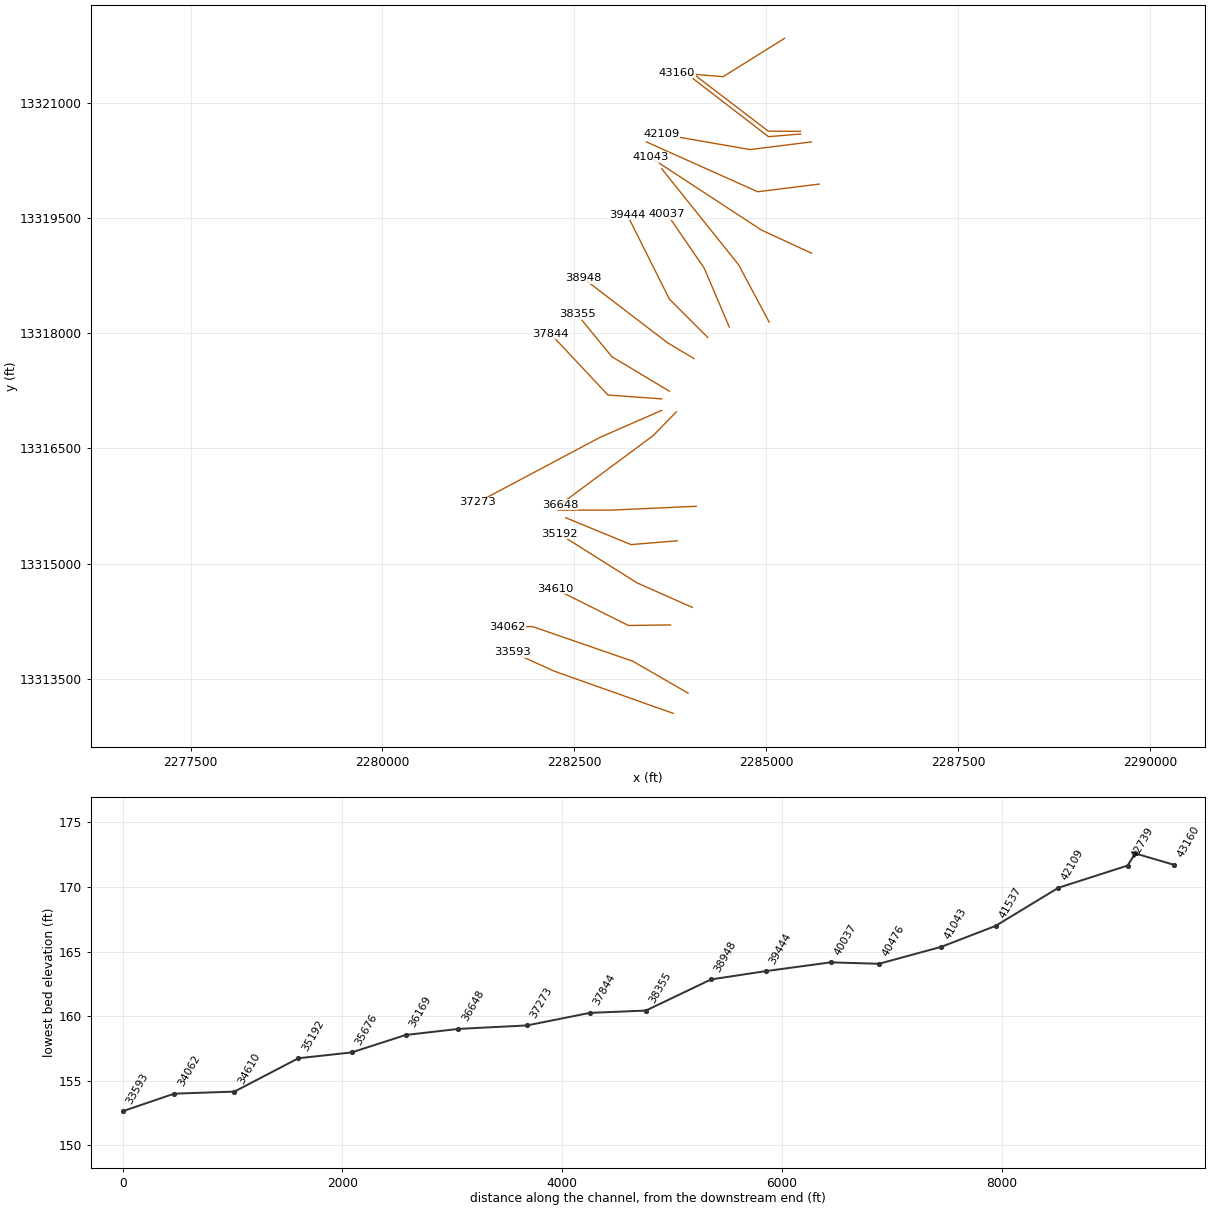
HEC-RAS study UNT003 IN NURI.prj: UNT003 IN NURI Base Level Engineering

--- UNT003 IN NURI.g01 (geometry) --- (continued)

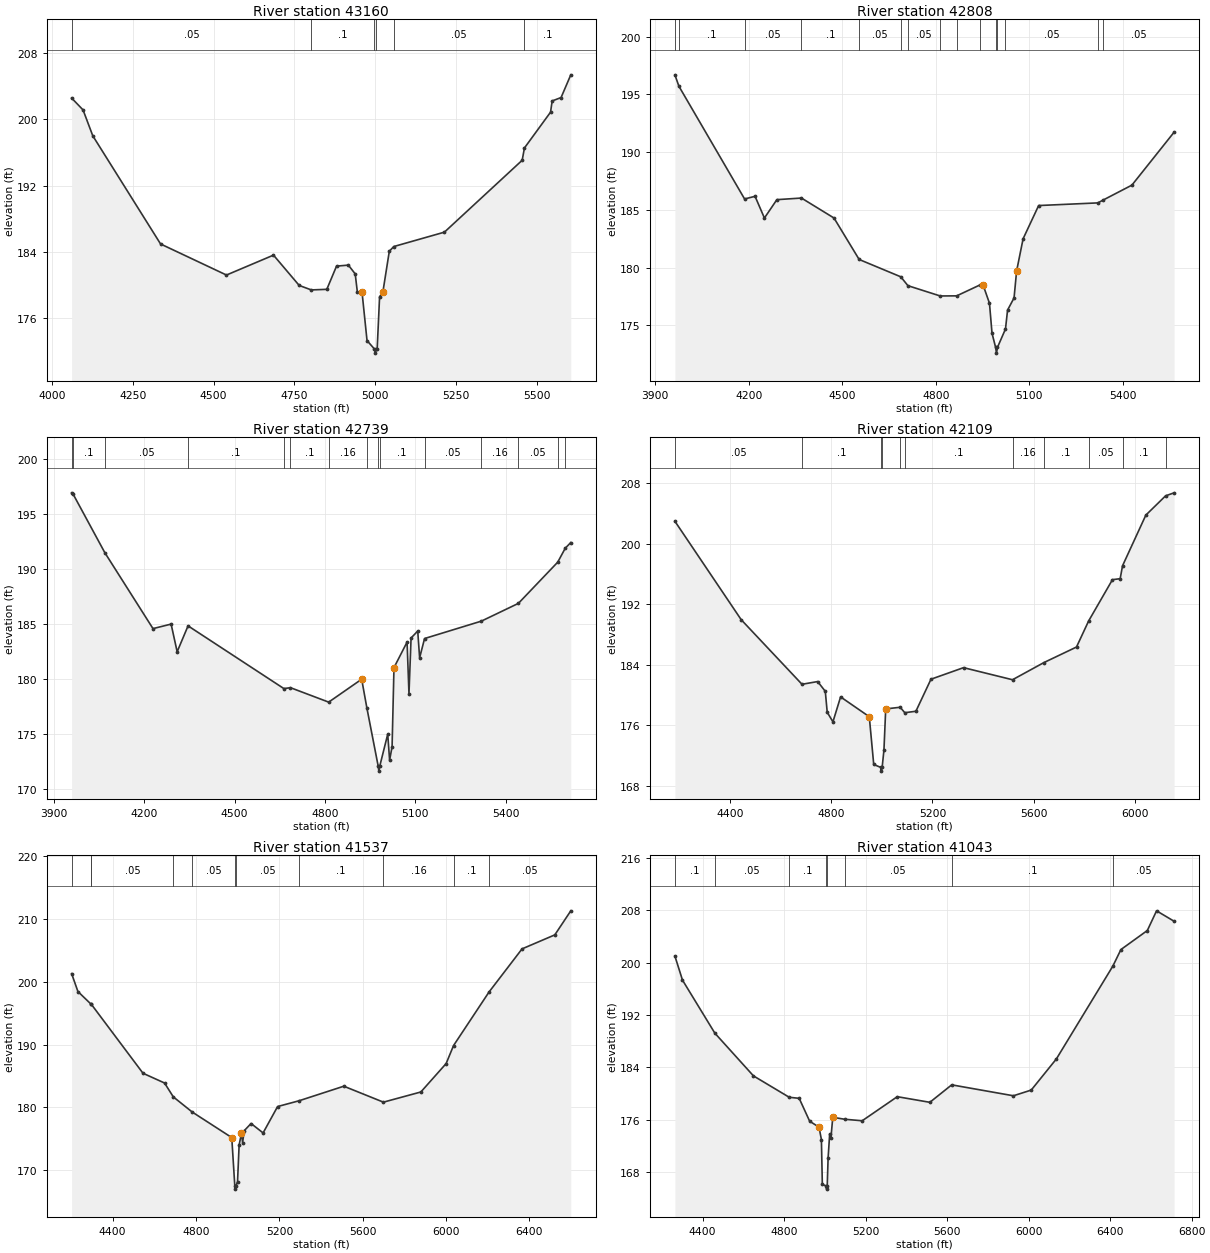
Type RM Length L Ch R = 1 ,43160   ,352,352,352
BEGIN DESCRIPTION:
UNT003 IN NURI 57.0
END DESCRIPTION:
XS GIS Cut Line= 3
      2285237.76     13321846.88      2284437.72     13321346.85
      2283837.74     13321396.85
#Sta/Elev= 30
  4060.4  202.59  4095.8  201.15  4125.9  198.02  4335.8  184.93  4539.8  181.17
  4685.4  183.58    4765  179.91  4802.5  179.37  4850.5  179.44  4880.6  182.25
  4917.2  182.37  4938.4  181.31  4944.9  179.16  4959.6  179.08    4975  173.24
  4997.9  172.22  5000.6  171.72  5003.9  172.22  5006.4  172.22  5013.9  178.54
  5023.9  179.07    5044  184.05  5057.9  184.62  5214.6  186.36  5455.4  195.06
  5462.4  196.55  5543.2  200.88  5548.2  202.24  5575.8  202.65  5605.9   205.4
#Mann= 6 ,-1 , 0
  4060.4     .05       0  4802.5      .1       0  4997.9     .07       0
  5003.9      .1       0  5057.9     .05       0  5462.4      .1       0
Bank Sta=4959.6,5023.9
XS Rating Curve= 0 ,0
Exp/Cntr=0.3,0.1

Type RM Length L Ch R = 1 ,42808   ,69,69,69
BEGIN DESCRIPTION:
UNT003 IN NURI 56.0
END DESCRIPTION:
XS GIS Cut Line= 3
       2285444.9     13320634.39      2285026.05     13320636.56
       2284086.4     13321354.86
#Sta/Elev= 30
  3962.8   196.7  3975.7  195.71  4186.4  185.95    4220  186.18    4250   184.3
    4290  185.89  4368.8  186.03  4473.3   184.3    4554  180.71  4687.5  179.21
  4710.5  178.44    4814  177.55    4867  177.56  4940.5  178.49  4951.2  178.53
  4972.1  176.92  4980.3  174.32  4991.8   173.1  4994.6   172.6  4997.8   173.1
  5023.5  174.69  5030.2  176.33    5051  177.38  5059.2  179.71    5080   182.5
  5129.9  185.38  5319.9  185.61  5336.4  185.85  5429.2  187.15  5564.4  191.73
#Mann= 15 ,-1 , 0
  3962.8     .05       0  3975.7      .1       0  4186.4     .05       0
  4368.8      .1       0    4554     .05       0  4687.5      .1       0
  4710.5     .05       0    4814     .16       0    4867     .05       0
  4940.5      .1       0  4991.8     .07       0  4997.8      .1       0
  5023.5     .05       0  5319.9     .16       0  5336.4     .05       0
Bank Sta=4951.2,5059.2
XS Rating Curve= 0 ,0
Exp/Cntr=0.3,0.1

Type RM Length L Ch R = 1 ,42739   ,630,630,630
BEGIN DESCRIPTION:
Mapping XS 559a5a3d
END DESCRIPTION:
XS GIS Cut Line= 3
       2285447.1     13320599.67      2285028.22     13320564.95
      2284047.29     13321320.18
#Sta/Elev= 30
  3958.4  196.91  3963.8  196.77  4068.5  191.49  4228.7  184.59  4288.9     185
    4309  182.49  4345.2  184.84  4663.5  179.15  4685.5  179.23  4812.4  177.92
    4922     180  4939.2   177.4  4976.5  172.16  4979.2  171.66  4982.5  172.16
  5008.5  175.01  5014.8  172.66    5023  173.87  5029.3  181.05  5072.8  183.37
  5079.1  178.68  5086.1  183.74  5108.2  184.37  5114.5  181.94  5130.9  183.69
  5319.7  185.27  5442.6  186.88  5573.3  190.62  5598.4  191.89  5616.7   192.4
#Mann= 15 ,-1 , 0
  3958.4     .05       0  3963.8      .1       0  4068.5     .05       0
  4345.2      .1       0  4663.5     .05       0  4685.5      .1       0
  4812.4     .16       0  4939.2      .1       0  4976.5     .07       0
  4982.5      .1       0  5130.9     .05       0  5319.7     .16       0
  5442.6     .05       0  5573.3      .1       0  5598.4     .05       0
Bank Sta=4922,5029.3
XS Rating Curve= 0 ,0
Exp/Cntr=0.3,0.1

Type RM Length L Ch R = 1 ,42109   ,572,572,572
BEGIN DESCRIPTION:
UNT003 IN NURI 55.0
END DESCRIPTION:
XS GIS Cut Line= 3
      2285587.74     13320496.86      2284787.72     13320396.85
      2283637.73     13320596.85
#Sta/Elev= 30
  4181.8     203  4443.8  189.98  4684.3  181.43  4746.2  181.79  4776.4   180.5
    4784  177.73  4806.6  176.46  4836.9  179.76  4950.3  177.14  4967.9  170.82
  4995.2  170.44  4997.9  169.94  5001.2  170.44  5008.3  172.73  5015.3  178.17
  5072.4  178.39  5090.7  177.67  5134.6  177.86  5194.2   182.1    5323  183.63
  5516.6  182.03  5640.6   184.3  5769.6  186.36  5817.4   189.8  5911.7  195.27
  5942.2   195.4  5951.6  197.11  6043.7  203.81  6121.7  206.36  6155.3  206.76
#Mann= 11 ,-1 , 0
  4181.8     .05       0  4684.3      .1       0  4995.2     .07       0
  5001.2      .1       0  5072.4     .16       0  5090.7      .1       0
  5516.6     .16       0  5640.6      .1       0  5817.4     .05       0
  5951.6      .1       0  6121.7     .05       0
Bank Sta=4950.3,5015.3
XS Rating Curve= 0 ,0
Exp/Cntr=0.3,0.1

Type RM Length L Ch R = 1 ,41537   ,494,494,494
BEGIN DESCRIPTION:
UNT003 IN NURI 54.0
END DESCRIPTION:
XS GIS Cut Line= 3
       2285687.7     13319946.85      2284887.72     13319846.85
      2283437.74     13320496.84
#Sta/Elev= 30
  4203.1  201.31  4233.3  198.46  4295.2  196.48  4297.8  196.42  4545.7  185.44
    4649  183.89    4691  181.68  4781.7  179.27  4971.5   175.2  4986.1  167.49
  4988.9  166.99  4992.1  167.49  4999.2  168.19  5006.8  174.01  5018.2  175.91
  5023.6  174.41  5031.2  176.29  5064.1  177.44  5121.8  175.94  5191.4  180.14
  5294.2  181.06  5509.2  183.38  5699.2  180.84  5878.8  182.46  6000.2  186.99
  6035.8  189.86  6205.9  198.38  6364.4  205.25  6521.6  207.48  6598.3  211.31
#Mann= 11 ,-1 , 0
  4203.1     .05       0  4295.2      .1       0  4297.8     .05       0
    4691      .1       0  4781.7     .05       0  4986.1    .035       0
  4992.1     .05       0  5294.2      .1       0  5699.2     .16       0
  6035.8      .1       0  6205.9     .05       0
Bank Sta=4971.5,5018.2
XS Rating Curve= 0 ,0
Exp/Cntr=0.3,0.1

Type RM Length L Ch R = 1 ,41043   ,567,567,567
BEGIN DESCRIPTION:
UNT003 IN NURI 53.0
END DESCRIPTION:
XS GIS Cut Line= 3
      2285587.74     13319046.85      2284937.72     13319346.85
      2283487.72     13320296.85
#Sta/Elev= 30
  4264.3     201  4301.5  197.32  4460.4  189.21  4649.8  182.68  4825.4  179.41
  4874.2  179.25  4925.6  175.75  4971.5  174.84  4983.2  172.95  4987.8  166.08
  5005.8  165.87  5008.6  165.37  5011.8  165.87  5016.1  170.14  5023.9  173.83
  5029.9  173.16    5039  176.35  5097.6  176.05  5183.4  175.82  5355.5   179.5
  5515.4  178.64  5622.6  181.31  5925.3  179.64  6012.8  180.51  6136.4  185.28
  6413.7  199.48  6452.9  201.99  6582.5   204.9  6627.8  207.91  6713.7  206.32
#Mann= 8 ,-1 , 0
  4264.3      .1       0  4460.4     .05       0  4825.4      .1       0
  5005.8     .07       0  5011.8      .1       0  5097.6     .05       0
  5622.6      .1       0  6413.7     .05       0
Bank Sta=4971.5,5039
XS Rating Curve= 0 ,0
Exp/Cntr=0.3,0.1

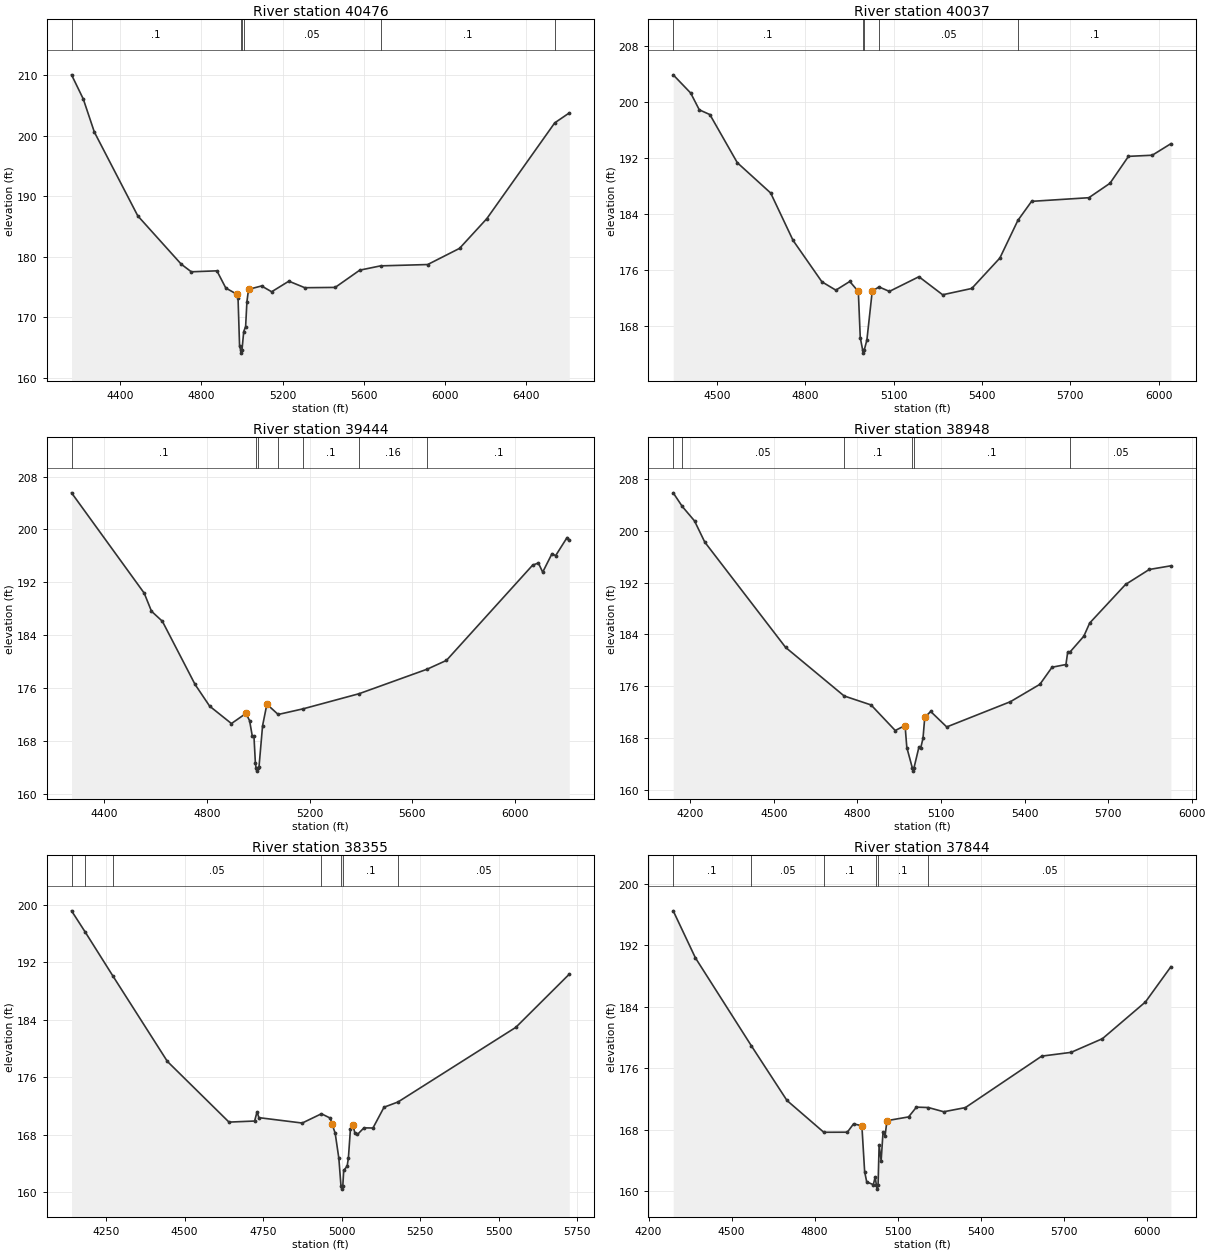
Type RM Length L Ch R = 1 ,40476   ,439,439,439
BEGIN DESCRIPTION:
UNT003 IN NURI 52.0
END DESCRIPTION:
XS GIS Cut Line= 3
      2285037.73     13318146.83      2284637.72     13318896.85
      2283637.72     13320146.85
#Sta/Elev= 30
    4161  210.05  4218.8  206.05  4273.3  200.59  4487.2  186.74  4701.1  178.76
  4750.7   177.5  4876.8  177.66  4920.7  174.81  4975.3  173.79  4980.9  173.09
  4988.4  165.24  4994.2  164.56    4997  164.06  5000.2  164.56  5008.8  167.62
  5018.2  168.46  5024.6  172.58  5032.6   174.6  5096.7  175.16  5146.3   174.2
  5231.1  175.95  5309.6  174.87  5459.2  174.92  5580.1  177.77  5682.6  178.48
  5914.7   178.7  6071.5  181.37    6206  186.29  6540.2  202.11  6611.8  203.75
#Mann= 6 ,-1 , 0
    4161      .1       0  4994.2     .07       0  5000.2      .1       0
  5008.8     .05       0  5682.6      .1       0  6540.2     .05       0
Bank Sta=4975.3,5032.6
XS Rating Curve= 0 ,0
Exp/Cntr=0.3,0.1

Type RM Length L Ch R = 1 ,40037   ,593,593,593
BEGIN DESCRIPTION:
UNT003 IN NURI 51.0
END DESCRIPTION:
XS GIS Cut Line= 3
      2284518.25     13318082.28      2284192.72     13318847.93
      2283708.34     13319556.27
#Sta/Elev= 30
  4351.4  203.94  4410.7  201.34    4440  198.94  4475.9  198.26  4569.1  191.38
  4682.4  187.05  4758.4  180.28  4856.4  174.36  4903.7  173.17    4951  174.41
    4980  172.98  4986.6  166.39  4994.5  164.67  4997.2  164.17  5000.5  164.67
  5009.1  166.04  5027.3  173.04  5050.3  173.63  5085.5  172.99  5185.8  175.09
  5266.4  172.51  5365.2  173.41  5460.7  177.76  5521.7  183.13  5568.4  185.86
  5762.8  186.38  5834.5  188.44  5897.4  192.29  5978.1  192.45  6041.5   194.1
#Mann= 5 ,-1 , 0
  4351.4      .1       0  4994.5     .07       0  5000.5      .1       0
  5050.3     .05       0  5521.7      .1       0
Bank Sta=4980,5027.3
XS Rating Curve= 0 ,0
Exp/Cntr=0.3,0.1

Type RM Length L Ch R = 1 ,39444   ,496,496,496
BEGIN DESCRIPTION:
UNT003 IN NURI 50.0
END DESCRIPTION:
XS GIS Cut Line= 3
      2284237.69     13317946.89      2283737.72     13318446.85
      2283187.72     13319546.86
#Sta/Elev= 30
  4273.6  205.54  4556.4  190.38  4584.7  187.65  4627.1  186.13  4754.4  176.58
    4811  173.31  4895.8  170.68  4952.4  172.21  4966.5  171.11  4977.1  168.75
  4983.5  168.75    4989  164.72  4991.6  163.99  4994.4  163.49  4997.6  163.99
    5003  164.08    5017  170.35  5033.8   173.6  5077.7  172.05  5175.5  172.91
  5392.8  175.19  5657.9   178.9  5732.5  180.22  6067.9  194.61  6090.3  194.94
  6107.1  193.55  6143.4  196.35  6157.4  196.04  6202.1  198.79  6210.5   198.4
#Mann= 7 ,-1 , 0
  4273.6      .1       0  4991.6     .07       0  4997.6      .1       0
  5077.7     .05       0  5175.5      .1       0  5392.8     .16       0
  5657.9      .1       0
Bank Sta=4952.4,5033.8
XS Rating Curve= 0 ,0
Exp/Cntr=0.3,0.1

Type RM Length L Ch R = 1 ,38948   ,593,593,593
BEGIN DESCRIPTION:
UNT003 IN NURI 49.0
END DESCRIPTION:
XS GIS Cut Line= 3
      2284057.46     13317672.01      2283710.21     13317880.36
      2282612.96     13318720.66
#Sta/Elev= 30
  4138.5  205.87  4171.1  203.76    4215  201.53  4251.9  198.25    4542  181.98
  4752.2  174.47  4848.9  173.08  4935.7  169.13    4971   169.9  4977.3   166.5
    4997  163.35  4999.8  162.85    5003  163.35  5020.9  166.59  5027.2  166.43
  5035.4  167.93  5041.7  171.17    5063  172.07  5120.6  169.68  5349.1  173.58
  5455.1  176.27  5498.7  178.91  5548.6  179.33  5554.9  181.25  5562.5  181.23
  5612.9  183.71  5633.8  185.74  5762.5   191.7  5847.7  194.02  5925.5  194.59
#Mann= 6 ,-1 , 0
  4138.5      .1       0  4171.1     .05       0  4752.2      .1       0
    4997     .07       0    5003      .1       0  5562.5     .05       0
Bank Sta=4971,5041.7
XS Rating Curve= 0 ,0
Exp/Cntr=0.3,0.1

Type RM Length L Ch R = 1 ,38355   ,511,511,511
BEGIN DESCRIPTION:
UNT003 IN NURI 48.0
END DESCRIPTION:
XS GIS Cut Line= 3
      2283737.76     13317246.83      2282987.72     13317696.85
      2282537.74     13318246.84
#Sta/Elev= 30
  4139.7  199.14  4184.1  196.13  4270.8  190.12  4444.9   178.2  4641.2  169.76
  4722.8  169.91  4730.6  171.19  4736.4  170.38  4874.4  169.63  4935.7  170.92
  4963.9  170.31  4969.7  169.45  4979.4  168.22  4991.1  164.73  4997.8  160.94
  5000.5  160.44  5003.8  160.94  5006.6  163.04  5017.6  163.64  5021.6  164.82
    5028  168.79  5035.9  169.34  5042.4   168.2  5050.3  168.04  5071.1  168.96
  5099.8  168.94    5135  171.83  5179.6  172.56  5554.9  182.94    5725  190.33
#Mann= 7 ,-1 , 0
  4139.7     .05       0  4184.1      .1       0  4270.8     .05       0
  4935.7      .1       0  4997.8     .07       0  5003.8      .1       0
  5179.6     .05       0
Bank Sta=4969.7,5035.9
XS Rating Curve= 0 ,0
Exp/Cntr=0.3,0.1

Type RM Length L Ch R = 1 ,37844   ,571,571,571
BEGIN DESCRIPTION:
UNT003 IN NURI 47.0
END DESCRIPTION:
XS GIS Cut Line= 3
      2283637.68     13317146.86      2282937.72     13317196.85
      2282187.74     13317996.83
#Sta/Elev= 30
  4289.2  196.48  4369.4  190.36  4571.3  178.93  4700.2   171.8  4833.3  167.66
  4918.3  167.67  4940.8  168.75  4970.9  168.51  4980.9  162.53  4988.4   161.2
  5012.2  160.84    5019  161.83  5023.4  160.76  5026.1  160.26  5029.4  160.76
  5033.2     166  5040.5  163.96  5047.4  167.71  5054.7  167.19  5061.5  169.17
  5139.7  169.66    5168  170.93    5211  170.88  5266.7  170.33  5344.8  170.87
  5620.8  177.57  5726.8  178.06  5840.1  179.84  5995.5  184.62  6087.5  189.21
#Mann= 6 ,-1 , 0
  4289.2      .1       0  4571.3     .05       0  4833.3      .1       0
  5023.4     .07       0  5029.4      .1       0    5211     .05       0
Bank Sta=4970.9,5061.5
XS Rating Curve= 0 ,0
Exp/Cntr=0.3,0.1

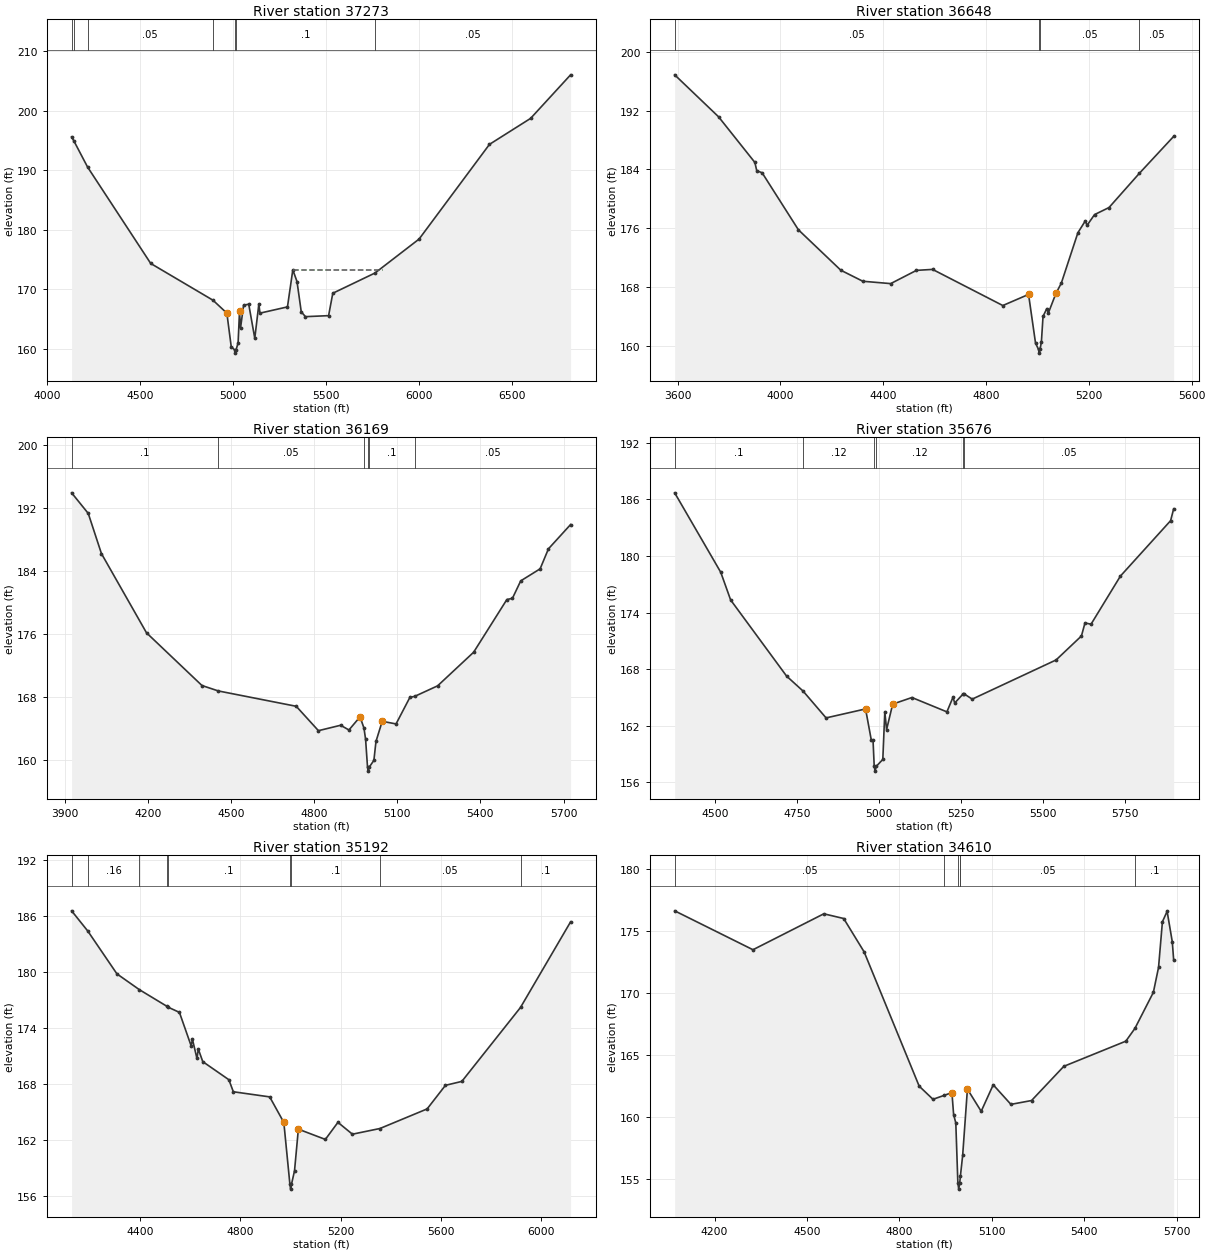
Type RM Length L Ch R = 1 ,37273   ,625,625,625
BEGIN DESCRIPTION:
UNT003 IN NURI 46.0
END DESCRIPTION:
XS GIS Cut Line= 3
      2283637.73     13316996.86      2282837.72     13316646.85
      2281237.71     13315796.85
#Sta/Elev= 30
  4132.2  195.58  4143.3  194.97  4218.1  190.52  4557.9  174.34  4892.9  168.17
  4967.6     166    4991  160.39  5010.6  159.79  5013.3  159.29  5016.6  159.79
  5028.1  161.01  5035.6  166.29  5041.2  163.51  5057.5  167.33  5085.2   167.5
  5117.8  161.78  5139.8  167.55  5145.5     166  5293.7  167.05  5322.5  173.28
  5345.1  171.29  5367.8  166.23  5390.4  165.41    5515  165.58  5537.6  169.34
  5764.9  172.74  6002.1  178.44  6380.7  194.33    6602  198.69  6817.2     206
#Mann= 7 ,-1 , 0
  4132.2     .05       0  4143.3      .1       0  4218.1     .05       0
  4892.9      .1       0  5010.6     .07       0  5016.6      .1       0
  5764.9     .05       0
#XS Ineff= 1 ,-1
 5322.49 5809.44   173.3
Permanent Ineff=
       F
Bank Sta=4967.6,5035.6
XS Rating Curve= 0 ,0
Exp/Cntr=0.3,0.1

Type RM Length L Ch R = 1 ,36648   ,479,479,479
BEGIN DESCRIPTION:
UNT003 IN NURI 45.0
END DESCRIPTION:
XS GIS Cut Line= 3
      2283828.26     13316977.58      2283522.71     13316665.08
      2282314.41     13315769.27
#Sta/Elev= 30
  3588.8  196.85  3759.4  191.15  3900.8  184.94    3908  183.83  3929.1  183.53
  4070.2  175.78  4235.1  170.29  4320.7  168.79  4429.2  168.47  4529.4  170.27
  4592.2   170.4  4865.4  165.49  4965.5     167  4992.6  160.39  5004.2  159.52
    5007  159.02  5010.2  159.52  5015.5  160.57  5021.8  164.01  5036.4  165.07
  5042.7  164.49  5071.9  167.13  5092.8  168.52  5157.5  175.39  5186.7  177.02
  5192.9  176.38  5222.2  177.85  5278.5  178.81    5396  183.44    5530  188.48
#Mann= 4 ,-1 , 0
  3588.8     .05       0  5004.2    .035       0  5010.2     .05       0
    5396     .05       0
Bank Sta=4965.5,5071.9
XS Rating Curve= 0 ,0
Exp/Cntr=0.3,0.1

Type RM Length L Ch R = 1 ,36169   ,493,493,493
BEGIN DESCRIPTION:
UNT003 IN NURI 44.0
END DESCRIPTION:
XS GIS Cut Line= 3
      2284087.72     13315746.85      2282987.72     13315696.85
      2282287.75     13315696.85
#Sta/Elev= 30
  3924.4  193.92  3984.5   191.3    4032   186.2  4194.7  176.13  4394.9  169.43
    4454  168.74  4735.2  166.79  4815.3  163.69  4895.4  164.38  4925.4  163.78
  4965.5  165.45  4979.7  164.01  4985.5  162.61  4992.5  159.05  4995.3  158.55
  4998.5  159.05  5015.5  159.92    5023  162.32  5045.5  164.88  5095.5  164.55
  5145.5  167.93  5162.7  168.05  5245.5  169.39  5375.5  173.66  5495.5  180.36
  5515.5  180.51  5545.5  182.73  5615.5  184.26  5645.5   186.8  5725.5  189.89
#Mann= 6 ,-1 , 0
  3924.4      .1       0    4454     .05       0  4979.7      .1       0
  4992.5     .07       0  4998.5      .1       0  5162.7     .05       0
Bank Sta=4965.5,5045.5
XS Rating Curve= 0 ,0
Exp/Cntr=0.3,0.1

Type RM Length L Ch R = 1 ,35676   ,484,484,484
BEGIN DESCRIPTION:
UNT003 IN NURI 43.0
END DESCRIPTION:
XS GIS Cut Line= 3
      2283837.75     13315296.86      2283237.72     13315246.85
      2282387.68     13315596.87
#Sta/Elev= 30
  4376.9  186.69  4517.4  178.27  4547.5  175.34  4718.1  167.27  4768.2  165.69
  4838.5  162.84  4958.9  163.79  4976.5  160.47  4981.7  160.47  4985.3   157.7
    4988   157.2  4991.3   157.7  5011.5  158.44  5017.6   163.5    5023   161.6
  5041.6   164.3  5100.3     165  5206.9  163.48  5225.4  165.02  5230.8  164.42
  5257.2  165.41  5257.9  165.42  5284.1  164.83  5539.8  168.98  5617.1  171.52
  5627.9   172.9  5646.4  172.77    5736  177.87    5889  183.74  5898.3     185
#Mann= 6 ,-1 , 0
  4376.9      .1       0  4768.2     .12       0  4985.3     .07       0
  4991.3     .12       0  5257.2      .1       0  5257.9     .05       0
Bank Sta=4958.9,5041.6
XS Rating Curve= 0 ,0
Exp/Cntr=0.3,0.1

Type RM Length L Ch R = 1 ,35192   ,582,582,582
BEGIN DESCRIPTION:
UNT003 IN NURI 42.0
END DESCRIPTION:
XS GIS Cut Line= 3
      2284036.68     13314428.11      2283315.29     13314748.44
      2282301.19      13315388.1
#Sta/Elev= 30
  4128.5  186.59    4193  184.42  4309.1  179.83  4398.3  178.14  4507.2  176.37
    4513  176.26  4558.1   175.7  4604.6  172.13  4610.1   172.8  4627.9  170.76
  4633.3  171.77  4651.1  170.42  4755.1  168.48  4772.9  167.19  4917.8  166.64
  4974.1   163.9  4998.4  157.25  5001.2  156.75  5004.4  157.25  5016.7  158.71
    5032  163.18  5139.6  162.08  5189.7  163.91  5247.4  162.64  5357.1  163.25
  5545.1  165.35  5618.1  167.88  5683.4   168.3  5917.2  176.23  6116.8  185.41
#Mann= 9 ,-1 , 0
  4128.5      .1       0    4193     .16       0  4398.3      .1       0
  4507.2     .05       0    4513      .1       0  4998.4     .07       0
  5004.4      .1       0  5357.1     .05       0  5917.2      .1       0
Bank Sta=4974.1,5032
XS Rating Curve= 0 ,0
Exp/Cntr=0.3,0.1

Type RM Length L Ch R = 1 ,34610   ,548,548,548
BEGIN DESCRIPTION:
UNT003 IN NURI 41.0
END DESCRIPTION:
XS GIS Cut Line= 3
      2283751.92      13314199.8      2283203.27     13314192.86
      2282245.06     13314671.96
#Sta/Elev= 30
  4070.5  176.63  4324.7  173.49  4554.7  176.39  4619.2  176.01  4685.5  173.32
  4864.3  162.48  4909.1  161.42  4944.7  161.73  4970.6  161.96  4976.1  160.19
  4983.2  159.51  4989.9  154.67  4992.7  154.17  4995.9  154.67    4998  155.19
  5005.5   156.9  5020.9  162.24  5065.6  160.45  5104.7  162.59  5162.1  161.01
  5229.1  161.32  5333.9  164.08  5535.2  166.11  5564.7  167.14  5624.6  170.05
  5641.4  172.06    5654  175.75  5669.3  176.59  5686.1  174.12  5690.5  172.66
#Mann= 6 ,-1 , 0
  4070.5     .05       0  4944.7      .1       0  4989.9    .035       0
  4995.9      .1       0    4998     .05       0  5564.7      .1       0
Bank Sta=4970.6,5020.9
XS Rating Curve= 0 ,0
Exp/Cntr=0.3,0.1

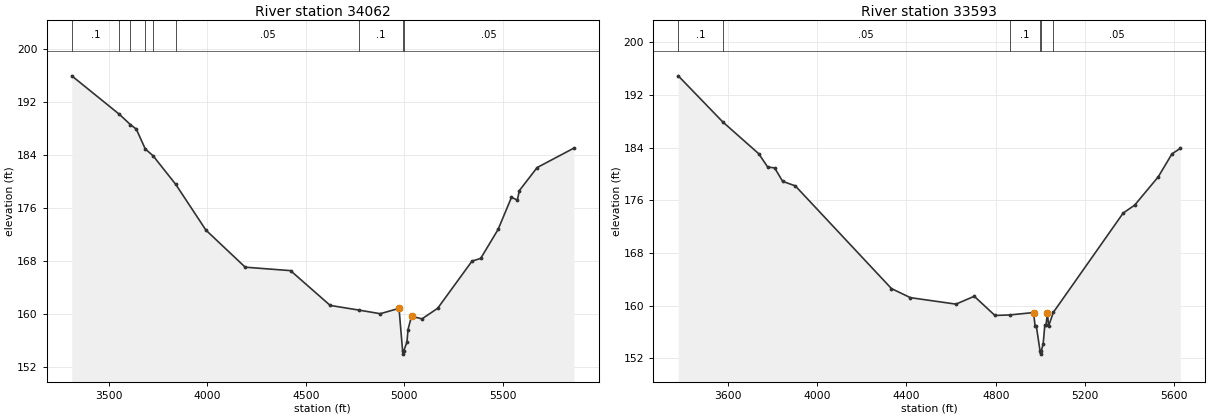
Type RM Length L Ch R = 1 ,34062   ,469,469,469
BEGIN DESCRIPTION:
UNT003 IN NURI 40.0
END DESCRIPTION:
XS GIS Cut Line= 4
      2283981.03     13313310.92      2283258.82     13313727.58
      2281953.27     13314178.97      2281621.31     13314172.05
#Sta/Elev= 30
  3312.6  196.01  3554.6  190.19  3609.6  188.66    3640  187.97  3685.6  184.97
    3725  183.95  3840.3  179.62  3993.3  172.72  4192.6  167.13  4422.6  166.61
  4623.7  161.36  4770.6  160.65  4877.6  160.11  4972.9  160.92    4991  154.51
  4993.8  154.01    4997  154.51  5013.1  155.82  5018.4  157.71  5036.3  159.74
  5089.2  159.33    5169  160.93  5343.2  168.05  5387.2  168.46  5475.4  172.82
  5543.3  177.67  5573.3  177.26  5583.3  178.69  5673.3  182.16  5859.8   185.1
#Mann= 9 ,-1 , 0
  3312.6      .1       0  3554.6     .05       0  3609.6      .1       0
  3685.6     .05       0    3725      .1       0  3840.3     .05       0
  4770.6      .1       0    4991    .035       0    4997     .05       0
Bank Sta=4972.9,5036.3
XS Rating Curve= 0 ,0
Exp/Cntr=0.3,0.1

Type RM Length L Ch R = 1 ,33593   ,554,554,554
BEGIN DESCRIPTION:
UNT003 IN NURI 39.0
END DESCRIPTION:
XS GIS Cut Line= 3
      2283787.72     13313046.86      2282237.72     13313596.85
      2281687.75     13313846.84
#Sta/Elev= 30
    3378  194.89  3577.3   187.9  3738.8  183.06  3778.8  181.04  3809.7  180.92
  3845.8  178.87  3902.3  178.19    4333   162.6  4417.9  161.22  4621.9  160.24
  4703.9  161.43  4796.5  158.52    4863   158.6  4969.6  158.96  4976.4   156.9
  4981.7  156.96  4998.5  153.15  5001.2  152.65  5004.5  153.15  5012.6  154.21
    5020  157.09  5025.4  157.09  5031.5   158.9    5037  156.93  5058.3     159
  5370.9  174.06  5422.5  175.27    5528  179.56  5589.5  183.05  5626.8  183.88
#Mann= 6 ,-1 , 0
    3378      .1       0  3577.3     .05       0    4863      .1       0
  4998.5     .07       0  5004.5      .1       0  5058.3     .05       0
Bank Sta=4969.6,5031.5
XS Rating Curve= 0 ,0
Exp/Cntr=0.3,0.1