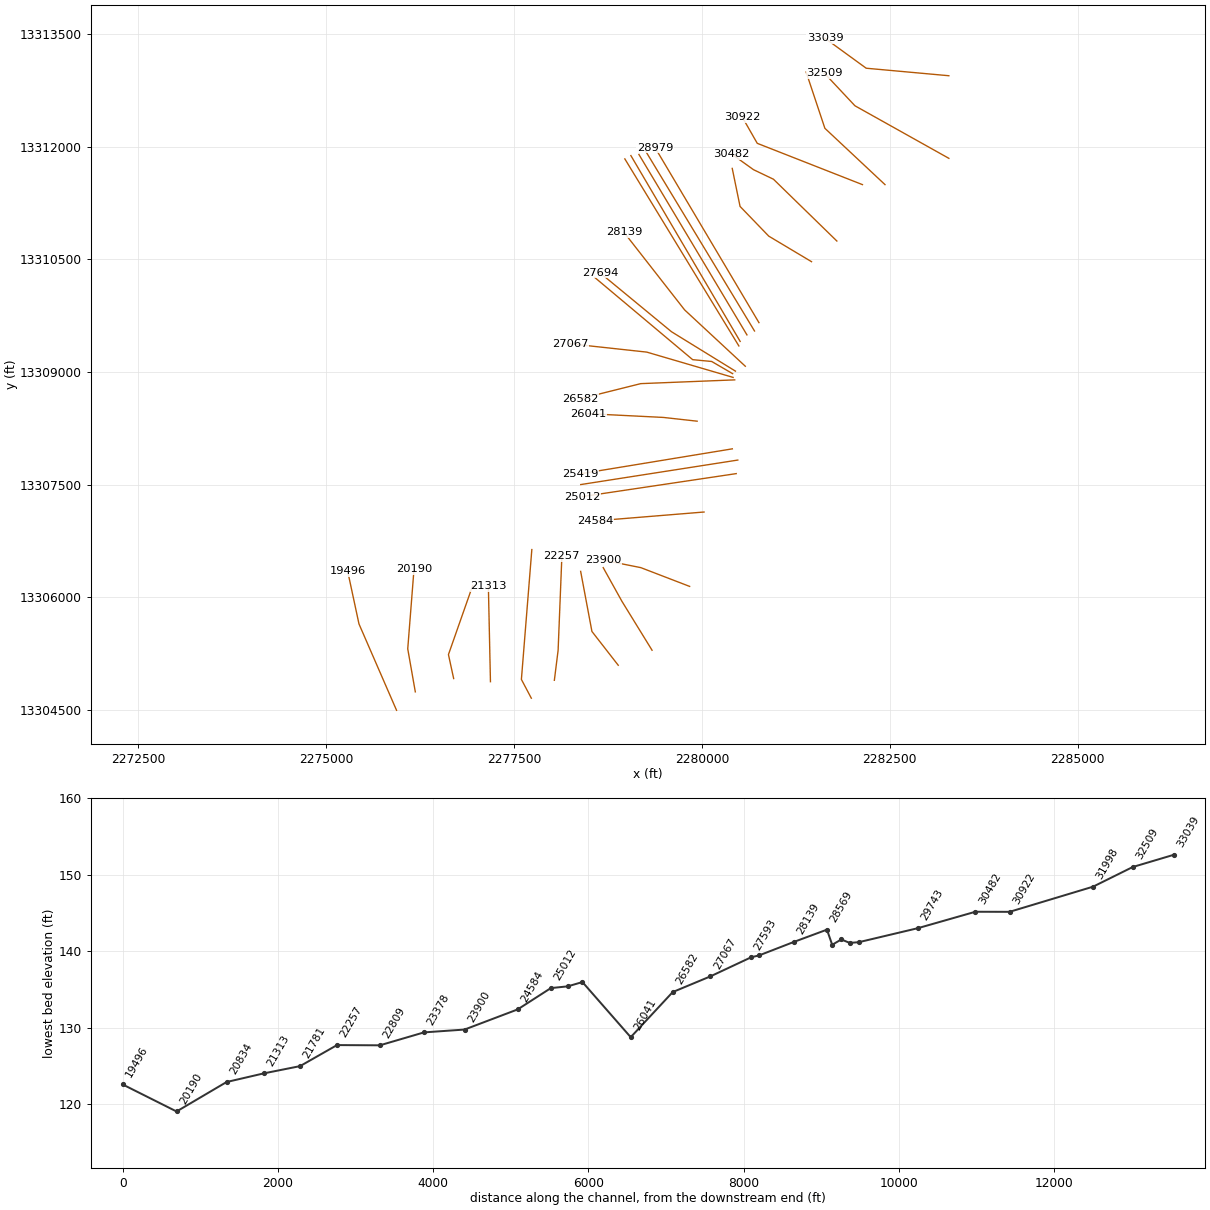
HEC-RAS study UNT003 IN NURI.prj: UNT003 IN NURI Base Level Engineering

--- UNT003 IN NURI.g01 (geometry) --- (continued)

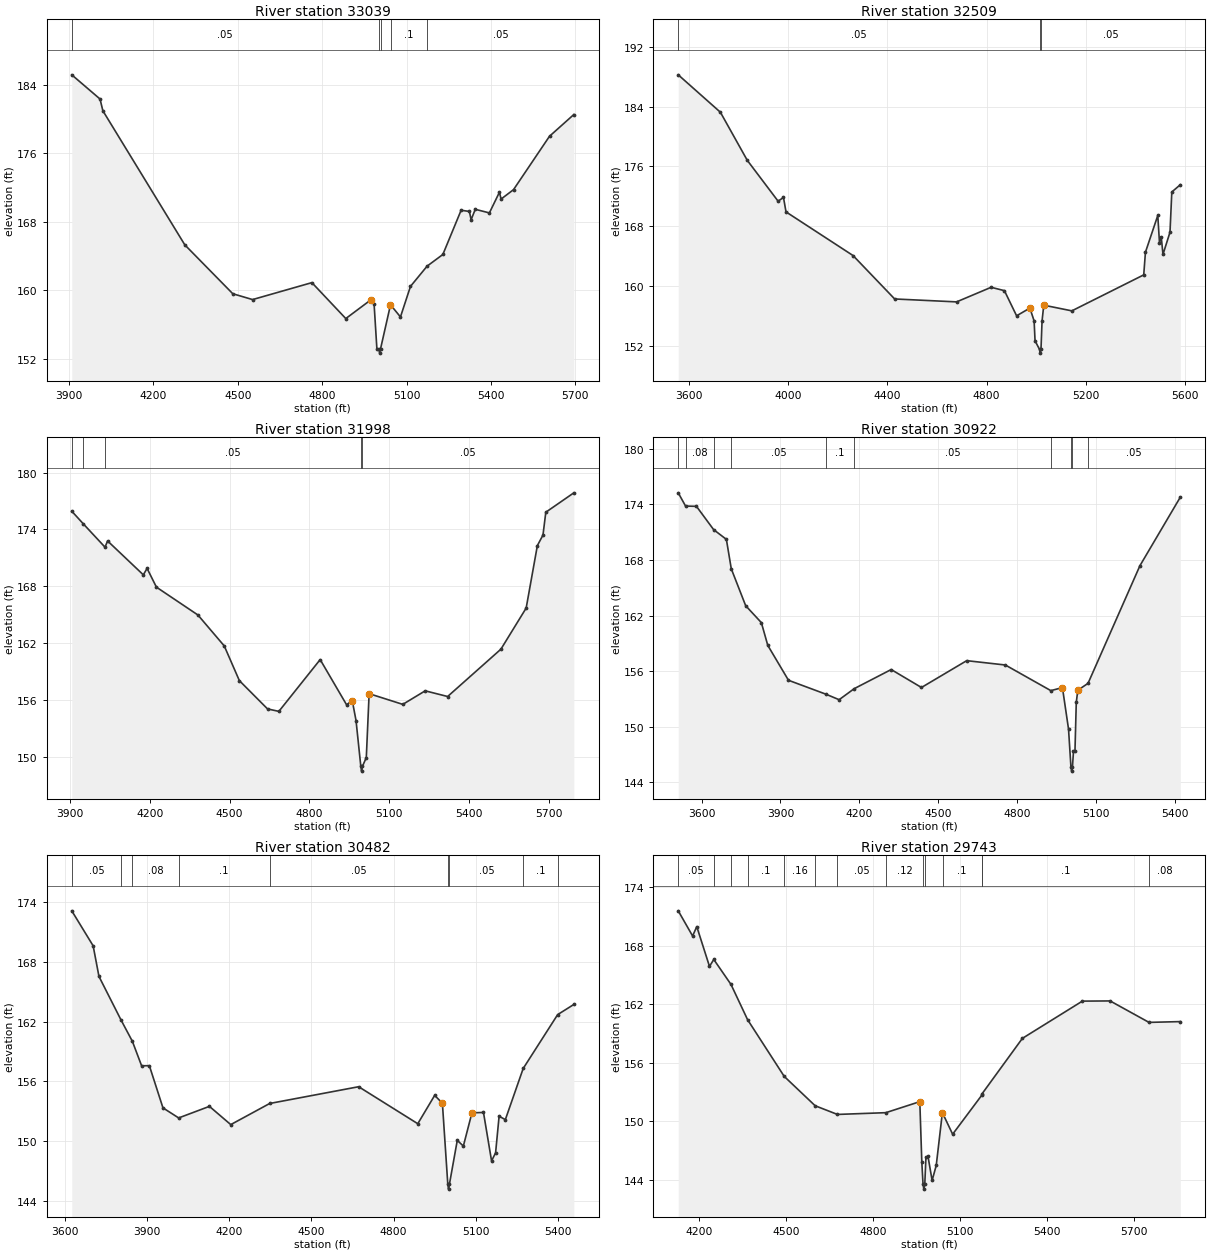
Type RM Length L Ch R = 1 ,33039   ,530,530,530
BEGIN DESCRIPTION:
UNT003 IN NURI 38.0
END DESCRIPTION:
XS GIS Cut Line= 3
      2283287.76     13312946.85      2282187.72     13313046.85
      2281637.76     13313446.83
#Sta/Elev= 30
  3910.1  185.17  4010.6  182.34  4020.6  180.97  4311.8   165.3  4482.5  159.58
  4552.8   158.9  4763.6  160.88  4884.1  156.68  4974.5   158.9  4984.6  158.43
  4994.6  153.16  5001.6  153.14  5004.4  152.64  5007.6  153.14  5042.9  158.27
  5043.8  158.26  5078.4  156.87    5114  160.44  5173.2  162.81  5229.1  164.17
    5294  169.34  5323.4   169.2  5329.6  168.23  5344.3  169.45  5394.5  169.03
  5430.1  171.44  5436.2  170.65  5480.3  171.75  5608.2  177.99  5694.7  180.53
#Mann= 5 ,-1 , 0
  3910.1     .05       0  5001.6     .03       0  5007.6     .05       0
  5043.8      .1       0  5173.2     .05       0
Bank Sta=4974.5,5042.9
XS Rating Curve= 0 ,0
Exp/Cntr=0.3,0.1

Type RM Length L Ch R = 1 ,32509   ,511,511,511
BEGIN DESCRIPTION:
UNT003 IN NURI 37.0
END DESCRIPTION:
XS GIS Cut Line= 3
      2283287.75     13311846.84      2282037.72     13312546.85
      2281631.93      13312979.7
#Sta/Elev= 30
    3556  188.24  3726.1  183.24  3834.6  176.81    3959  171.35  3980.7  171.85
  3990.9  169.92  4261.5  164.08  4429.3  158.28  4679.2  157.89  4818.6  159.84
  4872.2  159.39  4921.4  156.03    4975  157.06  4992.1  155.34  4995.8  152.69
  5013.8  151.54  5016.5  151.04  5019.8  151.54  5024.1  155.34    5031  157.45
  5144.3  156.69  5434.4   161.5  5441.3  164.53  5491.1  169.44  5497.9  165.82
  5505.2  166.52  5512.1  164.23  5540.4  167.21  5547.7  172.58    5582  173.55
#Mann= 3 ,-1 , 0
    3556     .05       0  5013.8     .03       0  5019.8     .05       0
Bank Sta=4975,5031
XS Rating Curve= 0 ,0
Exp/Cntr=0.3,0.1

Type RM Length L Ch R = 1 ,31998   ,1076,1076,1076
BEGIN DESCRIPTION:
UNT003 IN NURI 36.0
END DESCRIPTION:
XS GIS Cut Line= 3
      2282437.72     13311496.85      2281637.72     13312246.85
      2281387.71     13312996.89
#Sta/Elev= 30
  3906.6  175.92  3950.1  174.58  4031.6  172.12  4041.2  172.78  4175.5   169.2
  4189.7  169.88  4224.8   167.9  4380.7  164.96  4479.8  161.69  4536.5  158.03
  4642.5  155.04    4685  154.78  4840.3  160.25  4939.5  155.48  4960.9  155.92
  4975.1  153.81  4993.1  148.97  4995.9  148.47  4999.1  148.97  5013.7   149.9
  5024.3  156.65  5150.8  155.52  5235.1  156.95  5319.4  156.35  5519.7  161.35
  5614.6  165.69  5656.7  172.29  5677.8   173.4  5688.4  175.81  5793.8  177.86
#Mann= 5 ,-1 , 0
  3906.6     .05       0  3950.1      .1       0  4031.6     .05       0
  4993.1    .035       0  4999.1     .05       0
Bank Sta=4960.9,5024.3
XS Rating Curve= 0 ,0
Exp/Cntr=0.3,0.1

Type RM Length L Ch R = 1 ,30922   ,440,440,440
BEGIN DESCRIPTION:
UNT003 IN NURI 35.0
END DESCRIPTION:
XS GIS Cut Line= 3
      2282137.77     13311496.84      2280737.72     13312046.85
      2280537.73     13312396.83
#Sta/Elev= 30
  3511.6  175.26  3539.4  173.83  3580.8   173.8  3646.1  171.28  3694.5  170.23
  3713.1  167.05  3767.8  163.06  3827.4  161.23  3851.8  158.77  3930.4     155
  4073.1  153.49  4122.8   152.9  4179.9  154.09  4320.6  156.16  4435.6  154.22
  4607.5  157.12  4754.3  156.65  4927.1  153.88  4971.1  154.21  4994.3  149.72
  5003.3  145.68    5006  145.18  5009.3  145.68  5013.1  147.32  5018.7  147.32
  5023.7  152.61  5029.5  153.92  5068.4  154.67  5265.6  167.39  5418.9  174.79
#Mann= 10 ,-1 , 0
  3511.6     .05       0  3539.4     .08       0  3646.1      .1       0
  3713.1     .05       0  4073.1      .1       0  4179.9     .05       0
  4927.1      .1       0  5003.3     .07       0  5009.3      .1       0
  5068.4     .05       0
Bank Sta=4971.1,5029.5
XS Rating Curve= 0 ,0
Exp/Cntr=0.3,0.1

Type RM Length L Ch R = 1 ,30482   ,739,739,739
BEGIN DESCRIPTION:
UNT003 IN NURI 34.0
END DESCRIPTION:
XS GIS Cut Line= 4
      2281797.04     13310745.85      2280953.31     13311568.75
      2280687.77     13311695.94      2280395.98     13311904.72
#Sta/Elev= 30
  3625.9   173.1  3703.9  169.59  3725.1  166.52  3805.1  162.18  3846.9  160.02
  3880.7  157.56    3909  157.57  3958.6  153.34  4015.9  152.33  4128.1  153.49
    4206  151.66  4348.1  153.78  4672.6  155.46  4888.3  151.75  4949.9  154.59
  4978.1  153.81  4997.8  145.69  5000.5  145.19  5003.8  145.69  5032.4  150.08
  5054.6  149.51  5085.9  152.84    5128  152.88  5157.5  148.02  5172.2  148.83
    5185   152.5  5207.8  152.16  5272.9  157.29  5398.6  162.69  5457.7  163.71
#Mann= 9 ,-1 , 0
  3625.9     .05       0  3805.1      .1       0  3846.9     .08       0
  4015.9      .1       0  4348.1     .05       0  4997.8    .035       0
  5003.8     .05       0  5272.9      .1       0  5398.6     .05       0
Bank Sta=4978.1,5085.9
XS Rating Curve= 0 ,0
Exp/Cntr=0.3,0.1

Type RM Length L Ch R = 1 ,29743   ,764,764,764
BEGIN DESCRIPTION:
UNT003 IN NURI 33.0
END DESCRIPTION:
XS GIS Cut Line= 4
      2281460.18     13310470.66      2280890.77     13310810.92
      2280508.82     13311206.75      2280404.84     13311712.79
#Sta/Elev= 30
  4129.7  171.59  4179.2  169.01  4193.6  169.97  4237.4  165.89  4252.2   166.6
  4311.5  164.04  4368.6  160.43  4494.9  154.61  4601.5   151.6  4678.2  150.71
  4844.9  150.89  4962.1  152.02    4969  145.81  4973.2  143.55    4976  143.05
  4979.2  143.55  4983.2   146.3  4990.4   146.4  5004.5  143.94  5018.7  145.48
  5039.8  150.88  5040.7  150.84  5075.2  148.68  5175.6  152.68  5176.7  152.83
  5315.5  158.51  5522.2  162.33  5617.8  162.35  5751.8  160.15  5859.7  160.23
#Mann= 14 ,-1 , 0
  4129.7     .05       0  4252.2      .1       0  4311.5     .08       0
  4368.6      .1       0  4494.9     .16       0  4601.5      .1       0
  4678.2     .05       0  4844.9     .12       0  4973.2     .07       0
  4979.2     .12       0  5040.7      .1       0  5175.6     .12       0
  5176.7      .1       0  5751.8     .08       0
Bank Sta=4962.1,5039.8
XS Rating Curve= 0 ,0
Exp/Cntr=0.3,0.1

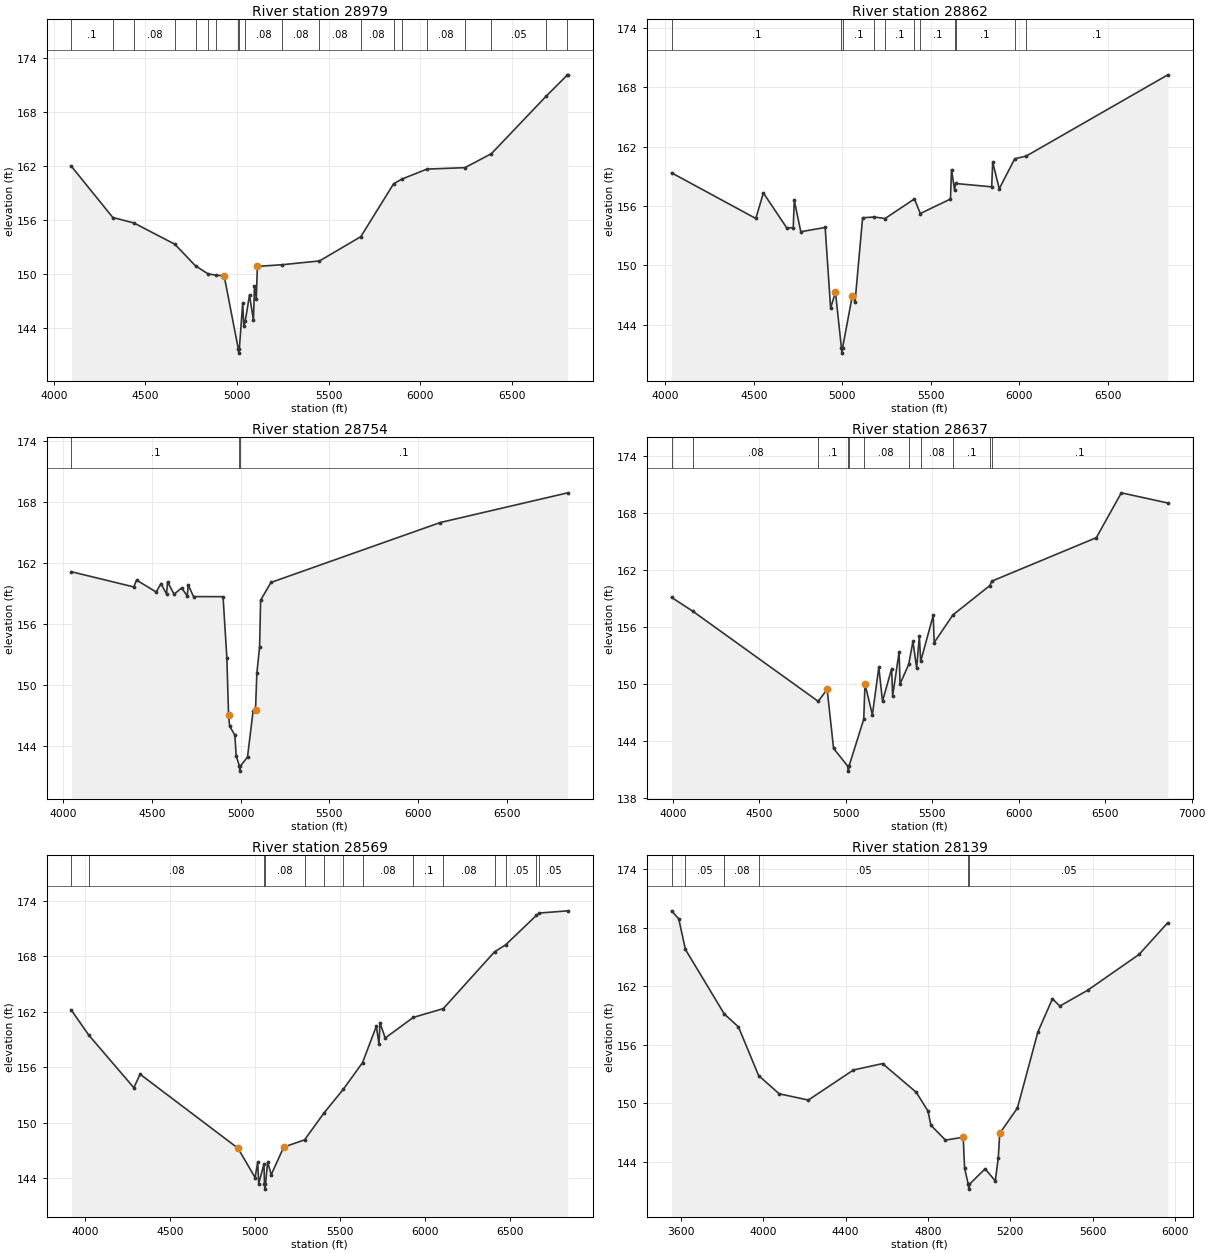
Type RM Length L Ch R = 1 ,28979   ,117,117,117
BEGIN DESCRIPTION:
UNT003 IN NURI 32.0
END DESCRIPTION:
XS GIS Cut Line= 2
      2280760.27     13309659.02      2279378.28     13311988.88
#Sta/Elev= 30
  4096.4  161.99  4322.1   156.3  4436.8   155.7  4660.6  153.33  4773.4  150.92
    4842  150.03  4886.2  149.88  4929.8  149.82  5006.7  141.71  5009.5  141.21
  5012.7  141.71  5031.2  146.82    5037  144.22  5044.6  144.74  5068.2  147.68
  5089.6  144.88  5095.4  148.71  5105.2  147.26  5111.1  150.86  5247.1  151.05
  5450.2  151.47  5675.8  154.17  5854.9  160.06  5901.4  160.59  6036.9  161.69
  6244.2  161.85  6388.9  163.41  6686.4  169.78  6803.9  172.18  6805.3  172.18
#Mann= 20 ,-1 , 0
  4096.4      .1       0  4322.1     .08       0  4436.8     .08       0
  4660.6     .08       0  4773.4     .12       0    4842      .1       0
  4886.2     .08       0  5006.7     .07       0  5012.7     .12       0
  5044.6     .08       0  5247.1     .08       0  5450.2     .08       0
  5675.8     .08       0  5854.9      .1       0  5901.4     .08       0
  6036.9     .08       0  6244.2      .1       0  6388.9     .05       0
  6686.4      .1       0  6803.9     .08       0
Bank Sta=4929.8,5111.1
XS Rating Curve= 0 ,0
Exp/Cntr=0.3,0.1

Type RM Length L Ch R = 1 ,28862   ,108,108,108
BEGIN DESCRIPTION:
Mapping XS 898ccb3e
END DESCRIPTION:
XS GIS Cut Line= 2
      2280701.24      13309547.9      2279249.82     13311947.26
#Sta/Elev= 30
  4034.5  159.36  4510.6  154.74  4553.3  157.32  4685.2   153.8  4722.1   153.8
  4727.9  156.58  4764.8   153.4  4902.5  153.83  4933.2  145.68  4960.7  147.28
  4994.6  141.62  4997.3  141.12  5000.6  141.62  5055.8  146.92  5071.3   146.3
    5114  154.81  5180.4  154.89  5240.5  154.73  5407.1  156.72    5440  155.24
  5610.6  156.71  5616.4  159.68  5633.8  157.63  5639.5  158.28  5843.4  157.94
  5849.2  160.44  5886.1  157.75  5973.8  160.78  6038.4  161.05  6838.7  169.27
#Mann= 11 ,-1 , 0
  4034.5      .1       0  4994.6     .07       0  5000.6      .1       0
  5180.4     .05       0  5240.5      .1       0  5407.1     .05       0
    5440      .1       0  5633.8     .05       0  5639.5      .1       0
  5973.8     .05       0  6038.4      .1       0
Bank Sta=4960.7,5055.8
XS Rating Curve= 0 ,0
Exp/Cntr=0.3,0.1

Type RM Length L Ch R = 1 ,28754   ,117,117,117
BEGIN DESCRIPTION:
Mapping XS b2abf5bc
END DESCRIPTION:
XS GIS Cut Line= 2
      2280600.54     13309495.83      2279163.02     13311898.64
#Sta/Elev= 30
  4045.3  161.17  4396.8  159.68  4412.4  160.35  4523.2  159.18  4550.4  160.01
  4581.6  158.98  4587.4  160.17  4624.4  158.96  4667.1  159.59  4698.3  158.78
  4704.1  159.87    4734  158.73  4900.5  158.72  4921.9  152.74  4931.7  147.06
  4937.5     146  4967.1  145.11  4974.5   143.1  4992.8  142.07  4995.6  141.57
  4998.8  142.07  5038.6  142.97  5069.8  147.45  5083.6  147.59  5091.2  151.19
  5106.7  153.78  5112.5  158.38  5170.9  160.12  6125.9  166.01  6845.3  168.93
#Mann= 3 ,-1 , 0
  4045.3      .1       0  4992.8     .07       0  4998.8      .1       0
Bank Sta=4931.7,5083.6
XS Rating Curve= 0 ,0
Exp/Cntr=0.3,0.1

Type RM Length L Ch R = 1 ,28637   ,68,68,68
BEGIN DESCRIPTION:
Mapping XS 95196efa
END DESCRIPTION:
XS GIS Cut Line= 2
      2280510.27     13309409.01      2279056.24      13311883.3
#Sta/Elev= 30
  3992.2  159.16  4115.5   157.7  4840.2  148.22    4892  149.48  4929.1  143.27
    5012  141.37  5014.7  140.87    5018  141.37  5103.7  146.34  5110.7  150.04
  5153.6   146.8  5190.8   151.8  5212.2  148.23    5265  151.66  5270.8  148.78
    5308  153.41  5313.8  150.06  5363.8  152.12  5388.1  154.52  5409.5  151.73
  5425.2  155.09    5433  152.43  5505.3  157.26  5511.1  154.41  5619.5  157.32
  5832.4   160.4    5844  160.87  6448.7  165.45  6593.2  170.17  6862.1   169.1
#Mann= 11 ,-1 , 0
  3992.2      .1       0  4115.5     .08       0  4840.2      .1       0
    5012     .07       0    5018      .1       0  5103.7     .08       0
  5363.8      .1       0    5433     .08       0  5619.5      .1       0
  5832.4     .08       0    5844      .1       0
Bank Sta=4892,5110.7
XS Rating Curve= 0 ,0
Exp/Cntr=0.3,0.1

Type RM Length L Ch R = 1 ,28569   ,430,430,430
BEGIN DESCRIPTION:
UNT003 IN NURI 31.0
END DESCRIPTION:
XS GIS Cut Line= 2
       2280493.2     13309348.47      2278975.54     13311839.58
#Sta/Elev= 30
  3921.8  162.16  4023.5  159.48  4288.3   153.8  4325.1  155.26  4900.3  147.27
  5001.1   144.1  5016.5  145.77  5022.4  143.45  5053.3  145.57  5056.2  143.35
  5058.9  142.85  5062.2  143.35  5074.6  145.77  5095.9  144.41  5169.5  147.39
  5291.9  148.17  5405.5  151.06    5519  153.62  5632.6  156.51  5713.8  160.44
  5729.2  158.49  5735.1  160.79    5766  159.17  5930.7  161.39  6107.1  162.34
  6408.4  168.47  6474.4  169.24  6654.6  172.41  6672.7  172.66  6838.8   172.9
#Mann= 14 ,-1 , 0
  3921.8      .1       0  4023.5     .08       0  5056.2     .07       0
  5062.2     .08       0  5291.9     .05       0  5405.5     .08       0
    5519     .05       0  5632.6     .08       0  5930.7      .1       0
  6107.1     .08       0  6408.4      .1       0  6474.4     .05       0
  6654.6      .1       0  6672.7     .05       0
Bank Sta=4900.3,5169.5
XS Rating Curve= 0 ,0
Exp/Cntr=0.3,0.1

Type RM Length L Ch R = 1 ,28139   ,445,445,445
BEGIN DESCRIPTION:
UNT003 IN NURI 30.0
END DESCRIPTION:
XS GIS Cut Line= 3
      2280578.69      13309078.5      2279770.67     13309829.18
      2278965.12     13310860.43
#Sta/Elev= 30
  3553.9  169.72  3588.8   168.9  3621.2  165.77  3810.5  159.15    3879  157.84
  3976.8  152.86  4076.9  150.99  4218.6  150.35    4438  153.43  4579.2  154.08
  4742.7  151.15  4799.7  149.24  4814.2  147.77  4884.8  146.25  4971.1  146.54
  4977.9  143.37  4995.7  141.73  4998.5  141.23  5001.7  141.73  5077.4  143.31
  5127.1  142.07  5141.6  144.44  5148.7  146.94  5234.8  149.54  5334.2  157.33
  5404.8  160.72  5440.6  159.97  5576.6   161.6  5825.4  165.25  5965.4  168.51
#Mann= 6 ,-1 , 0
  3553.9     .08       0  3621.2     .05       0  3810.5     .08       0
  3976.8     .05       0  4995.7    .035       0  5001.7     .05       0
Bank Sta=4971.1,5148.7
XS Rating Curve= 0 ,0
Exp/Cntr=0.3,0.1

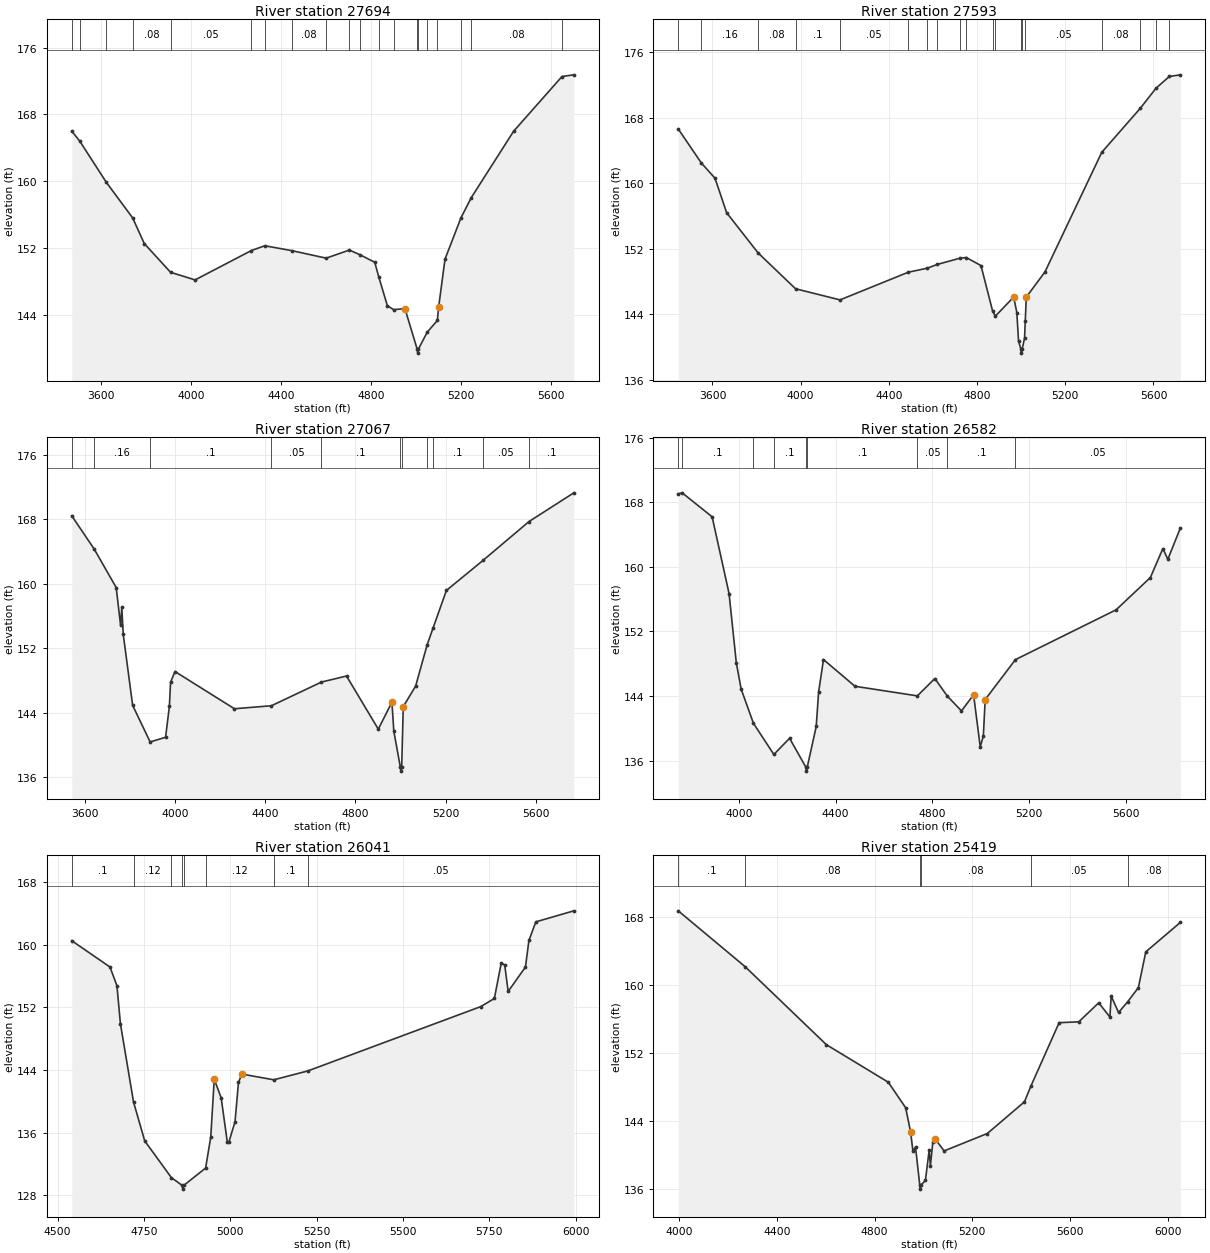
Type RM Length L Ch R = 1 ,27694   ,101,101,101
BEGIN DESCRIPTION:
UNT003 IN NURI 29.0
END DESCRIPTION:
XS GIS Cut Line= 3
      2280447.75     13309013.21      2279597.06     13309537.52
      2278645.93     13310322.02
#Sta/Elev= 30
  3470.3  166.01    3506  164.81  3623.5  159.91    3741  155.64  3792.5  152.58
  3909.6  149.14  4018.5  148.23  4268.7  151.74  4328.4  152.31  4448.2  151.73
  4601.5  150.83  4704.3   151.8  4751.3  151.24  4817.2  150.34  4834.8  148.63
  4873.2  145.16    4901  144.67  4951.4  144.81  5005.7  139.98  5008.5  139.48
  5011.7  139.98  5050.8  141.99  5095.7  143.38  5101.2  144.95  5129.8  150.72
  5200.5  155.64  5246.4  158.06  5434.8     166  5649.8  172.54  5702.5  172.74
#Mann= 20 ,-1 , 0
  3470.3     .05       0    3506      .1       0  3623.5     .16       0
    3741     .08       0  3909.6     .05       0  4268.7      .1       0
  4328.4     .05       0  4448.2     .08       0  4601.5      .1       0
  4704.3     .08       0  4751.3     .05       0  4834.8     .08       0
    4901     .05       0  5005.7     .07       0  5011.7     .08       0
  5050.8     .05       0  5095.7     .08       0  5200.5     .05       0
  5246.4     .08       0  5649.8     .05       0
Bank Sta=4951.4,5101.2
XS Rating Curve= 0 ,0
Exp/Cntr=0.3,0.1

Type RM Length L Ch R = 1 ,27593   ,526,526,526
BEGIN DESCRIPTION:
UNT003 IN NURI 28.0
END DESCRIPTION:
XS GIS Cut Line= 4
       2280409.9     13308979.84      2280131.78     13309141.68
      2279878.31     13309165.99      2278576.24     13310259.73
#Sta/Elev= 30
  3444.9  166.61  3549.9  162.45  3611.6   160.6  3664.5  156.38    3807  151.48
  3976.9   147.1  4178.5  145.74  4488.3  149.12  4574.1  149.61  4619.8  150.07
  4722.3  150.83  4751.4  150.91  4817.8  149.93  4870.6  144.38  4882.9  143.75
  4966.1  146.09  4980.4   144.2  4988.2  140.72  4998.6  139.74  5001.3  139.24
  5004.6  139.74  5015.5  141.08  5018.8   143.2  5023.3  146.08  5107.9  149.15
  5365.6  163.76  5540.5  169.14  5611.8  171.59    5672  173.02  5721.8  173.22
#Mann= 19 ,-1 , 0
  3444.9      .1       0  3549.9     .16       0    3807     .08       0
  3976.9      .1       0  4178.5     .05       0  4488.3      .1       0
  4574.1     .08       0  4619.8      .1       0  4722.3     .08       0
  4751.4      .1       0  4870.6     .08       0  4882.9      .1       0
  4998.6     .07       0  5004.6      .1       0  5018.8     .05       0
  5365.6     .08       0  5540.5     .05       0  5611.8     .08       0
    5672     .05       0
Bank Sta=4966.1,5023.3
XS Rating Curve= 0 ,0
Exp/Cntr=0.3,0.1

Type RM Length L Ch R = 1 ,27067   ,485,485,485
BEGIN DESCRIPTION:
Mapping XS 4a768bde
END DESCRIPTION:
XS GIS Cut Line= 3
      2280416.55     13308929.86       2279267.2     13309266.68
      2278246.41     13309377.79
#Sta/Elev= 30
  3543.4  168.42  3642.6   164.3  3740.2  159.52  3759.8  154.82    3765  157.08
  3771.4  153.72  3813.1   144.9  3890.7  140.36    3959  140.94  3975.9  144.76
  3981.1  147.76  4000.7   149.1    4264  144.48  4427.8  144.85  4649.6  147.79
  4760.7  148.54  4901.5  141.95  4961.9   145.3  4970.3   141.7  4999.1  137.24
  5001.8  136.74  5005.1  137.24  5012.2  144.75  5066.8  147.28  5117.5  152.37
  5144.1  154.49  5203.3  159.16  5365.7  162.89  5569.4  167.71  5767.9  171.27
#Mann= 11 ,-1 , 0
  3543.4      .1       0  3642.6     .16       0  3890.7      .1       0
  4427.8     .05       0  4649.6      .1       0  4999.1     .07       0
  5005.1      .1       0  5117.5     .05       0  5144.1      .1       0
  5365.7     .05       0  5569.4      .1       0
Bank Sta=4961.9,5012.2
XS Rating Curve= 0 ,0
Exp/Cntr=0.3,0.1

Type RM Length L Ch R = 1 ,26582   ,541,541,541
BEGIN DESCRIPTION:
UNT003 IN NURI 27.0
END DESCRIPTION:
XS GIS Cut Line= 3
       2280437.7     13308896.85      2279187.72     13308846.85
      2278387.72     13308646.85
#Sta/Elev= 30
  3749.6  169.04  3765.9  169.16  3889.7  166.19  3959.7  156.69  3989.8  148.08
  4009.8  144.84  4060.4  140.62  4144.9  136.75  4209.9  138.76    4277  135.19
  4279.8  134.69    4283  135.19    4320  140.22    4330   144.5  4350.1  148.51
  4480.2   145.2  4738.1  144.01  4810.4  146.16  4862.1  143.98  4920.5  142.15
  4970.6  144.15  4998.1   137.7  5010.9  139.05  5018.6  143.56  5143.5   148.5
  5559.8  154.67  5701.5  158.67    5753  162.25  5773.7  160.93  5825.2  164.79
#Mann= 9 ,-1 , 0
  3749.6     .05       0  3765.9      .1       0  4060.4     .16       0
  4144.9      .1       0    4277     .07       0    4283      .1       0
  4738.1     .05       0  4862.1      .1       0  5143.5     .05       0
Bank Sta=4970.6,5018.6
XS Rating Curve= 0 ,0
Exp/Cntr=0.3,0.1

Type RM Length L Ch R = 1 ,26041   ,622,622,622
BEGIN DESCRIPTION:
UNT003 IN NURI 26.0
END DESCRIPTION:
XS GIS Cut Line= 3
      2279937.75     13308346.85      2279487.72     13308396.85
      2278487.77     13308446.85
#Sta/Elev= 30
  4541.2  160.53  4651.9  157.17    4672  154.78  4682.1  149.92  4720.1  139.91
  4752.5  134.95  4829.7  130.26  4860.2  129.29  4862.9  128.79  4866.2  129.29
  4928.8  131.48  4943.7  135.44  4953.8  142.83  4973.9  140.45  4991.5  134.84
  4996.5  134.84    5014  137.41    5024  142.42    5034  143.49  5126.2  142.76
  5224.6  143.89  5724.9   152.1    5765  153.15    5785  157.68    5795  157.42
    5805  154.05  5855.1  157.17  5865.1  160.56  5885.1  162.94  5995.2  164.35
#Mann= 8 ,-1 , 0
  4541.2      .1       0  4720.1     .12       0  4829.7     .07       0
  4860.2     .07       0  4866.2     .07       0  4928.8     .12       0
  5126.2      .1       0  5224.6     .05       0
Bank Sta=4953.8,5034
XS Rating Curve= 0 ,0
Exp/Cntr=0.3,0.1

Type RM Length L Ch R = 1 ,25419   ,189,189,189
BEGIN DESCRIPTION:
UNT003 IN NURI 25.0
END DESCRIPTION:
XS GIS Cut Line= 2
      2280406.07     13307978.49      2278378.28     13307645.15
#Sta/Elev= 30
  3996.3  168.77  4269.9   162.2  4602.7  153.01    4856  148.59    4927  145.59
  4947.2  142.76  4957.1  140.44  4967.5  140.96  4984.8   136.5  4987.5     136
  4990.8   136.5    5008  137.03  5023.4  140.58  5028.5  138.78  5038.4  141.55
  5048.6  141.87  5084.6   140.5  5261.4  142.55  5413.4  146.28  5439.1  148.09
  5555.3   155.6  5635.7   155.7  5717.4  157.94  5763.2  156.26  5768.3  158.74
  5798.5   156.8  5835.2  158.04  5879.6  159.72    5910  163.94  6051.3   167.4
#Mann= 6 ,-1 , 0
  3996.3      .1       0  4269.9     .08       0  4984.8     .07       0
  4990.8     .08       0  5439.1     .05       0  5835.2     .08       0
Bank Sta=4947.2,5048.6
XS Rating Curve= 0 ,0
Exp/Cntr=0.3,0.1

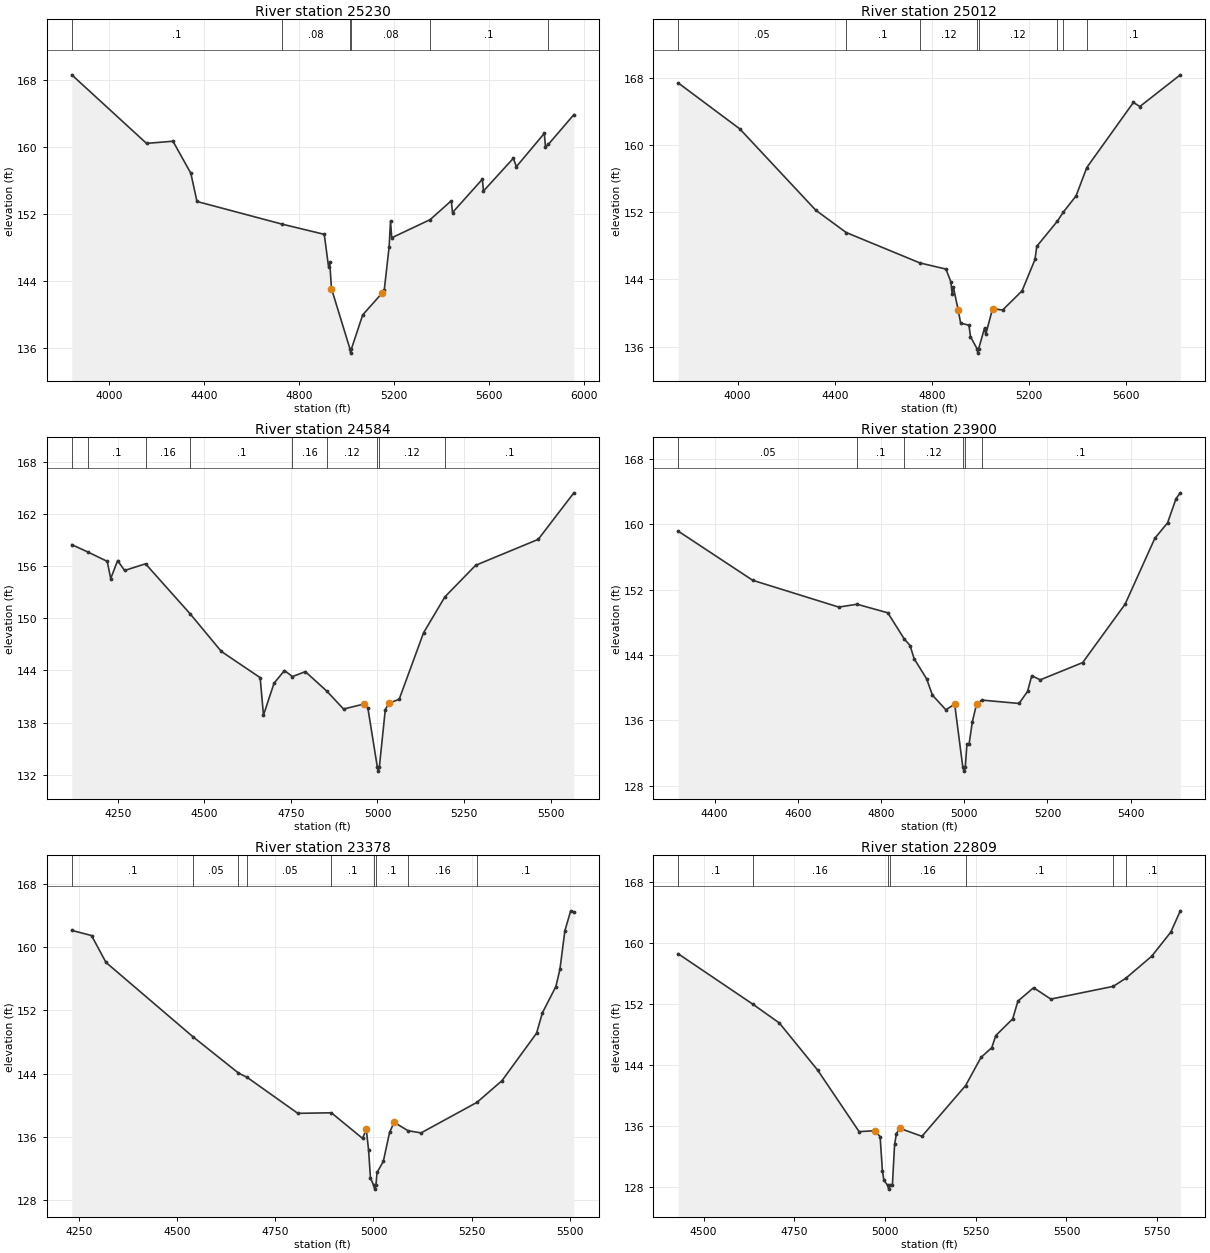
Type RM Length L Ch R = 1 ,25230   ,218,218,218
BEGIN DESCRIPTION:
Mapping XS a7935184
END DESCRIPTION:
XS GIS Cut Line= 2
      2280478.99     13307829.18      2278388.72     13307502.79
#Sta/Elev= 30
  3842.7  168.64  4157.7  160.46  4269.1  160.72  4344.4   156.9  4370.3  153.53
  4730.1  150.82  4906.7  149.61  4924.6  145.75  4929.6  146.27  4937.1  143.13
    5015  135.94  5017.8  135.44    5021  135.94  5068.6     140  5149.6  142.58
  5159.7  143.03    5180  148.13  5185.8  151.17  5190.9   149.2    5353  151.37
    5442  153.62    5447  152.21  5572.6  156.18  5577.6  154.78  5703.2  158.68
  5716.4  157.69  5833.8  161.66  5838.8  160.04  5850.5  160.33  5958.3  163.89
#Mann= 6 ,-1 , 0
  3842.7      .1       0  4730.1     .08       0    5015     .07       0
    5021     .08       0    5353      .1       0  5850.5     .08       0
Bank Sta=4937.1,5149.6
XS Rating Curve= 0 ,0
Exp/Cntr=0.3,0.1

Type RM Length L Ch R = 1 ,25012   ,428,428,428
BEGIN DESCRIPTION:
UNT003 IN NURI 24.0
END DESCRIPTION:
XS GIS Cut Line= 2
      2280458.13     13307648.62      2278413.03     13307343.07
#Sta/Elev= 30
  3755.5  167.45    4009  161.97  4322.1  152.26  4447.4   149.6  4751.1  145.97
    4858  145.24  4878.2  143.73  4883.7  142.27  4888.7  143.08  4908.6  140.32
  4918.7  138.79  4952.9  138.54  4959.1  137.18  4986.5  135.71  4989.2  135.21
  4992.5  135.71  5017.1  138.21  5022.1  137.45  5050.1  140.52  5091.4  140.35
  5171.5  142.64  5224.8  146.39  5232.1  147.95  5316.8  150.95  5341.8  152.05
  5393.9  153.97  5438.2  157.36    5630  165.12  5656.8  164.64  5823.3  168.42
#Mann= 8 ,-1 , 0
  3755.5     .05       0  4447.4      .1       0  4751.1     .12       0
  4986.5     .07       0  4992.5     .12       0  5316.8      .1       0
  5341.8     .12       0  5438.2      .1       0
Bank Sta=4908.6,5050.1
XS Rating Curve= 0 ,0
Exp/Cntr=0.3,0.1

Type RM Length L Ch R = 1 ,24584   ,684,684,684
BEGIN DESCRIPTION:
UNT003 IN NURI 23.0
END DESCRIPTION:
XS GIS Cut Line= 2
      2280029.71     13307137.31      2278585.22     13307019.25
#Sta/Elev= 30
  4117.6  158.46    4165   157.6  4219.9  156.54    4230  154.56    4250  156.63
  4270.1  155.49  4330.5  156.26  4459.9  150.48  4549.4  146.18  4661.4  143.17
    4671  138.86  4701.5  142.53  4731.6  143.99  4754.7  143.29  4791.8  143.86
    4853  141.65  4902.2  139.56  4962.4  140.15  4972.4  139.66  4999.5  132.92
  5002.3  132.42  5005.5  132.92  5022.6  139.48  5032.6  140.23  5062.7  140.68
    5133  148.32  5194.5  152.45  5283.5  156.09  5464.1  159.07  5566.9  164.42
#Mann= 9 ,-1 , 0
  4117.6     .05       0    4165      .1       0  4330.5     .16       0
  4459.9      .1       0  4754.7     .16       0    4853     .12       0
  4999.5     .07       0  5005.5     .12       0  5194.5      .1       0
Bank Sta=4962.4,5032.6
XS Rating Curve= 0 ,0
Exp/Cntr=0.3,0.1

Type RM Length L Ch R = 1 ,23900   ,522,522,522
BEGIN DESCRIPTION:
UNT003 IN NURI 22.0
END DESCRIPTION:
XS GIS Cut Line= 3
      2279837.69     13306146.87      2279187.72     13306396.85
      2278687.71     13306496.86
#Sta/Elev= 30
  4312.8  159.15  4491.7  153.14  4698.5  149.86  4742.4  150.21  4816.3  149.16
  4855.6  145.98  4869.9  145.15  4879.5  143.55  4909.5  141.09  4923.5  139.09
  4955.6   137.3    4977  137.97  4996.5  130.29  4999.3  129.79  5002.5  130.29
  5006.5  133.13  5011.7  133.13  5019.4  135.81  5029.6  138.01  5042.4  138.48
  5131.6  138.07    5152  139.54  5162.2  141.46  5182.6  140.96  5284.5  143.07
  5386.5  150.22  5457.9  158.28  5488.5  160.17  5508.9  163.14  5519.1  163.84
#Mann= 6 ,-1 , 0
  4312.8     .05       0  4742.4      .1       0  4855.6     .12       0
  4996.5     .07       0  5002.5     .12       0  5042.4      .1       0
Bank Sta=4977,5029.6
XS Rating Curve= 0 ,0
Exp/Cntr=0.3,0.1

Type RM Length L Ch R = 1 ,23378   ,569,569,569
BEGIN DESCRIPTION:
UNT003 IN NURI 21.0
END DESCRIPTION:
XS GIS Cut Line= 3
      2279337.74     13305296.82      2278937.72     13305946.85
      2278687.74     13306396.82
#Sta/Elev= 30
    4232  162.09  4282.3  161.44    4319  158.05    4540  148.68  4656.3  144.08
  4678.8  143.52  4807.4  138.99  4892.8  139.06  4972.1  135.83  4981.7  136.95
  4987.6  134.32  4992.3  130.82  5000.3  129.92    5003  129.42  5006.3  129.92
    5009  131.52    5025  132.92    5041  136.59  5052.5  137.86  5087.8   136.8
  5121.1  136.52  5263.5  140.38    5327  143.11  5415.1  149.11    5430  151.69
  5464.3     155  5474.6  157.19  5487.2  162.05    5502  164.56    5510  164.42
#Mann= 9 ,-1 , 0
    4232      .1       0    4540     .05       0  4656.3      .1       0
  4678.8     .05       0  4892.8      .1       0  5000.3     .07       0
  5006.3      .1       0  5087.8     .16       0  5263.5      .1       0
Bank Sta=4981.7,5052.5
XS Rating Curve= 0 ,0
Exp/Cntr=0.3,0.1

Type RM Length L Ch R = 1 ,22809   ,552,552,552
BEGIN DESCRIPTION:
UNT003 IN NURI 20.0
END DESCRIPTION:
XS GIS Cut Line= 3
      2278887.72     13305096.86      2278537.72     13305546.85
      2278387.72     13306346.83
#Sta/Elev= 30
  4429.9  158.55  4635.9  151.94  4708.6  149.49  4814.5   143.3  4928.5  135.26
  4971.9  135.38  4986.4   134.6  4992.7  130.15  4996.8  128.89  5007.2  128.23
  5009.9  127.73  5013.2  128.23  5020.3  128.32  5026.3  133.58  5031.4  135.01
  5040.7  135.69  5101.7  134.65  5222.1   141.3  5264.5  144.98  5294.2  146.26
  5305.2  147.84  5351.8  150.03  5366.3  152.36  5409.5  154.11    5457  152.62
  5629.2  154.29    5664  155.36  5735.1  158.24  5787.6  161.39  5813.9  164.18
#Mann= 7 ,-1 , 0
  4429.9      .1       0  4635.9     .16       0  5007.2     .07       0
  5013.2     .16       0  5222.1      .1       0  5629.2     .16       0
    5664      .1       0
Bank Sta=4971.9,5040.7
XS Rating Curve= 0 ,0
Exp/Cntr=0.3,0.1

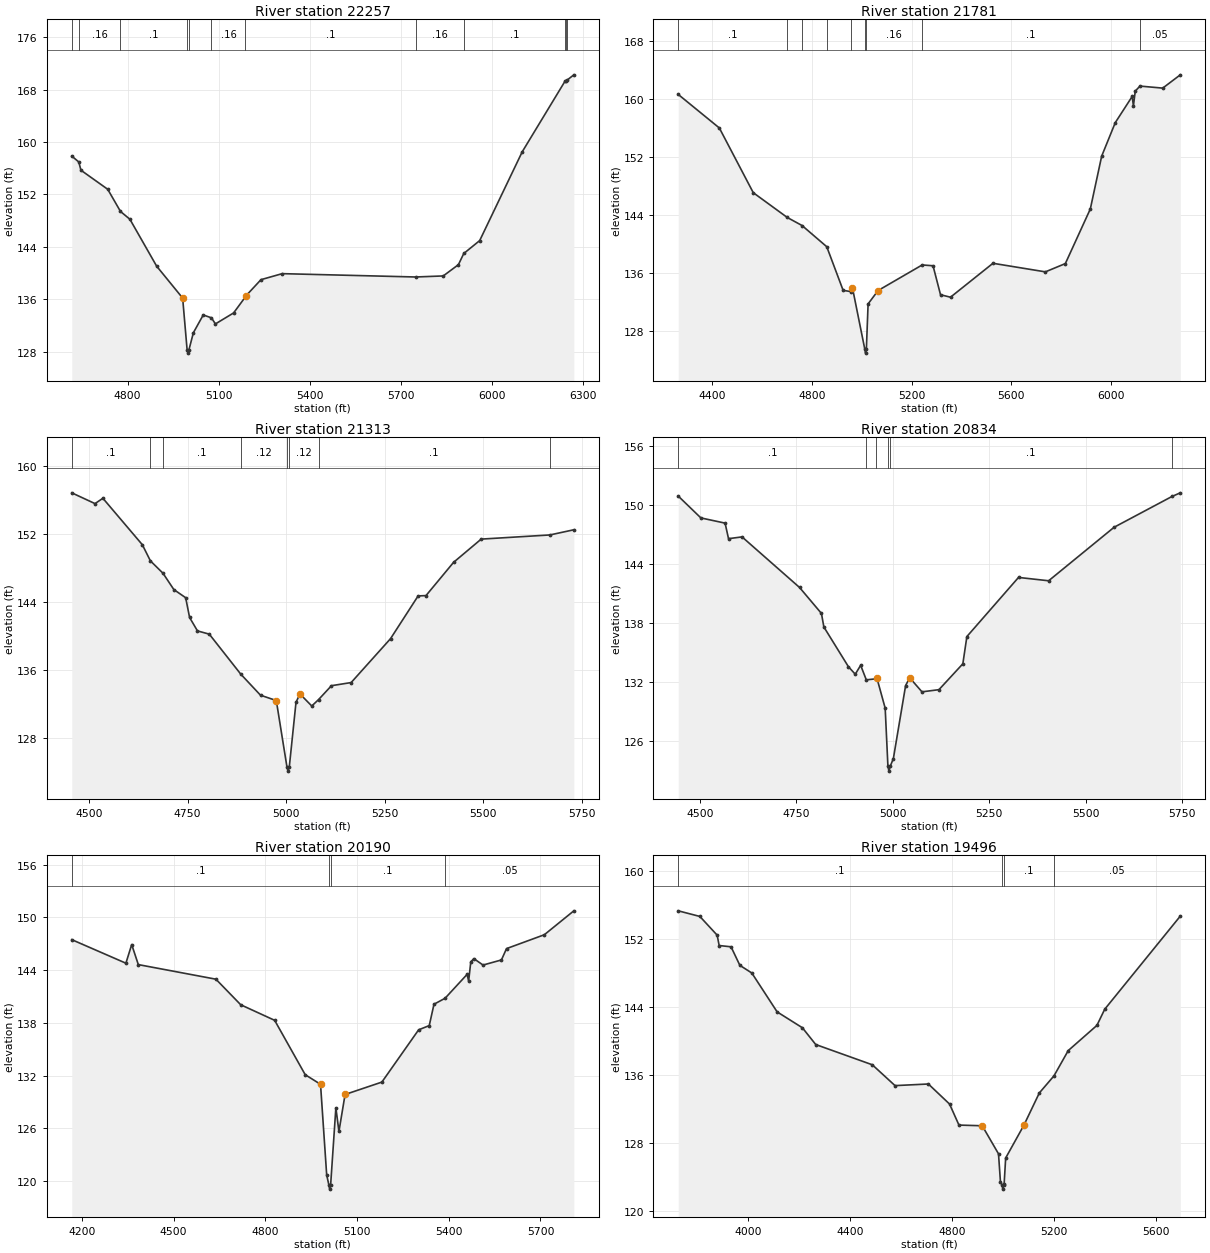
Type RM Length L Ch R = 1 ,22257   ,476,476,476
BEGIN DESCRIPTION:
UNT003 IN NURI 19.0
END DESCRIPTION:
XS GIS Cut Line= 3
      2278037.72     13304896.86      2278087.72     13305296.85
      2278137.72     13306546.84
#Sta/Elev= 30
  4616.2  157.86  4639.3  156.96  4646.4   155.7  4734.6  152.79  4776.7   149.4
  4807.7  148.21  4895.9  141.04  4981.5  136.17  4996.2  128.26  4998.9  127.76
  5002.2  128.26  5016.8  130.87  5049.3  133.59  5076.4  133.15  5089.4  132.22
  5149.4   133.9  5187.9  136.33  5189.4  136.48  5239.5  138.98  5309.5   139.9
  5748.9  139.39    5840  139.55    5890  141.27  5907.7  142.98  5960.1  144.95
  6100.2  158.51  6241.1  169.29  6243.6  169.35    6248  169.46  6270.3  170.27
#Mann= 12 ,-1 , 0
  4616.2      .1       0  4639.3     .16       0  4776.7      .1       0
  4996.2     .07       0  5002.2      .1       0  5076.4     .16       0
  5187.9      .1       0  5748.9     .16       0  5907.7      .1       0
  6241.1     .16       0  6243.6      .1       0    6248     .16       0
Bank Sta=4981.5,5189.4
XS Rating Curve= 0 ,0
Exp/Cntr=0.3,0.1

Type RM Length L Ch R = 1 ,21781   ,468,468,468
BEGIN DESCRIPTION:
UNT003 IN NURI 18.0
END DESCRIPTION:
XS GIS Cut Line= 3
      2277731.05     13304658.13       2277599.1     13304908.14
      2277737.99     13306637.28
#Sta/Elev= 30
  4262.5  160.63  4427.7  156.01    4564   147.1  4700.6  143.69    4760  142.58
  4859.3  139.66  4925.1  133.65  4958.6  133.47  4962.7  133.97  5012.4  125.51
  5015.2  125.01  5018.4  125.51  5025.4  131.79  5065.6  133.63  5242.6  137.15
  5286.3  137.04  5316.4  133.05  5356.5  132.71  5527.1  137.38  5737.7   136.2
    5818  137.34  5918.3  144.86  5963.9  152.13  6018.6  156.75  6086.5  160.35
  6091.5  159.06  6098.9  161.09  6117.8  161.78  6209.2   161.5  6279.9  163.33
#Mann= 9 ,-1 , 0
  4262.5      .1       0  4700.6     .16       0    4760      .1       0
  4859.3     .12       0  4958.6     .16       0  5012.4     .07       0
  5018.4     .16       0  5242.6      .1       0  6117.8     .05       0
Bank Sta=4962.7,5065.6
XS Rating Curve= 0 ,0
Exp/Cntr=0.3,0.1

Type RM Length L Ch R = 1 ,21313   ,479,479,479
BEGIN DESCRIPTION:
UNT003 IN NURI 17.0
END DESCRIPTION:
XS GIS Cut Line= 2
      2277187.34     13304877.83      2277159.56     13306152.02
#Sta/Elev= 30
    4456  156.83    4515  155.56    4535  156.19  4635.1  150.72  4655.6  148.82
  4687.6  147.36  4715.1  145.44  4745.1  144.48  4755.1  142.15  4775.1  140.57
  4805.1  140.19    4885  135.48  4935.1     133  4975.2  132.37  5002.2  124.56
  5004.9  124.06  5008.2  124.56  5025.2  132.16  5035.2  133.15  5065.2  131.73
  5082.4  132.48  5115.2  134.12  5165.2  134.49  5265.2  139.66  5335.2  144.69
  5355.2  144.73  5425.3  148.65  5495.3  151.38  5669.7  151.87  5730.5  152.48
#Mann= 8 ,-1 , 0
    4456      .1       0  4655.6     .16       0  4687.6      .1       0
    4885     .12       0  5002.2     .07       0  5008.2     .12       0
  5082.4      .1       0  5669.7     .05       0
Bank Sta=4975.2,5035.2
XS Rating Curve= 0 ,0
Exp/Cntr=0.3,0.1

Type RM Length L Ch R = 1 ,20834   ,644,644,644
BEGIN DESCRIPTION:
UNT003 IN NURI 16.0
END DESCRIPTION:
XS GIS Cut Line= 3
      2276697.75     13304919.47      2276628.31      13305238.9
      2276951.24     13306159.09
#Sta/Elev= 30
  4443.5  150.89  4502.2  148.67    4565  148.14  4573.9  146.56    4609  146.74
  4758.1   141.6  4814.9  138.96  4821.2  137.58  4884.8  133.55  4902.6  132.78
  4916.6  133.69  4931.2  132.21    4956  132.31    4959  132.35  4980.2  129.33
  4987.3  123.43    4990  122.93  4993.3  123.43  5001.4   124.2  5033.2  131.63
  5043.8  132.42  5075.6  130.99  5119.6  131.21  5181.6  133.84  5192.1  136.61
    5326  142.62  5404.1  142.28  5573.9  147.72    5724  150.85  5745.6  151.22
#Mann= 6 ,-1 , 0
  4443.5      .1       0  4931.2     .16       0    4956      .1       0
  4987.3     .07       0  4993.3      .1       0    5724     .05       0
Bank Sta=4959,5043.8
XS Rating Curve= 0 ,0
Exp/Cntr=0.3,0.1

Type RM Length L Ch R = 1 ,20190   ,694,694,694
BEGIN DESCRIPTION:
UNT003 IN NURI 15.0
END DESCRIPTION:
XS GIS Cut Line= 3
      2276187.33     13304742.41      2276086.64     13305315.29
      2276169.88     13306373.06
#Sta/Elev= 30
  4166.6  147.47  4343.7  144.79  4362.7  146.91  4384.3  144.63  4638.2  142.97
  4719.4  140.06  4830.4  138.29  4930.4   132.1  4980.5  131.01  5000.6  120.71
  5007.6  119.58  5010.4  119.08  5013.6  119.58  5030.7  128.34  5040.7  125.64
  5060.8  129.85  5181.2  131.26  5301.5  137.21  5336.2  137.69  5351.7  140.12
    5388   140.8  5460.1  143.52  5465.1  142.76  5472.1  144.94  5482.1  145.31
  5512.2  144.58  5572.4  145.16    5589  146.45  5712.8  148.03  5809.3  150.75
#Mann= 4 ,-1 , 0
  4166.6      .1       0  5007.6     .07       0  5013.6      .1       0
    5388     .05       0
Bank Sta=4980.5,5060.8
XS Rating Curve= 0 ,0
Exp/Cntr=0.3,0.1

Type RM Length L Ch R = 1 ,19496   ,487,487,487
BEGIN DESCRIPTION:
UNT003 IN NURI 14.0
END DESCRIPTION:
XS GIS Cut Line= 3
      2275937.73     13304496.82      2275437.72     13305646.85
      2275287.72     13306346.84
#Sta/Elev= 30
  3726.6  155.33  3811.4  154.67  3879.3  152.47  3887.2  151.25  3933.8   151.1
  3968.4  148.92  4015.3  148.02  4114.6  143.45  4213.8  141.58  4266.1  139.61
    4488  137.23  4577.2  134.78    4708  134.97  4791.2  132.61    4828  130.14
  4919.3  130.06  4983.2  126.76  4990.9  123.42  4997.2  123.11    5000  122.61
  5003.2  123.11  5005.3  123.24  5011.3  126.27  5082.9  130.13  5143.4  133.92
  5200.9  135.93  5256.8   138.9  5369.3  141.86  5399.9  143.76  5696.5  154.71
#Mann= 4 ,-1 , 0
  3726.6      .1       0  4997.2     .07       0  5003.2      .1       0
  5200.9     .05       0
Bank Sta=4919.3,5082.9
XS Rating Curve= 0 ,0
Exp/Cntr=0.3,0.1