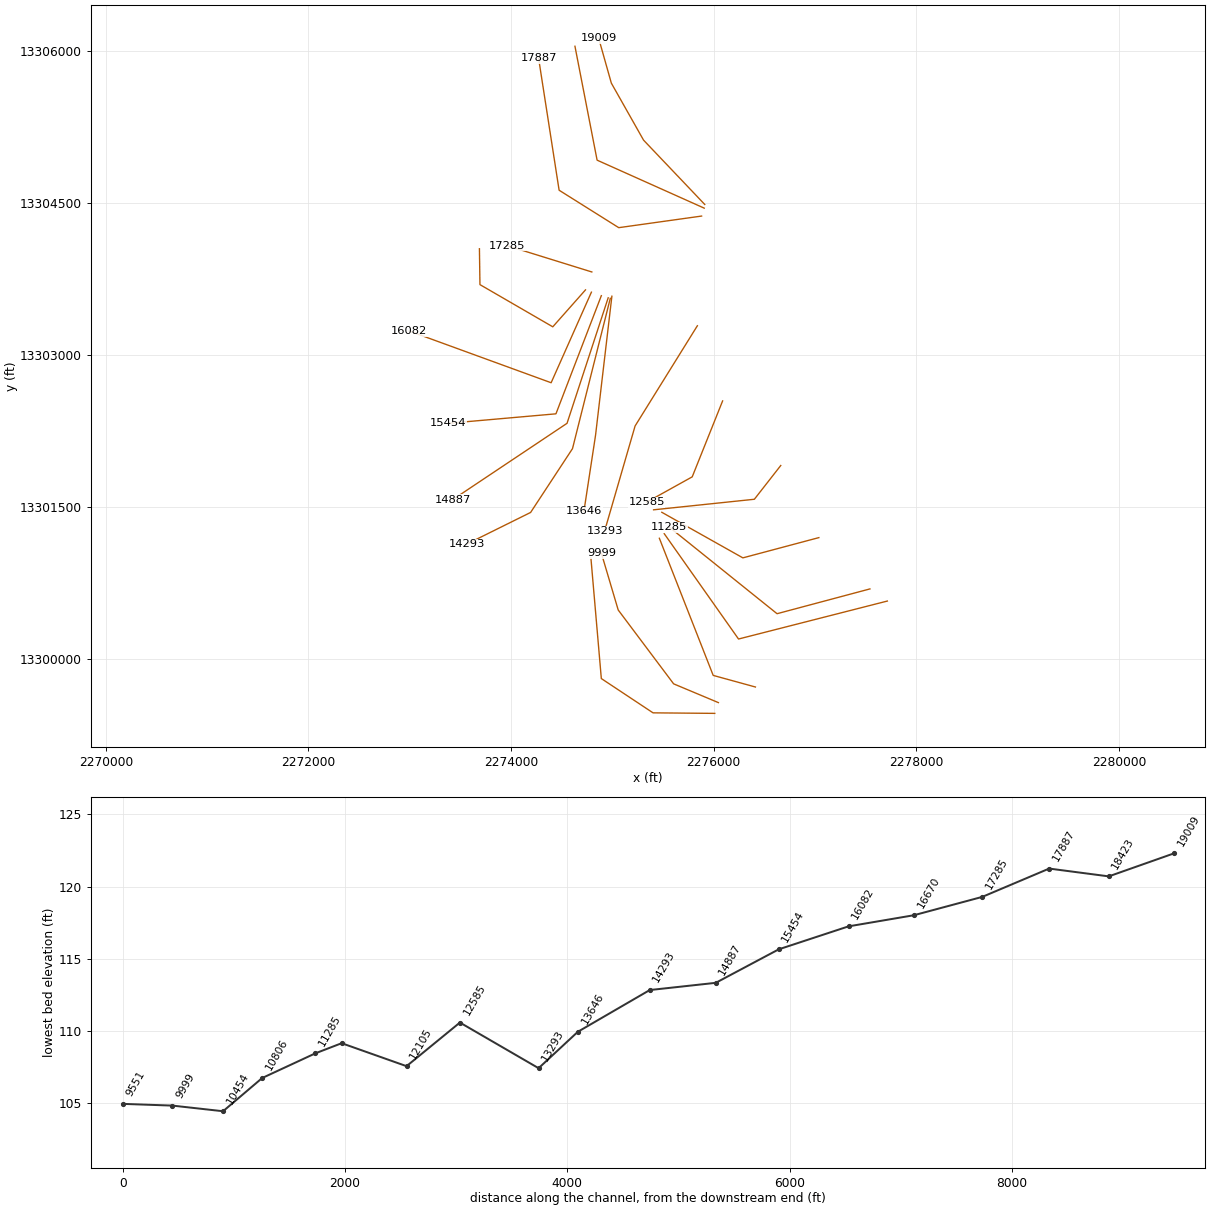
HEC-RAS study UNT003 IN NURI.prj: UNT003 IN NURI Base Level Engineering

--- UNT003 IN NURI.g01 (geometry) --- (continued)

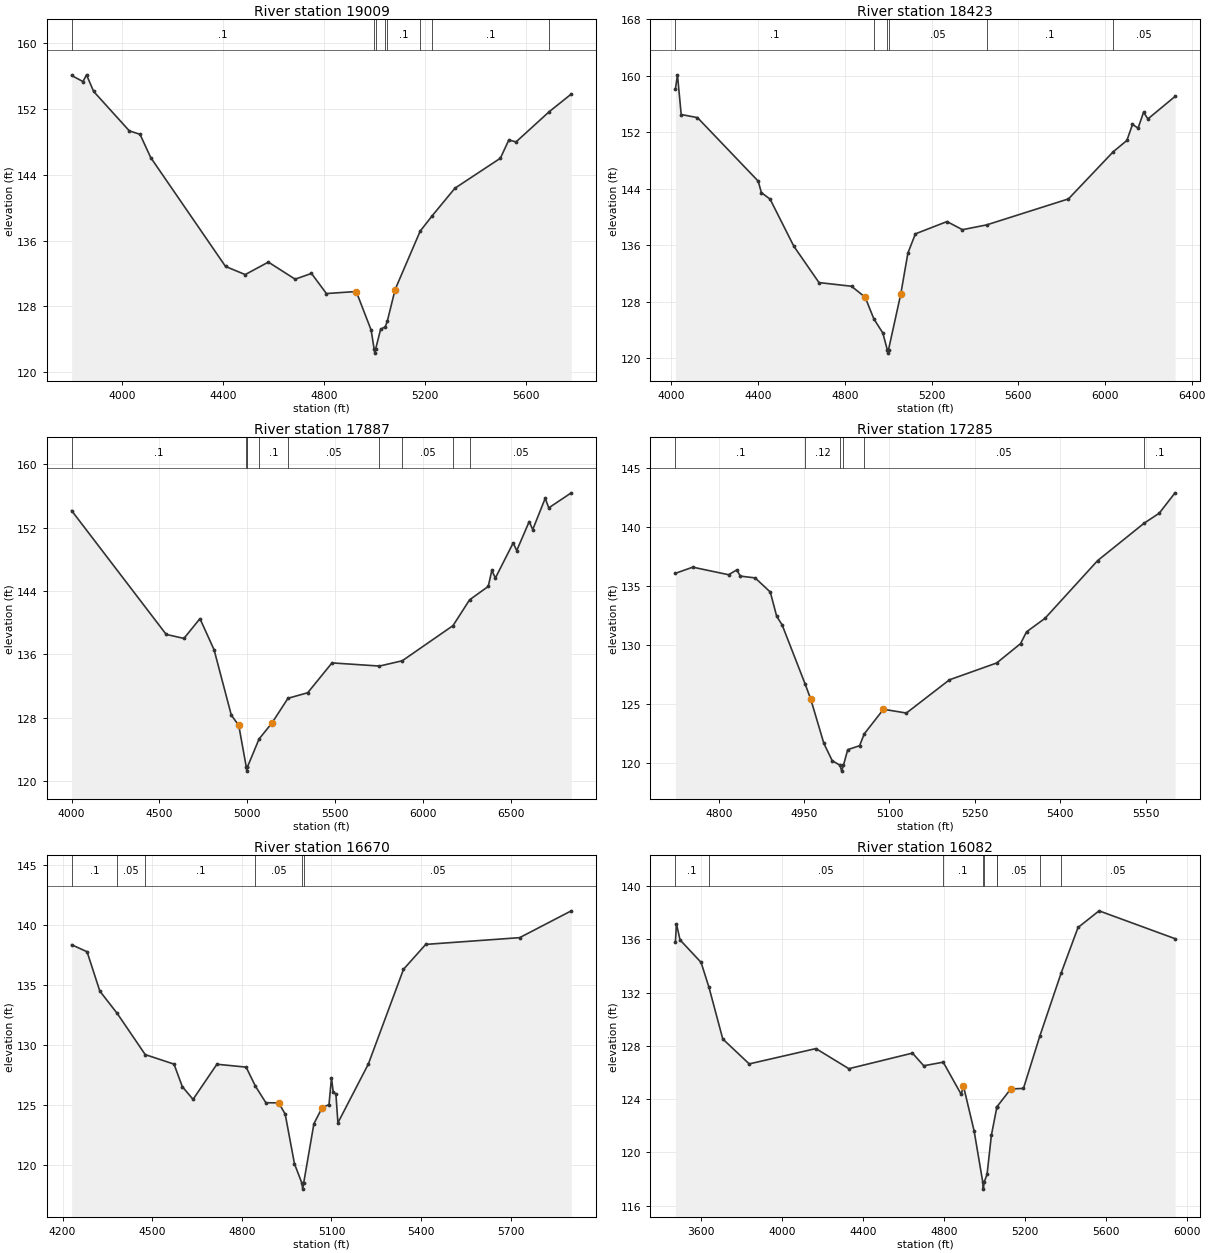
Type RM Length L Ch R = 1 ,19009   ,586,586,586
BEGIN DESCRIPTION:
Mapping XS 26cf4243
END DESCRIPTION:
XS GIS Cut Line= 4
      2275911.48     13304487.09      2275307.34     13305122.48
      2274989.64     13305684.98      2274864.63     13306127.69
#Sta/Elev= 30
  3798.6  156.09  3843.5  155.35  3857.6  156.17  3885.9  154.15  4027.5  149.35
  4069.9  148.93  4112.4   146.1  4409.3  132.85  4487.4  131.86  4579.2  133.38
  4685.4   131.3  4750.4     132  4809.6  129.55    4928   129.8  4987.2   125.1
    4999   122.8  5001.7   122.3    5005   122.8  5024.8  125.21  5043.5  125.51
  5051.9  126.26  5082.3  130.04  5181.8  137.15  5229.8  139.03  5319.6  142.37
    5500  146.02  5533.6  148.24  5562.3  148.01  5694.1  151.69  5781.4  153.83
#Mann= 8 ,-1 , 0
  3798.6      .1       0    4999     .07       0    5005      .1       0
  5043.5     .05       0  5051.9      .1       0  5181.8     .05       0
  5229.8      .1       0  5694.1     .05       0
Bank Sta=4928,5082.3
XS Rating Curve= 0 ,0
Exp/Cntr=0.3,0.1

Type RM Length L Ch R = 1 ,18423   ,536,536,536
BEGIN DESCRIPTION:
Mapping XS 042210d4
END DESCRIPTION:
XS GIS Cut Line= 3
       2275906.3      13304450.6      2274849.01     13304924.56
      2274630.27     13306049.53
#Sta/Elev= 30
  4018.7   158.1  4028.1  160.12  4045.4   154.5  4120.4  154.06  4400.7  145.06
    4415  143.45  4455.5  142.51  4565.1  135.84    4681   130.7    4831  130.18
  4893.8  128.63  4934.3  125.55  4975.6  123.55  4995.8  121.21  4998.5  120.71
  5001.8  121.21  5058.2  129.07  5091.1  134.88  5125.7   137.6  5271.4  139.34
  5342.7  138.19  5454.4  138.87  5831.7  142.55  6038.4  149.23  6101.3  150.83
  6127.1   153.1    6153  152.57  6178.1  154.82  6198.4  153.88  6323.4  157.06
#Mann= 6 ,-1 , 0
  4018.7      .1       0  4934.3     .05       0  4995.8     .03       0
  5001.8     .05       0  5454.4      .1       0  6038.4     .05       0
Bank Sta=4893.8,5058.2
XS Rating Curve= 0 ,0
Exp/Cntr=0.3,0.1

Type RM Length L Ch R = 1 ,17887   ,602,602,602
BEGIN DESCRIPTION:
Mapping XS 20389838
END DESCRIPTION:
XS GIS Cut Line= 4
      2275880.29     13304372.48      2275062.55     13304257.89
      2274474.01     13304627.69      2274271.13     13305933.42
#Sta/Elev= 30
  4000.7  154.15  4538.5  138.52  4639.4  138.01  4730.6  140.51  4811.1  136.57
    4909  128.32  4951.4  127.02  4994.3  121.75  4997.1  121.25  5000.3  121.75
  5000.6  121.77  5066.8  125.31  5139.9  127.32  5231.3  130.45  5343.6  131.15
  5481.7  134.92  5751.9  134.52  5881.6  135.19  6170.2  139.63  6264.5  142.89
  6370.7  144.58    6391   146.6  6411.2  145.64  6512.4  150.07  6532.7  149.11
  6603.5  152.77  6623.7  151.76  6694.6  155.71  6714.8   154.5  6842.9   156.4
#Mann= 10 ,-1 , 0
  4000.7      .1       0  4994.3     .07       0  5000.3      .1       0
  5000.6     .05       0  5066.8      .1       0  5231.3     .05       0
  5751.9      .1       0  5881.6     .05       0  6170.2      .1       0
  6264.5     .05       0
Bank Sta=4951.4,5139.9
XS Rating Curve= 0 ,0
Exp/Cntr=0.3,0.1

Type RM Length L Ch R = 1 ,17285   ,615,615,615
BEGIN DESCRIPTION:
Mapping XS 8f005d83
END DESCRIPTION:
XS GIS Cut Line= 2
      2274796.89      13303820.4       2273958.4     13304080.81
#Sta/Elev= 30
  4723.9  136.08  4754.4   136.6  4817.3  135.96  4831.5  136.36  4838.2  135.84
    4864  135.69  4890.6  134.49  4901.8  132.44  4911.5  131.69  4951.9  126.68
  4961.7   125.4  4984.8  121.64  4999.5  120.17  5013.2  119.79    5016  119.29
  5019.2  119.79  5026.7  121.11  5047.6  121.45  5055.7  122.45  5089.5  124.54
  5129.8  124.22  5205.4  127.04  5288.5  128.47  5330.4  130.11  5340.9  131.11
  5373.4  132.26  5465.9  137.16  5547.5  140.33  5574.1  141.18  5601.9  142.91
#Mann= 6 ,-1 , 0
  4723.9      .1       0  4951.9     .12       0  5013.2     .07       0
  5019.2     .12       0  5055.7     .05       0  5547.5      .1       0
Bank Sta=4961.7,5089.5
XS Rating Curve= 0 ,0
Exp/Cntr=0.3,0.1

Type RM Length L Ch R = 1 ,16670   ,588,588,588
BEGIN DESCRIPTION:
Mapping XS 0496f04e
END DESCRIPTION:
XS GIS Cut Line= 4
      2274734.45     13303643.33      2274411.51     13303278.73
      2273692.76     13303695.39      2273687.55     13304049.61
#Sta/Elev= 30
  4230.5  138.33  4282.1  137.75  4324.8  134.48  4383.1  132.62  4476.8   129.2
  4573.1  128.41  4600.8  126.54  4636.8  125.48  4716.6   128.4  4814.4  128.16
  4845.7  126.57  4880.6   125.2  4923.7  125.19  4945.2  124.25  4976.2  120.13
    5001  118.52  5003.8  118.02    5007  118.52  5041.3  123.46  5068.7  124.78
  5091.8  125.05  5100.1  127.25  5105.9  126.09  5114.9  125.93  5121.6  123.53
  5223.5  128.42  5341.1  136.29  5415.5  138.36  5729.8  138.92  5902.6  141.15
#Mann= 6 ,-1 , 0
  4230.5      .1       0  4383.1     .05       0  4476.8      .1       0
  4845.7     .05       0    5001    .035       0    5007     .05       0
Bank Sta=4923.7,5068.7
XS Rating Curve= 0 ,0
Exp/Cntr=0.3,0.1

Type RM Length L Ch R = 1 ,16082   ,628,628,628
BEGIN DESCRIPTION:
UNT003 IN NURI 13.0
END DESCRIPTION:
XS GIS Cut Line= 3
      2274792.81     13303620.81      2274395.27     13302726.34
      2272994.83     13303237.07
#Sta/Elev= 30
  3471.9  135.79  3476.9  137.17  3494.7  135.96  3598.7  134.27  3637.9  132.39
    3706  128.52  3836.7  126.65  4166.3   127.8  4329.1  126.29  4643.5  127.46
  4699.3  126.51  4795.6  126.78  4884.5  124.36  4895.2  125.01  4948.4  121.61
  4991.3  117.75    4994  117.25  4997.3  117.75  5012.3  118.36  5033.6  121.29
  5060.9  123.42  5061.2  123.43  5061.5  123.44  5129.4  124.77  5192.2  124.81
  5272.6  128.72  5378.2  133.46  5461.9  136.89  5565.8  138.14  5941.4  136.05
#Mann= 10 ,-1 , 0
  3471.9      .1       0  3637.9     .05       0  4795.6      .1       0
  4991.3     .07       0  4997.3      .1       0  5060.9     .05       0
  5061.2      .1       0  5061.5     .05       0  5272.6      .1       0
  5378.2     .05       0
Bank Sta=4895.2,5129.4
XS Rating Curve= 0 ,0
Exp/Cntr=0.3,0.1

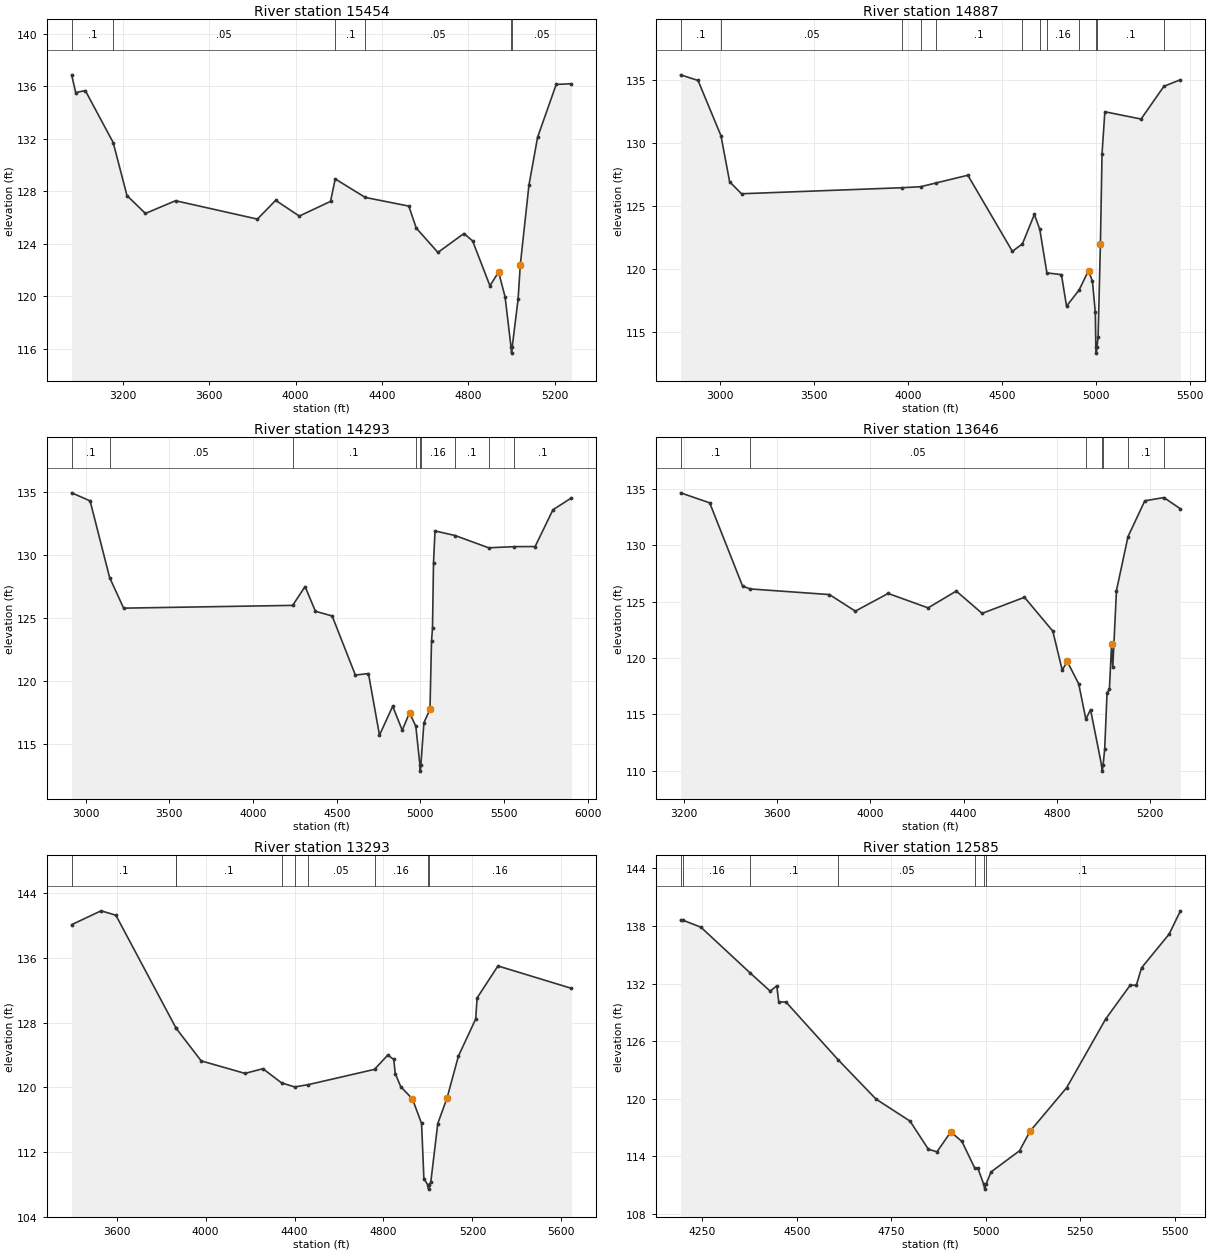
Type RM Length L Ch R = 1 ,15454   ,567,567,567
BEGIN DESCRIPTION:
Mapping XS 78bfc46c
END DESCRIPTION:
XS GIS Cut Line= 3
      2274890.67     13303585.99      2274442.76     13302419.35
      2273381.45     13302325.71
#Sta/Elev= 30
  2962.4  136.86  2981.1  135.51  3025.7  135.66  3154.8   131.7  3218.6  127.66
  3304.2   126.3  3443.5  127.27  3822.7  125.87  3907.4   127.3  4016.7   126.1
  4161.5  127.22  4183.1  128.93  4322.5  127.52  4524.1  126.86  4558.4  125.19
  4658.8  123.33  4779.3  124.77  4819.5  124.21  4899.8  120.79  4939.9  121.84
    4970  119.94  4997.2  116.16  4999.9  115.66  5003.2  116.16  5030.3  119.78
  5040.3  122.37  5080.5  128.46  5120.6  132.11  5206.8  136.13  5277.5  136.18
#Mann= 6 ,-1 , 0
  2962.4      .1       0  3154.8     .05       0  4183.1      .1       0
  4322.5     .05       0  4997.2     .03       0  5003.2     .05       0
Bank Sta=4939.9,5040.3
XS Rating Curve= 0 ,0
Exp/Cntr=0.3,0.1

Type RM Length L Ch R = 1 ,14887   ,594,594,594
BEGIN DESCRIPTION:
UNT003 IN NURI 12.0
END DESCRIPTION:
XS GIS Cut Line= 3
      2274958.39     13303565.21      2274552.14      13302325.6
      2273423.41     13301571.39
#Sta/Elev= 30
  2788.2  135.43  2881.2  134.98  3003.1   130.6  3049.5  126.94  3112.7  125.99
  3969.2  126.47  4066.6  126.55    4147  126.84    4318  127.46  4555.2  121.42
  4608.7  122.01  4672.3  124.35  4701.2  123.17    4739  119.71  4816.5  119.57
  4843.7  117.07  4910.5  118.35  4960.7  119.89  4981.7  119.03  4996.7  116.61
  4999.7  113.84  5002.5  113.34  5005.7  113.84  5011.7  114.59  5024.1  122.02
  5032.7  129.16  5047.7   132.5  5240.6  131.92  5362.3  134.52  5450.2  135.04
#Mann= 12 ,-1 , 0
  2788.2      .1       0  3003.1     .05       0  3969.2      .1       0
  4066.6     .05       0    4147      .1       0  4608.7     .16       0
  4701.2      .1       0    4739     .16       0  4910.5      .1       0
  4999.7     .07       0  5005.7      .1       0  5362.3     .16       0
Bank Sta=4960.7,5024.1
XS Rating Curve= 0 ,0
Exp/Cntr=0.3,0.1

Type RM Length L Ch R = 1 ,14293   ,647,647,647
BEGIN DESCRIPTION:
Mapping XS a770fd44
END DESCRIPTION:
XS GIS Cut Line= 4
      2274979.23     13303560.02      2274606.18     13302075.61
      2274192.76     13301445.39      2273562.66     13301132.95
#Sta/Elev= 30
  2915.8  134.97    3026  134.33  3142.8  128.23  3226.5   125.8  4236.8  126.02
    4311  127.52  4372.9  125.55  4472.8  125.18  4611.6  120.48  4689.9   120.6
  4755.8   115.7  4834.6     118  4891.8  116.09  4935.2  117.48    4973  116.41
  4997.3  113.34  5000.1  112.84  5003.3  113.34  5021.4  116.69  5057.6  117.76
  5066.7  123.15  5072.7  124.23  5078.7  129.41  5087.7  131.94    5209  131.57
  5407.8   130.6  5559.7  130.69    5686   130.7  5792.5  133.62  5903.4  134.57
#Mann= 9 ,-1 , 0
  2915.8      .1       0  3142.8     .05       0  4236.8      .1       0
    4973     .16       0  4997.3     .07       0  5003.3     .16       0
    5209      .1       0  5407.8     .05       0  5559.7      .1       0
Bank Sta=4935.2,5057.6
XS Rating Curve= 0 ,0
Exp/Cntr=0.3,0.1

Type RM Length L Ch R = 1 ,13646   ,353,353,353
BEGIN DESCRIPTION:
Mapping XS 3a72213d
END DESCRIPTION:
XS GIS Cut Line= 3
      2274994.84      13303580.8      2274833.39     13302205.81
      2274718.81     13301455.85
#Sta/Elev= 30
  3186.5  134.65  3311.3  133.76  3452.3  126.37  3485.4  126.12  3824.8  125.62
  3935.6  124.15  4076.5  125.72  4247.7  124.44  4368.5  125.93  4479.3  123.95
  4660.9  125.38  4782.3  122.38  4822.8  118.91  4844.1  119.69  4893.6  117.69
  4924.1  114.56  4944.2  115.41  4991.8  110.45  4994.5  109.95  4997.8  110.45
  5004.9   111.9    5015  116.92  5025.1  117.21  5034.5  121.21  5039.6  119.18
  5055.4  125.98  5104.8  130.76  5176.8  133.94  5258.7  134.23  5329.6  133.23
#Mann= 7 ,-1 , 0
  3186.5      .1       0  3485.4     .05       0  4924.1     .16       0
  4991.8     .07       0  4997.8     .16       0  5104.8      .1       0
  5258.7     .16       0
Bank Sta=4844.1,5034.5
XS Rating Curve= 0 ,0
Exp/Cntr=0.3,0.1

Type RM Length L Ch R = 1 ,13293   ,708,708,708
BEGIN DESCRIPTION:
UNT003 IN NURI 11.0
END DESCRIPTION:
XS GIS Cut Line= 3
      2275838.58     13303289.12      2275224.01     13302299.56
      2274922.33     13301259.29
#Sta/Elev= 30
  3397.7  140.11  3529.9  141.82  3596.5  141.28  3867.7   127.3    3868  127.29
  3980.2  123.28  4177.3  121.73  4257.8  122.31  4341.7  120.56  4400.6  120.06
  4460.1  120.33  4759.8  122.23  4819.5     124  4846.5  123.45  4853.1  121.71
  4877.7   120.1  4930.6  118.56  4971.5  115.54  4981.9  108.72    5000  107.93
  5002.7  107.43    5006  107.93  5013.1  108.34  5044.3  115.53    5086  118.69
  5137.2  123.87  5214.8  128.45  5221.3  131.06    5315  135.01  5645.7  132.24
#Mann= 9 ,-1 , 0
  3397.7      .1       0  3867.7     .16       0    3868      .1       0
  4341.7     .16       0  4400.6      .1       0  4460.1     .05       0
  4759.8     .16       0    5000     .07       0    5006     .16       0
Bank Sta=4930.6,5086
XS Rating Curve= 0 ,0
Exp/Cntr=0.3,0.1

Type RM Length L Ch R = 1 ,12585   ,480,480,480
BEGIN DESCRIPTION:
UNT003 IN NURI 10.0
END DESCRIPTION:
XS GIS Cut Line= 3
      2276087.72     13302546.86      2275787.72     13301796.85
      2275337.69     13301546.84
#Sta/Elev= 30
  4192.3   138.6  4198.3   138.6  4246.2  137.86  4376.9  133.08  4429.3  131.21
  4446.8  131.76  4452.1  130.07    4471  130.08  4608.7  124.08  4709.3  119.97
  4799.5  117.67    4848  114.74  4870.8  114.48  4907.2  116.55  4936.8  115.55
  4971.2  112.74  4978.5  112.81  4994.4  111.09  4997.1  110.59  5000.4  111.09
  5013.8  112.38  5089.3  114.59  5116.8  116.61    5214  121.16    5317   128.3
  5382.2  131.84  5398.2  131.81  5411.9  133.63  5485.1  137.15  5514.9  139.57
#Mann= 7 ,-1 , 0
  4192.3      .1       0  4198.3     .16       0  4376.9      .1       0
  4608.7     .05       0  4971.2      .1       0  4994.4     .07       0
  5000.4      .1       0
Bank Sta=4907.2,5116.8
XS Rating Curve= 0 ,0
Exp/Cntr=0.3,0.1

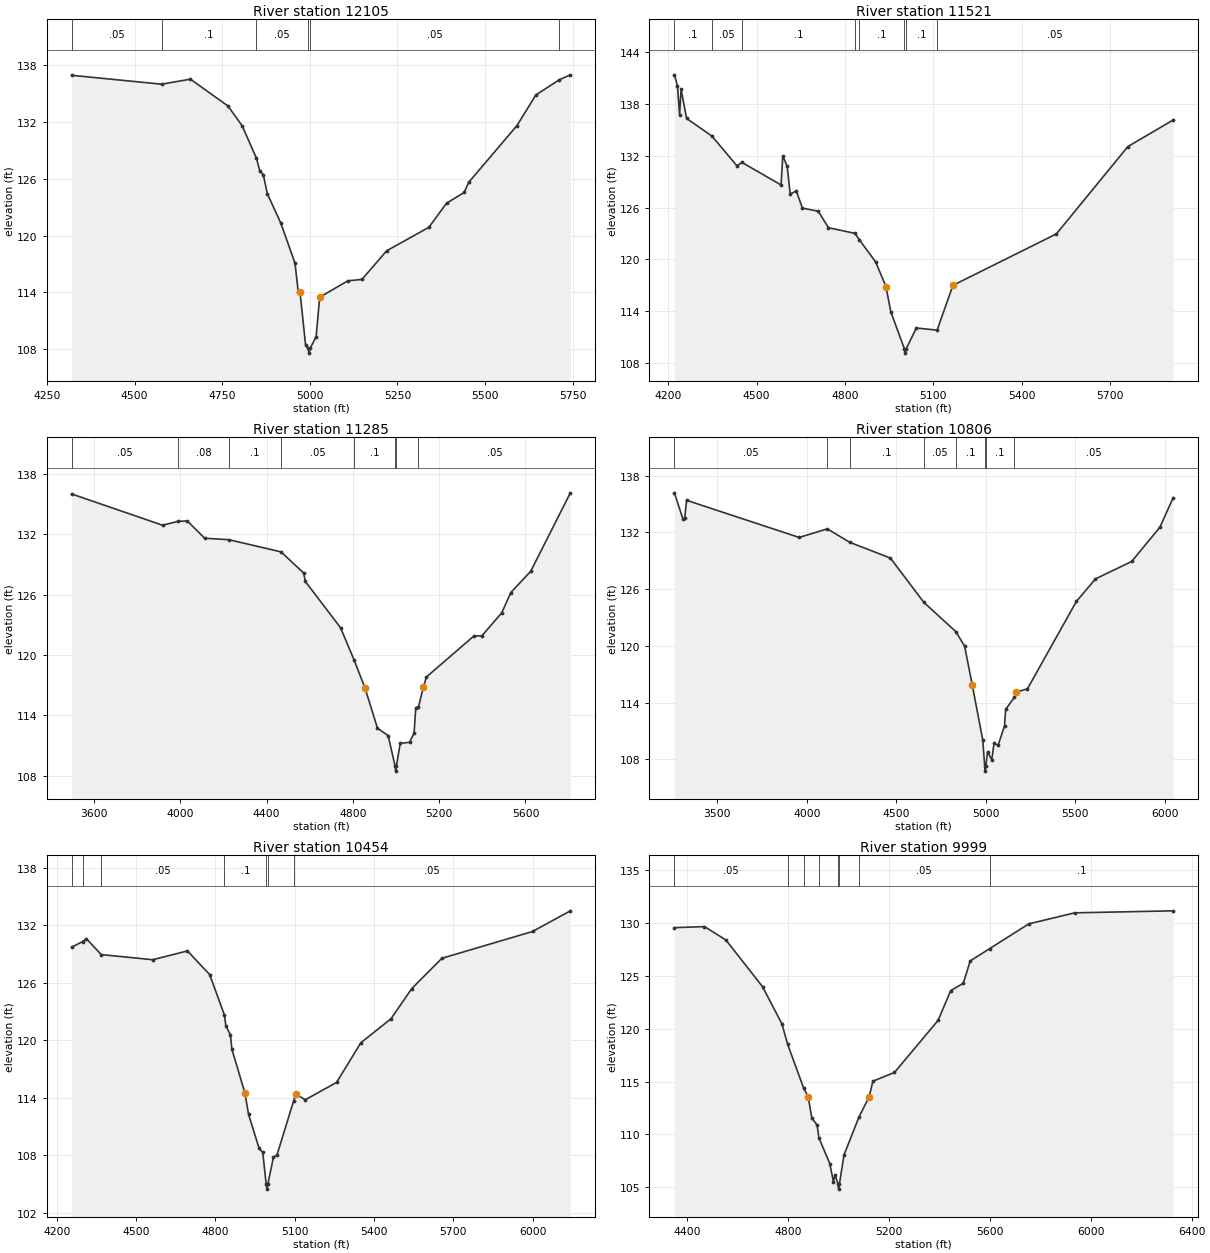
Type RM Length L Ch R = 1 ,12105   ,584,584,584
BEGIN DESCRIPTION:
Mapping XS a5eac4f1
END DESCRIPTION:
XS GIS Cut Line= 3
      2276661.48      13301908.9      2276401.09      13301575.6
      2275406.29     13301471.43
#Sta/Elev= 30
  4320.2  136.93  4577.2  135.99  4659.2  136.52  4766.7  133.68  4806.9  131.59
  4847.6  128.17  4857.1  126.83  4867.2  126.43  4878.7  124.42  4917.5  121.28
  4957.7  117.07  4966.9  114.04    4972  114.02  4987.9  108.41  4994.9  108.07
  4997.7  107.57  5000.9  108.07    5018  109.32  5028.1  113.48  5108.5  115.21
  5148.7  115.36  5219.1  118.38  5339.8  120.87    5390  123.41  5440.3  124.55
  5453.3  125.62  5591.1  131.62  5644.9  134.85  5712.4  136.47  5743.4  136.98
#Mann= 6 ,-1 , 0
  4320.2     .05       0  4577.2      .1       0  4847.6     .05       0
  4994.9    .035       0  5000.9     .05       0  5712.4      .1       0
Bank Sta=4972,5028.1
XS Rating Curve= 0 ,0
Exp/Cntr=0.3,0.1

Type RM Length L Ch R = 1 ,11521   ,236,236,236
BEGIN DESCRIPTION:
UNT003 IN NURI 9.0
END DESCRIPTION:
XS GIS Cut Line= 3
      2277037.72     13301196.85      2276287.72     13300996.85
      2275487.71     13301446.86
#Sta/Elev= 30
  4220.7  141.38    4231  140.11  4238.2  136.77  4243.3  139.69  4262.1  136.33
  4348.1  134.29  4433.5  130.83  4449.6  131.25  4582.9  128.63  4588.7  131.99
  4603.6  130.81    4614  127.58  4634.7  127.93  4655.4  125.95  4709.1  125.59
    4744  123.68  4833.4  123.03  4848.5   122.3  4904.4   119.7  4939.3  116.87
  4955.5  113.96  5001.9  109.66  5004.6  109.16  5007.9  109.66  5042.5  112.07
  5112.9  111.82  5166.8  117.01    5518  122.96  5760.8  133.07  5914.8  136.15
#Mann= 8 ,-1 , 0
  4220.7      .1       0  4348.1     .05       0  4449.6      .1       0
  4833.4     .05       0  4848.5      .1       0  5001.9     .07       0
  5007.9      .1       0  5112.9     .05       0
Bank Sta=4939.3,5166.8
XS Rating Curve= 0 ,0
Exp/Cntr=0.3,0.1

Type RM Length L Ch R = 1 ,11285   ,479,479,479
BEGIN DESCRIPTION:
Mapping XS 7309d427
END DESCRIPTION:
XS GIS Cut Line= 3
      2277541.74     13300690.19      2276625.05     13300445.39
      2275562.62     13301299.51
#Sta/Elev= 30
    3496  136.01  3917.6   132.9  3990.6  133.29  4032.7  133.32  4112.9  131.61
  4225.6  131.46  4467.1  130.25  4571.5  128.15  4579.5  127.31  4742.7  122.71
  4805.8  119.49  4856.3  116.71  4913.8  112.73  4963.4  111.99  4995.6  108.96
  4998.4  108.46  5001.6  108.96  5019.5  111.23  5062.6  111.32  5083.5  112.23
  5091.4  114.76  5103.6  114.81  5126.6  116.81    5141  117.82  5361.8  121.91
    5397  121.89  5489.8  124.19    5532  126.21  5624.2  128.32    5808  136.12
#Mann= 8 ,-1 , 0
    3496     .05       0  3990.6     .08       0  4225.6      .1       0
  4467.1     .05       0  4805.8      .1       0  4995.6     .07       0
  5001.6      .1       0  5103.6     .05       0
Bank Sta=4856.3,5126.6
XS Rating Curve= 0 ,0
Exp/Cntr=0.3,0.1

Type RM Length L Ch R = 1 ,10806   ,352,352,352
BEGIN DESCRIPTION:
UNT003 IN NURI 8.0
END DESCRIPTION:
XS GIS Cut Line= 3
      2277713.56     13300570.38      2276244.84     13300195.39
      2275511.59     13301235.47
#Sta/Elev= 30
  3259.8  136.18  3307.1  133.42  3317.4   133.5  3327.8  135.39  3957.3  131.46
  4114.9  132.37  4239.4  130.95  4467.4  129.28  4654.1   124.6  4832.7  121.51
  4882.4  119.96  4924.3  115.91  4983.4  110.07  4994.7  107.25  4997.4  106.75
  5000.7  107.25  5010.5   108.8  5033.9  107.95  5046.6  109.69  5069.7   109.5
  5105.4  111.55  5111.5  113.27  5160.8  114.57  5168.9   115.1  5233.4  115.45
  5506.8  124.69  5613.9  127.08    5816  128.92  5973.6  132.53  6048.2  135.66
#Mann= 8 ,-1 , 0
  3259.8     .05       0  4114.9     .08       0  4239.4      .1       0
  4654.1     .05       0  4832.7      .1       0  4994.7     .07       0
  5000.7      .1       0  5160.8     .05       0
Bank Sta=4924.3,5168.9
XS Rating Curve= 0 ,0
Exp/Cntr=0.3,0.1

Type RM Length L Ch R = 1 ,10454   ,455,455,455
BEGIN DESCRIPTION:
Mapping XS 490c22dd
END DESCRIPTION:
XS GIS Cut Line= 3
      2276411.54     13299721.43      2275994.84     13299836.02
       2275463.6     13301190.17
#Sta/Elev= 30
    4256  129.72  4297.6  130.32  4311.8  130.62  4367.9  128.96  4562.6  128.42
  4694.2  129.34  4778.3  126.87  4834.1  122.64  4839.5  121.52  4856.9  120.57
  4862.3  119.07  4911.2  114.54  4925.4  112.27  4965.4   108.7  4979.1  108.29
  4992.2  104.95  4994.9  104.45  4998.2  104.95  5019.6  107.79  5032.8     108
  5095.9  113.67  5103.7  114.36  5140.2  113.79  5258.4   115.6  5350.4  119.75
  5464.3  122.25  5542.9  125.41  5656.8  128.57  5999.6  131.37  6142.8  133.53
#Mann= 7 ,-1 , 0
    4256     .05       0  4297.6     .08       0  4367.9     .05       0
  4834.1      .1       0  4992.2     .07       0  4998.2      .1       0
  5095.9     .05       0
Bank Sta=4911.2,5103.7
XS Rating Curve= 0 ,0
Exp/Cntr=0.3,0.1

Type RM Length L Ch R = 1 ,9999    ,448,448,448
BEGIN DESCRIPTION:
UNT003 IN NURI 7.0
END DESCRIPTION:
XS GIS Cut Line= 4
      2276046.11     13299567.29      2275604.22     13299752.69
      2275057.34     13300481.85      2274891.06     13301043.07
#Sta/Elev= 30
  4350.8  129.53  4469.9  129.63  4555.1  128.36  4700.1  123.95  4776.8  120.44
    4799  118.54  4862.9  114.37  4880.7  113.56  4895.3  111.55  4916.2  110.89
  4923.3  109.68  4966.2  107.26  4980.7  105.55    4987   106.2  4998.6  105.34
  5001.3  104.84  5004.6  105.34  5022.7  108.07    5082  111.65  5122.7  113.58
    5137  115.03  5222.7  115.86  5395.3  120.77  5445.3  123.58  5495.3  124.28
  5522.7  126.39  5599.1  127.54  5754.8  129.89  5936.7  130.93  6326.8  131.12
#Mann= 8 ,-1 , 0
  4350.8     .05       0    4799      .1       0  4862.9     .05       0
  4923.3      .1       0  4998.6     .07       0  5004.6      .1       0
    5082     .05       0  5599.1      .1       0
Bank Sta=4880.7,5122.7
XS Rating Curve= 0 ,0
Exp/Cntr=0.3,0.1

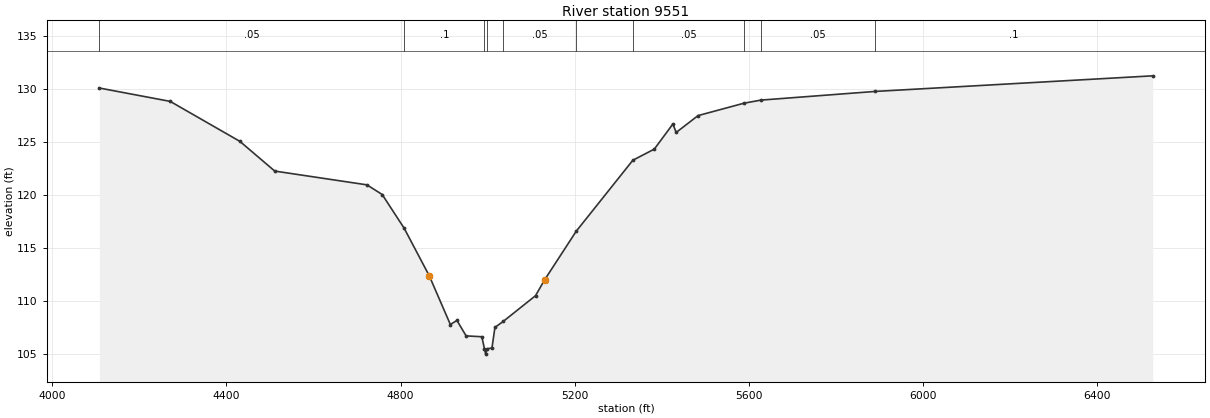
Type RM Length L Ch R = 1 ,9551    ,573,573,573
BEGIN DESCRIPTION:
UNT003 IN NURI 6.0
END DESCRIPTION:
XS GIS Cut Line= 4
      2276010.44     13299461.02      2275401.09     13299466.23
      2274890.68     13299804.77      2274787.72     13300996.88
#Sta/Elev= 30
  4108.5  130.05  4271.2  128.79  4431.2  125.02  4511.2  122.22  4722.9  120.92
  4757.9  120.01  4808.3  116.83  4865.9  112.35  4914.4  107.75  4929.5  108.14
  4950.5  106.68  4986.6   106.6  4992.7  105.46  4995.4  104.96  4998.7  105.46
  5009.9  105.54  5016.7  107.48  5035.6  108.04  5109.9  110.47    5131  111.98
  5203.2  116.54  5333.3  123.24  5382.6  124.29  5425.3  126.66  5432.8  125.86
    5483  127.45  5588.6  128.62  5627.2  128.91  5889.9  129.73  6526.9   131.2
#Mann= 10 ,-1 , 0
  4108.5     .05       0  4808.3      .1       0  4992.7     .07       0
  4998.7      .1       0  5035.6     .05       0  5203.2      .1       0
  5333.3     .05       0  5588.6      .1       0  5627.2     .05       0
  5889.9      .1       0
Bank Sta=4865.9,5131
XS Rating Curve= 0 ,0
Exp/Cntr=0.3,0.1