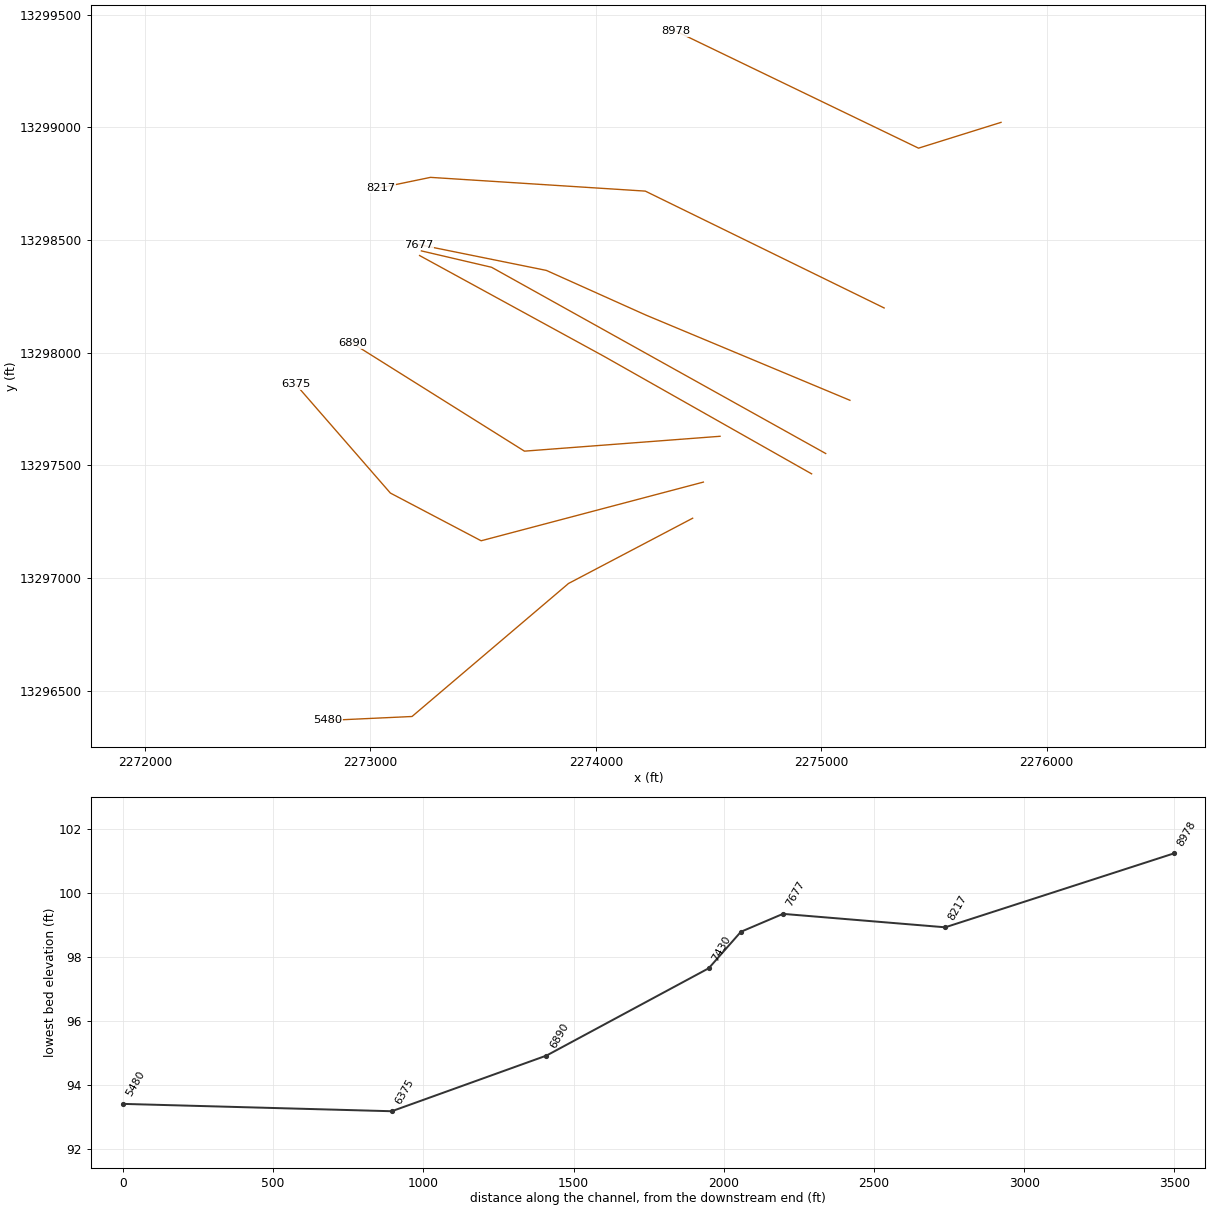
HEC-RAS study UNT003 IN NURI.prj: UNT003 IN NURI Base Level Engineering

--- UNT003 IN NURI.g01 (geometry) --- (continued)

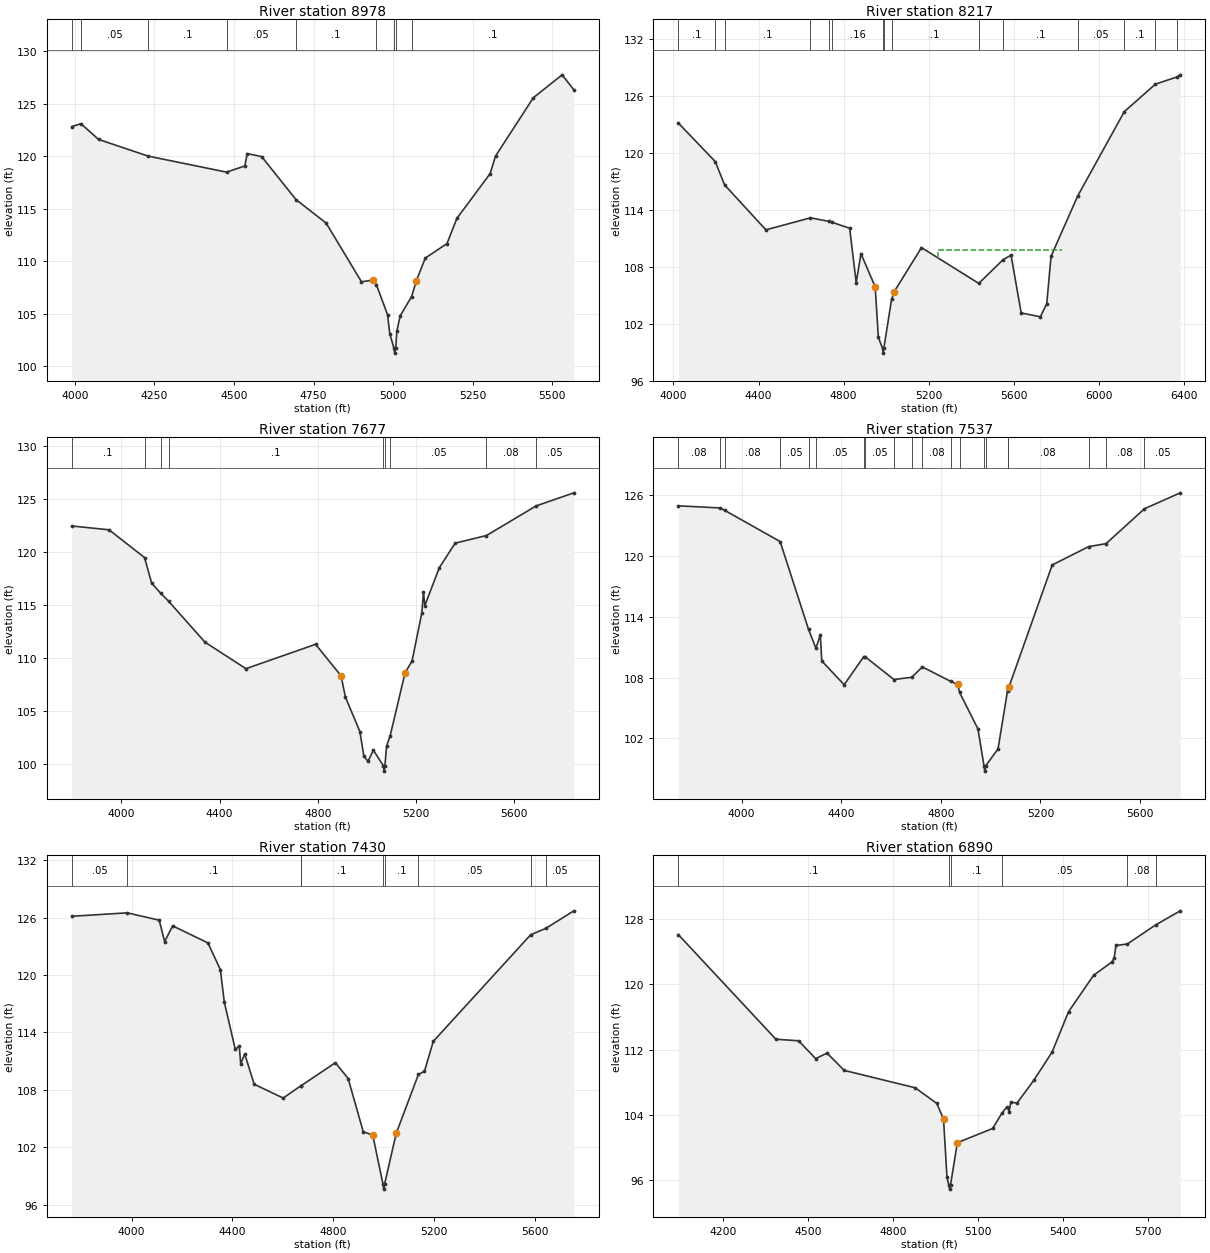
Type RM Length L Ch R = 1 ,8978    ,761,761,761
BEGIN DESCRIPTION:
UNT003 IN NURI 5.0
END DESCRIPTION:
XS GIS Cut Line= 3
      2275798.06     13299022.48        2275432.     13298908.08
      2274356.82     13299426.61
#Sta/Elev= 30
  3990.2  122.83  4018.9  123.11  4074.4  121.61  4229.9  120.02  4476.5  118.49
  4533.9  119.08  4541.5  120.26  4586.7  119.97  4694.7  115.87  4789.3  113.63
  4900.3  108.03    4937   108.2  4947.1  107.76  4982.2  104.89  4989.1   103.1
  5001.9  101.73  5004.6  101.23  5007.9  101.73  5011.3  103.31  5021.9  104.79
  5057.7  106.62  5072.7  108.14  5100.9   110.3  5168.7  111.67    5200  114.08
  5304.4  118.35  5321.4  120.02    5440  125.58  5530.5  127.77  5567.4  126.34
#Mann= 9 ,-1 , 0
  3990.2      .1       0  4018.9     .05       0  4229.9      .1       0
  4476.5     .05       0  4694.7      .1       0  4947.1     .16       0
  5001.9     .07       0  5007.9     .16       0  5057.7      .1       0
Bank Sta=4937,5072.7
XS Rating Curve= 0 ,0
Exp/Cntr=0.3,0.1

Type RM Length L Ch R = 1 ,8217    ,540,540,540
BEGIN DESCRIPTION:
UNT003 IN NURI 4.0
END DESCRIPTION:
XS GIS Cut Line= 4
      2275279.48     13298198.91      2274219.54     13298717.45
      2273266.35     13298778.45      2273045.25      13298732.7
#Sta/Elev= 30
  4022.4  123.18  4196.4  119.11  4240.7  116.64  4434.7  111.91    4644  113.18
  4731.6   112.8  4746.7   112.7  4828.5  112.08  4859.3  106.35  4881.6  109.41
  4948.4  105.91  4963.6  100.57  4983.1   99.42  4985.8   98.92  4989.1   99.42
  5025.6  104.58  5037.4  105.38  5166.2  110.04  5435.6  106.27    5550  108.77
  5587.3  109.24  5635.1  103.15  5725.3  102.75  5755.3  104.13  5775.4  109.12
    5901  115.49    6120  124.37  6266.3  127.27    6366  128.01  6383.3  128.25
#Mann= 15 ,-1 , 0
  4022.4      .1       0  4196.4     .05       0  4240.7      .1       0
    4644     .16       0  4731.6      .1       0  4746.7     .16       0
  4983.1     .07       0  4989.1     .16       0  5025.6      .1       0
  5435.6     .05       0    5550      .1       0    5901     .05       0
    6120      .1       0  6266.3     .05       0    6366     .08       0
#XS Ineff= 1 ,-1
 5244.14 5828.12  109.81
Permanent Ineff=
       F
Bank Sta=4948.4,5037.4
XS Rating Curve= 0 ,0
Exp/Cntr=0.3,0.1

Type RM Length L Ch R = 1 ,7677    ,140,140,140
BEGIN DESCRIPTION:
UNT003 IN NURI 3.0
END DESCRIPTION:
XS GIS Cut Line= 4
      2275127.61     13297789.19      2274221.41     13298167.64
      2273780.44     13298365.56      2273214.43     13298480.15
#Sta/Elev= 30
  3798.9  122.48  3950.5  122.12    4095   119.5  4123.9  117.09  4160.8  116.13
  4192.8  115.38  4340.6  111.52  4507.5  109.01  4790.9  111.31  4894.6  108.34
  4912.2  106.34  4971.3  103.07  4987.2  100.78  5004.2  100.26  5026.1  101.32
    5067   99.84  5069.7   99.34    5073   99.84  5079.9  101.71  5094.5  102.68
  5154.9  108.61  5183.5  109.74  5223.4  114.29  5229.9  116.27  5235.4  114.96
  5294.3  118.54  5358.9  120.86  5486.3  121.58  5687.9  124.37  5841.8  125.61
#Mann= 9 ,-1 , 0
  3798.9      .1       0    4095     .08       0  4160.8     .05       0
  4192.8      .1       0    5067     .07       0    5073      .1       0
  5094.5     .05       0  5486.3     .08       0  5687.9     .05       0
Bank Sta=4894.6,5154.9
XS Rating Curve= 0 ,0
Exp/Cntr=0.3,0.1

Type RM Length L Ch R = 1 ,7537    ,107,107,107
BEGIN DESCRIPTION:
UNT003 IN NURI 2.0
END DESCRIPTION:
XS GIS Cut Line= 3
      2275019.99     13297553.08      2273537.38     13298379.45
        2273226.     13298452.11
#Sta/Elev= 30
  3745.1  124.93    3913  124.72  3931.2  124.49  4154.4  121.41  4268.7  112.74
    4298   110.9    4316  112.19  4321.8  109.64  4411.7  107.29  4490.5  110.07
  4497.3  110.03  4611.6  107.81  4683.1  108.03  4725.9  109.05  4840.2  107.62
  4868.1  107.32  4875.6  106.53  4949.2  102.94  4973.7   99.28  4976.4   98.78
  4979.7   99.28  5029.9  100.97  5068.1   106.7  5069.2  106.77  5073.8  107.08
  5247.6   119.1    5394  120.91  5463.8   121.2  5618.3  124.64  5762.2  126.21
#Mann= 20 ,-1 , 0
  3745.1     .08       0    3913      .1       0  3931.2     .08       0
  4154.4     .05       0  4268.7      .1       0    4298     .05       0
  4490.5      .1       0  4497.3     .05       0  4611.6     .08       0
  4683.1     .05       0  4725.9     .08       0  4840.2      .1       0
  4875.6     .08       0  4973.7     .07       0  4979.7     .08       0
  5068.1     .05       0  5069.2     .08       0    5394     .05       0
  5463.8     .08       0  5618.3     .05       0
Bank Sta=4868.1,5073.8
XS Rating Curve= 0 ,0
Exp/Cntr=0.3,0.1

Type RM Length L Ch R = 1 ,7430    ,540,540,540
BEGIN DESCRIPTION:
Mapping XS d2a0a40c
END DESCRIPTION:
XS GIS Cut Line= 3
      2274957.53     13297462.77      2274037.38     13297983.62
      2273217.94     13298431.53
#Sta/Elev= 30
    3763  126.13  3983.1  126.49  4109.7  125.72  4131.4  123.49  4163.2  125.13
  4302.9  123.35  4352.2  120.57  4368.1  117.15  4411.4  112.24  4427.3  112.56
    4433  110.74  4448.9  111.75  4486.5  108.59  4601.6  107.15  4670.9  108.42
  4671.6  108.42  4808.5  110.84  4859.1  109.19  4918.9  103.64  4956.7  103.28
  4997.4   98.14  5000.2   97.64  5003.4   98.14  5049.8  103.47  5137.7  109.61
  5161.8  109.95  5196.8  113.07  5582.9   124.2  5643.2  124.87  5754.2   126.7
#Mann= 9 ,-1 , 0
    3763     .05       0  3983.1      .1       0  4670.9     .08       0
  4671.6      .1       0  4997.4     .07       0  5003.4      .1       0
  5137.7     .05       0  5582.9     .08       0  5643.2     .05       0
Bank Sta=4956.7,5049.8
XS Rating Curve= 0 ,0
Exp/Cntr=0.3,0.1

Type RM Length L Ch R = 1 ,6890    ,515,515,515
BEGIN DESCRIPTION:
Mapping XS f507b9e2
END DESCRIPTION:
XS GIS Cut Line= 3
       2274551.3     13297629.45      2273683.21     13297563.48
      2272919.94     13298042.26
#Sta/Elev= 30
  4042.7  126.08  4387.3  113.26  4467.5  113.07  4527.7  110.88  4567.8  111.57
    4628  109.45  4878.7  107.32  4955.2   105.4  4978.8  103.48    4991   96.34
  4997.4   95.41  5000.2   94.91  5003.4   95.41  5027.5  100.59  5152.4  102.34
  5185.4  104.24  5203.1  104.99  5210.2  104.41  5216.1  105.54  5238.5  105.46
  5297.5  108.24  5362.2  111.71  5419.9  116.63  5508.3  121.09  5571.9  122.69
  5580.8  123.16  5587.2  124.74  5627.3  124.92  5727.9  127.27  5814.3  128.98
#Mann= 6 ,-1 , 0
  4042.7      .1       0  4997.4     .07       0  5003.4      .1       0
  5185.4     .05       0  5627.3     .08       0  5727.9     .05       0
Bank Sta=4978.8,5027.5
XS Rating Curve= 0 ,0
Exp/Cntr=0.3,0.1

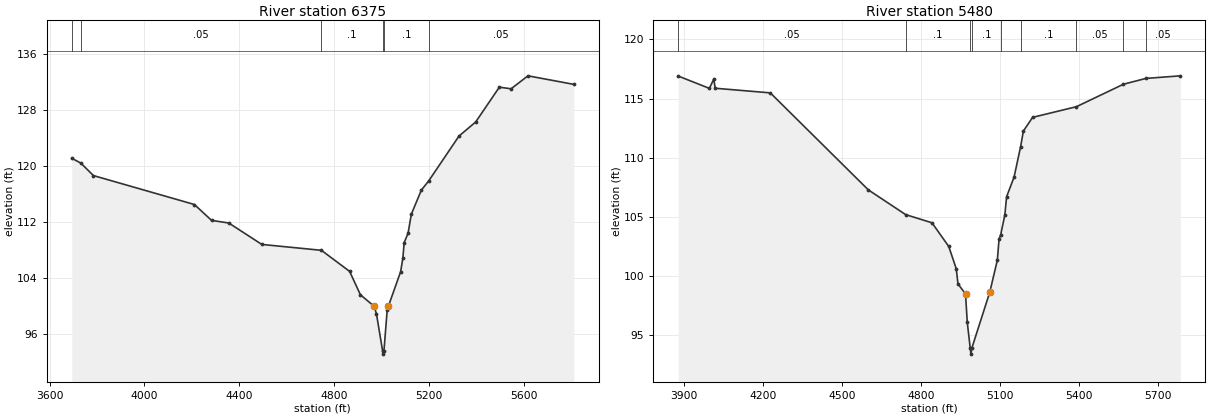
Type RM Length L Ch R = 1 ,6375    ,895,895,895
BEGIN DESCRIPTION:
Mapping XS 376bc389
END DESCRIPTION:
XS GIS Cut Line= 4
      2274477.15     13297426.16        2273491.     13297165.74
      2273088.22     13297377.54      2272668.09     13297860.17
#Sta/Elev= 30
  3693.8  121.13  3731.6  120.45  3785.1  118.66  4210.3  114.53  4282.7  112.26
  4355.1  111.89  4494.4  108.83  4745.4  107.99  4864.3  104.98  4909.5  101.65
  4967.5     100  4977.3   98.91  5002.9   93.67  5005.6   93.17  5008.9   93.67
  5022.3    99.4  5027.9  100.05    5079  104.93  5088.4  106.86  5094.1   109.1
  5110.4  110.43  5124.2  113.15  5166.3  116.58  5197.1  117.89  5324.9   124.3
  5395.2  126.31  5494.9  131.28  5544.3  131.05  5615.5   132.9  5808.7  131.68
#Mann= 6 ,-1 , 0
  3693.8      .1       0  3731.6     .05       0  4745.4      .1       0
  5002.9     .07       0  5008.9      .1       0  5197.1     .05       0
Bank Sta=4967.5,5027.9
XS Rating Curve= 0 ,0
Exp/Cntr=0.3,0.1

Type RM Length L Ch R = 1 ,5480    ,0,0,0
BEGIN DESCRIPTION:
UNT003 IN NURI 1.0
END DESCRIPTION:
XS GIS Cut Line= 4
      2274429.66     13297265.84      2273878.73     13296976.21
      2273184.28     13296385.93      2272811.83     13296368.61
#Sta/Elev= 30
  3877.4   116.9  3995.8  115.86  4012.2  116.64  4017.9  115.87    4227  115.48
  4599.4  107.28  4741.1  105.19    4841   104.5  4904.7   102.5  4933.3  100.61
  4939.8   99.33  4968.4   98.49    4975    96.1  4986.3    93.9    4989    93.4
  4992.3    93.9  5060.7   98.65  5089.2  101.34  5095.8  103.12  5102.1   103.5
  5117.8  105.18  5124.4   106.7  5152.9  108.37  5177.6  110.93  5188.1  112.25
  5223.2  113.41  5389.5  114.31  5568.2  116.21  5653.3   116.7  5784.1  116.92
#Mann= 9 ,-1 , 0
  3877.4     .05       0  4741.1      .1       0  4986.3     .07       0
  4992.3      .1       0  5102.1     .05       0  5177.6      .1       0
  5389.5     .05       0  5568.2      .1       0  5653.3     .05       0
Bank Sta=4968.4,5060.7
XS Rating Curve= 0 ,0
Exp/Cntr=0.3,0.1

Chan Stop Cuts=-1
Use User Specified Reach Order=0
Composite Channel Slope=5