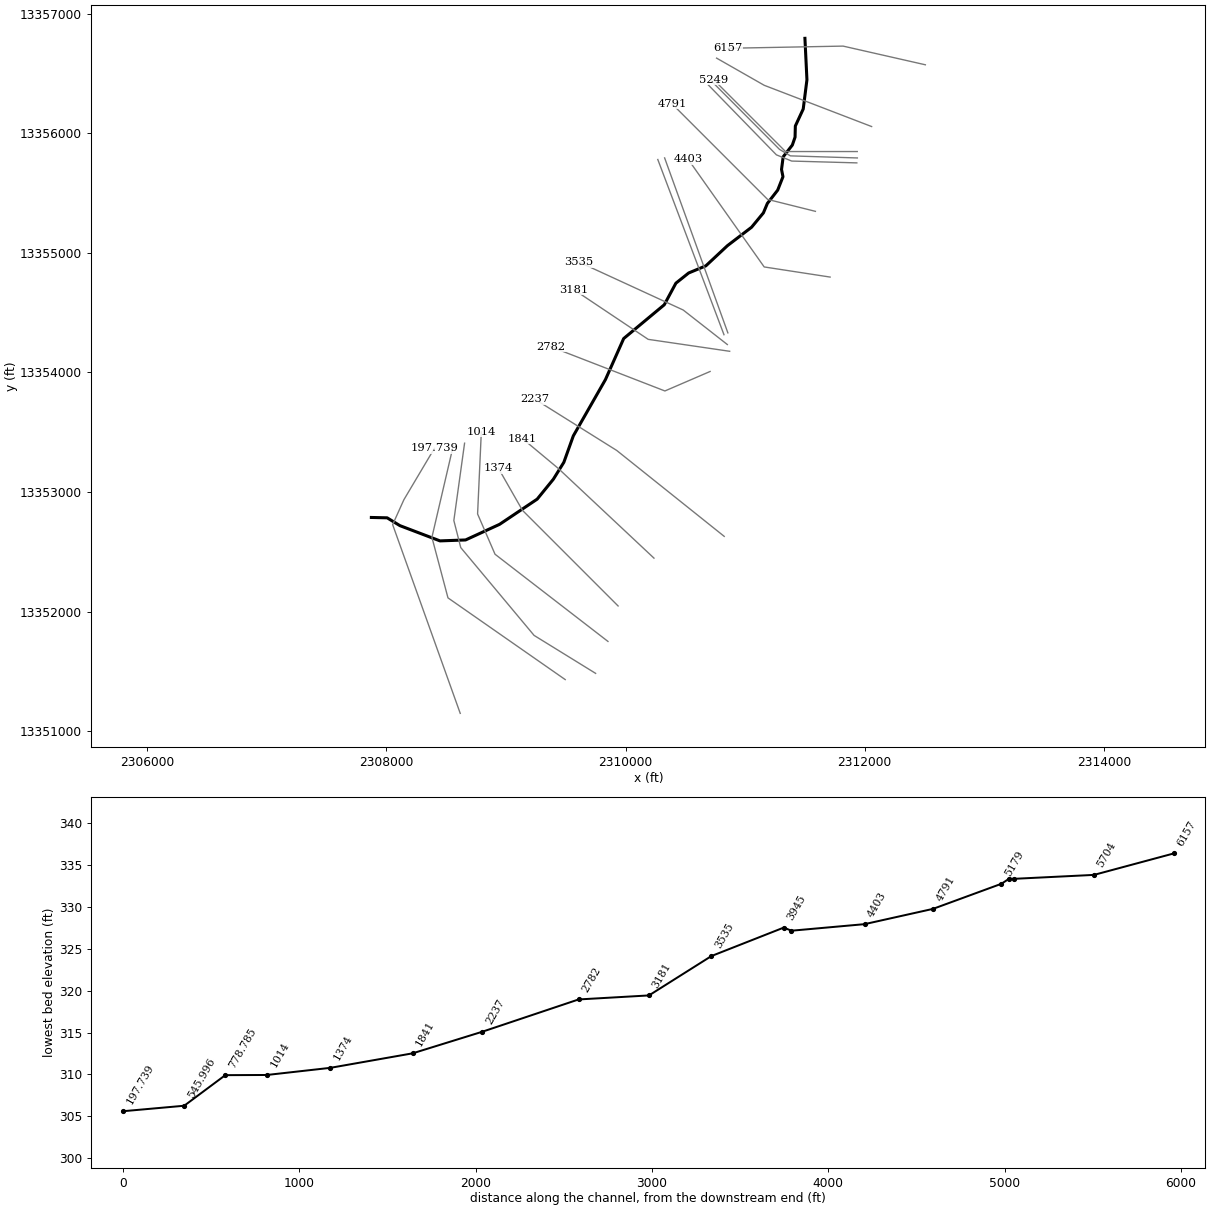
--- UNT004 IN NURI.prj (project) ---

Proj Title=UNT004 IN NURI Base Level Engineering
Current Plan=p01
Default Exp/Contr=0.3,0.1
English Units
Geom File=g01
Flow File=f01
Plan File=p01
Y Axis Title=Elevation
X Axis Title(PF)=Main Channel Distance
X Axis Title(XS)=Station
BEGIN DESCRIPTION:
UNT004 IN NURI
END DESCRIPTION:
DSS Export Rating Curves= 0
DSS Export Rating Curve Sorted= 0
DSS Export Volume Flow Curves= 0
DXF OffsetX= 0
DXF OffsetY= 0
DXF ScaleX= 1
DXF ScaleY= 10

--- UNT004 IN NURI.p01 (plan) ---

Plan Title=Multiple Run
Short Identifier=Multiple
Geom File=g01
Flow File=f01
Subcritical Flow
K Sum by GR= 0
Std Step Tol= 0.01
Critical Tol= 0.01
Num of Std Step Trials= 20
Max Error Tol= 0.3
Flow Tol Ratio= 0.001
Split Flow NTrial= 30
Split Flow Tol= 0.02
Split Flow Ratio= 0.02
Log Output Level= 0
Friction Slope Method= 1
Unsteady Friction Slope Method= 2
Unsteady Bridges Friction Slope Method= 1
Parabolic Critical Depth
Global Vel Dist=  1 , 1 , 1
Global Log Level= 0
CheckData=True
Encroach Param= -1, 0, 0, 0
BEGIN DESCRIPTION:
Multiple Run
END DESCRIPTION:

--- UNT004 IN NURI.f01 (steady flow) ---

Flow Title=Multiple
Program Version=4.10
Number of Profiles= 7
Profile Names=10-year,25-year,50-year,1pct_min,100-year,1pct_plu,500-year
River Rch & RM=UNT004 IN NURI,Reach-1         ,6157
     590     832    1035     941    1273    1721    1930
River Rch & RM=UNT004 IN NURI,Reach-1         ,4791
     648     915    1139    1035    1400    1893    2123
Boundary for River Rch & Prof#=UNT004 IN NURI,Reach-1         , 1
Up Type= 0
Dn Type= 3
Dn Slope=0.005
Boundary for River Rch & Prof#=UNT004 IN NURI,Reach-1         , 2
Up Type= 0
Dn Type= 3
Dn Slope=0.005
Boundary for River Rch & Prof#=UNT004 IN NURI,Reach-1         , 3
Up Type= 0
Dn Type= 3
Dn Slope=0.005
Boundary for River Rch & Prof#=UNT004 IN NURI,Reach-1         , 4
Up Type= 0
Dn Type= 3
Dn Slope=0.005
Boundary for River Rch & Prof#=UNT004 IN NURI,Reach-1         , 5
Up Type= 0
Dn Type= 3
Dn Slope=0.005
Boundary for River Rch & Prof#=UNT004 IN NURI,Reach-1         , 6
Up Type= 0
Dn Type= 3
Dn Slope=0.005
Boundary for River Rch & Prof#=UNT004 IN NURI,Reach-1         , 7
Up Type= 0
Dn Type= 3
Dn Slope=0.005
DSS Import GetInterval= 0
DSS Import GetPeak= 0
DSS Import FillOption= 0

--- UNT004 IN NURI.g01 (geometry) ---

Geom Title=Existing Conditions
Program Version=4.10

River Reach=UNT004 IN NURI  ,Reach-1
Reach XY= 30
      2311500.07     13356793.53      2311516.88     13356446.84
      2311485.78     13356202.46      2311419.92     13356060.27
      2311417.58     13355967.23      2311394.79     13355901.04
      2311318.15     13355802.74      2311304.41       13355697.
      2311316.45     13355636.37      2311272.39     13355524.33
      2311186.02     13355412.92      2311152.83     13355333.93
      2311053.94     13355213.92      2310851.93     13355059.61
       2310671.7     13354891.15      2310527.95     13354831.43
      2310421.01     13354746.01      2310323.79     13354565.45
      2309984.48     13354283.05       2309831.9      13353939.8
      2309563.35     13353469.24      2309484.19     13353248.32
      2309396.29     13353106.58      2309260.99      13352940.1
      2308946.66     13352729.42      2308662.17     13352598.77
      2308448.43       13352591.      2308113.48     13352718.43
      2308006.51     13352783.88      2307874.44     13352786.89

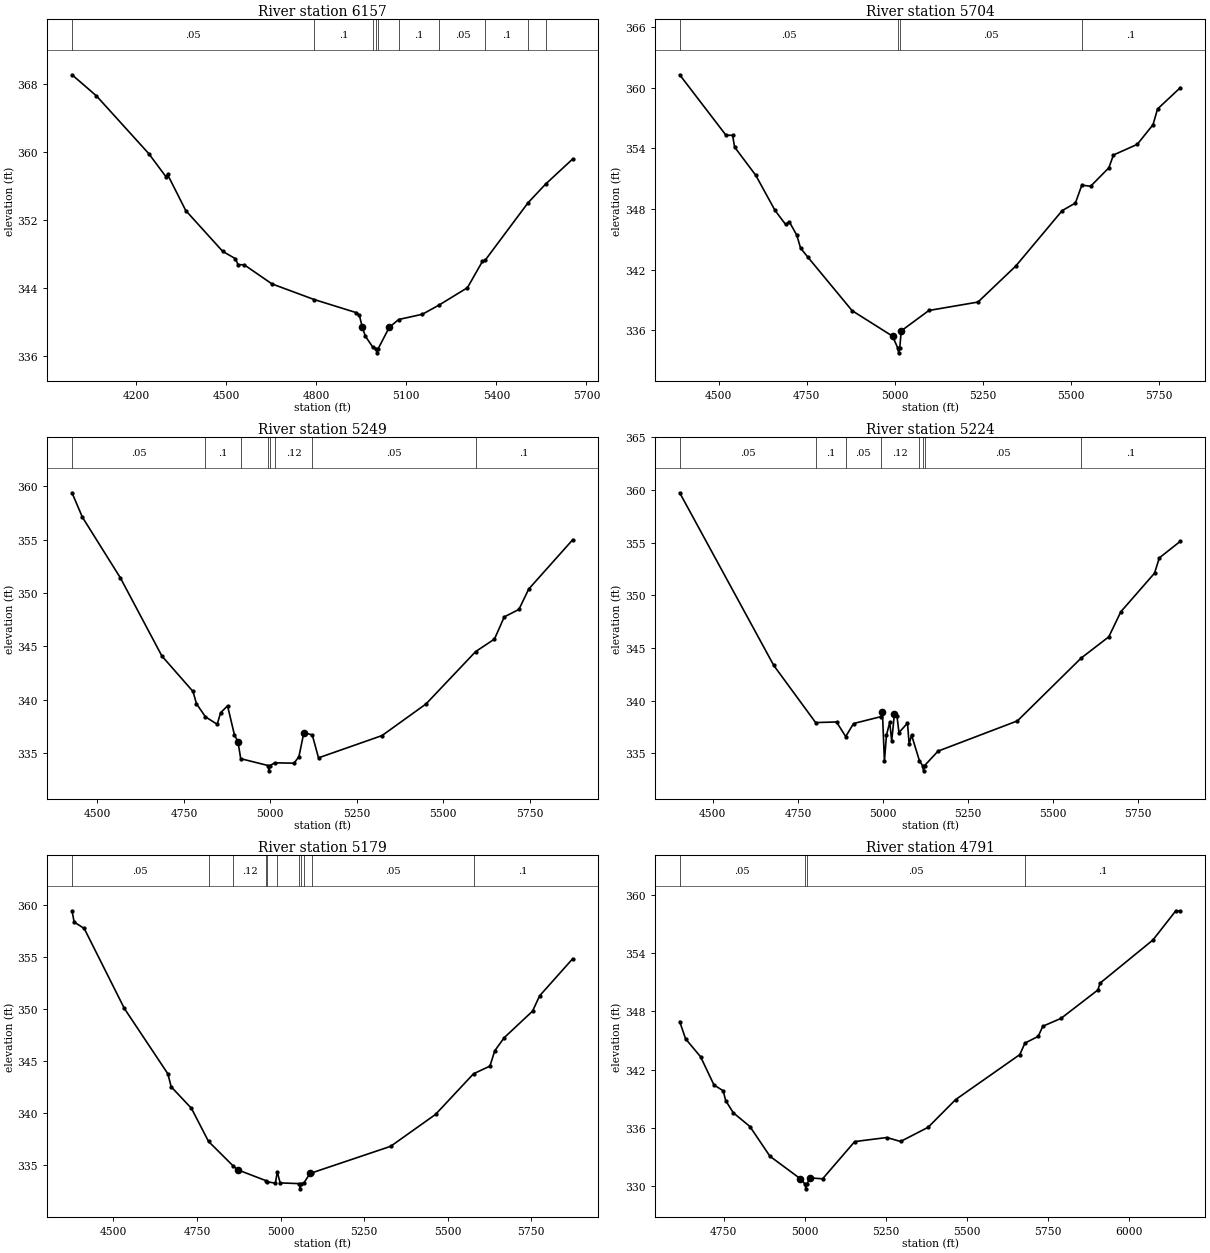
Type RM Length L Ch R = 1 ,6157    ,453,453,453
BEGIN DESCRIPTION:
UNT004 IN NURI 13.0
END DESCRIPTION:
XS GIS Cut Line= 3
      2312507.09     13356572.35      2311819.19     13356728.59
      2310857.19     13356710.39
#Sta/Elev= 30
  3986.8  369.13  4068.2  366.64  4242.5  359.83  4299.8   357.1  4304.9  357.38
  4365.6  353.12  4488.6  348.31  4530.6  347.45  4539.9  346.74  4560.4  346.72
  4652.7  344.47    4793  342.63  4933.7  341.08  4943.7   340.8  4953.7  339.35
  4963.7  338.31  4989.4  336.97  5000.7  336.84  5003.5  336.34  5006.7  336.84
  5043.5  339.35  5074.7  340.27  5153.8  340.89  5210.5     342  5303.8  344.02
  5353.8  347.13  5363.7   347.3  5505.5  354.03  5563.9  356.23  5654.4   359.2
#Mann= 10 ,-1 , 0
  3986.8     .05       0    4793      .1       0  4989.4     .12       0
  5000.7     .07       0  5006.7     .12       0  5074.7      .1       0
  5210.5     .05       0  5363.7      .1       0  5505.5     .05       0
  5563.9      .1       0
Bank Sta=4953.7,5043.5
XS Rating Curve= 0 ,0
Exp/Cntr=0.3,0.1

Type RM Length L Ch R = 1 ,5704    ,455,455,455
BEGIN DESCRIPTION:
UNT004 IN NURI 12.0
END DESCRIPTION:
XS GIS Cut Line= 3
      2312057.88     13356055.85      2311159.46      13356400.9
      2310761.41     13356628.05
#Sta/Elev= 30
  4389.6  361.27  4520.8   355.3  4539.7  355.28  4545.4  354.12  4605.5  351.33
  4660.1  347.86  4690.2  346.47  4700.4  346.75  4721.9  345.41  4732.6  344.13
    4754  343.21  4878.8  337.95  4993.5  335.43  5008.1  334.28  5010.8  333.78
  5014.1  334.28  5018.2  335.95  5096.8  337.97    5236   338.8  5343.2  342.36
  5474.9  347.84  5512.4  348.59  5530.7  350.36  5555.6  350.25  5607.3  352.07
  5620.4  353.34  5687.9  354.39  5732.7  356.34  5745.5  357.89  5810.3     360
#Mann= 4 ,-1 , 0
  4389.6     .05       0  5008.1    .035       0  5014.1     .05       0
  5530.7      .1       0
Bank Sta=4993.5,5018.2
XS Rating Curve= 0 ,0
Exp/Cntr=0.3,0.1

Type RM Length L Ch R = 1 ,5249    ,25,25,25
BEGIN DESCRIPTION:
UNT004 IN NURI 11.0
END DESCRIPTION:
XS GIS Cut Line= 3
      2311937.68     13355846.85      2311337.72     13355846.85
      2310737.71     13356446.86
#Sta/Elev= 30
  4426.3  359.41  4456.3  357.12  4566.3  351.42  4686.3  344.09  4776.3  340.76
  4786.3  339.61  4812.3  338.38  4846.3  337.68  4856.3  338.77  4876.3  339.41
  4896.3  336.67  4906.3  336.06  4914.4  334.45  4993.3  333.81    4996  333.31
  4999.3  333.81  5012.6  334.06  5068.7  334.03  5082.8  334.65    5097  336.89
  5121.4  336.68  5139.4  334.53  5323.2  336.62  5450.5  339.59  5593.9   344.5
  5648.5  345.68  5676.8  347.76  5719.2  348.46  5747.5  350.37  5874.8     355
#Mann= 8 ,-1 , 0
  4426.3     .05       0  4812.3      .1       0  4914.4     .05       0
  4993.3     .03       0  4999.3     .05       0  5012.6     .12       0
  5121.4     .05       0  5593.9      .1       0
Bank Sta=4906.3,5097
XS Rating Curve= 0 ,0
Exp/Cntr=0.3,0.1

Type RM Length L Ch R = 1 ,5224    ,45,45,45
BEGIN DESCRIPTION:
Mapping XS 7e2a9a8b
END DESCRIPTION:
XS GIS Cut Line= 4
      2311938.51     13355793.26      2311378.65     13355810.62
       2311287.5     13355864.87      2310718.94      13356435.6
#Sta/Elev= 30
  4402.5  359.73  4679.1  343.34  4802.1  337.92  4863.5  337.98  4890.5  336.59
  4913.5  337.83  4993.7  338.48  4998.5  338.88  5004.3  334.24  5010.3  336.73
  5019.9  337.94  5025.7  336.18  5033.5  338.69  5041.3  338.51  5047.1  336.97
  5072.1  337.87    5077  335.89  5084.1  336.73  5107.2   334.3  5116.4  333.84
  5119.2  333.34  5122.4  333.84  5161.9  335.21  5395.2  338.08  5582.9  344.05
  5663.9  346.06  5699.3  348.44  5798.3   352.1  5812.4  353.55  5874.3  355.13
#Mann= 8 ,-1 , 0
  4402.5     .05       0  4802.1      .1       0  4890.5     .05       0
  4993.7     .12       0  5107.2     .05       0  5116.4     .07       0
  5122.4     .05       0  5582.9      .1       0
Bank Sta=4998.5,5033.5
XS Rating Curve= 0 ,0
Exp/Cntr=0.3,0.1

Type RM Length L Ch R = 1 ,5179    ,388,388,388
BEGIN DESCRIPTION:
Mapping XS 5d6c7810
END DESCRIPTION:
XS GIS Cut Line= 4
      2311934.16     13355752.03       2311389.5     13355767.22
      2311261.46      13355819.3      2310693.45     13356402.49
#Sta/Elev= 30
  4376.5   359.4  4382.9  358.32    4413   357.7    4533  350.03  4663.1  343.76
  4673.1  342.51  4733.5  340.45  4784.7  337.27  4858.9   334.9  4873.1  334.53
    4956  333.51  4960.5   333.4  4984.7  333.26  4990.3  334.35  4998.9  333.29
  5055.9  333.22  5058.7  332.72  5061.9  333.22  5070.4  333.31  5088.8  334.23
  5093.3  334.25  5329.3   336.8  5463.5  339.86  5577.1  343.76  5626.3   344.5
  5640.5  345.96  5668.8  347.22  5753.6  349.77  5774.8  351.24  5873.7   354.8
#Mann= 11 ,-1 , 0
  4376.5     .05       0  4784.7      .1       0  4858.9     .12       0
    4956     .05       0  4960.5     .12       0  4990.3     .05       0
  5055.9     .03       0  5061.9     .05       0  5070.4     .12       0
  5093.3     .05       0  5577.1      .1       0
Bank Sta=4873.1,5088.8
XS Rating Curve= 0 ,0
Exp/Cntr=0.3,0.1

Type RM Length L Ch R = 1 ,4791    ,388,388,388
BEGIN DESCRIPTION:
UNT004 IN NURI 10.0
END DESCRIPTION:
XS GIS Cut Line= 3
      2311587.75     13355346.85      2311187.72     13355446.85
      2310387.73     13356246.84
#Sta/Elev= 30
    4614  346.94  4632.1  345.16  4678.5  343.31  4719.7  340.41    4748  339.82
  4755.8  338.81    4779  337.56  4830.5  336.14  4892.3  333.08  4985.1  330.79
  5000.2  330.23  5002.9  329.73  5006.2  330.23    5016  330.86  5054.6  330.76
  5153.6  334.59  5252.6  335.01    5295   334.6  5379.9  336.06  5464.8  338.91
  5662.7  343.54  5678.4  344.72  5719.3  345.41  5733.5  346.45    5790  347.27
  5903.2  350.18  5910.2  350.89  6072.9  355.32  6143.6  358.33  6157.7   358.3
#Mann= 4 ,-1 , 0
    4614     .05       0  5000.2     .03       0  5006.2     .05       0
  5678.4      .1       0
Bank Sta=4985.1,5016
XS Rating Curve= 0 ,0
Exp/Cntr=0.3,0.1

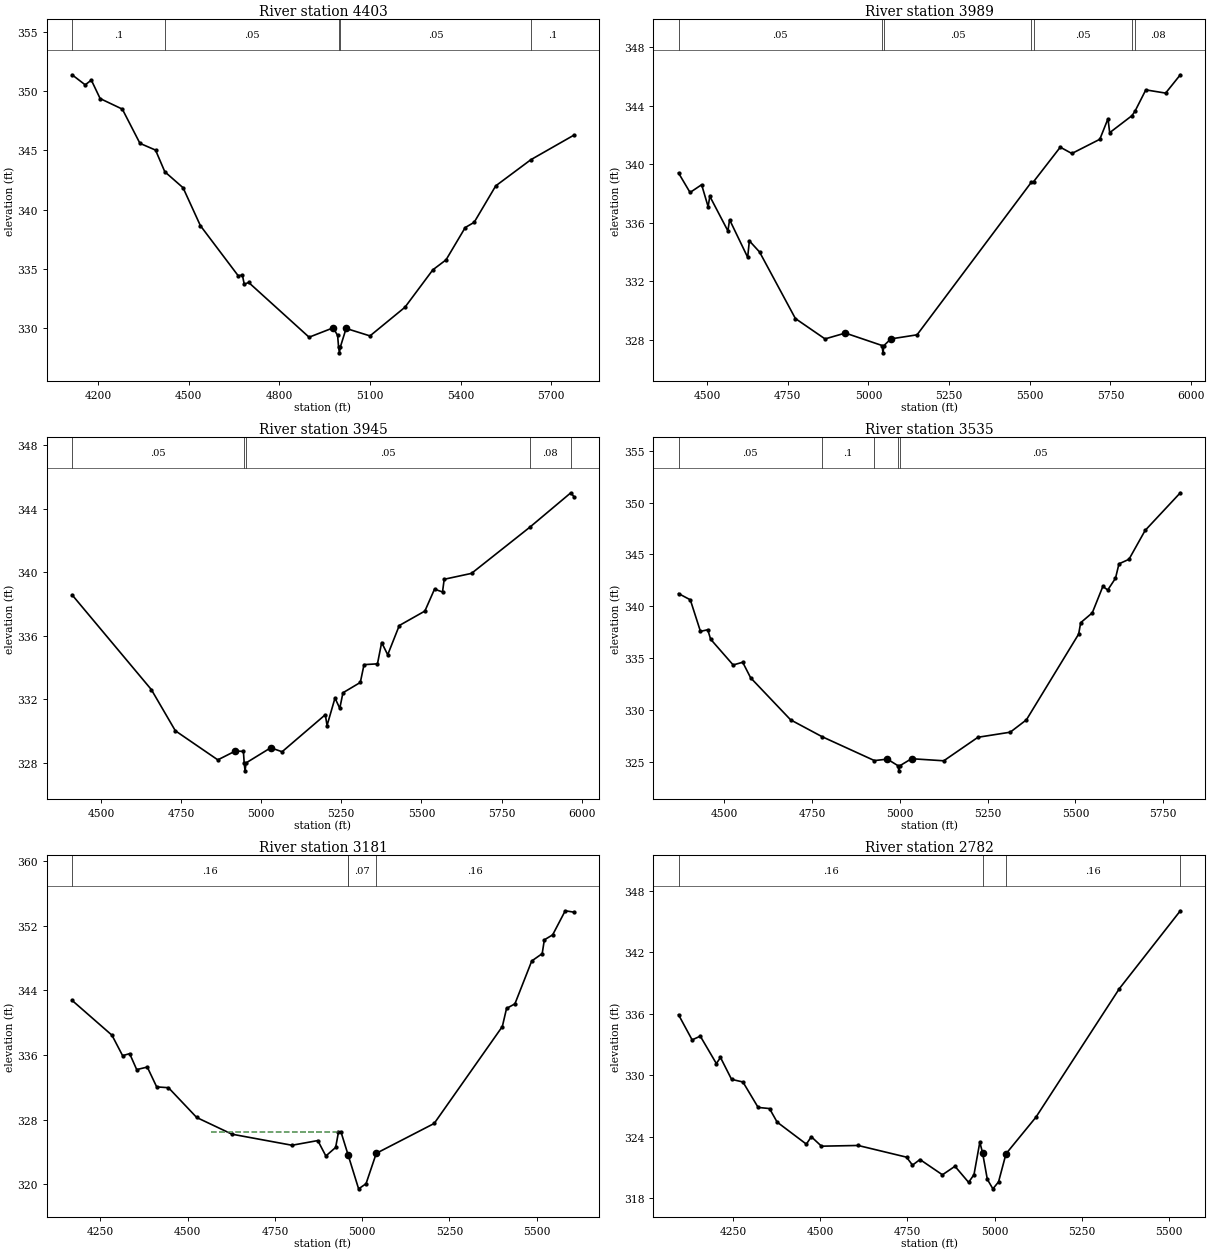
Type RM Length L Ch R = 1 ,4403    ,414,414,414
BEGIN DESCRIPTION:
UNT004 IN NURI 9.0
END DESCRIPTION:
XS GIS Cut Line= 3
      2311710.72     13354797.16      2311159.46      13354881.8
      2310523.05      13355782.3
#Sta/Elev= 30
  4114.3  351.39  4157.8  350.54    4178  350.94  4207.2  349.38  4280.6  348.49
  4338.9   345.6  4390.5  345.03  4421.2   343.2  4481.6  341.85  4538.9  338.65
  4663.7  334.43  4677.9  334.47    4684  333.71  4698.8  333.85  4898.6  329.23
  4978.2  330.02    4993  329.38  4996.1  328.41  4998.9  327.91  5002.1  328.41
  5021.1  329.97  5100.1  329.34  5215.8  331.76  5308.1  334.92  5351.7  335.76
  5415.2  338.49  5444.8  338.93  5516.2  342.01  5632.5  344.22  5774.7  346.29
#Mann= 5 ,-1 , 0
  4114.3      .1       0  4421.2     .05       0  4996.1     .03       0
  5002.1     .05       0  5632.5      .1       0
Bank Sta=4978.2,5021.1
XS Rating Curve= 0 ,0
Exp/Cntr=0.3,0.1

Type RM Length L Ch R = 1 ,3989    ,44,44,44
BEGIN DESCRIPTION:
Mapping XS ecafd93a
END DESCRIPTION:
XS GIS Cut Line= 2
      2310855.65     13354330.57      2310326.79     13355793.62
#Sta/Elev= 30
  4411.1   339.4  4446.8  338.07  4482.7   338.6  4502.8   337.1  4508.1  337.81
  4564.1  335.45  4569.4  336.21  4625.4  333.65  4630.7  334.77  4662.3  334.01
  4773.4  329.47  4865.3  328.08  4928.2  328.48  5042.1  327.63  5044.9  327.13
  5048.1  327.63  5069.3  328.08  5150.6  328.36  5505.3  338.78  5511.9  338.81
  5594.6  341.16  5630.5  340.73  5717.2   341.7  5742.5   343.1  5747.8  342.15
  5816.8  343.31  5826.4  343.62  5859.8  345.07  5921.2  344.85  5966.8   346.1
#Mann= 7 ,-1 , 0
  4411.1     .05       0  5042.1     .04       0  5048.1     .05       0
  5505.3      .1       0  5511.9     .05       0  5816.8      .1       0
  5826.4     .08       0
Bank Sta=4928.2,5069.3
XS Rating Curve= 0 ,0
Exp/Cntr=0.3,0.1

Type RM Length L Ch R = 1 ,3945    ,410,410,410
BEGIN DESCRIPTION:
UNT004 IN NURI 8.0
END DESCRIPTION:
XS GIS Cut Line= 2
       2310823.1     13354315.38      2310269.71     13355780.24
#Sta/Elev= 30
  4409.9  338.57  4657.3  332.61  4732.2  330.02  4864.7  328.19  4919.8  328.75
  4944.6  328.72    4947     328  4949.7   327.5    4953     328  5029.8  328.95
  5065.3   328.7  5200.2  331.03  5205.6  330.35  5230.4  332.08  5245.3  331.43
  5255.2  332.41  5309.4  333.06    5321  334.18  5362.9  334.23    5376  335.57
  5394.9   334.8    5431  336.64  5510.9  337.55    5541  338.93  5565.9  338.75
  5571.2  339.55  5656.4  339.92  5837.5  342.81  5966.4  344.99  5975.8  344.75
#Mann= 5 ,-1 , 0
  4409.9     .05       0    4947     .04       0    4953     .05       0
  5837.5     .08       0  5966.4     .05       0
Bank Sta=4919.8,5029.8
XS Rating Curve= 0 ,0
Exp/Cntr=0.3,0.1

Type RM Length L Ch R = 1 ,3535    ,354,354,354
BEGIN DESCRIPTION:
UNT004 IN NURI 7.0
END DESCRIPTION:
XS GIS Cut Line= 3
      2310851.27     13354232.95      2310482.38     13354521.56
        2309610.     13354923.03
#Sta/Elev= 30
  4369.8  341.22  4403.3  340.62  4432.2  337.57    4453  337.73  4461.1  336.82
  4525.3  334.33  4552.5  334.59  4575.1  333.09    4689  329.03  4778.3  327.41
  4927.5   325.1  4964.4  325.24  4994.4  324.61  4997.2  324.11  5000.4  324.61
  5033.1  325.28    5125  325.08  5222.3  327.35  5314.2  327.84  5360.2  329.03
    5509  337.31  5514.8  338.41  5547.8  339.36  5577.9  341.91  5591.9  341.57
  5613.9   342.7  5623.8  344.09  5652.3  344.53  5698.2  347.31  5798.5  350.95
#Mann= 5 ,-1 , 0
  4369.8     .05       0  4778.3      .1       0  4927.5     .05       0
  4994.4     .03       0  5000.4     .05       0
Bank Sta=4964.4,5033.1
XS Rating Curve= 0 ,0
Exp/Cntr=0.3,0.1

Type RM Length L Ch R = 1 ,3181    ,399,399,399
BEGIN DESCRIPTION:
UNT004 IN NURI 6.0
END DESCRIPTION:
XS GIS Cut Line= 3
      2310870.86      13354176.5      2310189.41     13354276.33
      2309567.47      13354692.4
#Sta/Elev= 30
  4169.2  342.77  4283.5  338.45  4313.9  335.92  4334.1  336.17  4354.3  334.19
  4384.6  334.51  4411.5  332.05  4445.3  331.95  4526.1  328.26  4627.2  326.19
    4799  324.82  4872.9   325.4    4896  323.49    4924  324.55  4932.1  326.44
    4939  326.51    4960  323.58  4989.8  319.42    5011  320.05  5040.4  323.82
  5206.2  327.52  5401.4  339.53  5413.4  341.77  5437.4  342.34  5485.6  347.65
  5515.5  348.56  5521.7  350.27  5545.5  350.89  5581.5  353.87  5606.2   353.7
#Mann= 4 ,-1 , 0
  4169.2     .16       0    4960     .05       0    4960     .07       0
  5040.4     .16       0
#XS Ineff= 1 ,-1
 4566.59  4931.7  326.41
Permanent Ineff=
       F
Bank Sta=4960,5040.4
XS Rating Curve= 0 ,0
Exp/Cntr=0.3,0.1

Type RM Length L Ch R = 1 ,2782    ,545,545,545
BEGIN DESCRIPTION:
UNT004 IN NURI 5.0
END DESCRIPTION:
XS GIS Cut Line= 3
      2310707.26     13354007.73      2310329.17     13353844.76
      2309371.84     13354215.97
#Sta/Elev= 30
  4093.7  335.92  4132.6  333.47  4156.1  333.83  4202.1  331.16    4214  331.75
  4245.7  329.62  4278.3  329.36  4321.9  326.88  4354.5  326.77  4376.3  325.45
  4460.1   323.3  4474.3  324.02  4503.5   323.1  4608.5  323.17  4747.3  322.03
  4764.4  321.25  4785.8   321.8  4850.2  320.31  4886.2  321.14  4925.3  319.57
  4940.7  320.33  4957.4  323.49  4965.2  322.47  4978.9  319.87  4994.9  318.94
  5011.1  319.62  5032.5  322.36  5118.3  325.93  5357.3  338.46  5532.2  346.06
#Mann= 4 ,-1 , 0
  4093.7     .16       0  4965.2     .07       0  5032.5     .16       0
  5532.2     .05       0
Bank Sta=4965.2,5032.5
XS Rating Curve= 0 ,0
Exp/Cntr=0.3,0.1

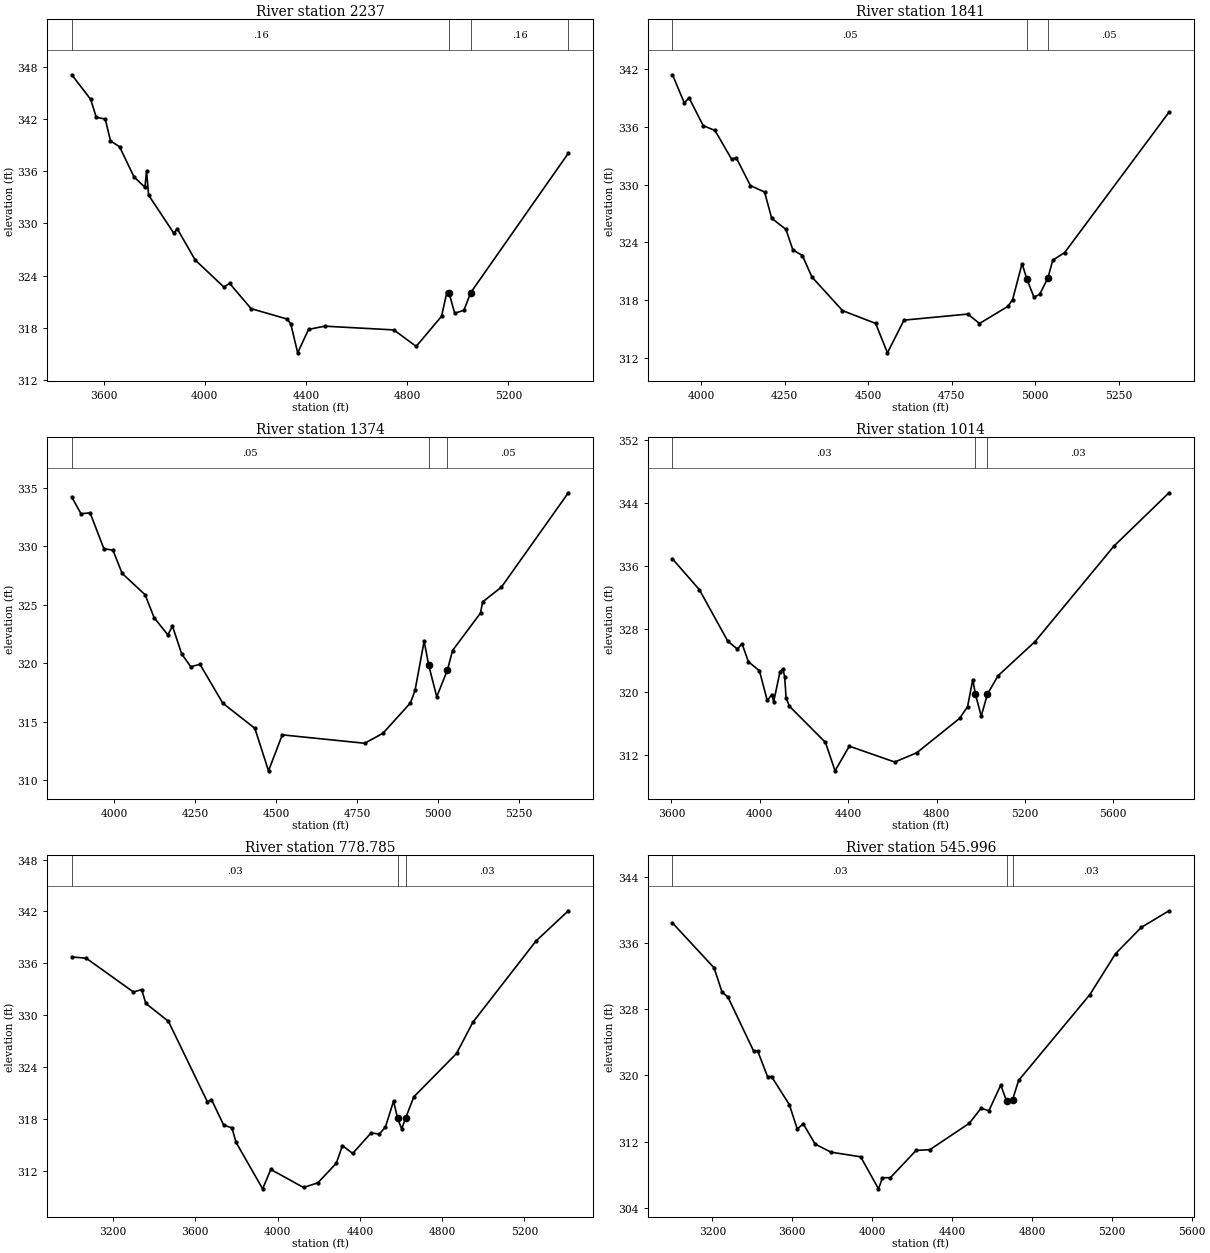
Type RM Length L Ch R = 1 ,2237    ,396,396,396
BEGIN DESCRIPTION:
UNT004 IN NURI 4.0
END DESCRIPTION:
XS GIS Cut Line= 3
      2310825.23     13352628.79      2309925.96     13353347.51
      2309238.45     13353778.07
#Sta/Elev= 30
  3474.7  347.11  3549.2  344.28  3571.6   342.2  3606.8  342.02  3627.6   339.5
  3663.5  338.82  3720.5  335.36  3763.7  334.16  3770.1  336.02  3778.1  333.26
  3877.4  328.89  3891.8  329.37  3962.2  325.79  4075.9  322.67  4098.3   323.1
  4183.2  320.19  4325.7  318.99  4340.1  318.43  4367.4   315.1  4410.5   317.8
  4474.5  318.17  4747.4  317.74  4835.8  315.84    4936  319.31  4957.2  322.09
    4966  321.97  4987.9  319.66  5024.4     320  5051.5  322.04  5437.1  338.08
#Mann= 4 ,-1 , 0
  3474.7     .16       0    4966     .07       0  5051.5     .16       0
  5437.1     .05       0
#XS Ineff= 1 ,-1
 4027.36 4955.13 321.466
Permanent Ineff=
       T
Bank Sta=4966,5051.5
XS Rating Curve= 0 ,0
Exp/Cntr=0.3,0.1

Type RM Length L Ch R = 1 ,1841    ,467,467,467
BEGIN DESCRIPTION:
UNT004 IN NURI 3.0
END DESCRIPTION:
XS GIS Cut Line= 3
      2310237.73     13352446.85      2309437.72     13353196.85
      2309137.73     13353446.85
#Sta/Elev= 30
  3913.8  341.43  3949.2  338.51  3963.4  339.03  4005.9  336.14  4041.1  335.64
  4090.9  332.65    4105  332.79  4147.1  329.91  4189.6  329.24    4211  326.51
  4253.5  325.36  4274.5  323.21  4302.9  322.64  4331.2  320.42    4423  316.91
  4522.2  315.58  4557.6  312.52  4607.2  315.92  4798.2  316.55  4833.3  315.57
  4918.3  317.35  4932.5  318.06  4960.8   321.8    4975  320.21  4996.5   318.3
  5013.7  318.61  5038.4  320.33  5052.7  322.15  5088.5  322.95  5400.9  337.54
#Mann= 3 , 0 , 0
  3913.8     .05       0    4975     .03       0  5038.4     .05       0
#XS Ineff= 1 ,-1
 4303.72 4958.27   320.2
Permanent Ineff=
       T
Bank Sta=4975,5038.4
XS Rating Curve= 0 ,0
Exp/Cntr=0.3,0.1

Type RM Length L Ch R = 1 ,1374    ,360,360,360
BEGIN DESCRIPTION:
UNT004 IN NURI 2.0
END DESCRIPTION:
XS GIS Cut Line= 3
      2309937.72     13352046.86      2309137.72     13352846.85
      2308937.71     13353196.87
#Sta/Elev= 30
  3868.7  334.22    3897   332.8  3925.3  332.87  3967.7  329.81    3996  329.67
  4024.3  327.69    4095  325.87  4123.3  323.89  4165.7  322.43  4179.8  323.18
  4208.1  320.81  4236.4   319.7  4264.7  319.91  4335.4  316.58  4434.4  314.43
  4476.6  310.79  4519.2  313.87  4773.8  313.15  4830.4  314.01  4915.2   316.6
  4929.4  317.67  4957.6  321.89  4971.8  319.82  4996.5  317.13  5029.6  319.42
  5045.4  321.09  5131.8   324.3  5138.3  325.25  5196.6  326.52  5403.2  334.59
#Mann= 3 , 0 , 0
  3868.7     .05       0  4971.8     .03       0  5029.6     .05       0
#XS Ineff= 1 ,-1
    4115 4959.77     320
Permanent Ineff=
       T
Bank Sta=4971.8,5029.6
XS Rating Curve= 0 ,0
Exp/Cntr=0.3,0.1

Type RM Length L Ch R = 1 ,1014    ,235,235,235
BEGIN DESCRIPTION:
Mapping XS 030c5efe
END DESCRIPTION:
XS GIS Cut Line= 4
      2309853.02     13351750.31       2308908.6     13352479.46
      2308762.76     13352816.26      2308793.97     13353502.79
#Sta/Elev= 30
  3604.7  336.91  3726.6  332.98  3855.2  326.43  3898.7  325.43  3919.5  326.11
  3948.5  323.81  3998.3  322.67  4033.7  318.89  4054.5  319.65  4062.6  318.71
  4091.5  322.57  4104.3  322.92  4112.5  321.92  4118.8  319.27  4133.3  318.18
  4297.2  313.55  4340.5  309.94    4405  313.08  4610.6  311.06  4710.5  312.24
    4904  316.61  4940.3   318.1  4963.8  321.55 4975.92  319.69  5002.1   316.9
 5030.27   319.7  5078.3  322.04  5245.5  326.38  5602.6  338.53  5852.1  345.32
#Mann= 3 , 0 , 0
  3604.7     .03       0 4975.92     .03       0 5030.27     .03       0
#XS Ineff= 2 ,-1
 3900.57 4092.33  322.16 4116.48 4957.39  318.41
Permanent Ineff=
       T       T
Bank Sta=4975.92,5030.27
XS Rating Curve= 0 ,0
Exp/Cntr=0.3,0.1

Type RM Length L Ch R = 1 ,778.785 ,233,233,233
BEGIN DESCRIPTION:
UNT004 IN NURI 1.0
END DESCRIPTION:
XS GIS Cut Line= 5
     2309749.777     13351483.18     2309235.166    13351800.706
     2308622.033    13352534.819     2308564.213    13352761.412
     2308653.979    13353408.035
#Sta/Elev= 30
    3000336.7423 3069.91336.5918 3299.62332.6834 3339.57332.9625 3359.54331.3631
  3469.4 329.299 3658.83 319.987 3678.72320.2465 3738.39317.2823 3778.17316.9783
 3798.06315.3041 3927.36309.9196 3967.14312.1594 4126.27310.0748 4195.89310.6158
  4285.4312.8789 4315.24314.9147 4364.96314.0161 4454.47316.3856 4494.26316.2516
 4524.09317.0675 4563.72 320.064 4583.46318.0647  4603.2316.8487 4622.94318.1476
 4662.41320.5681 4869.75325.5736 4948.78329.1721 5255.03338.5576 5413.09342.0768
#Mann= 3 , 0 , 0
    3000     .03       0 4583.46    .025       0 4622.94     .03       0
#XS Ineff= 1 ,-1
 3660.56 4563.38   317.5
Permanent Ineff=
       T
Bank Sta=4583.46,4622.94
XS Rating Curve= 0 ,0
Exp/Cntr=0.3,0.1

Type RM Length L Ch R = 1 ,545.996 ,348,348,348
BEGIN DESCRIPTION:
Mapping XS 50e9cca9
END DESCRIPTION:
XS GIS Cut Line= 4
     2309495.467    13351431.231     2308515.159    13352114.477
     2308380.829    13352620.695      2308561.03    13353394.225
#Sta/Elev= 30
    3000338.4514 3208.32333.0163    3248330.0933 3277.76329.4792 3406.72322.9322
 3426.56322.9706 3476.16319.8541    3496319.8684 3585.28316.4653 3624.96313.5132
 3654.72314.1514 3714.24311.6969  3793.6310.7148  3942.4310.1509 4031.68306.2759
 4051.52307.6159  4091.2 307.625 4219.86310.9249 4288.88311.0143  4486.1314.2003
 4545.26316.0251 4584.71315.7323 4643.87318.8333 4673.61316.8687 4703.43317.0841
 4733.22319.3873 5090.06329.7763 5218.91334.7331 5347.77337.9139 5486.54339.9237
#Mann= 3 , 0 , 0
    3000     .03       0 4673.61    .025       0 4703.43     .03       0
#XS Ineff= 2 , 0
       0 4647.73  317.18               0
Permanent Ineff=
       T       F
Bank Sta=4673.61,4703.43
XS Rating Curve= 0 ,0
Exp/Cntr=0.3,0.1

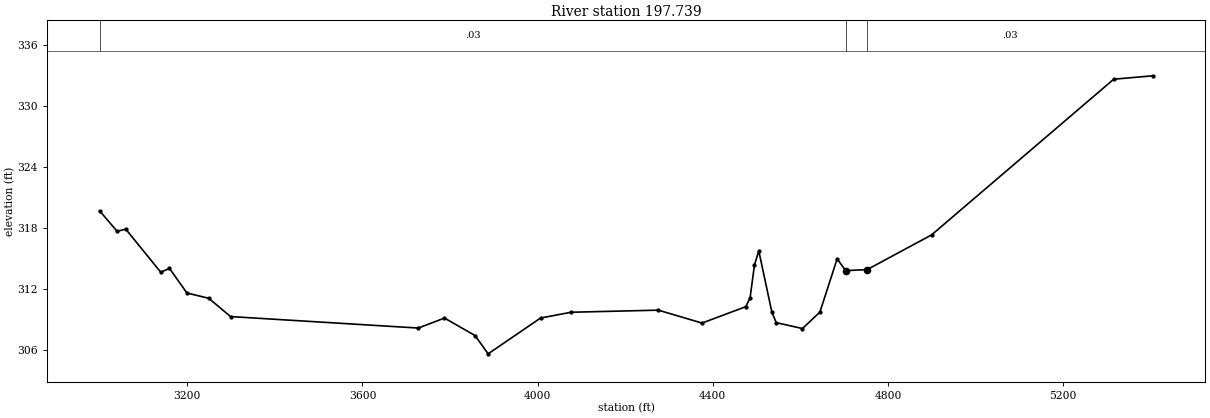
Type RM Length L Ch R = 1 ,197.739 ,0,0,0
BEGIN DESCRIPTION:
UNT004 IN NURI 14.0
END DESCRIPTION:
XS GIS Cut Line= 4
     2308617.688    13351148.633     2308052.583    13352726.758
     2308146.333    13352935.091     2308401.542    13353364.778
#Sta/Elev= 30
    3000319.6652 3039.87317.6624  3059.8317.8658 3139.54313.6398 3159.48314.0152
 3199.35311.5954 3249.18311.0798 3299.02309.2814 3727.62308.1546 3787.42309.1357
 3857.19 307.419 3887.09305.6211  4006.7309.1365 4076.47309.7072 4275.82309.9125
 4375.49308.6432 4475.17310.2484 4485.13311.0906  4495.1 314.319 4505.07315.7375
 4534.97309.7132 4544.94308.6858 4604.74308.1066 4644.61  309.72 4683.99314.9492
 4703.59313.7952  4752.6313.8972 4899.64317.3054 5315.56332.5979 5404.68332.9359
#Mann= 3 , 0 , 0
    3000     .03       0 4703.59    .025       0  4752.6     .03       0
#XS Ineff= 2 ,-1
 3069.01 4505.63   313.5 4512.73  4691.6312.9638
Permanent Ineff=
       T       T
Bank Sta=4703.59,4752.6
XS Rating Curve= 0 ,0
Exp/Cntr=0.3,0.1

Chan Stop Cuts=-1
Use User Specified Reach Order=0
Composite Channel Slope=5