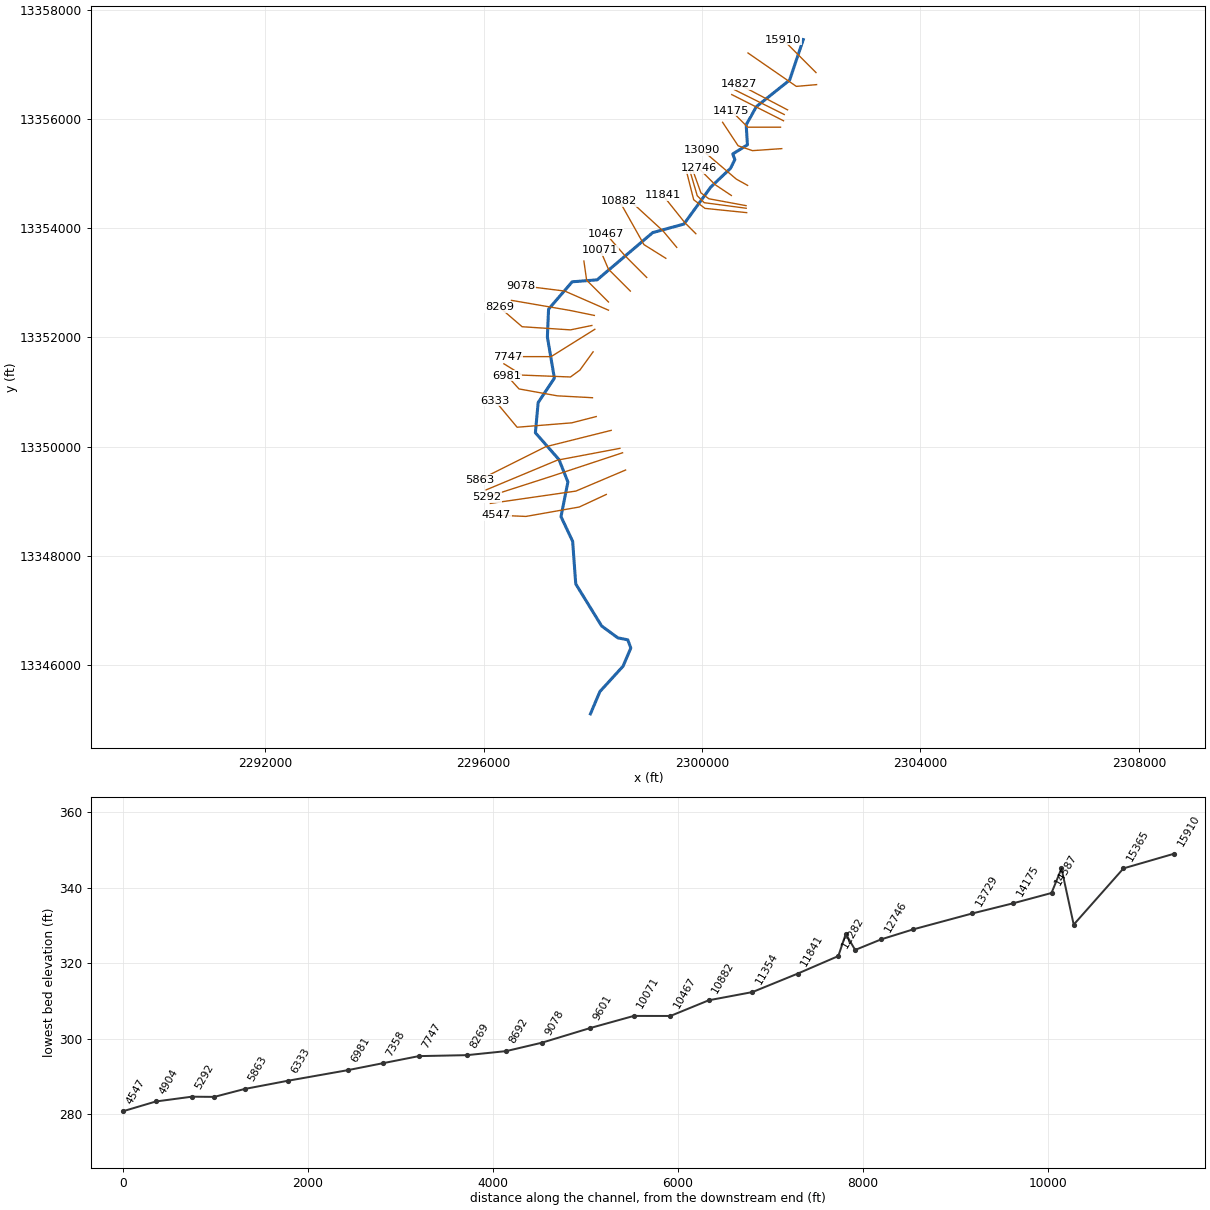
--- UNT005 IN NURI.prj (project) ---

Proj Title=UNT005 IN NURI Base Level Engineering
Current Plan=p01
Default Exp/Contr=0.3,0.1
English Units
Geom File=g01
Flow File=f01
Plan File=p01
BEGIN DESCRIPTION:
UNT005 IN NURI
END DESCRIPTION:

--- UNT005 IN NURI.p01 (plan) ---

Plan Title=Multiple Run
Short Identifier=Multiple
Geom File=g01
Flow File=f01
Subcritical Flow
K Sum by GR= 0
Std Step Tol= 0.01
Critical Tol= 0.01
Num of Std Step Trials= 20
Max Error Tol= 0.3
Flow Tol Ratio= 0.001
Split Flow NTrial= 30
Split Flow Tol= 0.02
Split Flow Ratio= 0.02
Log Output Level= 0
Friction Slope Method= 1
Unsteady Friction Slope Method= 2
Unsteady Bridges Friction Slope Method= 1
Parabolic Critical Depth
Global Vel Dist=  1 , 1 , 1
Global Log Level= 0
CheckData=True
Encroach Param= -1, 0, 0, 0
BEGIN DESCRIPTION:
Multiple Run
END DESCRIPTION:

--- UNT005 IN NURI.f01 (steady flow) ---

Flow Title=Multiple
Number of Profiles=7
Profile Names=10-year,25-year,50-year,1pct_min,100-year,1pct_plu,500-year
River Rch & RM= UNT005 IN NURI,Reach-1,15910
     478     669     828     749    1013    1370    1522
River Rch & RM= UNT005 IN NURI,Reach-1,11841
     894    1298    1646    1522    2059    2784    3237
River Rch & RM= UNT005 IN NURI,Reach-1,8269
    1143    1678    2143    1995    2698    3648    4297
River Rch & RM= UNT005 IN NURI,Reach-1,5863
    1433    2124    2729    2555    3455    4672    5565
River Rch & RM= UNT005 IN NURI,Reach-1,2240
    1454    2155    2770    2592    3505    4741    5644
Boundary for River Rch & Prof#=UNT005 IN NURI,Reach-1,1
Up Type=0
Dn Type=3
Dn Slope=0.005
Boundary for River Rch & Prof#=UNT005 IN NURI,Reach-1,2
Up Type=0
Dn Type=3
Dn Slope=0.005
Boundary for River Rch & Prof#=UNT005 IN NURI,Reach-1,3
Up Type=0
Dn Type=3
Dn Slope=0.005
Boundary for River Rch & Prof#=UNT005 IN NURI,Reach-1,4
Up Type=0
Dn Type=3
Dn Slope=0.005
Boundary for River Rch & Prof#=UNT005 IN NURI,Reach-1,5
Up Type=0
Dn Type=3
Dn Slope=0.005
Boundary for River Rch & Prof#=UNT005 IN NURI,Reach-1,6
Up Type=0
Dn Type=3
Dn Slope=0.005
Boundary for River Rch & Prof#=UNT005 IN NURI,Reach-1,7
Up Type=0
Dn Type=3
Dn Slope=0.005

--- UNT005 IN NURI.g01 (geometry) ---

Geom Title=Existing Conditions

River Reach=UNT005 IN NURI,Reach-1
Reach XY= 30
      2301854.18     13357450.13      2301604.20     13356708.97
      2300995.03     13356222.97      2300809.36     13355890.90
      2300831.96     13355524.50      2300563.72     13355356.83
      2300601.73     13355252.98      2300522.82     13355094.24
      2300160.92     13354750.74      2299668.67     13354073.09
      2299097.72     13353916.86      2298080.33     13353052.16
      2297623.24     13353016.49      2297191.00     13352515.50
      2297169.37     13352007.24      2297297.18     13351252.22
      2297000.51     13350805.77      2296949.93     13350252.73
      2297383.34     13349759.75      2297544.95     13349351.75
      2297418.61     13348717.27      2297631.58     13348266.16
      2297688.87     13347484.91      2298162.89     13346715.11
      2298458.60     13346498.54      2298640.94     13346462.39
      2298697.18     13346312.16      2298553.96     13345978.23
      2298131.09     13345514.93      2297957.72     13345106.85

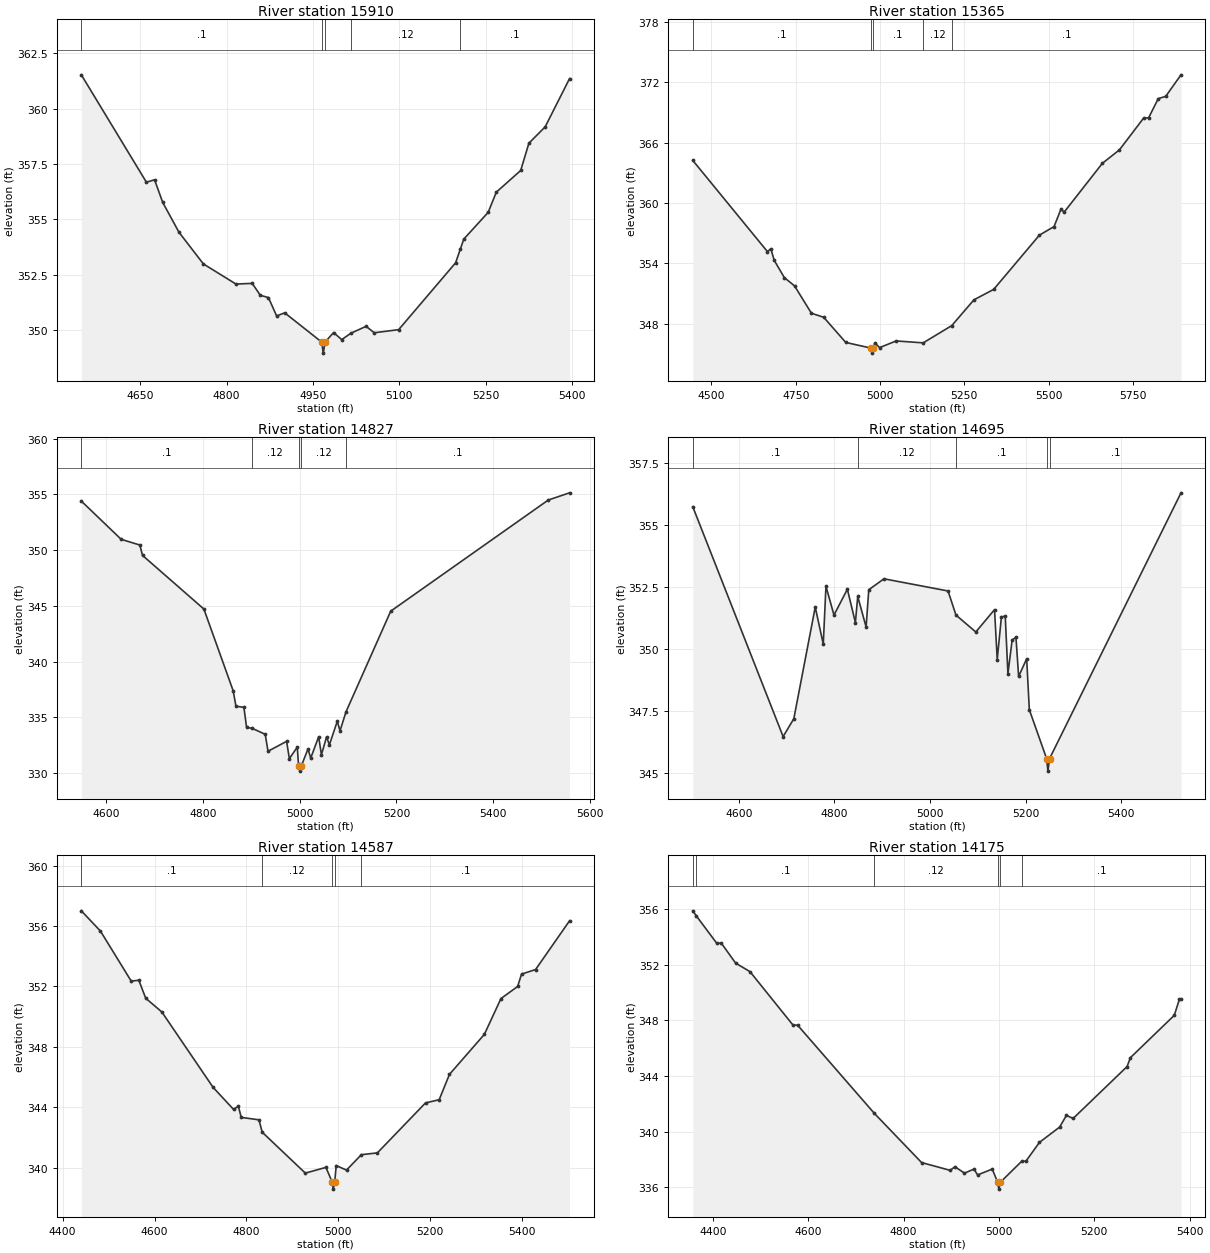
Type RM Length L Ch R = 1,15910,545,545,545
BEGIN DESCRIPTION:
UNT005 IN NURI 32.0
END DESCRIPTION:
XS GIS Cut Line= 3
      2302087.70     13356846.87      2301787.72     13357146.85
      2301487.72     13357446.85
#Sta/Elev= 30
  4547.4  361.53  4660.5  356.68  4674.7  356.79  4688.8  355.77  4717.1  354.42
  4759.5  352.99  4816.1  352.08  4844.4  352.11  4858.5  351.57  4872.6  351.47
  4886.8  350.64  4900.9  350.78  4965.1  349.46  4967.9  348.96  4971.1  349.46
  4985.8  349.89  4999.9  349.57  5016.0  349.86  5042.3  350.17  5056.5  349.88
  5098.9  350.02  5197.9  353.04  5206.1  353.66  5212.1  354.11  5254.5  355.32
  5268.6  356.23  5311.0  357.21  5325.2  358.44  5353.5  359.18  5395.9  361.36
#Mann=5,-1,0
  4547.4     0.1       0  4965.1    0.07       0  4971.1     0.1       0
  5016.0    0.12       0  5206.1     0.1       0
Bank Sta=4965.1,4971.1
Exp/Cntr=0.3,0.1

Type RM Length L Ch R = 1,15365,538,538,538
BEGIN DESCRIPTION:
UNT005 IN NURI 31.0
END DESCRIPTION:
XS GIS Cut Line= 3
      2302098.33     13356626.45      2301727.19     13356593.90
      2300842.26     13357205.54
#Sta/Elev= 30
  4444.7  364.23  4666.2  355.17  4676.2  355.46  4686.2  354.31  4716.3  352.59
  4746.5  351.77  4796.7  349.05  4833.1  348.65  4898.6  346.15  4973.3  345.59
  4976.1  345.09  4979.3  345.59  4985.1  346.10  4999.0  345.64  5048.0  346.30
  5128.3  346.11  5213.2  347.83  5278.6  350.38  5337.3  351.42  5473.0  356.81
  5516.4  357.66  5537.3  359.42  5546.0  359.08  5659.7  363.94  5710.4  365.28
  5782.0  368.43  5796.9  368.46  5825.6  370.37  5847.6  370.59  5893.0  372.73
#Mann=5,-1,0
  4444.7     0.1       0  4973.3    0.07       0  4979.3     0.1       0
  5128.3    0.12       0  5213.2     0.1       0
Bank Sta=4973.3,4979.3
Exp/Cntr=0.3,0.1

Type RM Length L Ch R = 1,14827,132,132,132
BEGIN DESCRIPTION:
UNT005 IN NURI 30.0
END DESCRIPTION:
XS GIS Cut Line= 2
      2301566.63     13356164.19      2300673.71     13356632.33
#Sta/Elev= 30
  4549.2  354.40  4631.5  350.97  4670.0  350.46  4675.6  349.53  4802.3  344.72
  4862.8  337.39  4868.5  336.01  4884.9  335.91  4890.5  334.11  4901.9  334.03
  4929.0  333.49  4934.7  331.97  4973.1  332.86  4978.8  331.31  4995.2  332.34
  4997.8  330.69  5000.6  330.19  5003.8  330.69  5017.3  332.18  5022.9  331.36
  5039.3  333.27  5045.0  331.66  5055.7  333.27  5061.4  332.54  5077.8  334.67
  5083.4  333.80  5095.7  335.50  5188.1  344.53  5513.3  354.49  5557.4  355.14
#Mann=5,-1,0
  4549.2     0.1       0  4901.9    0.12       0  4997.8    0.07       0
  5003.8    0.12       0  5095.7     0.1       0
Bank Sta=4997.8,5003.8
Exp/Cntr=0.3,0.1

Type RM Length L Ch R = 1,14695,108,108,108
BEGIN DESCRIPTION:
UNT005 IN NURI 29.0
END DESCRIPTION:
XS GIS Cut Line= 2
      2301505.83     13356079.57      2300591.40     13356534.62
#Sta/Elev= 30
  4503.7  355.72  4692.7  346.47  4715.1  347.19  4759.9  351.68  4776.7  350.19
  4782.3  352.52  4799.1  351.36  4827.1  352.40  4843.9  351.06  4848.8  352.11
  4866.3  350.88  4871.9  352.38  4903.7  352.82  5037.7  352.33  5054.3  351.36
  5095.8  350.68  5135.0  351.58  5140.6  349.57  5149.4  351.29  5157.4  351.31
  5163.0  349.00  5171.8  350.35  5179.8  350.47  5185.4  348.89  5202.2  349.60
  5207.8  347.55  5244.0  345.58  5246.7  345.08  5250.0  345.58  5525.1  356.28
#Mann=5,-1,0
  4503.7     0.1       0  4848.8    0.12       0  5054.3     0.1       0
  5244.0    0.07       0  5250.0     0.1       0
Bank Sta=5244,5250
Exp/Cntr=0.3,0.1

Type RM Length L Ch R = 1,14587,412,412,412
BEGIN DESCRIPTION:
Mapping XS 7a4a9d84
END DESCRIPTION:
XS GIS Cut Line= 2
      2301492.81     13355964.56      2300544.48     13356444.15
#Sta/Elev= 30
  4440.6  357.00  4482.2  355.66  4549.1  352.35  4565.8  352.40  4580.8  351.21
  4615.9  350.30  4727.4  345.31  4771.9  343.85  4782.5  344.06  4788.6  343.32
  4827.3  343.16  4834.3  342.34  4928.2  339.63  4973.0  340.01  4986.2  339.07
  4988.9  338.57  4992.2  339.07  4995.4  340.13  5017.8  339.83  5050.1  340.85
  5085.0  340.97  5189.8  344.28  5219.5  344.49  5241.9  346.17  5317.9  348.82
  5354.0  351.19  5390.3  351.99  5398.8  352.81  5429.3  353.11  5503.3  356.34
#Mann=5,-1,0
  4440.6     0.1       0  4834.3    0.12       0  4986.2    0.07       0
  4992.2    0.12       0  5050.1     0.1       0
Bank Sta=4986.2,4992.2
Exp/Cntr=0.3,0.1

Type RM Length L Ch R = 1,14175,446,446,446
BEGIN DESCRIPTION:
UNT005 IN NURI 28.0
END DESCRIPTION:
XS GIS Cut Line= 3
      2301437.76     13355846.85      2300837.72     13355846.85
      2300537.72     13356146.85
#Sta/Elev= 30
  4357.7  355.86  4365.3  355.49  4407.7  353.54  4417.7  353.53  4447.7  352.10
  4477.7  351.49  4567.7  347.66  4577.7  347.64  4738.5  341.31  4837.7  337.77
  4897.7  337.21  4907.7  337.47  4927.7  337.01  4947.7  337.30  4955.2  336.88
  4986.0  337.30  4997.2  336.36  4999.9  335.86  5003.2  336.36  5047.7  337.86
  5056.7  337.87  5085.0  339.22  5127.4  340.32  5141.6  341.16  5155.7  340.94
  5268.9  344.67  5275.9  345.31  5367.9  348.35  5378.5  349.49  5382.0  349.49
#Mann=6,-1,0
  4357.7    0.05       0  4365.3     0.1       0  4738.5    0.12       0
  4997.2    0.07       0  5003.2    0.12       0  5047.7     0.1       0
Bank Sta=4997.2,5003.2
Exp/Cntr=0.3,0.1

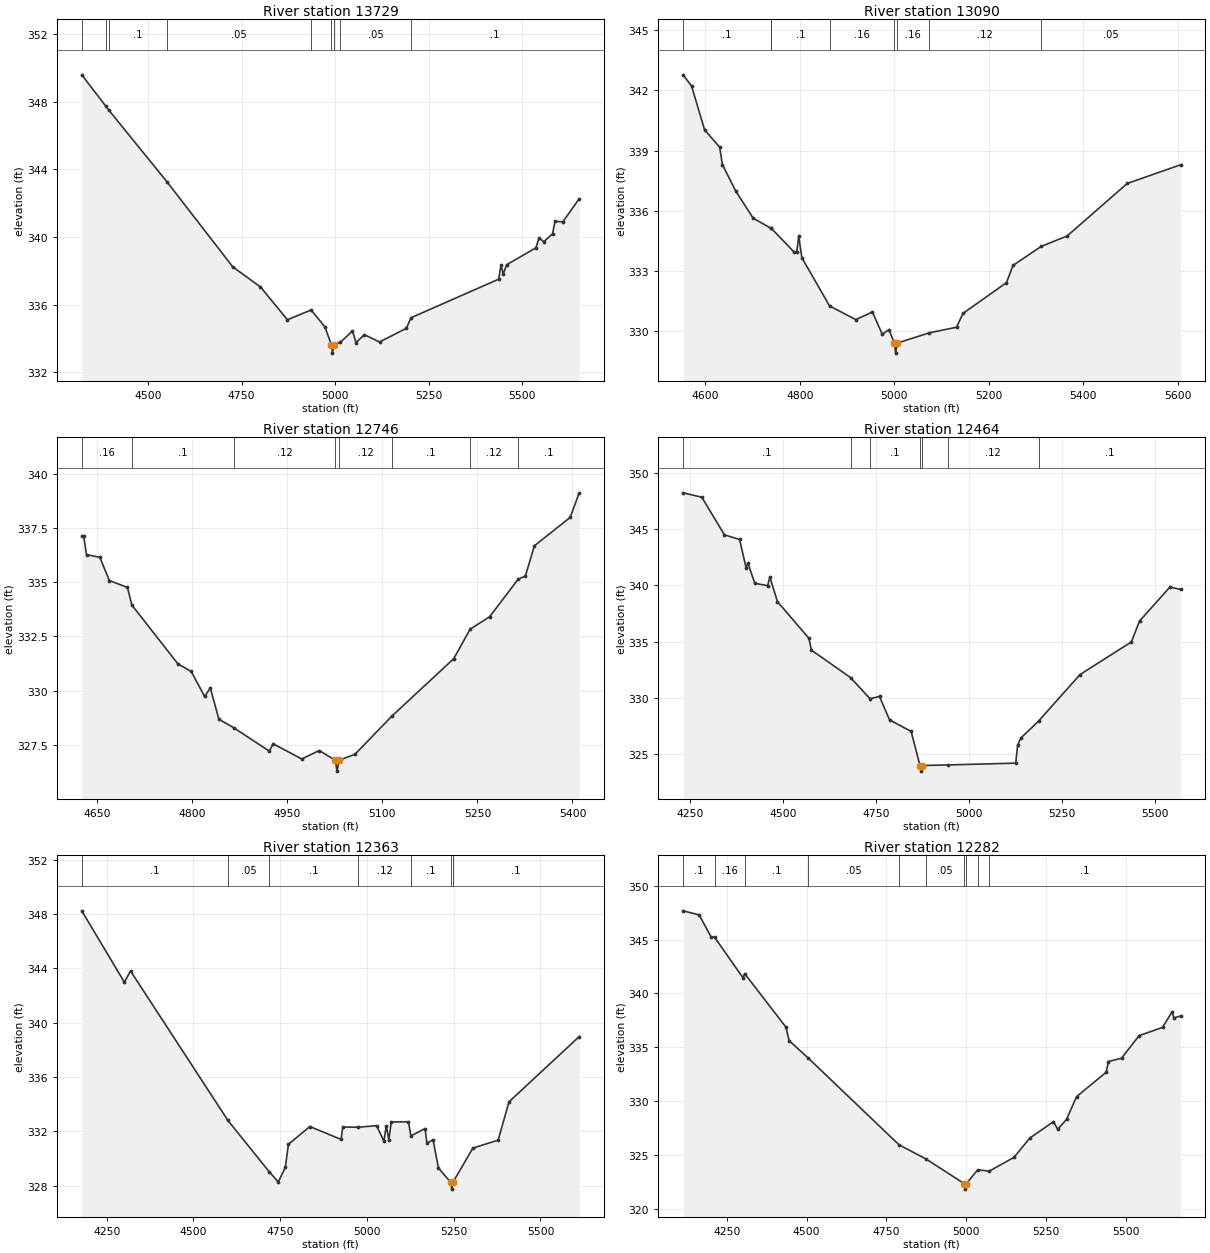
Type RM Length L Ch R = 1,13729,639,639,639
BEGIN DESCRIPTION:
UNT005 IN NURI 27.0
END DESCRIPTION:
XS GIS Cut Line= 4
      2301460.30     13355454.58      2300924.24     13355417.68
      2300661.65     13355506.66      2300377.36     13355936.34
#Sta/Elev= 30
  4322.9  349.58  4386.7  347.74  4395.7  347.48  4550.3  343.27  4726.4  338.24
  4800.5  337.05  4872.8  335.11  4935.8  335.69  4972.7  334.70  4990.2  333.64
  4993.0  333.14  4996.2  333.64  5014.2  333.78  5046.6  334.45  5056.0  333.76
  5078.3  334.23  5118.9  333.80  5190.8  334.61  5203.0  335.23  5437.5  337.51
  5443.6  338.35  5449.6  337.81  5458.6  338.36  5536.8  339.36  5545.4  339.95
  5557.9  339.72  5581.4  340.19  5588.0  340.92  5609.0  340.90  5652.7  342.26
#Mann=9,-1,0
  4322.9     0.1       0  4386.7    0.05       0  4395.7     0.1       0
  4550.3    0.05       0  4935.8    0.12       0  4990.2    0.07       0
  4996.2    0.12       0  5014.2    0.05       0  5203.0     0.1       0
Bank Sta=4990.2,4996.2
Exp/Cntr=0.3,0.1

Type RM Length L Ch R = 1,13090,344,344,344
BEGIN DESCRIPTION:
UNT005 IN NURI 26.0
END DESCRIPTION:
XS GIS Cut Line= 3
      2300835.25     13354781.42      2300628.27     13354896.41
      2300007.31     13355425.38
#Sta/Elev= 30
  4553.3  342.78  4571.2  342.22  4598.7  340.04  4630.6  339.18  4636.4  338.31
  4664.9  336.98  4701.6  335.64  4738.9  335.14  4739.3  335.15  4787.5  333.97
  4793.7  333.97  4797.9  334.74  4804.5  333.67  4863.2  331.27  4918.7  330.59
  4953.8  330.97  4974.7  329.86  4989.0  330.09  5000.2  329.42  5003.0  328.92
  5006.2  329.42  5074.1  329.93  5131.8  330.21  5145.5  330.90  5237.4  332.43
  5251.4  333.29  5311.3  334.24  5365.6  334.75  5493.0  337.37  5605.8  338.30
#Mann=8,-1,0
  4553.3     0.1       0  4738.9    0.05       0  4739.3     0.1       0
  4863.2    0.16       0  5000.2    0.07       0  5006.2    0.16       0
  5074.1    0.12       0  5311.3    0.05       0
Bank Sta=5000.2,5006.2
Exp/Cntr=0.3,0.1

Type RM Length L Ch R = 1,12746,282,282,282
BEGIN DESCRIPTION:
UNT005 IN NURI 25.0
END DESCRIPTION:
XS GIS Cut Line= 3
      2300537.69     13354596.87      2300237.72     13354796.85
      2299937.71     13355096.86
#Sta/Elev= 30
  4625.8  337.10  4628.8  337.10  4633.3  336.26  4654.3  336.14  4669.3  335.07
  4697.9  334.75  4704.8  333.94  4777.5  331.23  4798.5  330.88  4819.6  329.73
  4828.6  330.12  4842.1  328.68  4865.5  328.29  4921.7  327.21  4927.7  327.55
  4972.8  326.85  5000.5  327.24  5025.8  326.79  5028.5  326.29  5031.8  326.79
  5057.0  327.07  5114.9  328.82  5212.6  331.47  5238.5  332.83  5269.2  333.40
  5314.3  335.13  5325.7  335.28  5339.9  336.67  5396.4  337.98  5410.6  339.11
#Mann=8,-1,0
  4625.8    0.16       0  4704.8     0.1       0  4865.5    0.12       0
  5025.8    0.07       0  5031.8    0.12       0  5114.9     0.1       0
  5238.5    0.12       0  5314.3     0.1       0
Bank Sta=5025.8,5031.8
Exp/Cntr=0.3,0.1

Type RM Length L Ch R = 1,12464,101,101,101
BEGIN DESCRIPTION:
Mapping XS fbfad90a
END DESCRIPTION:
XS GIS Cut Line= 4
      2300807.07     13354410.73      2300125.62     13354536.60
      2299980.23     13354645.11      2299823.99     13355081.28
#Sta/Elev= 30
  4231.9  348.23  4282.1  347.84  4343.1  344.49  4383.8  344.08  4401.1  341.58
  4406.2  341.98  4424.5  340.19  4459.2  339.97  4465.1  340.75  4485.5  338.56
  4570.2  335.29  4577.0  334.24  4682.1  331.80  4734.5  329.92  4760.0  330.12
  4787.0  328.04  4845.1  327.01  4868.9  323.98  4871.6  323.48  4874.9  323.98
  4943.3  324.03  5126.3  324.19  5131.6  325.80  5140.0  326.42  5187.8  327.93
  5299.3  332.07  5437.4  334.97  5459.4  336.83  5541.0  339.85  5569.6  339.64
#Mann=7,-1,0
  4231.9     0.1       0  4682.1    0.05       0  4734.5     0.1       0
  4868.9    0.07       0  4874.9     0.1       0  4943.3    0.12       0
  5187.8     0.1       0
Bank Sta=4868.9,4874.9
Exp/Cntr=0.3,0.1

Type RM Length L Ch R = 1,12363,81,81,81
BEGIN DESCRIPTION:
UNT005 IN NURI 24.0
END DESCRIPTION:
XS GIS Cut Line= 4
      2300809.24     13354362.99      2300040.99     13354464.99
      2299912.95     13354593.03      2299778.41     13355050.91
#Sta/Elev= 30
  4178.3  348.23  4300.9  342.98  4318.8  343.80  4599.3  332.80  4718.3  329.02
  4744.7  328.27  4764.9  329.35  4773.7  331.04  4835.5  332.35  4925.4  331.40
  4930.4  332.31  4974.2  332.30  5027.6  332.41  5048.8  331.28  5055.9  332.42
  5063.0  331.38  5070.1  332.68  5119.6  332.70  5126.5  331.66  5167.5  332.20
  5172.7  331.13  5190.5  331.37  5206.1  329.29  5241.7  328.24  5244.4  327.74
  5247.7  328.24  5305.1  330.76  5378.1  331.35  5409.3  334.17  5611.6  338.97
#Mann=7,-1,0
  4178.3     0.1       0  4599.3    0.05       0  4718.3     0.1       0
  4974.2    0.12       0  5126.5     0.1       0  5241.7    0.07       0
  5247.7     0.1       0
Bank Sta=5241.7,5247.7
Exp/Cntr=0.3,0.1

Type RM Length L Ch R = 1,12282,441,441,441
BEGIN DESCRIPTION:
Mapping XS b4b6f5f4
END DESCRIPTION:
XS GIS Cut Line= 4
      2300817.95     13354282.69      2300054.01     13354360.82
      2299847.85     13354519.24      2299717.85     13355032.72
#Sta/Elev= 30
  4113.2  347.66  4163.7  347.28  4201.1  345.21  4211.5  345.22  4300.5  341.46
  4305.9  341.84  4435.1  336.88  4445.1  335.63  4505.6  333.99  4789.2  325.97
  4874.1  324.65  4994.0  322.36  4996.7  321.86  5000.0  322.36  5035.6  323.65
  5071.9  323.53  5149.0  324.80  5199.1  326.60  5272.8  328.11  5286.2  327.41
  5314.0  328.34  5345.0  330.43  5437.8  332.69  5445.1  333.69  5486.1  334.00
  5541.0  336.09  5614.3  336.85  5644.1  338.29  5650.1  337.73  5670.8  337.91
#Mann=10,-1,0
  4113.2     0.1       0  4211.5    0.16       0  4305.9     0.1       0
  4505.6    0.05       0  4789.2     0.1       0  4874.1    0.05       0
  4994.0    0.03       0  5000.0    0.05       0  5035.6    0.12       0
  5071.9     0.1       0
Bank Sta=4994,5000
Exp/Cntr=0.3,0.1

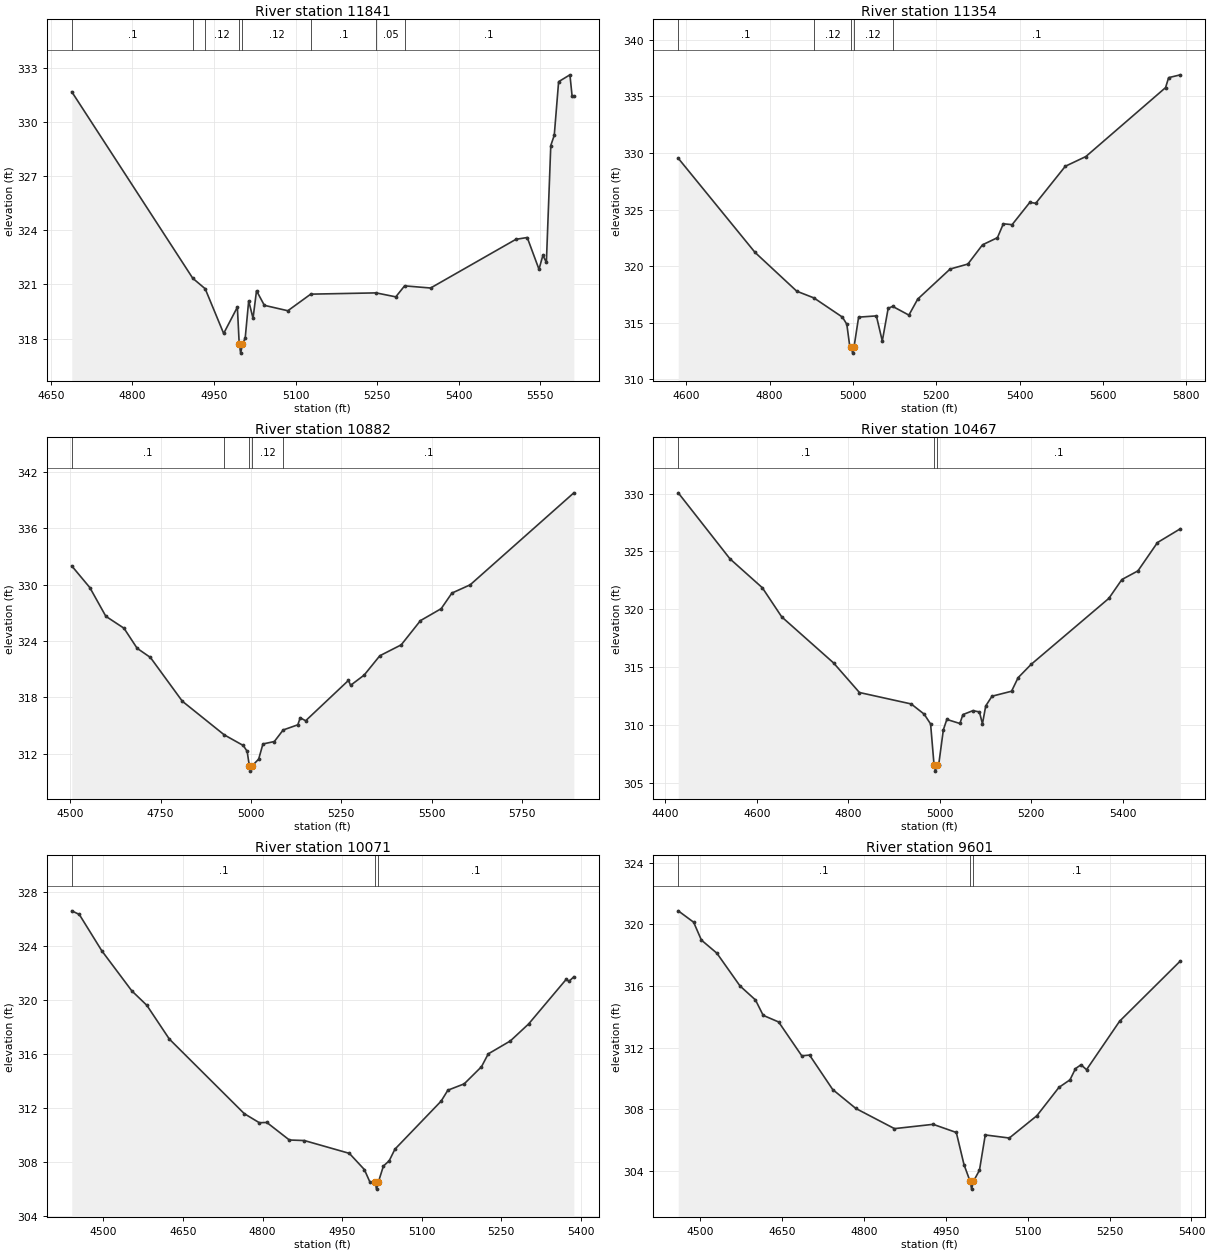
Type RM Length L Ch R = 1,11841,487,487,487
BEGIN DESCRIPTION:
UNT005 IN NURI 23.0
END DESCRIPTION:
XS GIS Cut Line= 3
      2299887.73     13353896.84      2299687.72     13354096.85
      2299287.70     13354596.88
#Sta/Elev= 30
  4688.5  331.68  4911.0  321.34  4933.8  320.76  4967.8  318.28  4993.0  319.74
  4996.4  317.69  4999.1  317.19  5002.4  317.69  5007.4  318.02  5013.8  320.09
  5021.8  319.12  5028.2  320.65  5042.6  319.84  5085.8  319.54  5127.9  320.46
  5248.1  320.53  5284.3  320.31  5300.5  320.92  5348.3  320.80  5505.2  323.50
  5526.0  323.60  5547.6  321.84  5554.8  322.61  5561.2  322.22  5569.3  328.70
  5575.7  329.27  5583.7  332.24  5604.5  332.62  5608.5  331.44  5611.7  331.44
#Mann=8,-1,0
  4688.5     0.1       0  4911.0    0.05       0  4933.8    0.12       0
  4996.4    0.07       0  5002.4    0.12       0  5127.9     0.1       0
  5248.1    0.05       0  5300.5     0.1       0
Bank Sta=4996.4,5002.4
Exp/Cntr=0.3,0.1

Type RM Length L Ch R = 1,11354,472,472,472
BEGIN DESCRIPTION:
UNT005 IN NURI 22.0
END DESCRIPTION:
XS GIS Cut Line= 3
      2299537.71     13353646.87      2299287.72     13353946.85
      2298687.74     13354496.83
#Sta/Elev= 30
  4581.0  329.54  4765.2  321.22  4865.4  317.79  4906.4  317.20  4974.9  315.50
  4985.4  314.87  4992.8  312.83  4996.5  312.82  4999.3  312.32  5002.5  312.82
  5013.7  315.50  5056.3  315.61  5070.5  313.39  5084.6  316.28  5095.4  316.45
  5134.3  315.68  5155.6  317.10  5233.2  319.75  5275.8  320.19  5310.9  321.89
  5346.7  322.52  5360.9  323.75  5381.9  323.67  5424.4  325.64  5438.6  325.56
  5509.5  328.83  5558.8  329.69  5750.0  335.78  5757.4  336.66  5785.4  336.91
#Mann=5,-1,0
  4581.0     0.1       0  4906.4    0.12       0  4996.5    0.07       0
  5002.5    0.12       0  5095.4     0.1       0
Bank Sta=4996.5,5002.5
Exp/Cntr=0.3,0.1

Type RM Length L Ch R = 1,10882,415,415,415
BEGIN DESCRIPTION:
UNT005 IN NURI 21.0
END DESCRIPTION:
XS GIS Cut Line= 3
      2299337.72     13353446.85      2298937.72     13353696.85
      2298487.71     13354496.87
#Sta/Elev= 30
  4504.0  331.99  4554.1  329.68  4598.3  326.63  4648.5  325.36  4685.0  323.22
  4721.6  322.25  4810.0  317.59  4926.0  314.01  4978.6  312.88  4989.4  312.26
  4995.7  310.65  4998.4  310.15  5001.7  310.65  5021.3  311.43  5033.1  313.04
  5064.6  313.30  5089.1  314.53  5129.6  315.08  5136.3  315.83  5151.3  315.51
  5269.9  319.81  5275.6  319.28  5313.2  320.37  5356.6  322.43  5415.8  323.59
  5469.1  326.17  5526.4  327.44  5556.1  329.10  5606.7  329.98  5893.6  339.77
#Mann=5,-1,0
  4504.0     0.1       0  4926.0    0.12       0  4995.7    0.07       0
  5001.7    0.12       0  5089.1     0.1       0
Bank Sta=4995.7,5001.7
Exp/Cntr=0.3,0.1

Type RM Length L Ch R = 1,10467,396,396,396
BEGIN DESCRIPTION:
UNT005 IN NURI 20.0
END DESCRIPTION:
XS GIS Cut Line= 3
      2298987.70     13353096.87      2298587.72     13353496.85
      2298237.70     13353896.88
#Sta/Elev= 30
  4428.3  330.06  4541.4  324.35  4612.1  321.85  4654.5  319.33  4767.7  315.35
  4824.3  312.79  4937.4  311.80  4965.7  310.92  4979.8  310.07  4987.4  306.49
  4990.2  305.99  4993.4  306.49  4997.3  306.49  5007.7  309.57  5015.3  310.46
  5043.8  310.11  5050.4  310.88  5072.3  311.22  5086.5  311.11  5093.1  310.08
  5100.3  311.63  5114.0  312.47  5156.7  312.90  5171.0  314.07  5199.4  315.22
  5369.3  320.93  5397.8  322.56  5432.9  323.31  5475.6  325.76  5525.5  326.95
#Mann=3,-1,0
  4428.3     0.1       0  4987.4    0.07       0  4993.4     0.1       0
Bank Sta=4987.4,4993.4
Exp/Cntr=0.3,0.1

Type RM Length L Ch R = 1,10071,470,470,470
BEGIN DESCRIPTION:
UNT005 IN NURI 19.0
END DESCRIPTION:
XS GIS Cut Line= 3
      2298687.75     13352846.83      2298287.72     13353246.85
      2298137.73     13353596.84
#Sta/Elev= 30
  4440.2  326.62  4454.4  326.35  4496.8  323.66  4553.4  320.69  4581.7  319.62
  4624.1  317.12  4765.5  311.59  4793.8  310.92  4807.9  310.94  4850.4  309.64
  4878.6  309.60  4963.5  308.65  4991.8  307.45  5002.4  306.51  5012.0  306.50
  5014.7  306.00  5018.0  306.50  5027.7  307.71  5038.6  308.10  5049.4  308.96
  5136.5  312.52  5149.2  313.33  5180.0  313.80  5212.6  315.07  5225.3  316.02
  5267.0  316.98  5301.5  318.24  5372.2  321.54  5377.6  321.40  5386.7  321.73
#Mann=3,-1,0
  4440.2     0.1       0  5012.0    0.07       0  5018.0     0.1       0
Bank Sta=5012,5018
Exp/Cntr=0.3,0.1

Type RM Length L Ch R = 1,9601,523,523,523
BEGIN DESCRIPTION:
UNT005 IN NURI 18.0
END DESCRIPTION:
XS GIS Cut Line= 3
      2298287.69     13352646.88      2297887.72     13353046.85
      2297837.72     13353396.85
#Sta/Elev= 30
  4460.4  320.88  4488.6  320.14  4502.8  318.98  4531.1  318.13  4573.5  316.00
  4601.8  315.09  4615.9  314.09  4644.2  313.66  4686.6  311.46  4700.8  311.51
  4743.2  309.27  4785.6  308.04  4856.3  306.73  4927.1  307.01  4969.5  306.48
  4983.6  304.39  4994.8  303.30  4997.5  302.80  5000.8  303.30  5011.9  304.03
  5022.5  306.32  5066.5  306.12  5117.0  307.57  5157.4  309.41  5177.6  309.90
  5187.7  310.63  5197.8  310.88  5207.9  310.56  5268.5  313.71  5379.6  317.62
#Mann=3,-1,0
  4460.4     0.1       0  4994.8    0.07       0  5000.8     0.1       0
Bank Sta=4994.8,5000.8
Exp/Cntr=0.3,0.1

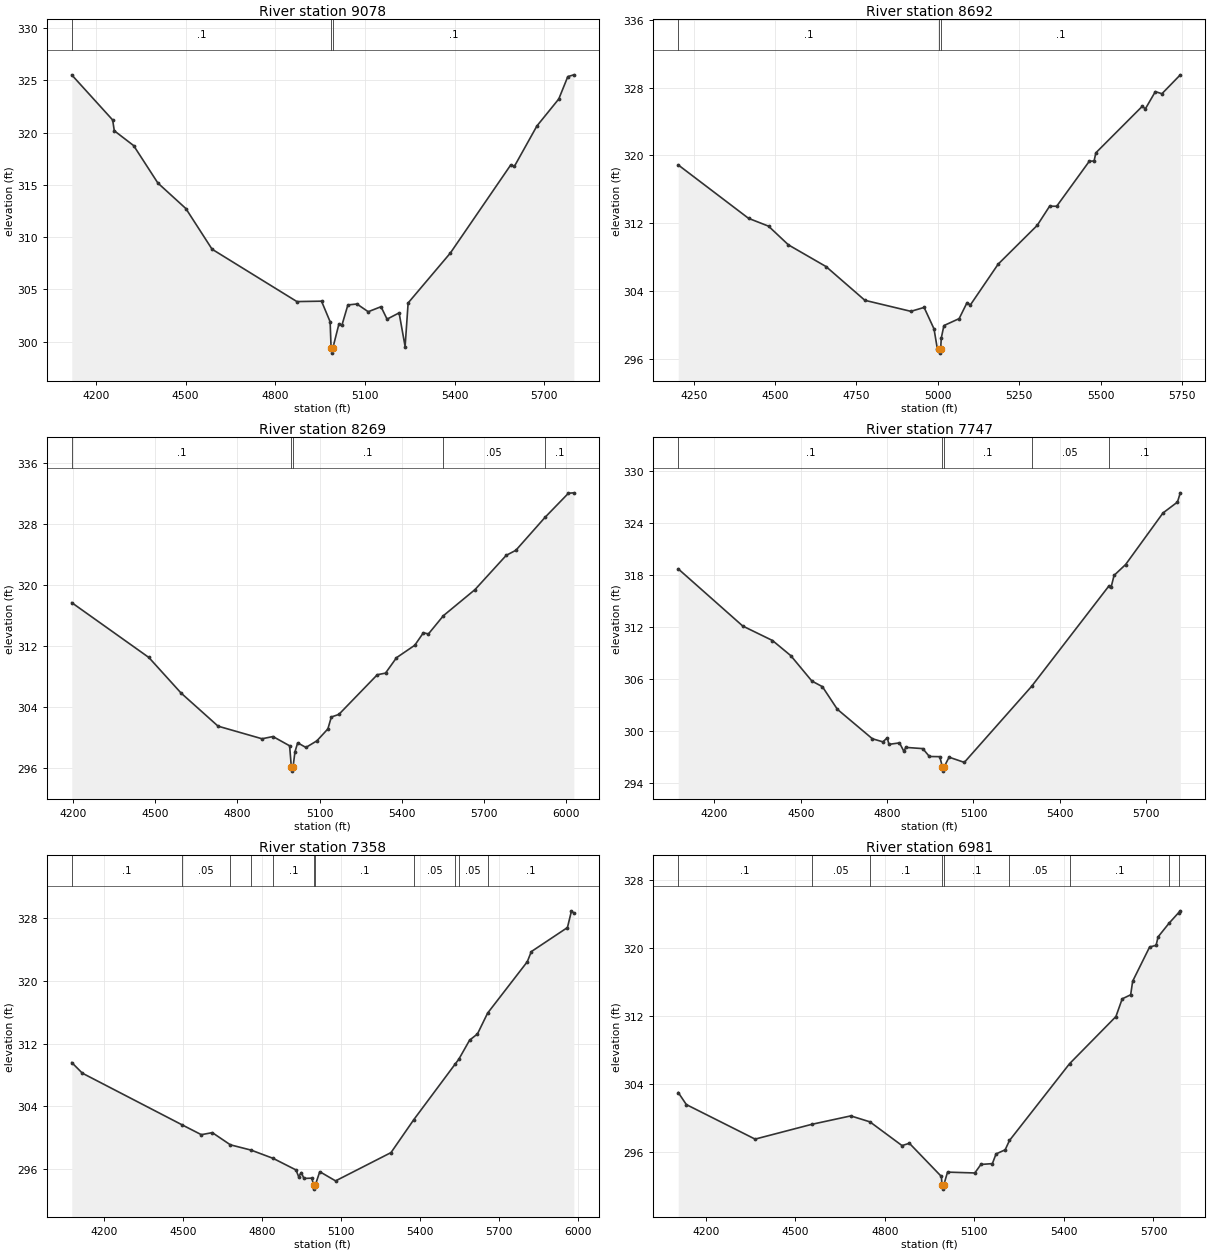
Type RM Length L Ch R = 1,9078,386,386,386
BEGIN DESCRIPTION:
UNT005 IN NURI 17.0
END DESCRIPTION:
XS GIS Cut Line= 3
      2298287.69     13352496.87      2297487.72     13352846.85
      2296687.72     13352946.85
#Sta/Elev= 30
  4119.0  325.52  4255.8  321.21  4261.2  320.18  4326.0  318.76  4407.0  315.18
  4500.6  312.74  4588.3  308.85  4872.1  303.84  4954.4  303.88  4983.2  301.91
  4986.4  299.41  4989.2  298.91  4992.4  299.41  5012.3  301.66  5022.4  301.56
  5042.6  303.52  5072.8  303.61  5110.6  302.87  5153.4  303.35  5173.6  302.16
  5213.9  302.76  5234.0  299.54  5244.1  303.71  5385.2  308.48  5586.8  316.89
  5599.4  316.77  5674.9  320.64  5748.0  323.22  5778.2  325.36  5798.4  325.53
#Mann=3,-1,0
  4119.0     0.1       0  4986.4    0.07       0  4992.4     0.1       0
Bank Sta=4986.4,4992.4
Exp/Cntr=0.3,0.1

Type RM Length L Ch R = 1,8692,423,423,423
BEGIN DESCRIPTION:
UNT005 IN NURI 16.0
END DESCRIPTION:
XS GIS Cut Line= 3
      2298029.34     13352400.97      2297580.85     13352492.97
      2296512.08     13352676.85
#Sta/Elev= 30
  4202.5  318.88  4418.5  312.58  4479.8  311.66  4541.0  309.45  4656.6  306.89
  4775.9  302.91  4917.2  301.61  4957.8  302.07  4988.2  299.54  4998.4  297.20
  5002.5  297.18  5005.3  296.68  5008.5  297.18  5010.6  298.47  5018.6  299.93
  5065.4  300.75  5089.7  302.64  5099.8  302.36  5185.3  307.18  5305.2  311.75
  5343.3  314.01  5365.1  314.01  5465.1  319.31  5479.9  319.35  5485.4  320.31
  5627.5  325.78  5637.6  325.51  5668.1  327.53  5688.3  327.28  5744.8  329.51
#Mann=3,-1,0
  4202.5     0.1       0  5002.5    0.07       0  5008.5     0.1       0
Bank Sta=5002.5,5008.5
Exp/Cntr=0.3,0.1

Type RM Length L Ch R = 1,8269,522,522,522
BEGIN DESCRIPTION:
UNT005 IN NURI 15.0
END DESCRIPTION:
XS GIS Cut Line= 4
      2297983.30     13352216.97      2297592.35     13352136.48
      2296706.88     13352193.98      2296292.90     13352550.46
#Sta/Elev= 30
  4195.2  317.68  4476.6  310.50  4594.2  305.84  4729.3  301.50  4889.6  299.85
  4929.7  300.14  4990.4  298.93  4996.8  296.11  4999.6  295.61  5002.8  296.11
  5009.9  298.13  5019.9  299.32  5049.9  298.71  5090.0  299.58  5130.1  301.14
  5142.7  302.70  5170.2  303.04  5310.5  308.24  5340.5  308.45  5380.6  310.47
  5447.3  312.10  5478.8  313.74  5497.1  313.58  5552.0  315.98  5667.1  319.39
  5781.2  323.88  5816.3  324.54  5922.9  328.86  6008.3  332.02  6028.0  332.07
#Mann=5,-1,0
  4195.2     0.1       0  4996.8    0.07       0  5002.8     0.1       0
  5552.0    0.05       0  5922.9     0.1       0
Bank Sta=4996.8,5002.8
Exp/Cntr=0.3,0.1

Type RM Length L Ch R = 1,7747,389,389,389
BEGIN DESCRIPTION:
UNT005 IN NURI 14.0
END DESCRIPTION:
XS GIS Cut Line= 3
      2298037.74     13352146.86      2297237.72     13351646.85
      2296437.74     13351646.85
#Sta/Elev= 30
  4074.8  318.70  4298.9  312.10  4402.1  310.43  4465.7  308.68  4538.9  305.75
  4575.4  305.10  4627.3  302.49  4748.8  299.09  4785.3  298.73  4800.6  299.19
  4806.5  298.44  4843.1  298.61  4858.4  297.63  4864.9  298.09  4923.9  297.95
  4946.9  297.04  4982.8  297.02  4992.2  295.85  4995.0  295.35  4998.2  295.85
  5015.3  296.96  5068.2  296.36  5301.6  305.13  5569.6  316.70  5578.2  316.63
  5588.2  317.95  5628.2  319.20  5758.2  325.16  5808.2  326.41  5818.2  327.48
#Mann=5,-1,0
  4074.8     0.1       0  4992.2    0.07       0  4998.2     0.1       0
  5301.6    0.05       0  5569.6     0.1       0
Bank Sta=4992.2,4998.2
Exp/Cntr=0.3,0.1

Type RM Length L Ch R = 1,7358,377,377,377
BEGIN DESCRIPTION:
UNT005 IN NURI 13.0
END DESCRIPTION:
XS GIS Cut Line= 5
      2298006.36     13351734.02      2297764.85     13351400.50
      2297592.35     13351274.01      2296706.88     13351308.50
      2296373.42     13351515.48
#Sta/Elev= 30
  4078.6  309.58  4118.6  308.23  4494.8  301.69  4570.0  300.40  4611.7  300.66
  4680.1  299.11  4759.3  298.43  4842.7  297.38  4929.1  295.91  4939.1  295.05
  4949.1  295.58  4959.1  294.83  4989.1  294.87  4996.1  293.97  4998.9  293.47
  5002.1  293.97  5019.2  295.69  5079.2  294.52  5289.4  298.12  5376.0  302.32
  5533.7  309.43  5546.7  310.01  5587.5  312.43  5617.3  313.22  5655.8  315.87
  5806.3  322.41  5821.6  323.70  5958.6  326.76  5974.0  328.89  5982.9  328.59
#Mann=11,-1,0
  4078.6     0.1       0  4494.8    0.05       0  4680.1     0.1       0
  4759.3    0.05       0  4842.7     0.1       0  4996.1    0.07       0
  5002.1     0.1       0  5376.0    0.05       0  5533.7     0.1       0
  5546.7    0.05       0  5655.8     0.1       0
Bank Sta=4996.1,5002.1
Exp/Cntr=0.3,0.1

Type RM Length L Ch R = 1,6981,648,648,648
BEGIN DESCRIPTION:
UNT005 IN NURI 12.0
END DESCRIPTION:
XS GIS Cut Line= 4
      2297994.87     13350894.51      2297350.86     13350929.01
      2296649.38     13351055.51      2296431.82     13351295.97
#Sta/Elev= 30
  4107.9  303.00  4135.1  301.58  4365.4  297.52  4555.5  299.26  4685.9  300.25
  4750.1  299.55  4857.6  296.76  4882.3  297.03  4989.4  293.13  4991.5  292.14
  4994.3  291.64  4997.5  292.14  5010.1  293.64  5101.5  293.54  5121.8  294.54
  5160.3  294.64  5172.6  295.78  5203.1  296.26  5217.6  297.36  5418.7  306.38
  5574.2  311.93  5595.2  314.01  5623.6  314.49  5630.3  316.09  5687.1  320.11
  5708.7  320.30  5715.5  321.30  5752.3  322.91  5783.9  324.13  5789.9  324.36
#Mann=9,-1,0
  4107.9     0.1       0  4555.5    0.05       0  4750.1     0.1       0
  4991.5    0.07       0  4997.5     0.1       0  5217.6    0.05       0
  5418.7     0.1       0  5752.3    0.08       0  5783.9     0.1       0
Bank Sta=4991.5,4997.5
Exp/Cntr=0.3,0.1

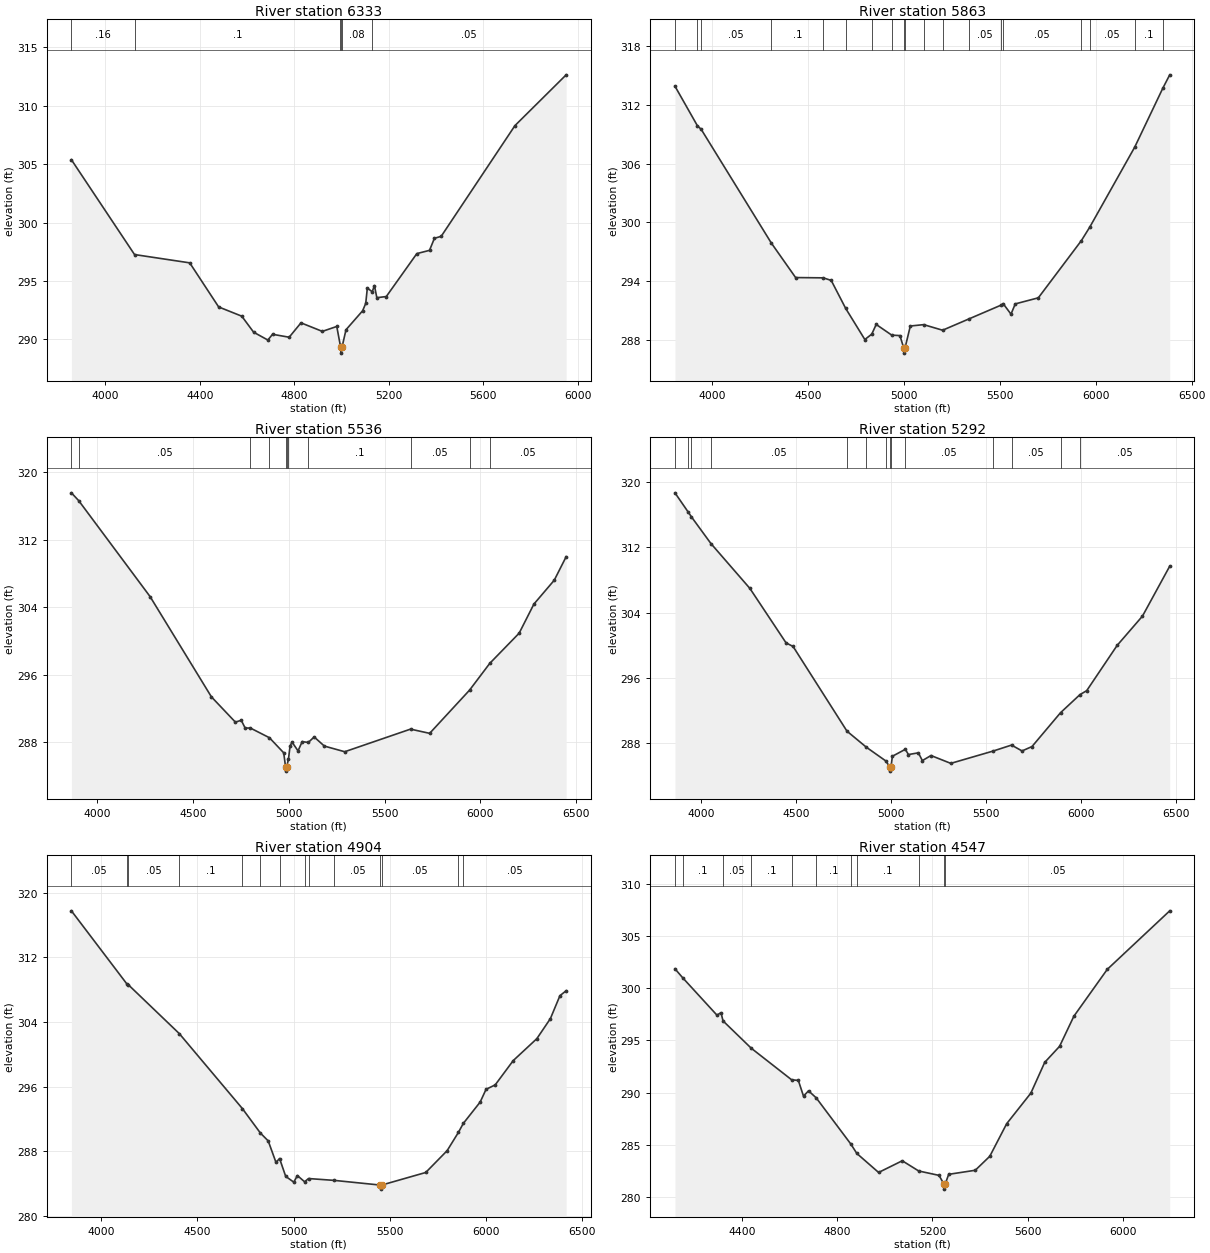
Type RM Length L Ch R = 1,6333,470,470,470
BEGIN DESCRIPTION:
UNT005 IN NURI 11.0
END DESCRIPTION:
XS GIS Cut Line= 4
      2298063.80     13350549.51      2297615.35     13350434.53
      2296614.88     13350354.03      2296212.56     13350836.81
#Sta/Elev= 30
  3855.8  305.37  4123.1  297.26  4356.8  296.55  4479.3  292.78  4577.2  291.99
  4627.4  290.62  4687.6  289.95  4707.6  290.44  4777.9  290.19  4828.0  291.42
  4918.3  290.69  4979.5  291.11  4994.0  289.54  4995.6  289.33  4998.3  288.83
  5001.6  289.33  5018.6  290.83  5088.9  292.45  5102.1  293.08  5108.9  294.39
  5129.7  294.08  5139.0  294.61  5149.1  293.57  5189.2  293.67  5318.5  297.34
  5372.2  297.62  5393.0  298.65  5421.7  298.82  5734.1  308.29  5950.9  312.63
#Mann=6,-1,0
  3855.8    0.16       0  4123.1     0.1       0  4994.0    0.08       0
  4995.6    0.07       0  5001.6    0.08       0  5129.7    0.05       0
Bank Sta=4995.6,5001.6
Exp/Cntr=0.3,0.1

Type RM Length L Ch R = 1,5863,327,327,327
BEGIN DESCRIPTION:
UNT005 IN NURI 10.0
END DESCRIPTION:
XS GIS Cut Line= 3
      2298337.75     13350296.86      2297137.72     13349996.85
      2295937.72     13349396.86
#Sta/Elev= 30
  3807.1  313.91  3924.0  309.87  3943.9  309.50  4309.2  297.89  4435.9  294.36
  4580.2  294.33  4621.4  294.07  4697.1  291.20  4796.7  288.03  4832.8  288.58
  4855.9  289.57  4936.8  288.48  4979.6  288.43  4999.8  287.14  5002.6  286.64
  5005.8  287.14  5033.8  289.41  5103.4  289.55  5202.0  288.98  5337.5  290.12
  5508.7  291.56  5517.4  291.70  5558.4  290.62  5580.7  291.67  5700.9  292.29
  5925.1  298.13  5969.2  299.52  6203.4  307.69  6349.6  313.70  6385.7  315.07
#Mann=19,-1,0
  3807.1    0.05       0  3924.0     0.1       0  3943.9    0.05       0
  4309.2     0.1       0  4580.2    0.05       0  4697.1     0.1       0
  4832.8    0.16       0  4936.8    0.08       0  4999.8    0.07       0
  5005.8    0.08       0  5103.4    0.05       0  5202.0     0.1       0
  5337.5    0.05       0  5508.7     0.1       0  5517.4    0.05       0
  5925.1     0.1       0  5969.2    0.05       0  6203.4     0.1       0
  6349.6    0.05       0
Bank Sta=4999.8,5005.8
Exp/Cntr=0.3,0.1

Type RM Length L Ch R = 1,5536,244,244,244
BEGIN DESCRIPTION:
Mapping XS c3e44dbf
END DESCRIPTION:
XS GIS Cut Line= 3
      2298497.92     13349967.56      2297352.11     13349751.42
      2296047.40     13349207.14
#Sta/Elev= 30
  3867.1  317.55  3905.6  316.61  4277.5  305.24  4597.0  293.36  4722.1  290.36
  4752.6  290.58  4773.0  289.66  4800.2  289.66  4899.6  288.51  4974.1  286.72
  4983.7  285.05  4986.5  284.55  4989.7  285.05  4999.0  286.00  5007.1  287.50
  5017.2  288.00  5048.7  286.95  5070.4  288.05  5102.2  287.95  5132.9  288.60
  5186.0  287.52  5292.1  286.85  5635.2  289.53  5735.0  289.03  5943.3  294.16
  6048.5  297.33  6201.7  300.91  6278.6  304.36  6384.7  307.19  6446.8  309.98
#Mann=11,-1,0
  3867.1     0.1       0  3905.6    0.05       0  4800.2     0.1       0
  4899.6    0.16       0  4983.7    0.07       0  4989.7    0.16       0
  4999.0    0.08       0  5102.2     0.1       0  5635.2    0.05       0
  5943.3     0.1       0  6048.5    0.05       0
Bank Sta=4983.7,4989.7
Exp/Cntr=0.3,0.1

Type RM Length L Ch R = 1,5292,388,388,388
BEGIN DESCRIPTION:
UNT005 IN NURI 9.0
END DESCRIPTION:
XS GIS Cut Line= 3
      2298545.80     13349886.65      2297264.58     13349463.05
      2296066.68     13349077.64
#Sta/Elev= 30
  3860.8  318.67  3931.6  316.28  3947.9  315.72  4050.4  312.46  4256.0  306.96
  4446.4  300.30  4483.4  299.86  4767.6  289.49  4870.0  287.52  4972.5  285.84
  4993.3  285.10  4996.0  284.60  4999.3  285.10  5006.8  286.42  5074.9  287.27
  5091.5  286.63  5143.7  286.84  5164.8  285.89  5210.2  286.51  5314.7  285.55
  5538.1  287.06  5634.8  287.79  5690.2  287.07  5742.7  287.61  5893.0  291.75
  5995.2  293.96  6031.0  294.45  6191.4  299.99  6325.0  303.58  6468.6  309.69
#Mann=14,-1,0
  3860.8     0.1       0  3931.6    0.05       0  3947.9     0.1       0
  4050.4    0.05       0  4767.6     0.1       0  4870.0    0.16       0
  4972.5    0.08       0  4993.3    0.07       0  4999.3    0.08       0
  5074.9    0.05       0  5538.1     0.1       0  5634.8    0.05       0
  5893.0     0.1       0  5995.2    0.05       0
Bank Sta=4993.3,4999.3
Exp/Cntr=0.3,0.1

Type RM Length L Ch R = 1,4904,357,357,357
BEGIN DESCRIPTION:
UNT005 IN NURI 8.0
END DESCRIPTION:
XS GIS Cut Line= 3
      2298601.39     13349570.69      2297691.67     13349185.27
      2296125.65     13348959.57
#Sta/Elev= 30
  3846.2  317.77  4133.8  308.74  4142.4  308.61  4406.9  302.57  4734.3  293.30
  4828.3  290.26  4868.5  289.30  4908.9  286.64  4927.5  287.12  4959.4  284.91
  5001.6  284.19  5020.0  285.01  5057.6  284.24  5078.0  284.64  5212.2  284.41
  5451.5  283.83  5454.2  283.33  5457.5  283.83  5686.9  285.39  5798.0  288.09
  5856.3  290.34  5882.3  291.47  5969.8  294.11  6000.1  295.68  6047.7  296.23
  6141.5  299.24  6264.0  301.95  6334.4  304.43  6384.0  307.27  6416.4  307.88
#Mann=14,-1,0
  3846.2    0.05       0  4133.8     0.1       0  4142.4    0.05       0
  4406.9     0.1       0  4734.3    0.16       0  4828.3    0.08       0
  4927.5     0.1       0  5057.6    0.05       0  5078.0     0.1       0
  5212.2    0.05       0  5451.5    0.07       0  5457.5    0.05       0
  5856.3     0.1       0  5882.3    0.05       0
Bank Sta=5451.5,5457.5
Exp/Cntr=0.3,0.1

Type RM Length L Ch R = 1,4547,398,398,398
BEGIN DESCRIPTION:
UNT005 IN NURI 7.0
END DESCRIPTION:
XS GIS Cut Line= 4
      2298247.79     13349123.54      2297753.35     13348893.57
      2296775.88     13348721.07      2296235.35     13348744.08
#Sta/Elev= 30
  4118.1  301.87  4150.9  301.00  4294.6  297.42  4311.5  297.66  4320.1  296.87
  4438.6  294.25  4608.3  291.22  4636.5  291.16  4658.2  289.65  4679.3  290.16
  4711.5  289.49  4856.9  285.06  4882.4  284.15  4973.8  282.33  5073.2  283.45
  5142.3  282.47  5227.6  282.05  5247.9  281.23  5250.6  280.73  5253.9  281.23
  5268.2  282.15  5379.9  282.54  5440.9  283.88  5512.0  287.01  5613.5  289.94
  5671.7  292.89  5734.2  294.43  5794.3  297.32  5934.4  301.81  6197.0  307.43
#Mann=11,-1,0
  4118.1    0.05       0  4150.9     0.1       0  4320.1    0.05       0
  4438.6     0.1       0  4608.3    0.08       0  4711.5     0.1       0
  4856.9    0.05       0  4882.4     0.1       0  5142.3    0.05       0
  5247.9    0.07       0  5253.9    0.05       0
Bank Sta=5247.9,5253.9
Exp/Cntr=0.3,0.1