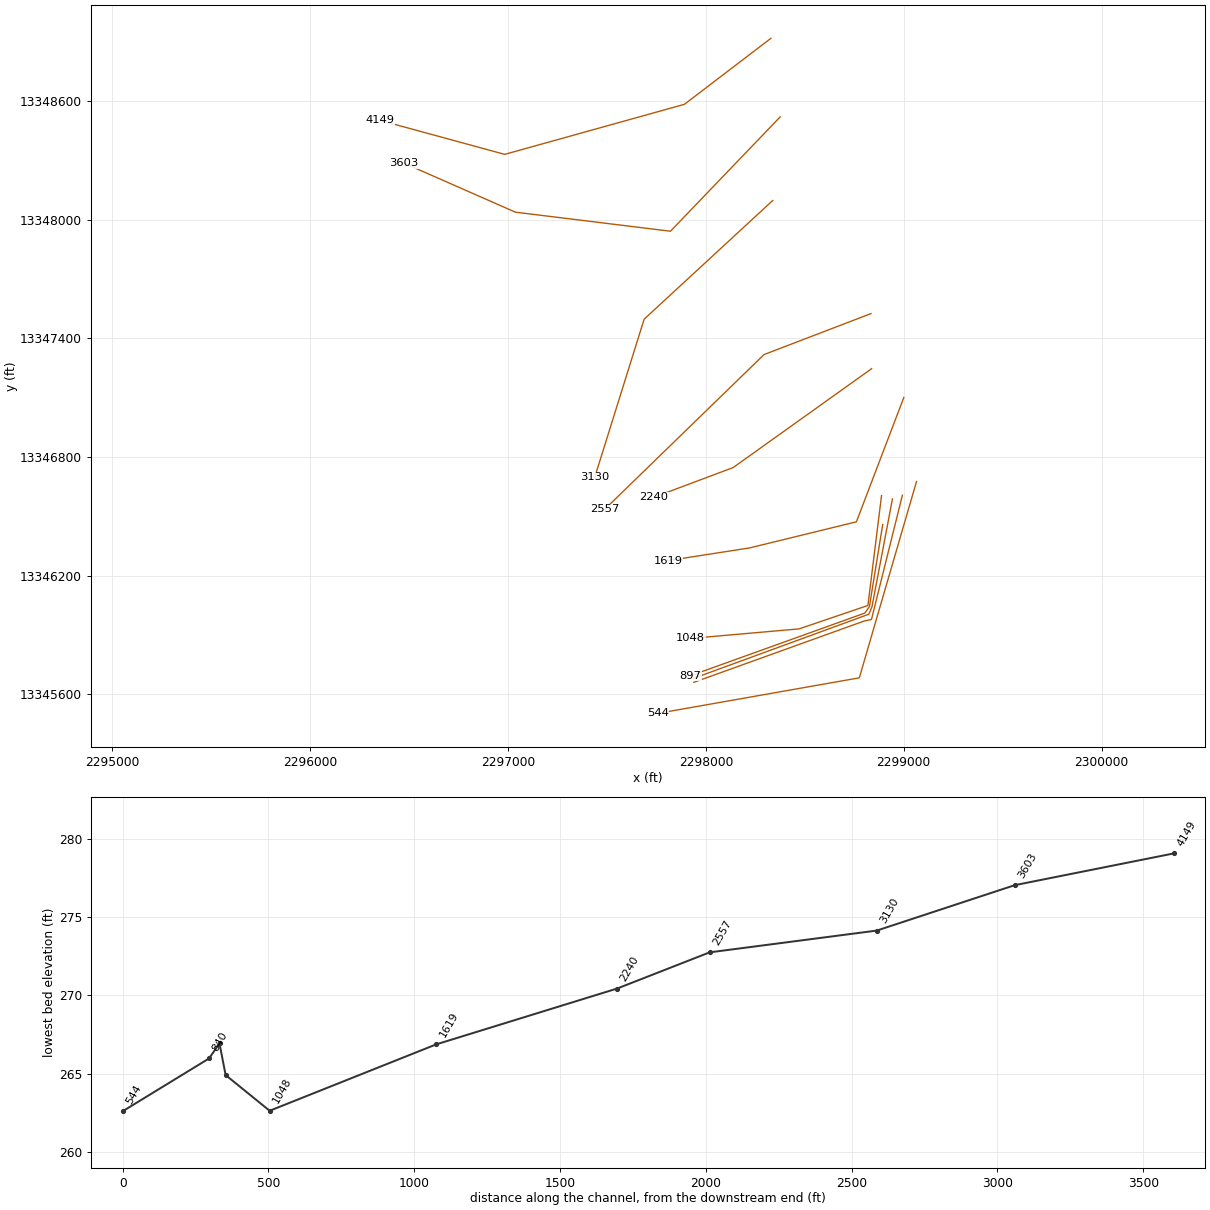
HEC-RAS study UNT005 IN NURI.prj: UNT005 IN NURI Base Level Engineering

--- UNT005 IN NURI.g01 (geometry) --- (continued)

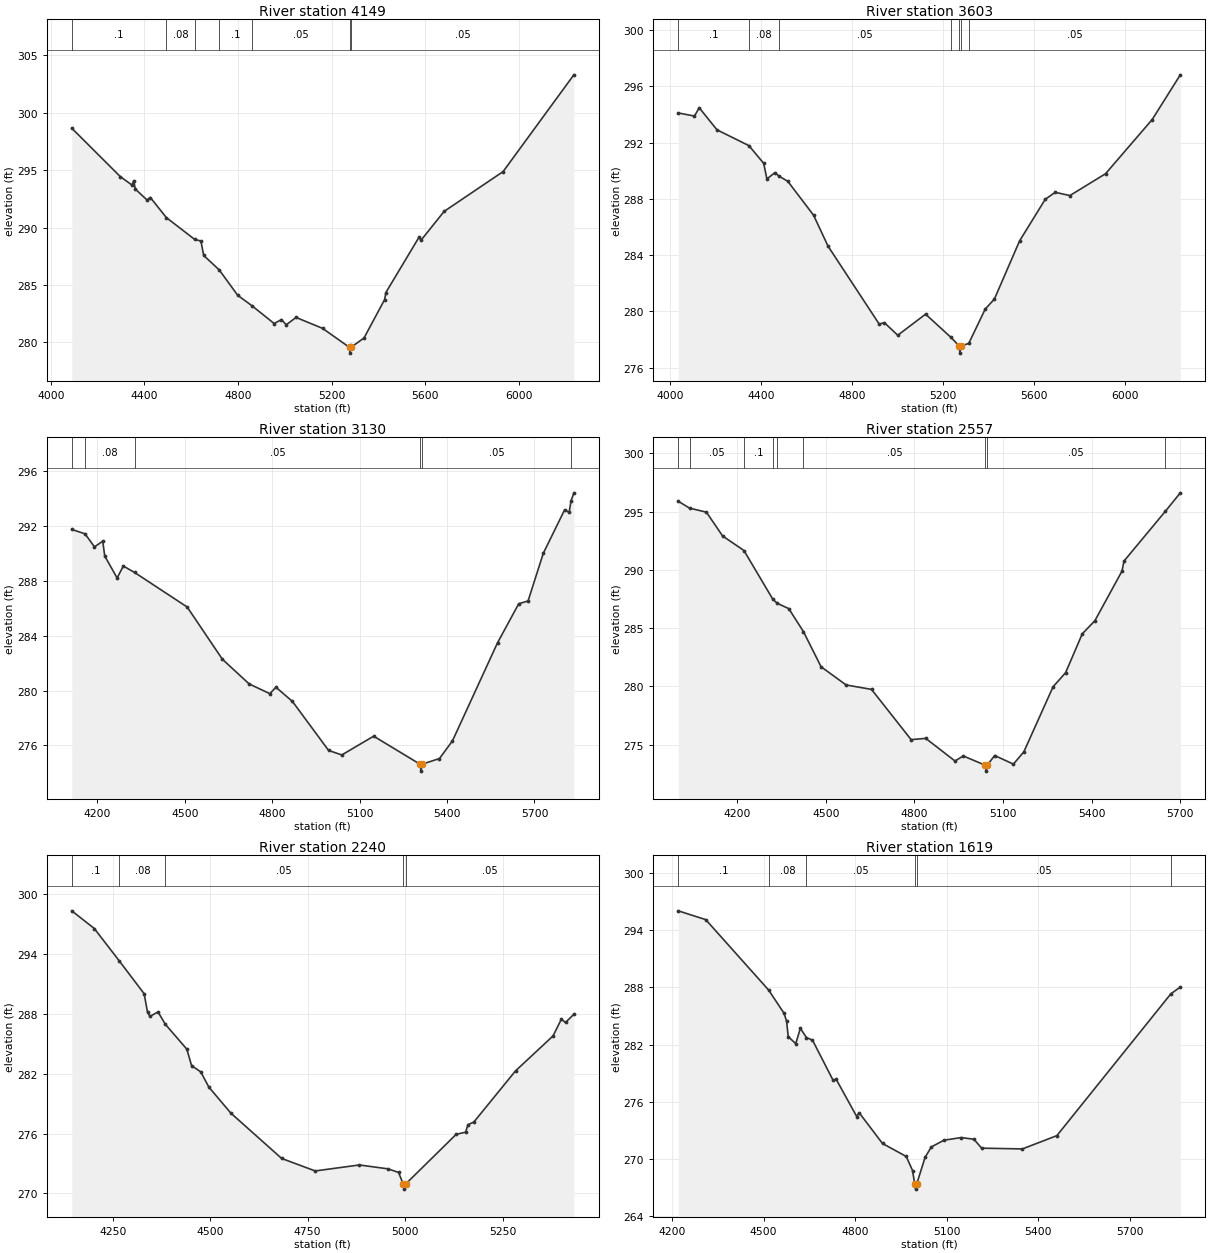
Type RM Length L Ch R = 1,4149,546,546,546
BEGIN DESCRIPTION:
UNT005 IN NURI 6.0
END DESCRIPTION:
XS GIS Cut Line= 4
      2298328.37     13348916.60      2297891.35     13348583.08
      2296982.87     13348330.09      2296352.87     13348501.90
#Sta/Elev= 30
  4089.3  298.66  4296.3  294.45  4346.2  293.71  4354.3  294.08  4360.7  293.36
  4410.6  292.41  4425.1  292.62  4493.6  290.87  4614.5  288.97  4641.3  288.83
  4653.2  287.57  4719.6  286.31  4798.5  284.10  4859.4  283.19  4954.2  281.64
  4985.4  281.98  5006.1  281.53  5047.7  282.17  5161.1  281.22  5276.3  279.56
  5279.0  279.06  5282.3  279.56  5338.3  280.38  5426.5  283.73  5431.7  284.34
  5573.7  289.17  5582.1  288.90  5680.7  291.41  5932.8  294.88  6235.1  303.31
#Mann=7,-1,0
  4089.3     0.1       0  4493.6    0.08       0  4614.5    0.05       0
  4719.6     0.1       0  4859.4    0.05       0  5276.3    0.03       0
  5282.3    0.05       0
Bank Sta=5276.3,5282.3
Exp/Cntr=0.3,0.1

Type RM Length L Ch R = 1,3603,473,473,473
BEGIN DESCRIPTION:
UNT005 IN NURI 5.0
END DESCRIPTION:
XS GIS Cut Line= 4
      2298375.55     13348519.64      2297820.86     13347941.52
      2297037.01     13348037.88      2296474.55     13348285.26
#Sta/Elev= 30
  4036.0  294.10  4107.3  293.88  4128.3  294.47  4206.2  292.90  4346.3  291.78
  4411.4  290.52  4425.5  289.41  4460.8  289.86  4478.9  289.61  4517.4  289.24
  4630.6  286.83  4694.1  284.63  4918.9  279.09  4941.1  279.20  5000.2  278.30
  5122.5  279.80  5233.2  278.16  5270.6  277.53  5273.3  277.03  5276.6  277.53
  5312.1  277.72  5384.4  280.16  5424.7  280.87  5535.5  285.01  5648.0  287.96
  5691.8  288.46  5756.4  288.23  5912.9  289.78  6117.8  293.63  6241.4  296.81
#Mann=7,-1,0
  4036.0     0.1       0  4346.3    0.08       0  4478.9    0.05       0
  5233.2     0.1       0  5270.6    0.03       0  5276.6     0.1       0
  5312.1    0.05       0
Bank Sta=5270.6,5276.6
Exp/Cntr=0.3,0.1

Type RM Length L Ch R = 1,3130,573,573,573
BEGIN DESCRIPTION:
UNT005 IN NURI 4.0
END DESCRIPTION:
XS GIS Cut Line= 3
      2298337.70     13348096.83      2297687.72     13347496.85
      2297437.72     13346696.86
#Sta/Elev= 30
  4112.5  291.76  4157.9  291.44  4190.4  290.49  4218.8  290.90  4225.6  289.82
  4268.1  288.22  4289.4  289.09  4328.1  288.62  4508.5  286.10  4629.3  282.29
  4721.2  280.49  4792.1  279.78  4813.1  280.25  4869.8  279.21  4993.7  275.64
  5039.0  275.31  5148.4  276.68  5307.8  274.63  5310.6  274.13  5313.8  274.63
  5374.2  275.05  5418.8  276.34  5573.3  283.49  5646.1  286.34  5678.1  286.54
  5730.4  290.02  5803.8  293.20  5819.0  293.00  5825.4  293.82  5835.2  294.43
#Mann=6,-1,0
  4112.5     0.1       0  4157.9    0.08       0  4328.1    0.05       0
  5307.8    0.03       0  5313.8    0.05       0  5825.4     0.1       0
Bank Sta=5307.8,5313.8
Exp/Cntr=0.3,0.1

Type RM Length L Ch R = 1,2557,317,317,317
BEGIN DESCRIPTION:
UNT005 IN NURI 3.0
END DESCRIPTION:
XS GIS Cut Line= 3
      2298834.31     13347525.10      2298293.84     13347318.11
      2297488.87     13346536.15
#Sta/Elev= 30
  3999.6  295.89  4037.8  295.30  4095.1  294.95  4149.9  292.91  4222.3  291.66
  4319.9  287.49  4335.2  287.13  4374.1  286.68  4423.9  284.70  4483.6  281.69
  4568.4  280.13  4654.4  279.75  4788.6  275.44  4838.1  275.55  4937.1  273.61
  4965.4  274.04  5040.3  273.24  5043.0  272.74  5046.3  273.24  5071.6  274.08
  5135.1  273.34  5170.6  274.40  5269.6  279.98  5311.9  281.18  5368.5  284.52
  5410.9  285.63  5502.9  289.89  5509.9  290.76  5649.7  295.02  5700.6  296.61
#Mann=9,-1,0
  3999.6     0.1       0  4037.8    0.05       0  4222.3     0.1       0
  4319.9    0.08       0  4335.2     0.1       0  4423.9    0.05       0
  5040.3    0.03       0  5046.3    0.05       0  5649.7     0.1       0
Bank Sta=5040.3,5046.3
Exp/Cntr=0.3,0.1

Type RM Length L Ch R = 1,2240,621,621,621
BEGIN DESCRIPTION:
UNT005 IN NURI 2.0
END DESCRIPTION:
XS GIS Cut Line= 3
      2298837.75     13347246.87      2298137.72     13346746.85
      2297737.69     13346596.84
#Sta/Elev= 30
  4145.1  298.30  4202.9  296.53  4267.0  293.28  4330.7  290.00  4339.3  288.16
  4345.4  287.73  4366.3  288.17  4385.2  286.93  4440.1  284.45  4452.4  282.79
  4475.7  282.18  4496.6  280.65  4553.1  278.04  4683.4  273.50  4769.4  272.25
  4882.5  272.85  4956.2  272.46  4983.2  272.10  4995.0  270.93  4997.7  270.43
  5001.0  270.93  5130.9  275.92  5154.9  276.13  5161.1  276.88  5176.2  277.15
  5283.0  282.27  5379.2  285.77  5400.5  287.44  5411.2  287.12  5432.6  287.94
#Mann=5,-1,0
  4145.1     0.1       0  4267.0    0.08       0  4385.2    0.05       0
  4995.0    0.03       0  5001.0    0.05       0
Bank Sta=4995,5001
Exp/Cntr=0.3,0.1

Type RM Length L Ch R = 1,1619,571,571,571
BEGIN DESCRIPTION:
Mapping XS aa61ce71
END DESCRIPTION:
XS GIS Cut Line= 4
      2299000.38     13347101.07      2298760.80     13346472.60
      2298220.86     13346340.66      2297807.63     13346276.41
#Sta/Elev= 30
  4220.0  296.00  4310.1  295.08  4516.6  287.70  4567.0  285.27  4575.4  284.44
  4580.7  282.83  4605.4  282.09  4620.5  283.70  4640.5  282.73  4660.3  282.46
  4727.5  278.28  4738.2  278.35  4805.4  274.46  4813.1  274.87  4889.9  271.64
  4967.8  270.28  4988.4  268.81  4995.7  267.36  4998.4  266.86  5001.7  267.36
  5029.6  270.19  5050.2  271.28  5091.3  271.98  5148.2  272.26  5189.9  272.08
  5214.9  271.15  5348.7  271.07  5461.7  272.46  5835.6  287.31  5866.6  288.02
#Mann=6,-1,0
  4220.0     0.1       0  4516.6    0.08       0  4640.5    0.05       0
  4995.7    0.03       0  5001.7    0.05       0  5835.6     0.1       0
Bank Sta=4995.7,5001.7
Exp/Cntr=0.3,0.1

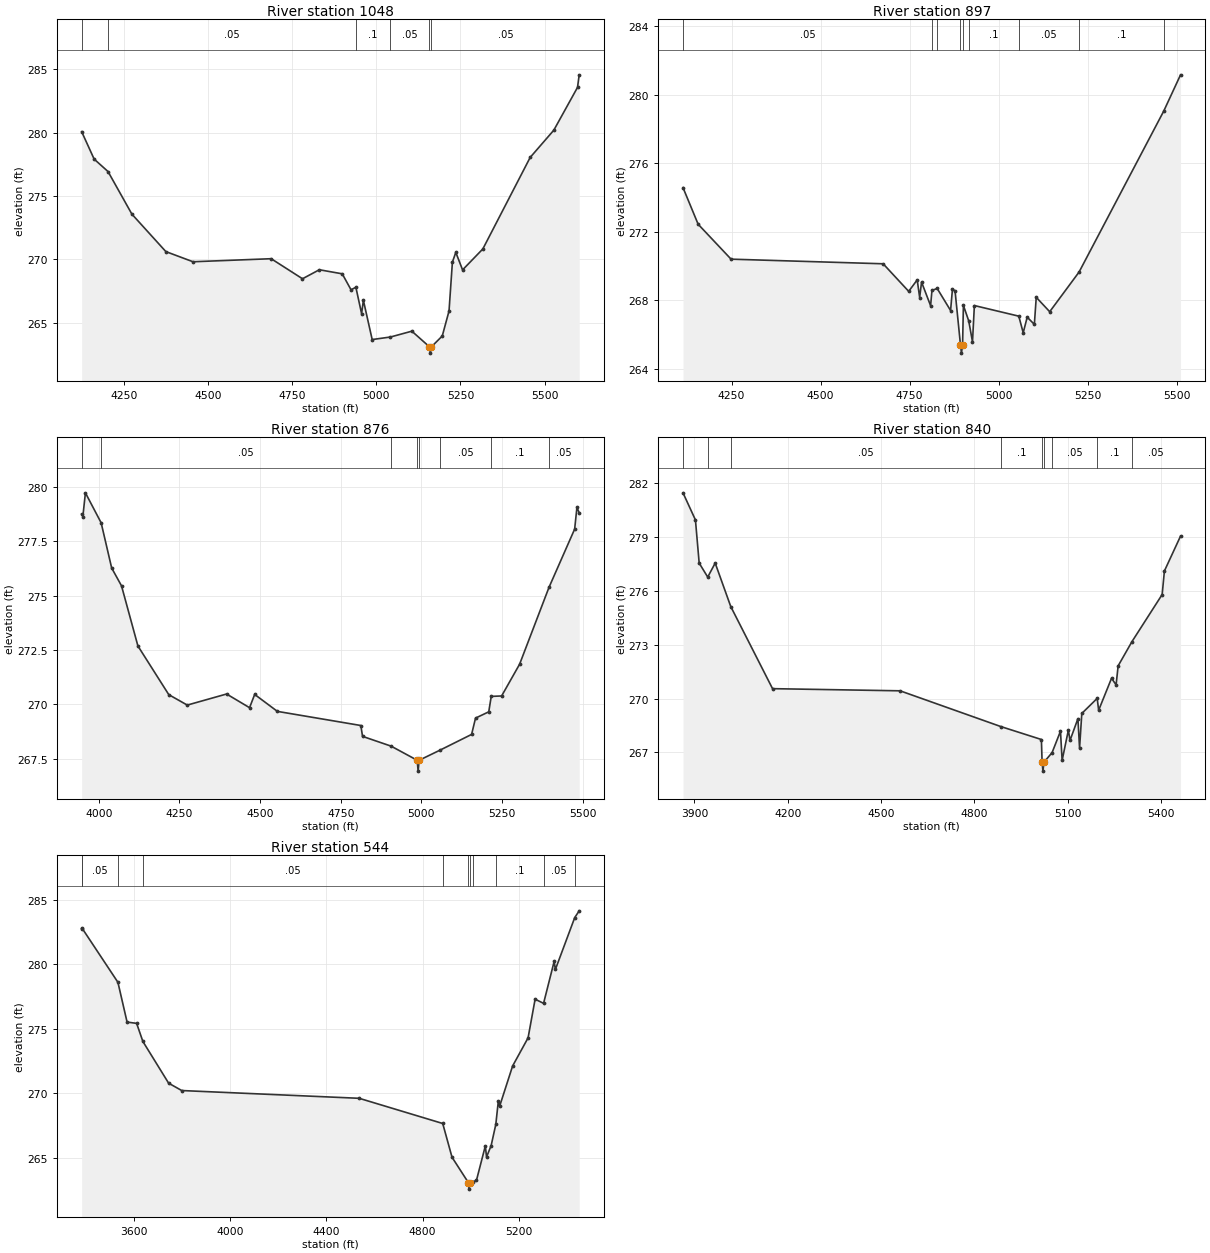
Type RM Length L Ch R = 1,1048,151,151,151
BEGIN DESCRIPTION:
Mapping XS 5b013ecb
END DESCRIPTION:
XS GIS Cut Line= 4
      2298887.72     13346604.93      2298818.88     13346049.74
      2298470.86     13345931.37      2297922.71     13345883.19
#Sta/Elev= 30
  4125.2  280.07  4162.2  277.91  4203.4  276.93  4274.4  273.57  4375.2  270.62
  4455.8  269.82  4687.9  270.06  4780.9  268.48  4830.9  269.19  4898.9  268.87
  4925.0  267.61  4939.4  267.81  4956.4  265.73  4961.7  266.78  4987.8  263.69
  5042.1  263.89  5105.6  264.35  5157.8  263.12  5160.6  262.62  5163.8  263.12
  5195.9  263.97  5216.0  265.94  5226.0  269.79  5236.1  270.56  5256.2  269.18
  5316.4  270.83  5456.9  278.04  5527.2  280.19  5597.5  283.56  5602.5  284.55
#Mann=6,-1,0
  4125.2    0.08       0  4203.4    0.05       0  4939.4     0.1       0
  5042.1    0.05       0  5157.8    0.07       0  5163.8    0.05       0
Bank Sta=5157.8,5163.8
Exp/Cntr=0.3,0.1

Type RM Length L Ch R = 1,897,21,21,21
BEGIN DESCRIPTION:
Mapping XS f1f0eb5c
END DESCRIPTION:
XS GIS Cut Line= 4
      2298893.65     13346458.85      2298826.50     13346043.88
      2298803.45     13346011.42      2297922.03     13345694.62
#Sta/Elev= 30
  4113.8  274.57  4156.3  272.43  4248.7  270.39  4675.7  270.12  4747.4  268.51
  4771.3  269.18  4778.2  268.15  4783.5  269.05  4808.9  267.67  4812.7  268.56
  4827.3  268.68  4865.0  267.39  4870.3  268.65  4877.6  268.53  4892.7  265.40
  4895.5  264.90  4898.7  265.40  4901.0  267.69  4916.0  266.78  4926.5  265.56
  4931.8  267.68  5056.5  267.06  5068.9  266.09  5080.1  267.00  5100.2  266.58
  5105.5  268.16  5143.3  267.32  5225.8  269.64  5463.4  279.04  5510.6  281.16
#Mann=9,-1,0
  4113.8    0.05       0  4812.7     0.1       0  4827.3    0.05       0
  4892.7    0.07       0  4898.7    0.05       0  4916.0     0.1       0
  5056.5    0.05       0  5225.8     0.1       0  5463.4    0.05       0
Bank Sta=4892.7,4898.7
Exp/Cntr=0.3,0.1

Type RM Length L Ch R = 1,876,36,36,36
BEGIN DESCRIPTION:
Mapping XS f7f58544
END DESCRIPTION:
XS GIS Cut Line= 4
      2298942.91     13346588.22      2298839.31     13346042.72
      2298823.73     13346005.59      2297934.45     13345680.08
#Sta/Elev= 30
  3946.8  278.75  3950.5  278.64  3958.4  279.73  4007.2  278.35  4039.8  276.27
  4070.3  275.45  4121.2  272.68  4216.9  270.44  4274.2  269.96  4396.1  270.47
  4467.3  269.84  4483.2  270.45  4553.6  269.67  4812.3  269.02  4817.6  268.52
  4906.2  268.07  4987.1  267.42  4989.9  266.92  4993.1  267.42  5057.0  267.88
  5155.7  268.61  5167.9  269.36  5208.9  269.65  5216.6  270.36  5248.8  270.38
  5304.5  271.84  5395.7  275.38  5475.2  278.06  5482.3  279.06  5489.3  278.81
#Mann=8,-1,0
  3946.8    0.08       0  4007.2    0.05       0  4906.2     0.1       0
  4987.1    0.07       0  4993.1     0.1       0  5057.0    0.05       0
  5216.6     0.1       0  5395.7    0.05       0
Bank Sta=4987.1,4993.1
Exp/Cntr=0.3,0.1

Type RM Length L Ch R = 1,840,296,296,296
BEGIN DESCRIPTION:
Mapping XS 7b33a114
END DESCRIPTION:
XS GIS Cut Line= 4
      2298993.25     13346607.27      2298836.93     13345978.96
      2298799.67     13345971.03      2297938.89     13345661.21
#Sta/Elev= 30
  3863.1  281.45  3903.1  279.94  3915.1  277.54  3942.6  276.76  3966.6  277.54
  4016.7  275.12  4151.1  270.55  4561.4  270.43  4885.5  268.44  5015.9  267.72
  5018.2  266.46  5020.9  265.96  5024.2  266.46  5050.3  266.99  5077.3  268.18
  5082.6  266.56  5102.7  268.24  5108.0  267.67  5133.4  268.88  5138.7  267.24
  5145.9  269.17  5195.4  270.01  5200.1  269.35  5241.6  271.13  5256.2  270.76
  5262.8  271.82  5307.3  273.17  5404.4  275.79  5411.6  277.10  5463.5  279.04
#Mann=9,-1,0
  3863.1    0.05       0  3942.6    0.08       0  4016.7    0.05       0
  4885.5     0.1       0  5018.2    0.07       0  5024.2     0.1       0
  5050.3    0.05       0  5195.4     0.1       0  5307.3    0.05       0
Bank Sta=5018.2,5024.2
Exp/Cntr=0.3,0.1

Type RM Length L Ch R = 1,544,0,0,0
BEGIN DESCRIPTION:
UNT005 IN NURI 1.0
END DESCRIPTION:
XS GIS Cut Line= 3
      2299064.60     13346676.12      2298775.55     13345683.97
      2297757.29     13345504.28
#Sta/Elev= 30
  3383.3  282.78  3386.6  282.74  3533.9  278.60  3572.0  275.52  3611.7  275.42
  3637.6  274.02  3744.7  270.79  3799.2  270.22  4536.4  269.62  4883.6  267.67
  4922.2  265.06  4990.3  263.09  4993.1  262.59  4996.3  263.09  5008.0  263.14
  5023.8  263.27  5060.6  265.93  5065.7  265.08  5084.7  265.95  5104.2  267.60
  5114.7  269.41  5119.8  268.99  5174.0  272.12  5238.3  274.30  5267.5  277.29
  5302.7  276.97  5346.6  280.21  5351.7  279.59  5432.2  283.61  5450.7  284.13
#Mann=11,-1,0
  3383.3     0.1       0  3386.6    0.05       0  3533.9    0.08       0
  3637.6    0.05       0  4883.6     0.1       0  4990.3    0.07       0
  4996.3     0.1       0  5008.0    0.05       0  5104.2     0.1       0
  5302.7    0.05       0  5432.2     0.1       0
Bank Sta=4990.3,4996.3
Exp/Cntr=0.3,0.1

Chan Stop Cuts=-1