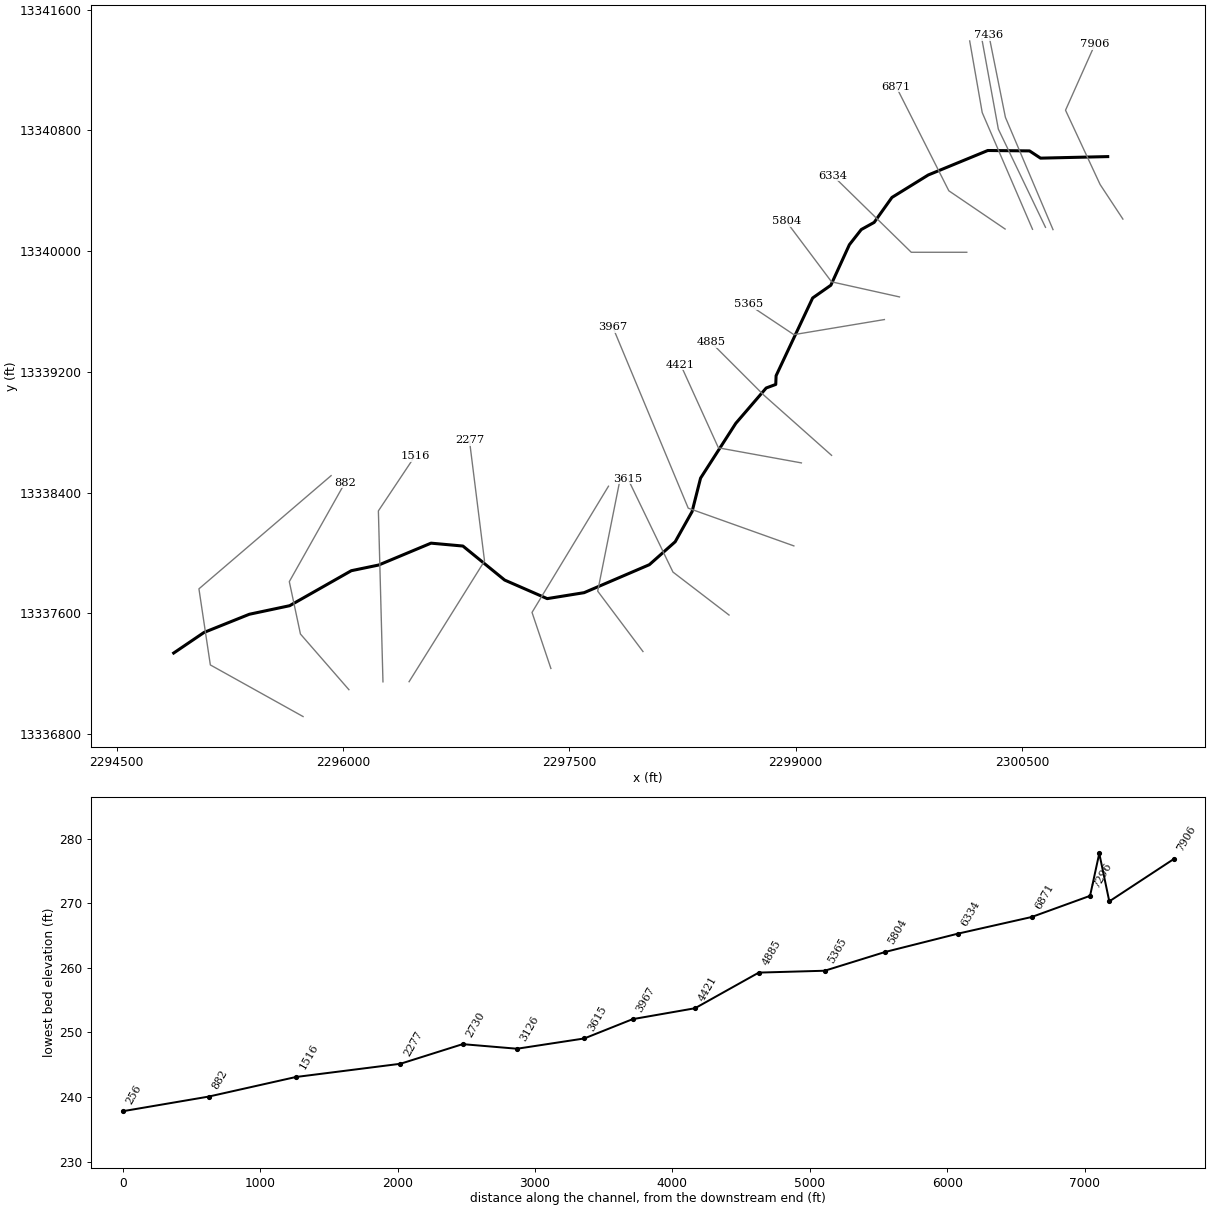
--- UNT006 IN NURI.prj (project) ---

Proj Title=UNT006 IN NURI Base Level Engineering
Current Plan=p01
Default Exp/Contr=0.3,0.1
English Units
Geom File=g01
Flow File=f01
Plan File=p01
BEGIN DESCRIPTION:
UNT006 IN NURI
END DESCRIPTION:

--- UNT006 IN NURI.p01 (plan) ---

Plan Title=Multiple Run
Short Identifier=Multiple
Geom File=g01
Flow File=f01
Subcritical Flow
K Sum by GR= 0
Std Step Tol= 0.01
Critical Tol= 0.01
Num of Std Step Trials= 20
Max Error Tol= 0.3
Flow Tol Ratio= 0.001
Split Flow NTrial= 30
Split Flow Tol= 0.02
Split Flow Ratio= 0.02
Log Output Level= 0
Friction Slope Method= 1
Unsteady Friction Slope Method= 2
Unsteady Bridges Friction Slope Method= 1
Parabolic Critical Depth
Global Vel Dist=  1 , 1 , 1
Global Log Level= 0
CheckData=True
Encroach Param= -1, 0, 0, 0
BEGIN DESCRIPTION:
Multiple Run
END DESCRIPTION:

--- UNT006 IN NURI.f01 (steady flow) ---

Flow Title=Multiple
Number of Profiles=7
Profile Names=10-year,25-year,50-year,1pct_min,100-year,1pct_plu,500-year
River Rch & RM= UNT006 IN NURI,Reach-1,7906
    1054    1544    1969    1832    2478    3351    3939
River Rch & RM= UNT006 IN NURI,Reach-1,3126
    1186    1744    2229    2077    2809    3799    4483
Boundary for River Rch & Prof#=UNT006 IN NURI,Reach-1,1
Up Type=0
Dn Type=3
Dn Slope=0.005
Boundary for River Rch & Prof#=UNT006 IN NURI,Reach-1,2
Up Type=0
Dn Type=3
Dn Slope=0.005
Boundary for River Rch & Prof#=UNT006 IN NURI,Reach-1,3
Up Type=0
Dn Type=3
Dn Slope=0.005
Boundary for River Rch & Prof#=UNT006 IN NURI,Reach-1,4
Up Type=0
Dn Type=3
Dn Slope=0.005
Boundary for River Rch & Prof#=UNT006 IN NURI,Reach-1,5
Up Type=0
Dn Type=3
Dn Slope=0.005
Boundary for River Rch & Prof#=UNT006 IN NURI,Reach-1,6
Up Type=0
Dn Type=3
Dn Slope=0.005
Boundary for River Rch & Prof#=UNT006 IN NURI,Reach-1,7
Up Type=0
Dn Type=3
Dn Slope=0.005

--- UNT006 IN NURI.g01 (geometry) ---

Geom Title=Existing Conditions

River Reach=UNT006 IN NURI,Reach-1
Reach XY= 30
      2301067.72     13340626.86      2300622.33     13340616.57
      2300549.55     13340664.63      2300272.85     13340667.18
      2299878.46     13340505.06      2299637.73     13340356.16
      2299519.96     13340190.82      2299434.40     13340143.34
      2299355.75     13340042.96      2299232.81     13339774.20
      2299112.25     13339689.83      2298870.01     13339174.72
      2298867.72     13339116.86      2298804.40     13339093.39
      2298602.95     13338859.22      2298369.56     13338496.09
      2298313.19     13338274.02      2298201.26     13338074.20
      2298030.16     13337922.34      2297597.72     13337736.85
      2297352.99     13337697.39      2297071.00     13337820.51
      2296794.48     13338045.89      2296583.19     13338065.00
      2296236.37     13337920.12      2296054.84     13337882.43
      2295646.21     13337650.51      2295379.06     13337593.83
      2295079.13     13337473.44      2294877.72     13337336.86

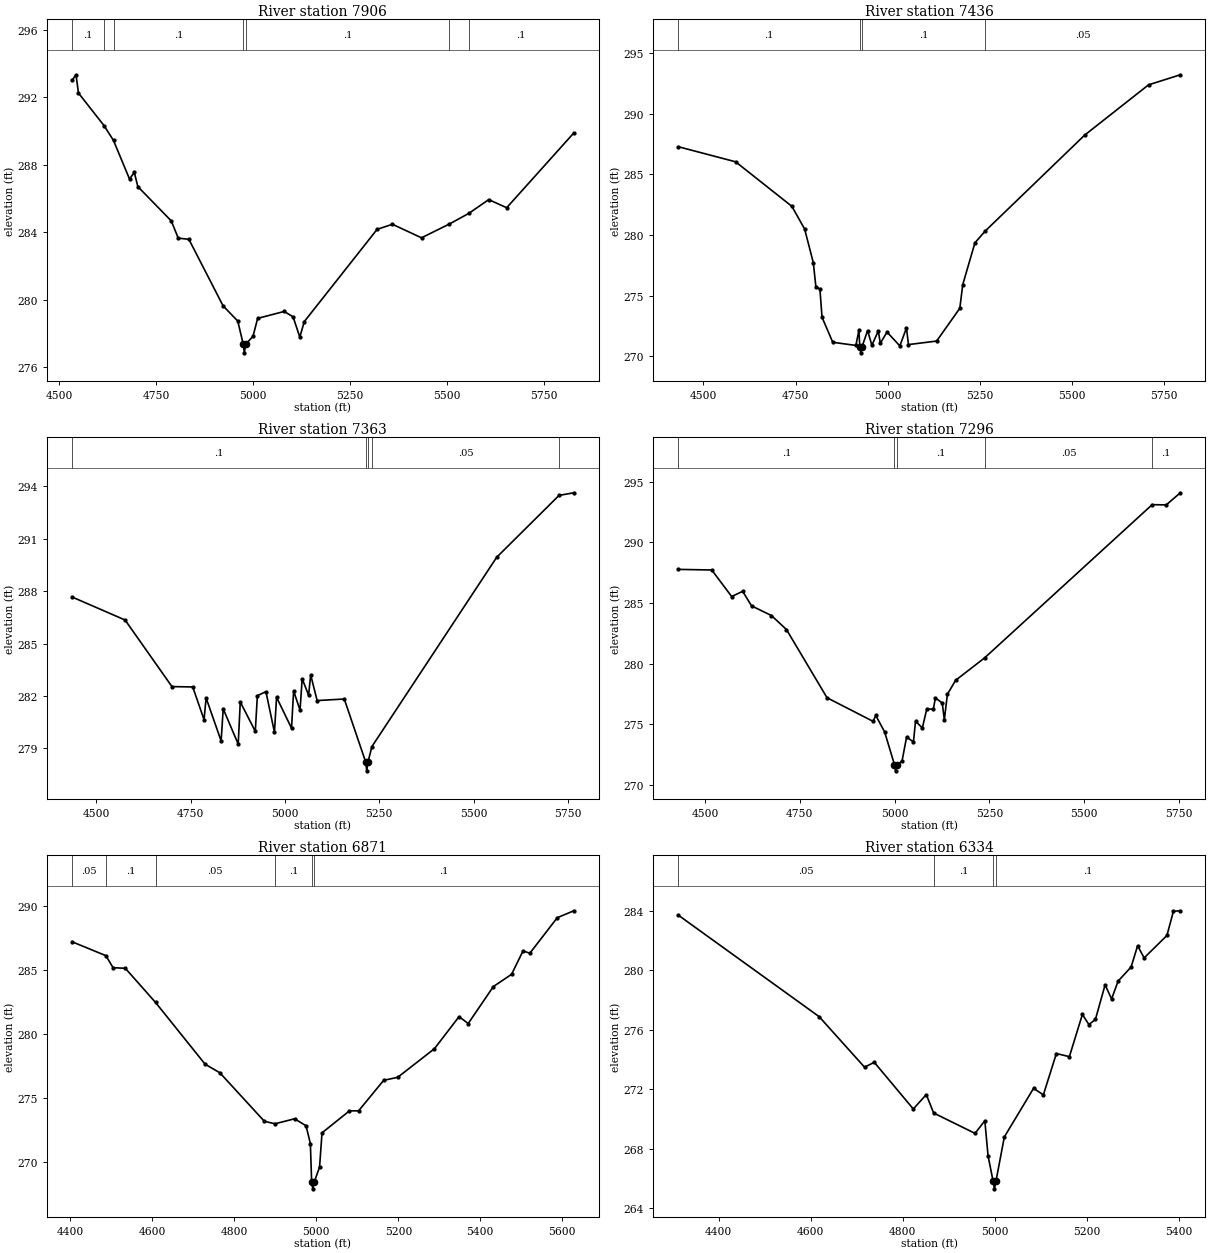
Type RM Length L Ch R = 1,7906,470,470,470
BEGIN DESCRIPTION:
UNT006 IN NURI 16.0
END DESCRIPTION:
XS GIS Cut Line= 4
      2301168.32     13340212.80      2301017.26     13340441.99
      2300788.10     13340934.17      2300983.07     13341370.91
#Sta/Elev= 30
  4532.6  292.99  4543.1  293.32  4549.4  292.24  4615.5  290.31  4639.9  289.43
  4681.2  287.15  4693.6  287.54  4702.7  286.70  4789.0  284.67  4807.0  283.65
  4834.5  283.58  4922.8  279.64  4960.7  278.74  4974.9  277.36  4977.7  276.86
  4980.9  277.36  5000.0  277.84  5012.0  278.90  5080.6  279.31  5103.5  278.99
  5120.8  277.79  5132.4  278.71  5320.4  284.17  5359.9  284.47  5435.0  283.67
  5506.5  284.48  5556.8  285.11  5608.5  285.93  5654.9  285.45  5828.3  289.88
#Mann=7,-1,0
  4532.6     0.1       0  4615.5    0.05       0  4639.9     0.1       0
  4974.9    0.07       0  4980.9     0.1       0  5506.5    0.05       0
  5556.8     0.1       0
Bank Sta=4974.9,4980.9
Exp/Cntr=0.3,0.1

Type RM Length L Ch R = 1,7436,73,73,73
BEGIN DESCRIPTION:
UNT006 IN NURI 15.0
END DESCRIPTION:
XS GIS Cut Line= 3
      2300705.12     13340142.92      2300389.66     13340887.30
      2300280.29     13341431.55
#Sta/Elev= 30
  4431.9  287.27  4587.3  286.03  4740.2  282.36  4774.8  280.49  4798.4  277.72
  4805.4  275.73  4816.3  275.55  4822.1  273.22  4851.2  271.16  4914.1  270.90
  4922.2  272.15  4924.7  270.79  4927.4  270.29  4930.7  270.79  4945.9  272.12
  4957.5  270.91  4975.0  272.10  4980.4  271.08  4998.7  272.00  5033.5  270.86
  5051.5  272.34  5056.9  270.97  5133.4  271.26  5196.4  273.96  5204.4  275.91
  5237.4  279.35  5264.9  280.31  5535.7  288.23  5709.1  292.37  5795.5  293.20
#Mann=4,-1,0
  4431.9     0.1       0  4924.7    0.07       0  4930.7     0.1       0
  5264.9    0.05       0
Bank Sta=4924.7,4930.7
Exp/Cntr=0.3,0.1

Type RM Length L Ch R = 1,7363,67,67,67
BEGIN DESCRIPTION:
Mapping XS 9fb5da5b
END DESCRIPTION:
XS GIS Cut Line= 3
      2300655.29     13340158.12      2300342.78     13340809.17
      2300233.41     13341408.10
#Sta/Elev= 30
  4435.0  287.67  4575.9  286.35  4700.2  282.54  4755.3  282.52  4785.3  280.65
  4790.8  281.89  4830.6  279.43  4836.1  281.27  4875.9  279.25  4881.4  281.66
  4921.2  279.98  4926.7  282.02  4949.4  282.25  4972.0  279.93  4977.6  281.93
  5017.3  280.16  5022.8  282.29  5039.9  281.19  5045.5  282.99  5062.6  282.05
  5068.1  283.21  5085.2  281.74  5157.2  281.83  5214.0  278.22  5216.8  277.72
  5220.0  278.22  5230.5  279.11  5561.4  289.94  5726.7  293.48  5766.0  293.63
#Mann=5,-1,0
  4435.0     0.1       0  5214.0    0.07       0  5220.0     0.1       0
  5230.5    0.05       0  5726.7     0.1       0
Bank Sta=5214,5220
Exp/Cntr=0.3,0.1

Type RM Length L Ch R = 1,7296,425,425,425
BEGIN DESCRIPTION:
UNT006 IN NURI 14.0
END DESCRIPTION:
XS GIS Cut Line= 3
      2300569.34     13340145.13      2300236.01     13340918.55
      2300152.99     13341393.36
#Sta/Elev= 30
  4429.7  287.77  4517.7  287.72  4570.2  285.53  4599.2  285.96  4622.7  284.76
  4675.2  283.96  4714.7  282.81  4821.8  277.18  4943.4  275.23  4950.3  275.72
  4973.8  274.36  4999.8  271.65  5002.5  271.15  5005.8  271.65  5019.6  271.94
  5031.7  273.94  5049.8  273.54  5055.3  275.24  5073.3  274.69  5084.9  276.24
  5102.3  276.25  5107.7  277.16  5125.8  276.75  5131.3  275.36  5139.4  277.47
  5161.1  278.62  5237.6  280.47  5679.6  293.11  5716.8  293.09  5753.9  294.09
#Mann=5,-1,0
  4429.7     0.1       0  4999.8    0.07       0  5005.8     0.1       0
  5237.6    0.05       0  5679.6     0.1       0
Bank Sta=4999.8,5005.8
Exp/Cntr=0.3,0.1

Type RM Length L Ch R = 1,6871,537,537,537
BEGIN DESCRIPTION:
UNT006 IN NURI 13.0
END DESCRIPTION:
XS GIS Cut Line= 3
      2300387.71     13340146.86      2300014.66     13340400.32
      2299665.71     13341090.40
#Sta/Elev= 30
  4403.9  287.20  4486.6  286.11  4504.2  285.17  4534.1  285.12  4607.8  282.45
  4728.7  277.62  4764.6  276.95  4873.4  273.15  4899.3  272.96  4947.1  273.35
  4975.0  272.80  4985.5  271.40  4988.6  268.37  4991.4  267.87  4994.6  268.37
  5007.9  269.57  5013.9  272.25  5080.8  273.97  5103.1  273.97  5164.3  276.36
  5198.4  276.59  5288.1  278.83  5348.2  281.34  5370.5  280.80  5431.8  283.69
  5476.3  284.65  5504.2  286.48  5520.9  286.30  5587.8  289.08  5628.2  289.62
#Mann=6,-1,0
  4403.9    0.05       0  4486.6     0.1       0  4607.8    0.05       0
  4899.3     0.1       0  4988.6    0.07       0  4994.6     0.1       0
Bank Sta=4988.6,4994.6
Exp/Cntr=0.3,0.1

Type RM Length L Ch R = 1,6334,530,530,530
BEGIN DESCRIPTION:
UNT006 IN NURI 12.0
END DESCRIPTION:
XS GIS Cut Line= 3
      2300133.79     13339992.81      2299765.80     13339992.81
      2299248.34     13340498.77
#Sta/Elev= 30
  4312.2  283.69  4618.3  276.87  4717.1  273.47  4738.2  273.80  4823.1  270.66
  4851.4  271.63  4867.3  270.39  4957.4  269.02  4978.7  269.87  4985.7  267.51
  4996.8  265.79  4999.6  265.29  5002.8  265.79  5021.1  268.78  5084.7  272.05
  5106.0  271.61  5134.3  274.39  5162.6  274.18  5190.9  277.02  5205.0  276.34
  5219.2  276.68  5240.3  279.01  5254.4  278.06  5268.6  279.26  5296.9  280.21
  5311.0  281.64  5325.2  280.82  5374.8  282.33  5388.9  283.96  5403.9  283.99
#Mann=4,-1,0
  4312.2    0.05       0  4867.3     0.1       0  4996.8    0.07       0
  5002.8     0.1       0
Bank Sta=4996.8,5002.8
Exp/Cntr=0.3,0.1

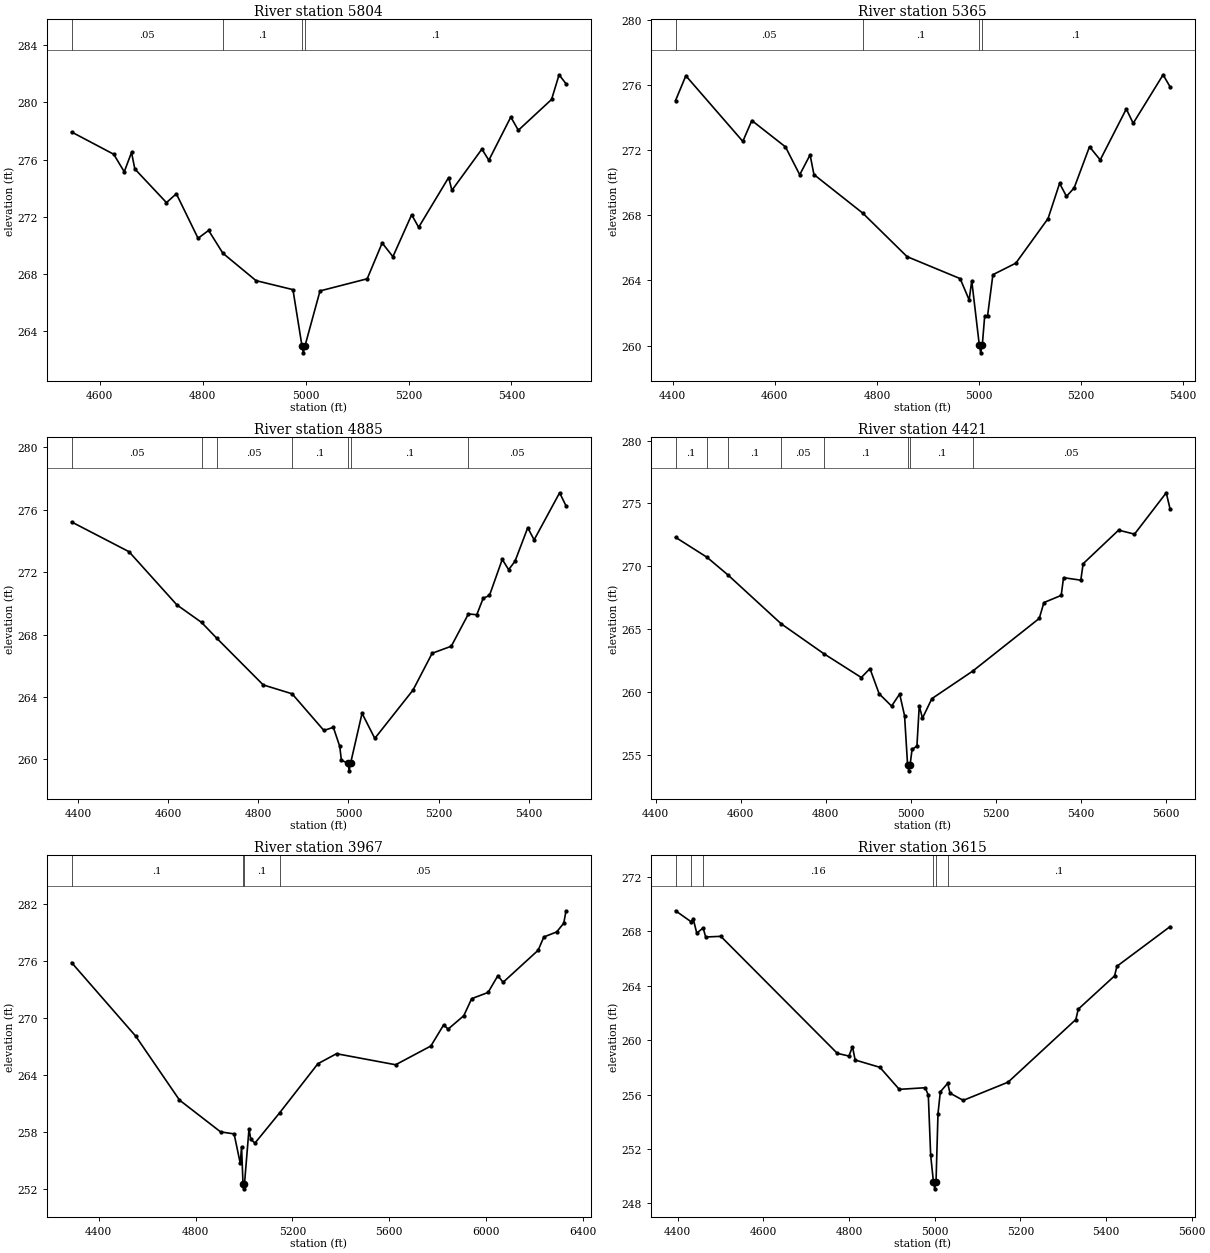
Type RM Length L Ch R = 1,5804,439,439,439
BEGIN DESCRIPTION:
UNT006 IN NURI 11.0
END DESCRIPTION:
XS GIS Cut Line= 3
      2299687.68     13339696.86      2299237.72     13339796.85
      2298937.74     13340196.83
#Sta/Elev= 30
  4545.1  277.93  4627.0  276.37  4647.5  275.14  4661.6  276.50  4668.0  275.34
  4729.5  272.98  4748.7  273.60  4790.9  270.48  4811.4  271.03  4839.2  269.43
  4903.6  267.51  4975.3  266.88  4992.8  262.95  4995.5  262.45  4998.8  262.95
  5027.9  266.79  5119.6  267.64  5148.7  270.15  5169.6  269.19  5206.0  272.13
  5219.6  271.25  5277.9  274.74  5284.2  273.84  5342.5  276.73  5356.0  275.95
  5398.7  278.98  5413.3  278.05  5477.9  280.21  5492.5  281.94  5506.0  281.31
#Mann=4,-1,0
  4545.1    0.05       0  4839.2     0.1       0  4992.8    0.07       0
  4998.8     0.1       0
Bank Sta=4992.8,4998.8
Exp/Cntr=0.3,0.1

Type RM Length L Ch R = 1,5365,480,480,480
BEGIN DESCRIPTION:
UNT006 IN NURI 10.0
END DESCRIPTION:
XS GIS Cut Line= 3
      2299587.69     13339546.85      2298987.72     13339446.85
      2298687.72     13339646.85
#Sta/Elev= 30
  4405.5  275.05  4425.7  276.57  4537.3  272.54  4555.0  273.82  4620.9  272.20
  4648.8  270.49  4669.1  271.71  4676.7  270.50  4772.4  268.13  4859.1  265.46
  4963.1  264.11  4980.8  262.80  4985.9  263.98  5000.6  260.05  5003.4  259.55
  5006.6  260.05  5011.2  261.80  5016.8  261.80  5027.3  264.35  5072.3  265.06
  5135.4  267.80  5158.0  269.96  5171.5  269.16  5186.5  269.68  5216.6  272.21
  5237.6  271.40  5288.7  274.53  5302.2  273.65  5360.8  276.63  5374.3  275.90
#Mann=4,-1,0
  4405.5    0.05       0  4772.4     0.1       0  5000.6    0.07       0
  5006.6     0.1       0
Bank Sta=5000.6,5006.6
Exp/Cntr=0.3,0.1

Type RM Length L Ch R = 1,4885,464,464,464
BEGIN DESCRIPTION:
UNT006 IN NURI 9.0
END DESCRIPTION:
XS GIS Cut Line= 3
      2299237.72     13338646.86      2298787.72     13339046.85
      2298437.69     13339396.89
#Sta/Elev= 30
  4385.6  275.22  4513.1  273.31  4619.3  269.90  4673.9  268.78  4707.5  267.77
  4810.8  264.77  4874.9  264.20  4945.4  261.85  4966.4  262.05  4980.6  260.83
  4984.3  259.93  4998.8  259.76  5001.6  259.26  5004.8  259.76  5030.1  262.95
  5058.4  261.34  5143.2  264.44  5185.7  266.80  5228.1  267.25  5266.1  269.32
  5284.7  269.27  5298.8  270.32  5312.9  270.51  5341.2  272.82  5355.4  272.16
  5369.5  272.70  5397.8  274.85  5411.9  274.07  5468.5  277.09  5482.7  276.25
#Mann=7,-1,0
  4385.6    0.05       0  4673.9     0.1       0  4707.5    0.05       0
  4874.9     0.1       0  4998.8    0.07       0  5004.8     0.1       0
  5266.1    0.05       0
Bank Sta=4998.8,5004.8
Exp/Cntr=0.3,0.1

Type RM Length L Ch R = 1,4421,454,454,454
BEGIN DESCRIPTION:
UNT006 IN NURI 8.0
END DESCRIPTION:
XS GIS Cut Line= 3
      2299037.68     13338596.86      2298487.72     13338696.85
      2298237.73     13339246.82
#Sta/Elev= 30
  4446.6  272.31  4520.7  270.72  4570.1  269.31  4694.8  265.44  4795.2  263.06
  4883.6  261.16  4903.9  261.87  4925.5  259.87  4954.8  258.89  4973.8  259.85
  4985.3  258.13  4992.4  254.24  4995.2  253.74  4998.4  254.24  5003.0  255.44
  5014.4  255.71  5019.9  258.90  5027.5  257.93  5049.5  259.48  5145.6  261.67
  5302.2  265.86  5313.1  267.12  5353.8  267.69  5359.3  269.10  5399.9  268.90
  5405.4  270.21  5488.9  272.88  5526.2  272.56  5600.9  275.85  5609.7  274.59
#Mann=8,-1,0
  4446.6     0.1       0  4520.7    0.05       0  4570.1     0.1       0
  4694.8    0.05       0  4795.2     0.1       0  4992.4    0.07       0
  4998.4     0.1       0  5145.6    0.05       0
Bank Sta=4992.4,4998.4
Exp/Cntr=0.3,0.1

Type RM Length L Ch R = 1,3967,352,352,352
BEGIN DESCRIPTION:
UNT006 IN NURI 7.0
END DESCRIPTION:
XS GIS Cut Line= 3
      2298987.76     13338046.84      2298287.72     13338296.85
      2297787.70     13339496.90
#Sta/Elev= 30
  4287.5  275.81  4553.0  268.07  4733.5  261.37  4903.4  258.03  4959.2  257.82
  4984.7  254.72  4990.0  256.46  4996.0  252.55  4998.7  252.05  5002.0  252.55
  5020.8  258.35  5028.2  257.24  5045.5  256.86  5147.0  260.02  5305.5  265.19
  5382.4  266.24  5626.7  265.08  5772.4  267.05  5825.5  269.28  5843.4  268.82
  5908.4  270.23  5940.9  272.02  6008.6  272.67  6049.2  274.43  6070.9  273.74
  6215.5  277.10  6239.3  278.50  6292.4  279.03  6321.6  279.95  6330.9  281.25
#Mann=4,-1,0
  4287.5     0.1       0  4996.0    0.07       0  5002.0     0.1       0
  5147.0    0.05       0
Bank Sta=4996,5002
Exp/Cntr=0.3,0.1

Type RM Length L Ch R = 1,3615,489,489,489
BEGIN DESCRIPTION:
UNT006 IN NURI 6.0
END DESCRIPTION:
XS GIS Cut Line= 3
      2298558.08     13337588.67      2298186.53     13337873.41
      2297887.93     13338491.45
#Sta/Elev= 30
  4394.9  269.52  4431.4  268.71  4436.2  268.92  4444.5  267.87  4459.3  268.26
  4465.3  267.59  4500.6  267.64  4772.6  259.03  4799.8  258.83  4808.0  259.52
  4814.3  258.54  4872.1  258.00  4917.3  256.38  4977.9  256.50  4985.1  255.95
  4990.6  251.53  4997.1  249.56  4999.9  249.06  5003.1  249.56  5007.7  254.59
  5013.2  256.20  5030.4  256.83  5035.8  256.10  5066.7  255.57  5171.4  256.91
  5329.6  261.52  5335.2  262.28  5420.0  264.73  5425.6  265.44  5549.4  268.35
#Mann=6,-1,0
  4394.9    0.08       0  4431.4    0.05       0  4459.3    0.16       0
  4997.1    0.07       0  5003.1    0.16       0  5030.4     0.1       0
Bank Sta=4997.1,5003.1
Exp/Cntr=0.3,0.1

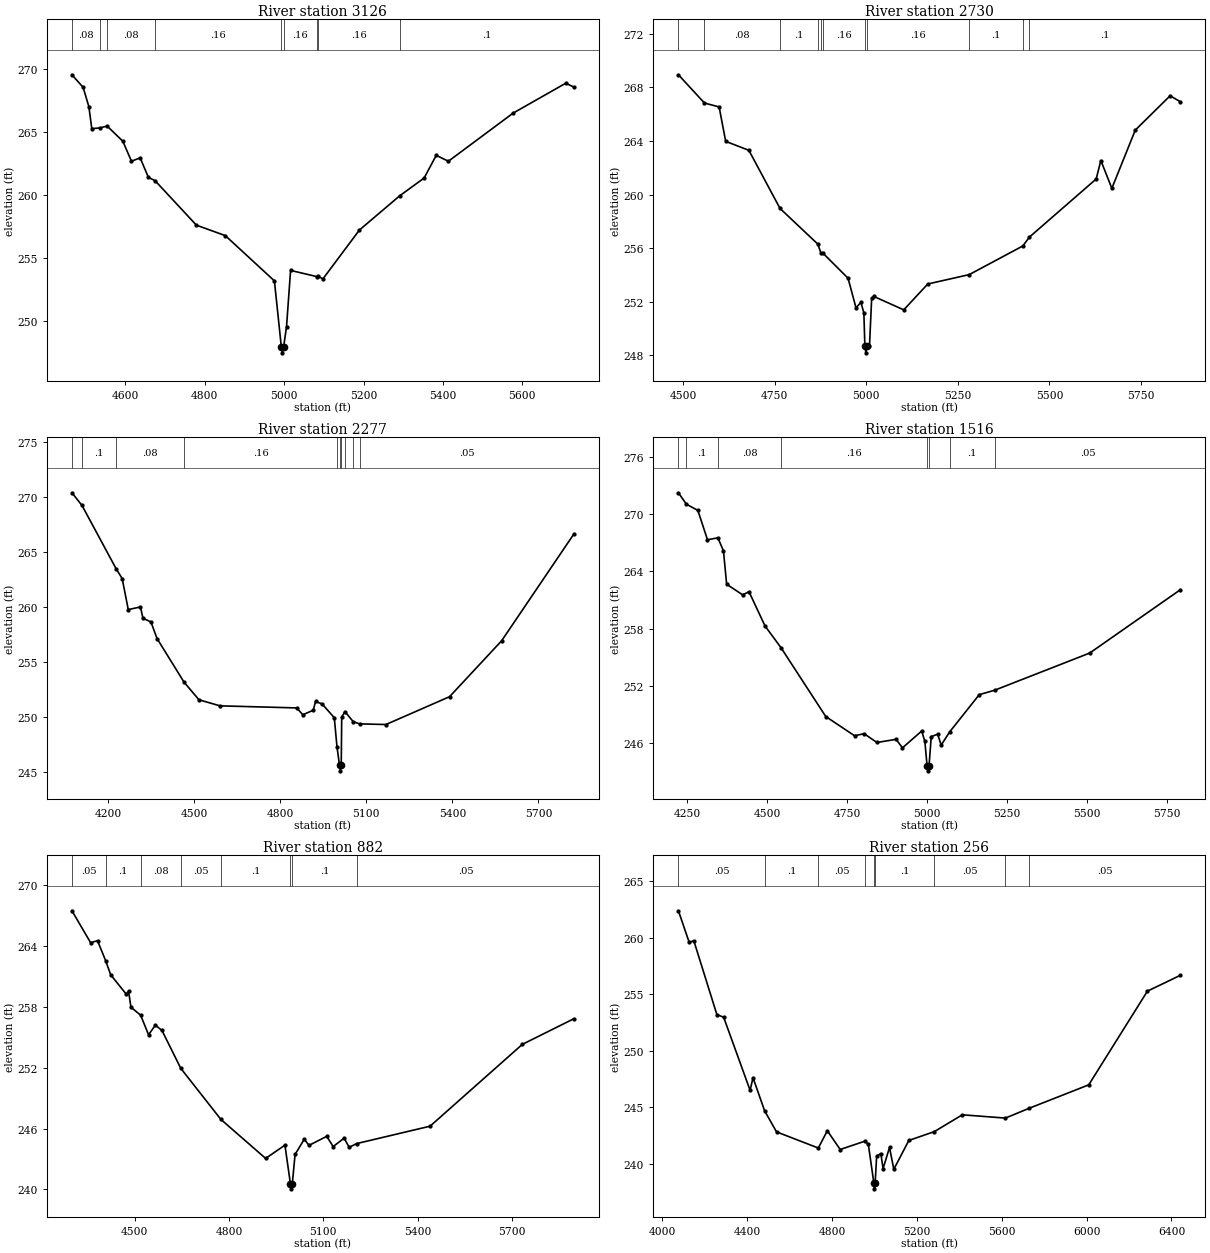
Type RM Length L Ch R = 1,3126,396,396,396
BEGIN DESCRIPTION:
UNT006 IN NURI 5.0
END DESCRIPTION:
XS GIS Cut Line= 3
      2297987.74     13337346.83      2297687.72     13337746.85
      2297837.72     13338496.87
#Sta/Elev= 30
  4465.1  269.53  4493.3  268.53  4507.8  266.99  4515.1  265.26  4534.7  265.31
  4553.8  265.46  4593.3  264.26  4615.1  262.67  4637.0  262.94  4657.8  261.39
  4674.5  261.13  4778.7  257.60  4851.6  256.77  4975.3  253.18  4992.7  247.97
  4995.5  247.47  4998.7  247.97  5005.9  249.55  5016.1  254.01  5082.0  253.52
  5085.6  253.53  5097.7  253.34  5189.5  257.21  5290.8  259.92  5352.7  261.34
  5383.2  263.14  5413.8  262.67  5577.0  266.49  5709.6  268.86  5730.0  268.55
#Mann=9,-1,0
  4465.1    0.08       0  4534.7    0.05       0  4553.8    0.08       0
  4674.5    0.16       0  4992.7    0.07       0  4998.7    0.16       0
  5082.0     0.1       0  5085.6    0.16       0  5290.8     0.1       0
Bank Sta=4992.7,4998.7
Exp/Cntr=0.3,0.1

Type RM Length L Ch R = 1,2730,453,453,453
BEGIN DESCRIPTION:
UNT006 IN NURI 4.0
END DESCRIPTION:
XS GIS Cut Line= 3
      2297377.49     13337234.56      2297252.51     13337606.05
      2297759.17     13338442.39
#Sta/Elev= 30
  4487.3  268.94  4558.4  266.83  4598.4  266.54  4616.3  263.97  4679.6  263.30
  4764.6  258.96  4867.7  256.30  4876.1  255.65  4882.2  255.61  4950.3  253.75
  4972.0  251.54  4985.4  251.95  4993.4  251.16  4996.2  248.68  4999.0  248.18
  5002.2  248.68  5008.8  248.69  5014.7  252.25  5020.6  252.39  5102.3  251.39
  5167.9  253.32  5281.0  254.02  5427.3  256.16  5445.2  256.82  5627.5  261.16
  5640.2  262.54  5670.2  260.46  5734.2  264.81  5829.2  267.37  5857.1  266.93
#Mann=11,-1,0
  4487.3    0.05       0  4558.4    0.08       0  4764.6     0.1       0
  4867.7    0.16       0  4876.1     0.1       0  4882.2    0.16       0
  4996.2    0.07       0  5002.2    0.16       0  5281.0     0.1       0
  5427.3    0.16       0  5445.2     0.1       0
Bank Sta=4996.2,5002.2
Exp/Cntr=0.3,0.1

Type RM Length L Ch R = 1,2277,761,761,761
BEGIN DESCRIPTION:
UNT006 IN NURI 3.0
END DESCRIPTION:
XS GIS Cut Line= 3
      2296437.73     13337146.88      2296937.72     13337946.85
      2296837.72     13338746.86
#Sta/Elev= 30
  4073.8  270.42  4108.8  269.27  4227.4  263.53  4248.9  262.62  4270.1  259.80
  4312.6  260.04  4321.4  259.01  4349.1  258.68  4370.4  257.17  4464.6  253.20
  4516.6  251.60  4589.7  251.05  4857.4  250.86  4878.6  250.24  4915.2  250.65
  4922.8  251.45  4945.8  251.22  4988.3  249.97  4997.6  247.35  5006.5  245.64
  5009.3  245.14  5012.5  245.64  5014.2  250.01  5025.1  250.53  5054.3  249.61
  5076.6  249.41  5168.3  249.35  5390.1  251.88  5571.5  256.96  5823.4  266.67
#Mann=10,-1,0
  4073.8    0.05       0  4108.8     0.1       0  4227.4    0.08       0
  4464.6    0.16       0  4997.6     0.1       0  5006.5    0.07       0
  5012.5     0.1       0  5025.1    0.16       0  5054.3     0.1       0
  5076.6    0.05       0
Bank Sta=5006.5,5012.5
Exp/Cntr=0.3,0.1

Type RM Length L Ch R = 1,1516,634,634,634
BEGIN DESCRIPTION:
UNT006 IN NURI 2.0
END DESCRIPTION:
XS GIS Cut Line= 3
      2296264.66     13337146.01      2296234.28     13338278.79
      2296476.80     13338642.57
#Sta/Elev= 30
  4222.2  272.22  4247.0  271.03  4283.1  270.37  4313.1  267.30  4345.7  267.50
  4363.1  266.14  4373.1  262.64  4423.1  261.53  4443.1  261.85  4493.1  258.27
  4543.0  256.00  4683.2  248.78  4773.2  246.77  4803.3  246.98  4843.3  246.06
  4903.3  246.39  4923.3  245.50  4983.3  247.26  4993.3  246.18  5000.3  243.59
  5003.1  243.09  5006.3  243.59  5013.3  246.67  5033.3  246.93  5044.4  245.79
  5070.7  247.16  5163.4  251.07  5212.1  251.54  5509.1  255.43  5792.6  262.06
#Mann=8,-1,0
  4222.2    0.05       0  4247.0     0.1       0  4345.7    0.08       0
  4543.0    0.16       0  5000.3    0.07       0  5006.3    0.16       0
  5070.7     0.1       0  5212.1    0.05       0
Bank Sta=5000.3,5006.3
Exp/Cntr=0.3,0.1

Type RM Length L Ch R = 1,882,626,626,626
BEGIN DESCRIPTION:
Mapping XS ffc6107b
END DESCRIPTION:
XS GIS Cut Line= 4
      2296038.96     13337093.90      2295717.78     13337462.82
      2295644.00     13337810.04      2296012.82     13338465.25
#Sta/Elev= 30
  4300.7  267.49  4360.1  264.34  4382.0  264.54  4407.8  262.57  4424.0  261.17
  4474.0  259.24  4480.7  259.57  4488.3  257.98  4519.1  257.19  4544.3  255.26
  4566.1  256.21  4587.0  255.68  4646.7  251.95  4774.3  246.91  4916.6  243.06
  4978.0  244.37  4995.4  240.56  4998.2  240.06  5001.4  240.56  5010.2  243.45
  5039.3  244.95  5054.7  244.35  5110.9  245.24  5131.3  244.23  5166.2  245.06
  5182.2  244.16  5206.8  244.53  5439.5  246.24  5732.8  254.31  5896.7  256.84
#Mann=8,-1,0
  4300.7    0.05       0  4407.8     0.1       0  4519.1    0.08       0
  4646.7    0.05       0  4774.3     0.1       0  4995.4    0.07       0
  5001.4     0.1       0  5206.8    0.05       0
Bank Sta=4995.4,5001.4
Exp/Cntr=0.3,0.1

Type RM Length L Ch R = 1,256,0,0,0
BEGIN DESCRIPTION:
UNT006 IN NURI 1.0
END DESCRIPTION:
XS GIS Cut Line= 4
      2295735.13     13336915.95      2295120.65     13337257.96
      2295045.04     13337762.30      2295920.98     13338512.48
#Sta/Elev= 30
  4075.3  262.39  4126.2  259.59  4147.9  259.74  4256.6  253.21  4288.6  252.97
  4413.2  246.51  4427.1  247.62  4481.6  244.70  4537.8  242.83  4734.9  241.40
  4777.4  242.93  4838.1  241.27  4954.8  242.01  4970.8  241.73  4996.9  238.29
  4999.6  237.79  5002.9  238.29  5010.0  240.69  5029.8  240.91  5040.3  239.58
  5070.7  241.45  5090.9  239.52  5161.7  242.07  5281.7  242.85  5414.0  244.34
  5617.0  244.05  5729.5  244.92  6010.0  246.99  6286.6  255.28  6441.8  256.68
#Mann=9,-1,0
  4075.3    0.05       0  4481.6     0.1       0  4734.9    0.05       0
  4954.8     0.1       0  4996.9    0.07       0  5002.9     0.1       0
  5281.7    0.05       0  5617.0     0.1       0  5729.5    0.05       0
Bank Sta=4996.9,5002.9
Exp/Cntr=0.3,0.1

Chan Stop Cuts=-1