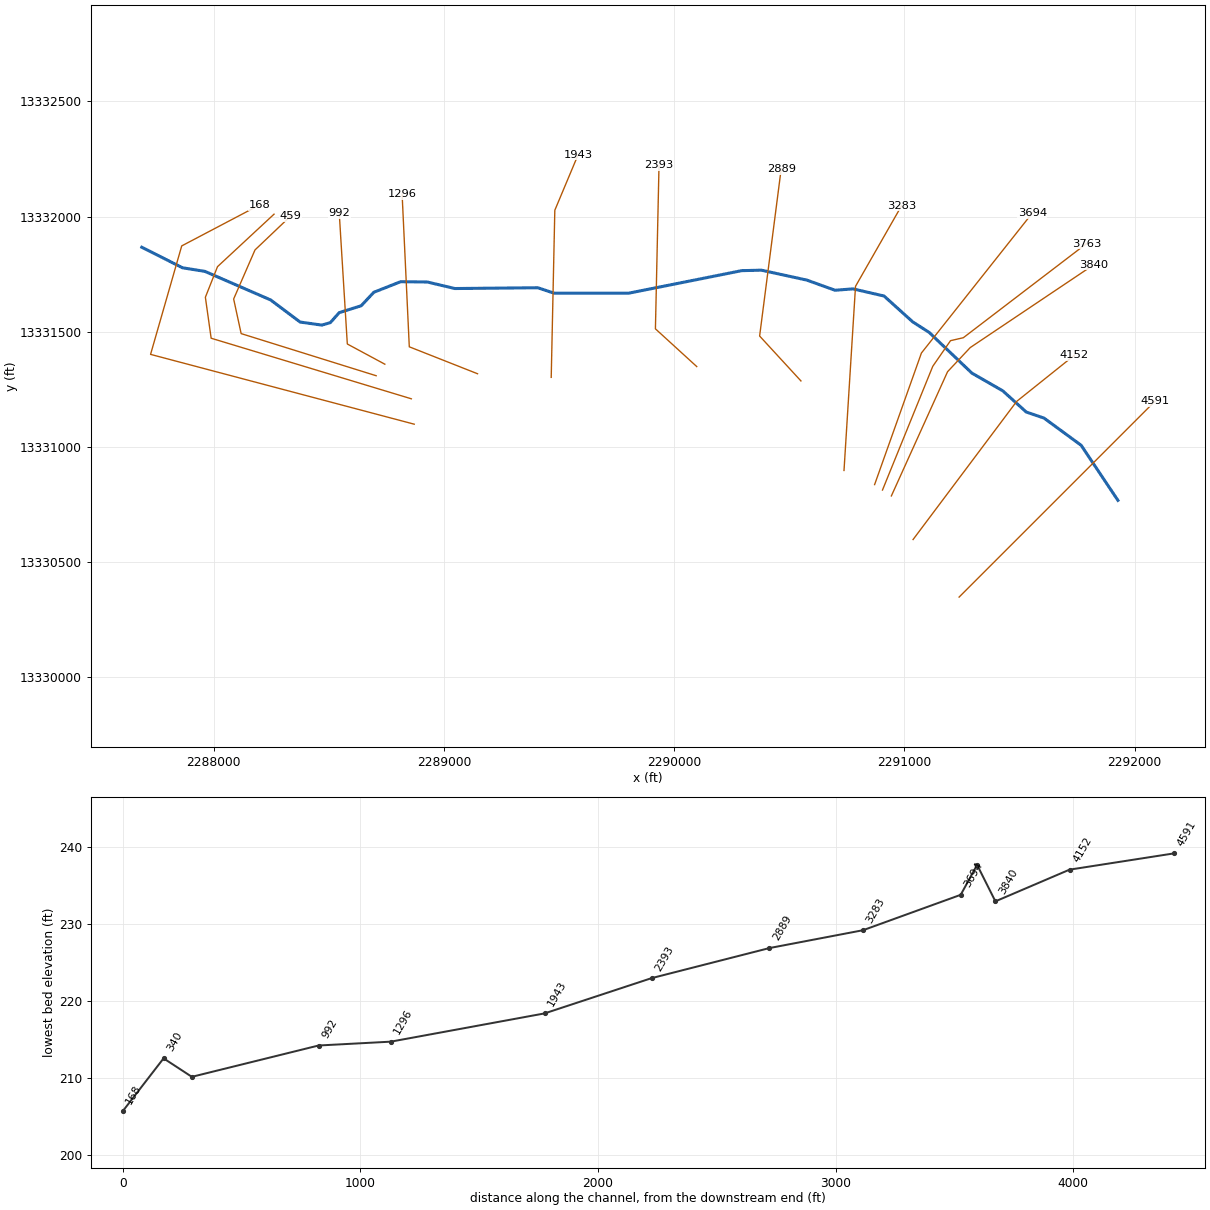
--- UNT007 IN NURI.prj (project) ---

Proj Title=UNT007 IN NURI Base Level Engineering
Current Plan=p01
Default Exp/Contr=0.3,0.1
English Units
Geom File=g01
Flow File=f01
Plan File=p01
BEGIN DESCRIPTION:
UNT007 IN NURI
END DESCRIPTION:

--- UNT007 IN NURI.p01 (plan) ---

Plan Title=Multiple Run
Short Identifier=Multiple
Geom File=g01
Flow File=f01
Subcritical Flow
K Sum by GR= 0
Std Step Tol= 0.01
Critical Tol= 0.01
Num of Std Step Trials= 20
Max Error Tol= 0.3
Flow Tol Ratio= 0.001
Split Flow NTrial= 30
Split Flow Tol= 0.02
Split Flow Ratio= 0.02
Log Output Level= 0
Friction Slope Method= 1
Unsteady Friction Slope Method= 2
Unsteady Bridges Friction Slope Method= 1
Parabolic Critical Depth
Global Vel Dist=  1 , 1 , 1
Global Log Level= 0
CheckData=True
Encroach Param= -1, 0, 0, 0
BEGIN DESCRIPTION:
Multiple Run
END DESCRIPTION:

--- UNT007 IN NURI.f01 (steady flow) ---

Flow Title=Multiple
Number of Profiles=7
Profile Names=10-year,25-year,50-year,1pct_min,100-year,1pct_plu,500-year
River Rch & RM= UNT007 IN NURI,Reach-1,4591
     625     893    1119    1025    1387    1875    2137
River Rch & RM= UNT007 IN NURI,Reach-1,3283
     631     902    1132    1037    1403    1897    2167
Boundary for River Rch & Prof#=UNT007 IN NURI,Reach-1,1
Up Type=0
Dn Type=3
Dn Slope=0.005
Boundary for River Rch & Prof#=UNT007 IN NURI,Reach-1,2
Up Type=0
Dn Type=3
Dn Slope=0.005
Boundary for River Rch & Prof#=UNT007 IN NURI,Reach-1,3
Up Type=0
Dn Type=3
Dn Slope=0.005
Boundary for River Rch & Prof#=UNT007 IN NURI,Reach-1,4
Up Type=0
Dn Type=3
Dn Slope=0.005
Boundary for River Rch & Prof#=UNT007 IN NURI,Reach-1,5
Up Type=0
Dn Type=3
Dn Slope=0.005
Boundary for River Rch & Prof#=UNT007 IN NURI,Reach-1,6
Up Type=0
Dn Type=3
Dn Slope=0.005
Boundary for River Rch & Prof#=UNT007 IN NURI,Reach-1,7
Up Type=0
Dn Type=3
Dn Slope=0.005

--- UNT007 IN NURI.g01 (geometry) ---

Geom Title=Existing Conditions

River Reach=UNT007 IN NURI,Reach-1
Reach XY= 30
      2291927.72     13330766.86      2291767.74     13331006.38
      2291606.69     13331124.36      2291529.35     13331150.79
      2291427.62     13331242.65      2291293.08     13331319.91
      2291107.93     13331496.37      2291036.21     13331542.37
      2290911.79     13331654.59      2290777.19     13331685.76
      2290698.87     13331679.73      2290576.47     13331723.84
      2290378.90     13331766.94      2290293.34     13331764.93
      2289802.68     13331666.95      2289477.78     13331667.14
      2289407.60     13331690.67      2289047.55     13331687.22
      2288927.51     13331715.58      2288811.90     13331716.92
      2288695.38     13331671.05      2288640.19     13331612.33
      2288544.78     13331582.43      2288506.37     13331539.16
      2288469.43     13331528.35      2288375.03     13331541.60
      2288247.07     13331637.61      2287961.48     13331761.75
      2287864.26     13331777.37      2287687.38     13331866.56

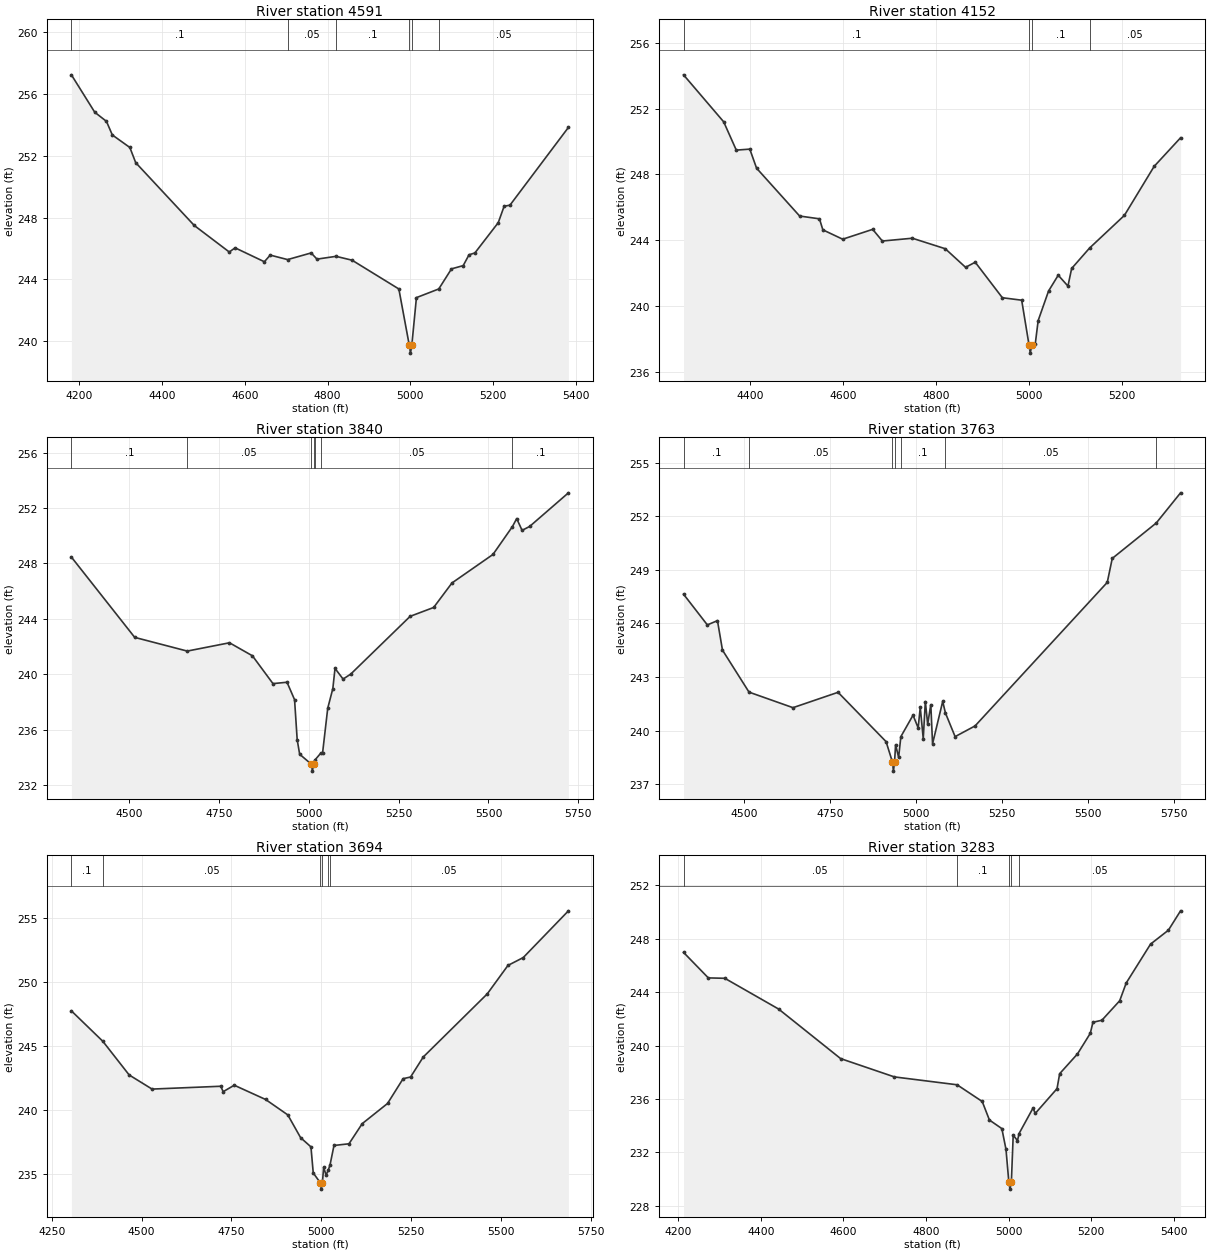
Type RM Length L Ch R = 1,4591,439,439,439
BEGIN DESCRIPTION:
UNT007 IN NURI 8.0
END DESCRIPTION:
XS GIS Cut Line= 3
      2291237.74     13330346.88      2291837.72     13330946.85
      2292087.69     13331196.82
#Sta/Elev= 30
  4180.6  257.23  4237.1  254.81  4265.4  254.22  4279.6  253.34  4322.0  252.53
  4336.1  251.55  4477.6  247.49  4562.4  245.77  4576.5  246.04  4647.3  245.14
  4661.4  245.57  4703.5  245.28  4760.4  245.71  4774.5  245.31  4820.6  245.49
  4859.4  245.24  4972.5  243.38  4997.8  239.73  5000.6  239.23  5003.8  239.73
  5015.0  242.82  5069.0  243.38  5099.8  244.68  5128.1  244.89  5142.2  245.59
  5156.4  245.71  5212.9  247.67  5227.1  248.73  5241.2  248.80  5382.6  253.83
#Mann=6,-1,0
  4180.6     0.1       0  4703.5    0.05       0  4820.6     0.1       0
  4997.8    0.07       0  5003.8     0.1       0  5069.0    0.05       0
Bank Sta=4997.8,5003.8
Exp/Cntr=0.3,0.1

Type RM Length L Ch R = 1,4152,312,312,312
BEGIN DESCRIPTION:
UNT007 IN NURI 7.0
END DESCRIPTION:
XS GIS Cut Line= 3
      2291037.71     13330596.84      2291487.72     13331196.85
      2291737.74     13331396.87
#Sta/Elev= 30
  4256.3  254.05  4342.8  251.19  4369.9  249.47  4399.0  249.53  4413.6  248.37
  4506.3  245.46  4549.0  245.29  4556.3  244.62  4599.0  244.05  4663.6  244.65
  4684.4  243.94  4749.0  244.11  4819.9  243.47  4863.6  242.34  4884.4  242.65
  4942.8  240.49  4984.4  240.34  5000.2  237.62  5002.9  237.12  5006.2  237.62
  5013.5  237.65  5019.9  239.10  5042.3  240.90  5063.1  241.86  5084.0  241.20
  5092.0  242.27  5130.5  243.51  5205.6  245.50  5269.6  248.48  5326.5  250.22
#Mann=4,-1,0
  4256.3     0.1       0  5000.2    0.07       0  5006.2     0.1       0
  5130.5    0.05       0
Bank Sta=5000.2,5006.2
Exp/Cntr=0.3,0.1

Type RM Length L Ch R = 1,3840,77,77,77
BEGIN DESCRIPTION:
Mapping XS d79db2f4
END DESCRIPTION:
XS GIS Cut Line= 4
      2290943.48     13330786.28      2291187.57     13331325.84
      2291286.06     13331430.76      2291823.57     13331791.23
#Sta/Elev= 30
  4339.3  248.46  4515.5  242.66  4661.7  241.67  4779.3  242.27  4843.1  241.33
  4900.3  239.32  4939.4  239.42  4960.4  238.16  4967.7  235.27  4974.6  234.22
  5007.2  233.50  5010.0  233.00  5013.2  233.50  5016.7  233.79  5033.4  234.30
  5038.5  234.34  5052.7  237.54  5066.9  238.96  5073.0  240.42  5095.4  239.65
  5116.4  240.00  5282.1  244.18  5347.5  244.82  5398.5  246.59  5512.6  248.65
  5566.7  250.66  5578.6  251.24  5593.6  250.39  5614.6  250.67  5722.6  253.10
#Mann=7,-1,0
  4339.3     0.1       0  4661.7    0.05       0  5007.2    0.03       0
  5013.2    0.05       0  5016.7     0.1       0  5033.4    0.05       0
  5566.7     0.1       0
Bank Sta=5007.2,5013.2
Exp/Cntr=0.3,0.1

Type RM Length L Ch R = 1,3763,69,69,69
BEGIN DESCRIPTION:
Mapping XS bada303f
END DESCRIPTION:
XS GIS Cut Line= 5
      2290904.91     13330811.92      2291123.33     13331349.39
      2291200.41     13331460.74      2291256.09     13331473.58
      2291790.94     13331882.21
#Sta/Elev= 30
  4322.9  247.64  4392.2  245.92  4421.6  246.16  4436.2  244.51  4513.4  242.16
  4641.3  241.29  4772.4  242.15  4912.1  239.39  4930.7  238.24  4933.5  237.74
  4936.7  238.24  4939.8  239.22  4948.6  238.51  4955.1  239.67  4990.5  240.87
  5005.4  240.16  5011.5  241.31  5020.2  239.56  5026.3  241.63  5033.1  240.37
  5042.2  241.46  5047.3  239.27  5076.8  241.64  5084.8  240.99  5112.9  239.67
  5171.0  240.27  5555.5  248.30  5570.0  249.64  5697.9  251.62  5768.7  253.31
#Mann=7,-1,0
  4322.9     0.1       0  4513.4    0.05       0  4930.7    0.07       0
  4936.7    0.05       0  4955.1     0.1       0  5084.8    0.05       0
  5697.9     0.1       0
Bank Sta=4930.7,4936.7
Exp/Cntr=0.3,0.1

Type RM Length L Ch R = 1,3694,411,411,411
BEGIN DESCRIPTION:
UNT007 IN NURI 6.0
END DESCRIPTION:
XS GIS Cut Line= 3
      2290870.66     13330835.48      2291074.08     13331407.20
      2291555.88     13332015.34
#Sta/Elev= 30
  4304.9  247.73  4392.4  245.36  4465.6  242.74  4529.3  241.64  4720.3  241.86
  4727.2  241.44  4758.0  241.94  4845.2  240.83  4906.9  239.63  4942.5  237.86
  4971.3  237.14  4977.7  235.11  4997.2  234.35  4999.9  233.85  5003.2  234.35
  5006.6  235.55  5013.4  234.94  5019.8  235.35  5024.5  235.75  5035.4  237.25
  5077.1  237.38  5114.0  238.95  5184.4  240.52  5227.7  242.45  5248.5  242.58
  5283.8  244.14  5461.7  249.05  5519.4  251.27  5561.9  251.88  5687.6  255.52
#Mann=6,-1,0
  4304.9     0.1       0  4392.4    0.05       0  4997.2    0.03       0
  5003.2    0.05       0  5019.8     0.1       0  5024.5    0.05       0
Bank Sta=4997.2,5003.2
Exp/Cntr=0.3,0.1

Type RM Length L Ch R = 1,3283,394,394,394
BEGIN DESCRIPTION:
UNT007 IN NURI 5.0
END DESCRIPTION:
XS GIS Cut Line= 3
      2290737.72     13330896.90      2290787.72     13331696.85
      2290987.71     13332046.83
#Sta/Elev= 30
  4212.3  246.97  4272.4  245.06  4312.4  245.03  4442.7  242.73  4593.0  239.02
  4723.2  237.65  4875.3  237.06  4936.2  235.81  4953.7  234.42  4983.8  233.78
  4993.8  232.23  5000.8  229.75  5003.5  229.25  5006.8  229.75  5011.3  233.29
  5021.7  232.88  5025.5  233.41  5059.2  235.31  5064.9  234.92  5117.5  236.77
  5123.9  237.89  5167.1  239.37  5198.1  240.91  5204.6  241.74  5226.2  241.89
  5269.4  243.35  5285.2  244.68  5344.2  247.59  5387.4  248.63  5416.9  250.08
#Mann=5,-1,0
  4212.3    0.05       0  4875.3     0.1       0  5000.8    0.07       0
  5006.8     0.1       0  5025.5    0.05       0
Bank Sta=5000.8,5006.8
Exp/Cntr=0.3,0.1

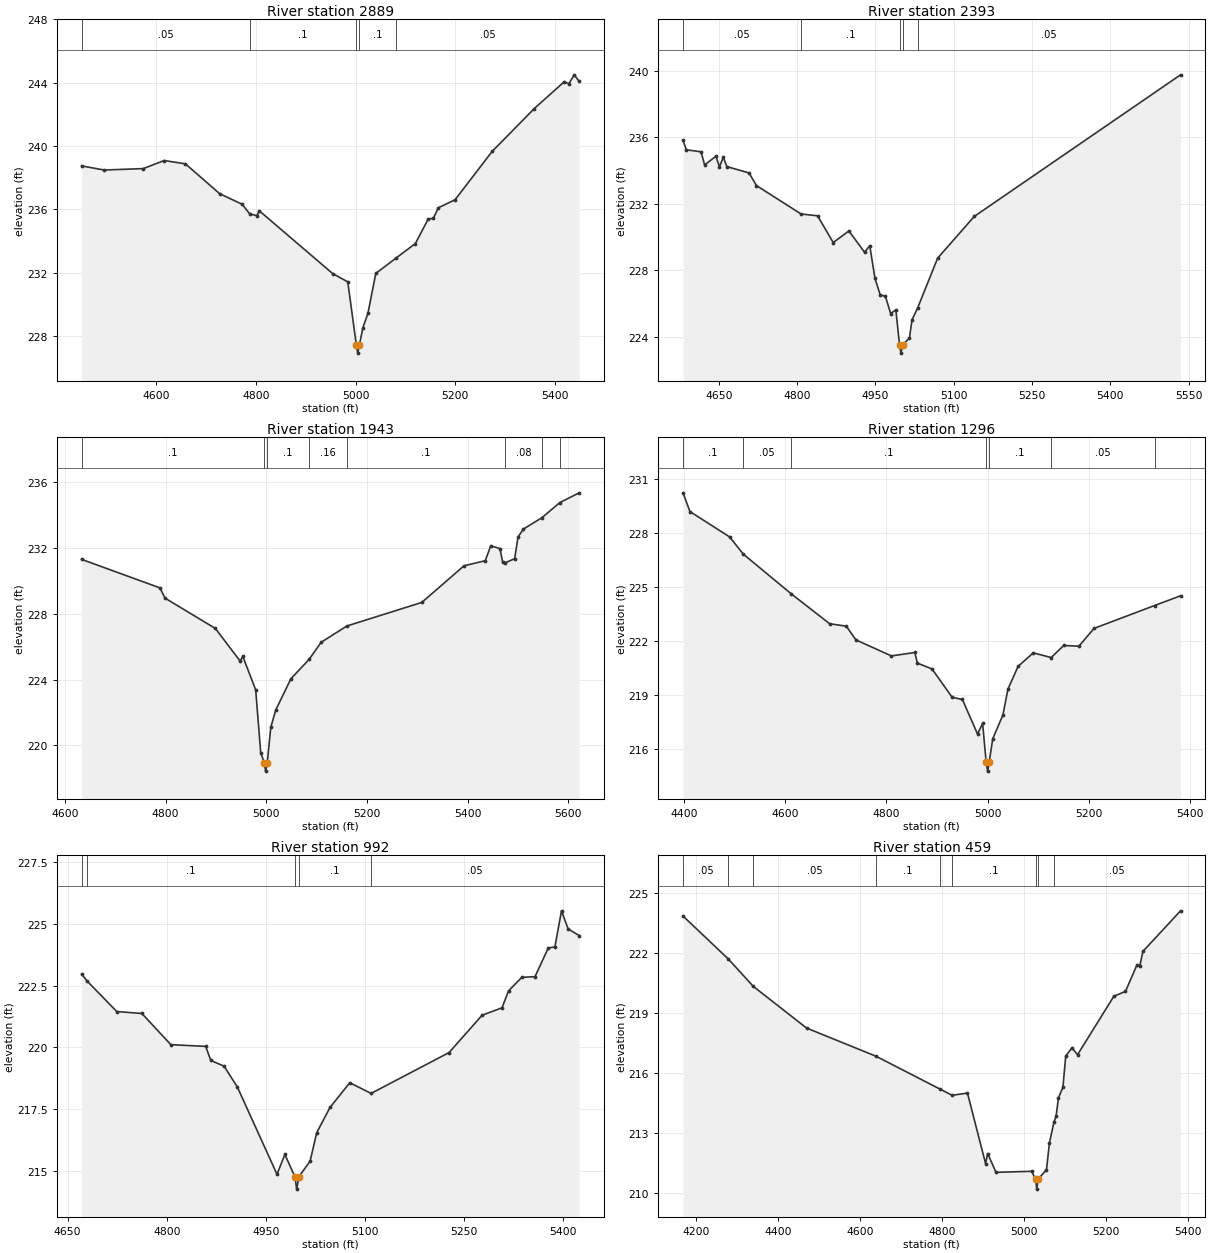
Type RM Length L Ch R = 1,2889,496,496,496
BEGIN DESCRIPTION:
UNT007 IN NURI 4.0
END DESCRIPTION:
XS GIS Cut Line= 3
      2290550.64     13331285.82      2290371.16     13331480.91
      2290464.81     13332206.70
#Sta/Elev= 30
  4451.3  238.75  4496.4  238.49  4574.7  238.58  4616.6  239.09  4659.2  238.88
  4728.0  236.99  4772.8  236.33  4788.0  235.72  4802.4  235.61  4807.4  235.91
  4954.3  231.95  4984.5  231.43  5001.7  227.43  5004.5  226.93  5007.7  227.43
  5014.8  228.54  5024.9  229.44  5040.6  231.96  5080.3  232.91  5120.0  233.85
  5145.9  235.41  5155.9  235.43  5166.0  236.11  5199.4  236.61  5273.7  239.66
  5358.2  242.37  5418.1  244.06  5427.5  243.94  5438.3  244.50  5448.2  244.08
#Mann=5,-1,0
  4451.3    0.05       0  4788.0     0.1       0  5001.7    0.07       0
  5007.7     0.1       0  5080.3    0.05       0
Bank Sta=5001.7,5007.7
Exp/Cntr=0.3,0.1

Type RM Length L Ch R = 1,2393,450,450,450
BEGIN DESCRIPTION:
UNT007 IN NURI 3.0
END DESCRIPTION:
XS GIS Cut Line= 3
      2290098.00     13331348.24      2289918.51     13331512.13
      2289934.11     13332222.10
#Sta/Elev= 30
  4581.5  235.82  4587.8  235.25  4616.1  235.13  4622.9  234.34  4644.5  234.86
  4651.3  234.23  4658.7  234.80  4665.5  234.24  4708.0  233.86  4722.2  233.10
  4807.6  231.39  4839.3  231.28  4869.3  229.67  4899.3  230.37  4929.3  229.09
  4939.3  229.48  4949.3  227.51  4959.3  226.53  4969.3  226.44  4979.3  225.40
  4989.3  225.62  4996.3  223.52  4999.1  223.02  5002.3  223.52  5015.3  223.93
  5020.3  225.03  5031.2  225.75  5069.3  228.73  5139.4  231.24  5534.7  239.76
#Mann=5,-1,0
  4581.5    0.05       0  4807.6     0.1       0  4996.3    0.07       0
  5002.3     0.1       0  5031.2    0.05       0
Bank Sta=4996.3,5002.3
Exp/Cntr=0.3,0.1

Type RM Length L Ch R = 1,1943,647,647,647
BEGIN DESCRIPTION:
UNT007 IN NURI 2.0
END DESCRIPTION:
XS GIS Cut Line= 3
      2289465.86     13331301.37      2289481.47     13332027.21
      2289582.83     13332268.91
#Sta/Elev= 30
  4633.5  231.29  4789.0  229.56  4799.0  228.94  4899.0  227.10  4948.4  225.11
  4953.4  225.41  4979.1  223.37  4989.1  219.57  4996.1  218.94  4998.8  218.44
  5002.1  218.94  5009.1  221.10  5019.1  222.16  5049.1  224.05  5085.2  225.22
  5109.1  226.26  5160.4  227.25  5309.1  228.68  5392.8  230.90  5435.0  231.21
  5445.9  232.11  5464.2  231.95  5469.6  231.13  5474.9  231.09  5493.4  231.33
  5500.1  232.65  5510.9  233.13  5547.9  233.83  5583.3  234.74  5621.6  235.33
#Mann=8,-1,0
  4633.5     0.1       0  4996.1    0.07       0  5002.1     0.1       0
  5085.2    0.16       0  5160.4     0.1       0  5474.9    0.08       0
  5547.9    0.05       0  5583.3     0.1       0
Bank Sta=4996.1,5002.1
Exp/Cntr=0.3,0.1

Type RM Length L Ch R = 1,1296,304,304,304
BEGIN DESCRIPTION:
Mapping XS 13f0e865
END DESCRIPTION:
XS GIS Cut Line= 3
      2289145.88     13331317.02      2288849.32     13331434.08
      2288818.10     13332097.42
#Sta/Elev= 30
  4398.3  230.23  4412.0  229.19  4490.4  227.78  4517.6  226.82  4611.7  224.63
  4687.9  222.96  4721.0  222.82  4739.9  222.06  4810.0  221.17  4856.3  221.36
  4861.3  220.77  4890.1  220.45  4930.1  218.87  4950.2  218.75  4980.2  216.83
  4990.2  217.42  4997.2  215.27  5000.0  214.77  5003.2  215.27  5010.2  216.57
  5030.2  217.88  5040.3  219.33  5060.3  220.59  5090.3  221.34  5125.6  221.08
  5150.4  221.75  5180.4  221.71  5210.4  222.70  5329.9  223.97  5381.2  224.51
#Mann=7,-1,0
  4398.3     0.1       0  4517.6    0.05       0  4611.7     0.1       0
  4997.2    0.07       0  5003.2     0.1       0  5125.6    0.05       0
  5329.9     0.1       0
Bank Sta=4997.2,5003.2
Exp/Cntr=0.3,0.1

Type RM Length L Ch R = 1,992,533,533,533
BEGIN DESCRIPTION:
Mapping XS a7756d20
END DESCRIPTION:
XS GIS Cut Line= 3
      2288743.02     13331358.58      2288580.08     13331446.31
      2288545.10     13332013.58
#Sta/Elev= 30
  4671.2  222.96  4679.5  222.68  4724.3  221.45  4762.4  221.37  4806.2  220.11
  4859.0  220.04  4866.8  219.47  4886.9  219.24  4906.9  218.40  4967.0  214.87
  4978.9  215.67  4994.1  214.77  4996.8  214.27  5000.1  214.77  5017.1  215.40
  5027.1  216.55  5047.2  217.57  5077.2  218.57  5109.5  218.14  5227.5  219.79
  5277.6  221.30  5307.7  221.60  5317.7  222.29  5337.7  222.83  5357.7  222.86
  5377.8  224.02  5387.8  224.06  5397.8  225.52  5407.8  224.79  5424.6  224.52
#Mann=5,-1,0
  4671.2    0.05       0  4679.5     0.1       0  4994.1    0.07       0
  5000.1     0.1       0  5109.5    0.05       0
Bank Sta=4994.1,5000.1
Exp/Cntr=0.3,0.1

Type RM Length L Ch R = 1,459,119,119,119
BEGIN DESCRIPTION:
Mapping XS 3bf186c6
END DESCRIPTION:
XS GIS Cut Line= 5
      2288705.41     13331308.45      2288118.90     13331491.42
      2288086.31     13331641.81      2288179.05     13331854.86
      2288333.12     13332001.47
#Sta/Elev= 30
  4168.5  223.85  4279.1  221.70  4340.1  220.33  4469.9  218.25  4639.4  216.84
  4795.3  215.20  4824.7  214.89  4862.2  215.00  4906.3  211.48  4911.4  211.98
  4931.7  211.04  5018.6  211.09  5028.5  210.70  5031.2  210.20  5034.5  210.70
  5054.9  211.17  5062.2  212.53  5073.1  213.55  5078.3  213.84  5084.1  214.77
  5095.0  215.29  5101.8  216.85  5116.8  217.26  5130.7  216.92  5219.2  219.84
  5247.5  220.08  5275.8  221.42  5282.7  221.37  5290.0  222.08  5381.8  224.11
#Mann=9,-1,0
  4168.5    0.05       0  4279.1     0.1       0  4340.1    0.05       0
  4639.4     0.1       0  4795.3    0.05       0  4824.7     0.1       0
  5028.5    0.07       0  5034.5     0.1       0  5073.1    0.05       0
Bank Sta=5028.5,5034.5
Exp/Cntr=0.3,0.1

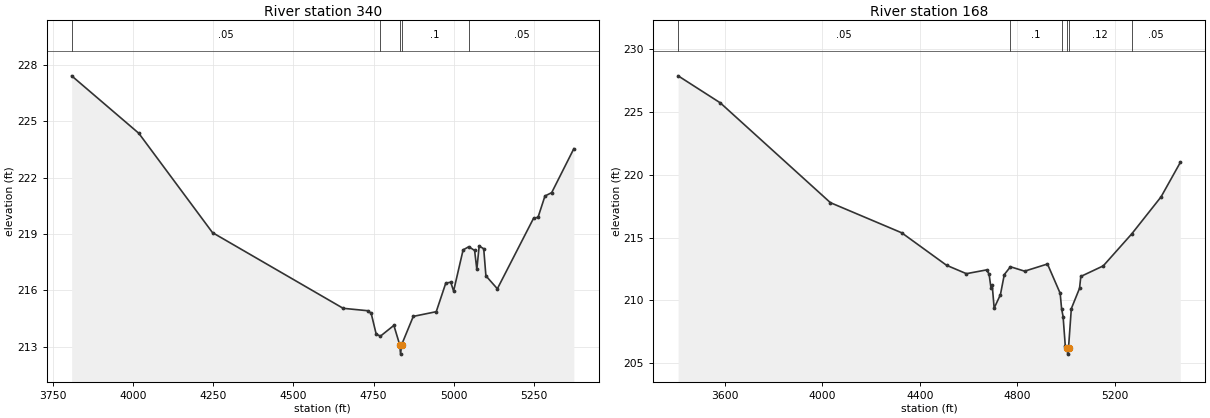
Type RM Length L Ch R = 1,340,172,172,172
BEGIN DESCRIPTION:
Mapping XS 86c65482
END DESCRIPTION:
XS GIS Cut Line= 5
      2288858.28     13331208.20      2287988.56     13331471.37
      2287963.50     13331649.33      2288016.13     13331782.17
      2288261.79     13332010.28
#Sta/Elev= 30
  3808.0  227.42  4017.5  224.36  4247.4  219.07  4654.9  215.04  4732.3  214.91
  4742.4  214.77  4758.0  213.66  4771.4  213.56  4813.1  214.13  4831.3  213.10
  4834.0  212.60  4837.3  213.10  4873.7  214.61  4945.3  214.86  4975.0  216.38
  4990.5  216.43  4999.4  215.96  5029.1  218.15  5046.8  218.32  5065.0  218.12
  5071.9  217.11  5079.2  218.36  5093.4  218.21  5100.2  216.77  5135.9  216.08
  5248.7  219.83  5262.9  219.89  5284.4  221.02  5305.4  221.20  5374.5  223.54
#Mann=5,-1,0
  3808.0    0.05       0  4771.4     0.1       0  4831.3    0.07       0
  4837.3     0.1       0  5046.8    0.05       0
Bank Sta=4831.3,4837.3
Exp/Cntr=0.3,0.1

Type RM Length L Ch R = 1,168,0,0,0
BEGIN DESCRIPTION:
UNT007 IN NURI 1.0
END DESCRIPTION:
XS GIS Cut Line= 4
      2288870.81     13331097.92      2287725.39     13331401.19
      2287860.74     13331872.40      2288199.14     13332050.38
#Sta/Elev= 30
  3409.6  227.87  3582.4  225.72  4033.5  217.78  4325.9  215.38  4509.3  212.80
  4590.7  212.13  4673.2  212.43  4683.6  212.10  4691.2  211.03  4696.4  211.24
  4704.4  209.39  4730.1  210.46  4746.0  212.06  4771.2  212.68  4829.3  212.33
  4922.9  212.90  4974.9  210.57  4980.8  209.33  4986.9  208.72  4995.7  206.41
  5003.1  206.23  5005.9  205.73  5009.1  206.23  5020.6  209.35  5054.3  210.97
  5059.5  211.91  5151.4  212.75  5268.3  215.30  5388.2  218.24  5467.1  220.98
#Mann=6,-1,0
  3409.6    0.05       0  4771.2     0.1       0  4980.8    0.12       0
  5003.1    0.07       0  5009.1    0.12       0  5268.3    0.05       0
Bank Sta=5003.1,5009.1
Exp/Cntr=0.3,0.1

Chan Stop Cuts=-1