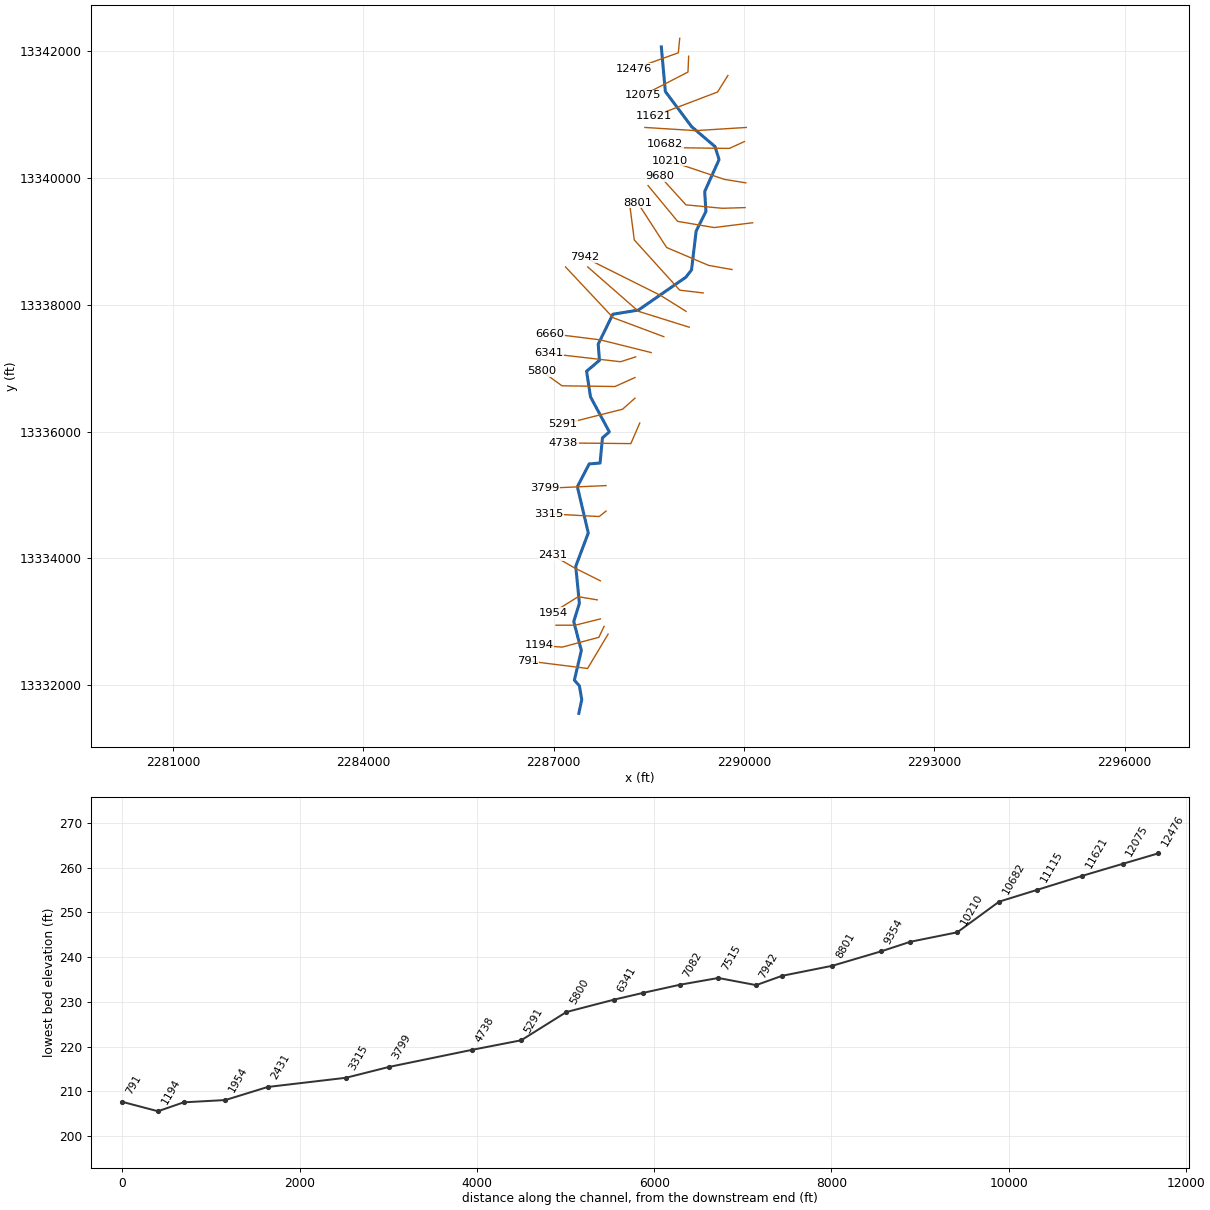
--- UNT008 IN NURI.prj (project) ---

Proj Title=UNT008 IN NURI Base Level Engineering
Current Plan=p01
Default Exp/Contr=0.3,0.1
English Units
Geom File=g01
Flow File=f01
Plan File=p01
Y Axis Title=Elevation
X Axis Title(PF)=Main Channel Distance
X Axis Title(XS)=Station
BEGIN DESCRIPTION:
UNT008 IN NURI
END DESCRIPTION:
DSS Export Rating Curves= 0
DSS Export Rating Curve Sorted= 0
DSS Export Volume Flow Curves= 0
DXF OffsetX= 0
DXF OffsetY= 0
DXF ScaleX= 1
DXF ScaleY= 10

--- UNT008 IN NURI.p01 (plan) ---

Plan Title=Multiple Run
Short Identifier=Multiple
Geom File=g01
Flow File=f01
Subcritical Flow
K Sum by GR= 0
Std Step Tol= 0.01
Critical Tol= 0.01
Num of Std Step Trials= 20
Max Error Tol= 0.3
Flow Tol Ratio= 0.001
Split Flow NTrial= 30
Split Flow Tol= 0.02
Split Flow Ratio= 0.02
Log Output Level= 0
Friction Slope Method= 1
Unsteady Friction Slope Method= 2
Unsteady Bridges Friction Slope Method= 1
Parabolic Critical Depth
Global Vel Dist=  1 , 1 , 1
Global Log Level= 0
CheckData=True
Encroach Param= -1, 0, 0, 0
BEGIN DESCRIPTION:
Multiple Run
END DESCRIPTION:

--- UNT008 IN NURI.f01 (steady flow) ---

Flow Title=Multiple
Program Version=4.10
Number of Profiles= 7
Profile Names=10-year,25-year,50-year,1pct_min,100-year,1pct_plu,500-year
River Rch & RM=UNT008 IN NURI,Reach-1         ,12476
     408     576     718     657     888    1201    1374
River Rch & RM=UNT008 IN NURI,Reach-1         ,8801
     481     686     860     792    1071    1448    1681
River Rch & RM=UNT008 IN NURI,Reach-1         ,6341
     522     747     939     866    1171    1584    1846
River Rch & RM=UNT008 IN NURI,Reach-1         ,1954
     522     747     939     866    1171    1584    1846
River Rch & RM=UNT008 IN NURI,Reach-1         ,1484
     540     774     974     899    1216    1644    1920
Boundary for River Rch & Prof#=UNT008 IN NURI,Reach-1         , 1
Up Type= 0
Dn Type= 3
Dn Slope=0.005
Boundary for River Rch & Prof#=UNT008 IN NURI,Reach-1         , 2
Up Type= 0
Dn Type= 3
Dn Slope=0.005
Boundary for River Rch & Prof#=UNT008 IN NURI,Reach-1         , 3
Up Type= 0
Dn Type= 3
Dn Slope=0.005
Boundary for River Rch & Prof#=UNT008 IN NURI,Reach-1         , 4
Up Type= 0
Dn Type= 3
Dn Slope=0.005
Boundary for River Rch & Prof#=UNT008 IN NURI,Reach-1         , 5
Up Type= 0
Dn Type= 3
Dn Slope=0.005
Boundary for River Rch & Prof#=UNT008 IN NURI,Reach-1         , 6
Up Type= 0
Dn Type= 3
Dn Slope=0.005
Boundary for River Rch & Prof#=UNT008 IN NURI,Reach-1         , 7
Up Type= 0
Dn Type= 3
Dn Slope=0.005
DSS Import GetInterval= 0
DSS Import GetPeak= 0
DSS Import FillOption= 0

--- UNT008 IN NURI.g01 (geometry) ---

Geom Title=Existing Conditions
Program Version=4.10

River Reach=UNT008 IN NURI  ,Reach-1
Reach XY= 30
      2288697.72     13342066.86      2288761.18     13341363.55
      2289174.42     13340810.13      2289544.74     13340494.56
      2289607.96     13340289.72      2289381.33     13339786.25
      2289400.77     13339472.36      2289246.61     13339163.33
      2289173.69     13338549.45      2289083.13     13338434.11
      2288336.61     13337917.18       2287932.8     13337850.89
      2287703.02     13337379.95      2287722.56     13337124.24
       2287519.6     13336951.78      2287581.45     13336548.46
      2287877.77     13335996.58       2287769.8     13335901.27
      2287732.02     13335504.18      2287560.55     13335491.02
      2287374.48     13335130.69      2287546.45     13334401.78
      2287348.72     13333876.97      2287406.14     13333292.74
      2287317.16     13333004.45      2287437.25     13332548.42
       2287327.3      13332081.5      2287405.84     13331991.29
      2287443.77     13331776.07      2287397.72     13331556.86

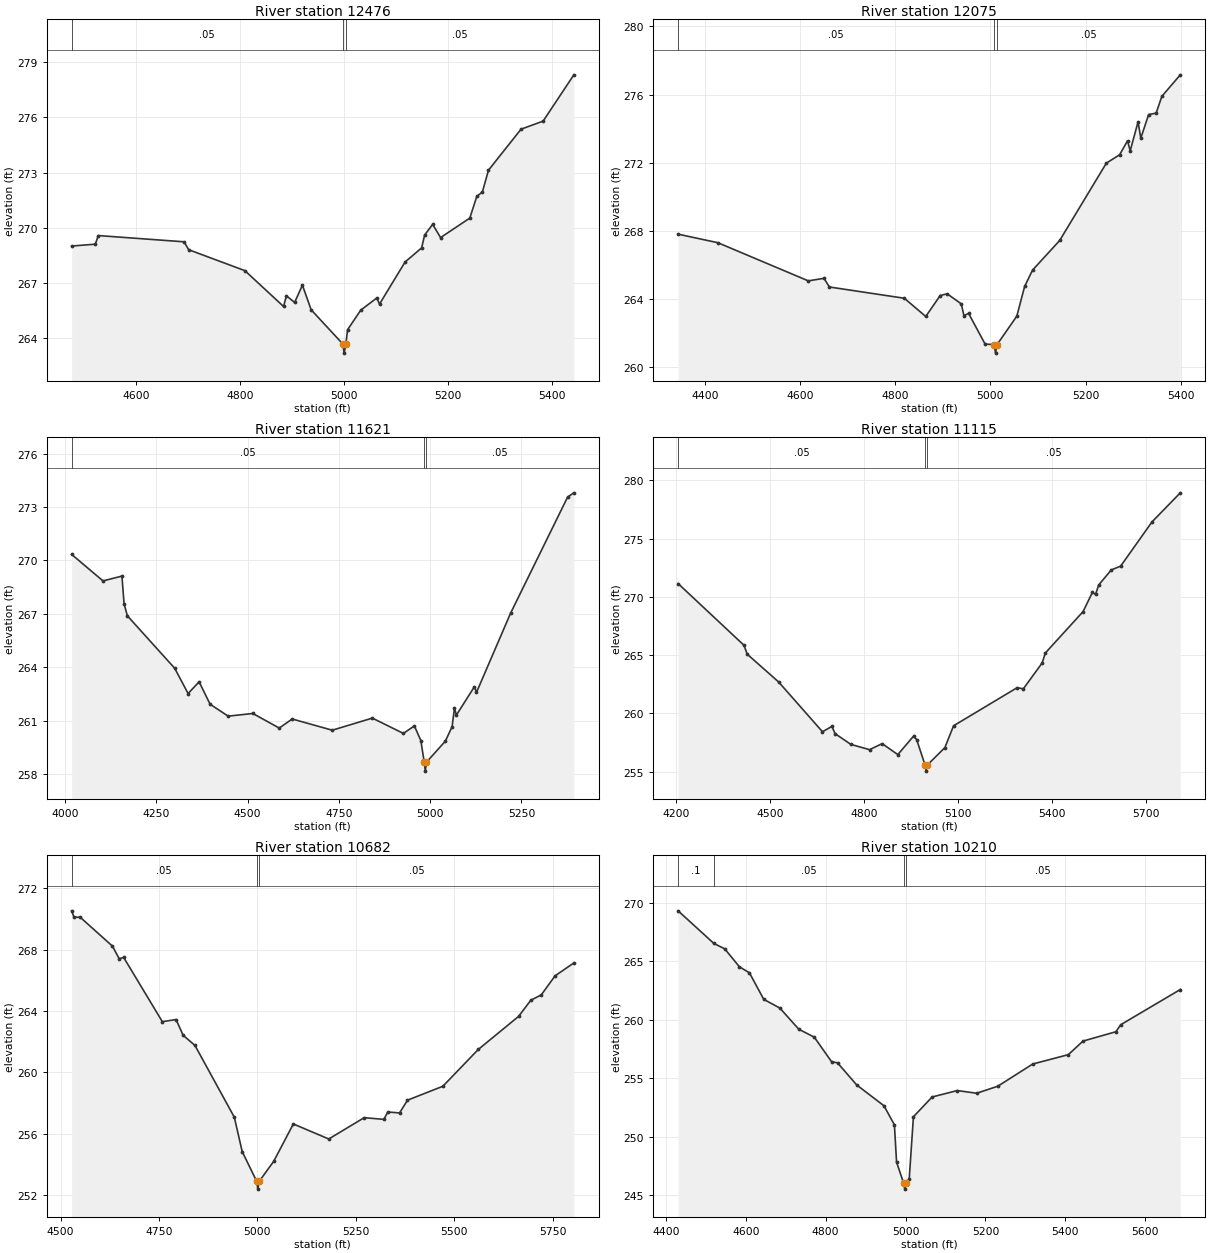
Type RM Length L Ch R = 1 ,12476   ,401,401,401
BEGIN DESCRIPTION:
UNT008 IN NURI 24.0
END DESCRIPTION:
XS GIS Cut Line= 3
      2288987.66     13342202.17      2288965.95     13341974.26
      2288272.13     13341724.92
#Sta/Elev= 30
    4476     269  4521.5   269.1  4527.3  269.57  4692.3  269.23  4701.1   268.8
  4809.3  267.66  4883.7  265.71  4889.2  266.29    4905  265.93    4920  266.87
  4936.8  265.53  4997.6  263.67  5000.3  263.17  5003.6  263.67  5006.8  264.44
  5032.2  265.51    5063  266.17  5068.3  265.84  5117.5  268.13  5149.4   268.9
  5155.1   269.6  5170.6  270.18  5185.8  269.46    5242  270.52  5255.6  271.71
  5266.2  271.94    5278  273.13  5340.6  275.36  5383.1   275.8  5442.2  278.32
#Mann= 3 ,-1 , 0
    4476     .05       0  4997.6     .03       0  5003.6     .05       0
Bank Sta=4997.6,5003.6
XS Rating Curve= 0 ,0
Exp/Cntr=0.3,0.1

Type RM Length L Ch R = 1 ,12075   ,454,454,454
BEGIN DESCRIPTION:
UNT008 IN NURI 23.0
END DESCRIPTION:
XS GIS Cut Line= 3
      2289128.71     13341920.05      2289117.86     13341670.44
      2288402.55     13341301.95
#Sta/Elev= 30
  4344.2  267.81  4427.5  267.31  4617.6  265.07  4650.5  265.22  4661.9  264.71
  4819.2  264.05  4864.2  262.98  4894.5  264.21  4909.2  264.31  4938.8  263.72
  4944.4  263.03  4954.2  263.16  4988.8  261.36  5007.9  261.33  5010.7  260.83
  5013.9  261.33  5055.4     263  5071.8  264.74  5088.4   265.7  5145.4  267.44
  5243.5  271.98  5271.3  272.47  5287.9  273.29  5293.5   272.7    5310   274.4
  5315.7  273.44  5332.2  274.83  5347.9  274.91    5360   275.9  5398.7  277.16
#Mann= 3 ,-1 , 0
  4344.2     .05       0  5007.9     .03       0  5013.9     .05       0
Bank Sta=5007.9,5013.9
XS Rating Curve= 0 ,0
Exp/Cntr=0.3,0.1

Type RM Length L Ch R = 1 ,11621   ,506,506,506
BEGIN DESCRIPTION:
UNT008 IN NURI 22.0
END DESCRIPTION:
XS GIS Cut Line= 3
       2289747.2     13341616.19      2289584.44     13341355.77
      2288586.14     13340975.98
#Sta/Elev= 30
  4018.3  270.34  4104.1  268.85    4156  269.12  4161.9  267.56  4170.8  266.89
  4300.5  263.94  4337.2  262.52  4367.3  263.18  4397.4  261.92  4446.9  261.25
  4514.5   261.4  4586.8  260.58  4622.2  261.09    4732  260.46  4841.7  261.14
  4926.7  260.28  4956.8   260.7  4974.5  259.88  4983.9  258.66  4986.7  258.16
  4989.9  258.66  5041.8  259.85  5060.1  260.66  5066.6   261.7  5071.9  261.31
  5121.4  262.91  5126.8  262.58  5220.6  267.05  5376.4  273.56  5393.5   273.8
#Mann= 3 ,-1 , 0
  4018.3     .05       0  4983.9     .03       0  4989.9     .05       0
Bank Sta=4983.9,4989.9
XS Rating Curve= 0 ,0
Exp/Cntr=0.3,0.1

Type RM Length L Ch R = 1 ,11115   ,433,433,433
BEGIN DESCRIPTION:
UNT008 IN NURI 21.0
END DESCRIPTION:
XS GIS Cut Line= 3
      2290037.76     13340796.86      2289237.72     13340746.85
      2288437.68     13340796.86
#Sta/Elev= 30
    4206  271.14  4416.4  265.84  4426.5  265.08  4526.7   262.7  4666.9  258.42
    4697  258.88    4707  258.26  4757.1  257.34  4817.2  256.88  4857.3   257.4
  4907.4  256.46  4957.5  258.04  4967.5  257.75  4994.6  255.54  4997.3  255.04
  5000.6  255.54  5057.7  257.06  5085.3  258.93  5288.1   262.2  5308.2  262.11
  5368.3  264.33  5378.3  265.18  5498.6  268.73  5528.6  270.38  5538.6  270.21
  5548.7  271.02  5588.7  272.31  5618.8  272.64    5719  276.44  5809.2  278.93
#Mann= 3 ,-1 , 0
    4206     .05       0  4994.6     .03       0  5000.6     .05       0
Bank Sta=4994.6,5000.6
XS Rating Curve= 0 ,0
Exp/Cntr=0.3,0.1

Type RM Length L Ch R = 1 ,10682   ,472,472,472
BEGIN DESCRIPTION:
UNT008 IN NURI 20.0
END DESCRIPTION:
XS GIS Cut Line= 4
      2290007.58     13340574.51       2289768.9     13340466.01
      2288987.65     13340476.86      2288761.29     13340530.76
#Sta/Elev= 30
    4528  270.53  4533.9  270.12  4549.8  270.11  4631.6  268.23  4648.7  267.41
  4660.2  267.49  4758.5   263.3  4793.3  263.44  4811.4  262.41  4841.4  261.75
  4941.4  257.07  4961.4  254.83  4998.4  252.88  5001.1  252.38  5004.4  252.88
  5041.4  254.19  5091.4  256.63  5181.4  255.65  5271.4  257.04  5321.4  256.93
  5331.4  257.41  5361.4  257.35  5381.4  258.18  5471.4  259.09  5561.4  261.49
    5664  263.65  5694.8   264.7  5721.5  265.05  5756.5  266.29  5804.2  267.13
#Mann= 3 ,-1 , 0
    4528     .05       0  4998.4     .03       0  5004.4     .05       0
Bank Sta=4998.4,5004.4
XS Rating Curve= 0 ,0
Exp/Cntr=0.3,0.1

Type RM Length L Ch R = 1 ,10210   ,530,530,530
BEGIN DESCRIPTION:
UNT008 IN NURI 19.0
END DESCRIPTION:
XS GIS Cut Line= 3
      2290029.27     13339923.49      2289692.95     13339977.73
      2288824.92     13340270.69
#Sta/Elev= 30
  4430.8  269.33  4520.3  266.54  4547.5  266.08  4584.3  264.54  4609.3  264.03
  4645.1  261.76  4685.6  261.01  4732.9   259.2  4771.5  258.53  4814.8  256.43
  4829.8  256.33  4877.7  254.44  4945.9  252.66  4972.1  251.03  4977.5  247.84
  4995.3  246.03  4998.1  245.53  5001.3  246.03  5009.2  246.41  5019.7  251.72
  5066.5  253.41  5129.5  253.96    5178  253.73  5230.8  254.33  5318.3  256.23
  5407.4  257.03  5444.1  258.19  5526.3  258.99  5538.5  259.59  5687.6   262.6
#Mann= 4 ,-1 , 0
  4430.8      .1       0  4520.3     .05       0  4995.3     .03       0
  5001.3     .05       0
Bank Sta=4995.3,5001.3
XS Rating Curve= 0 ,0
Exp/Cntr=0.3,0.1

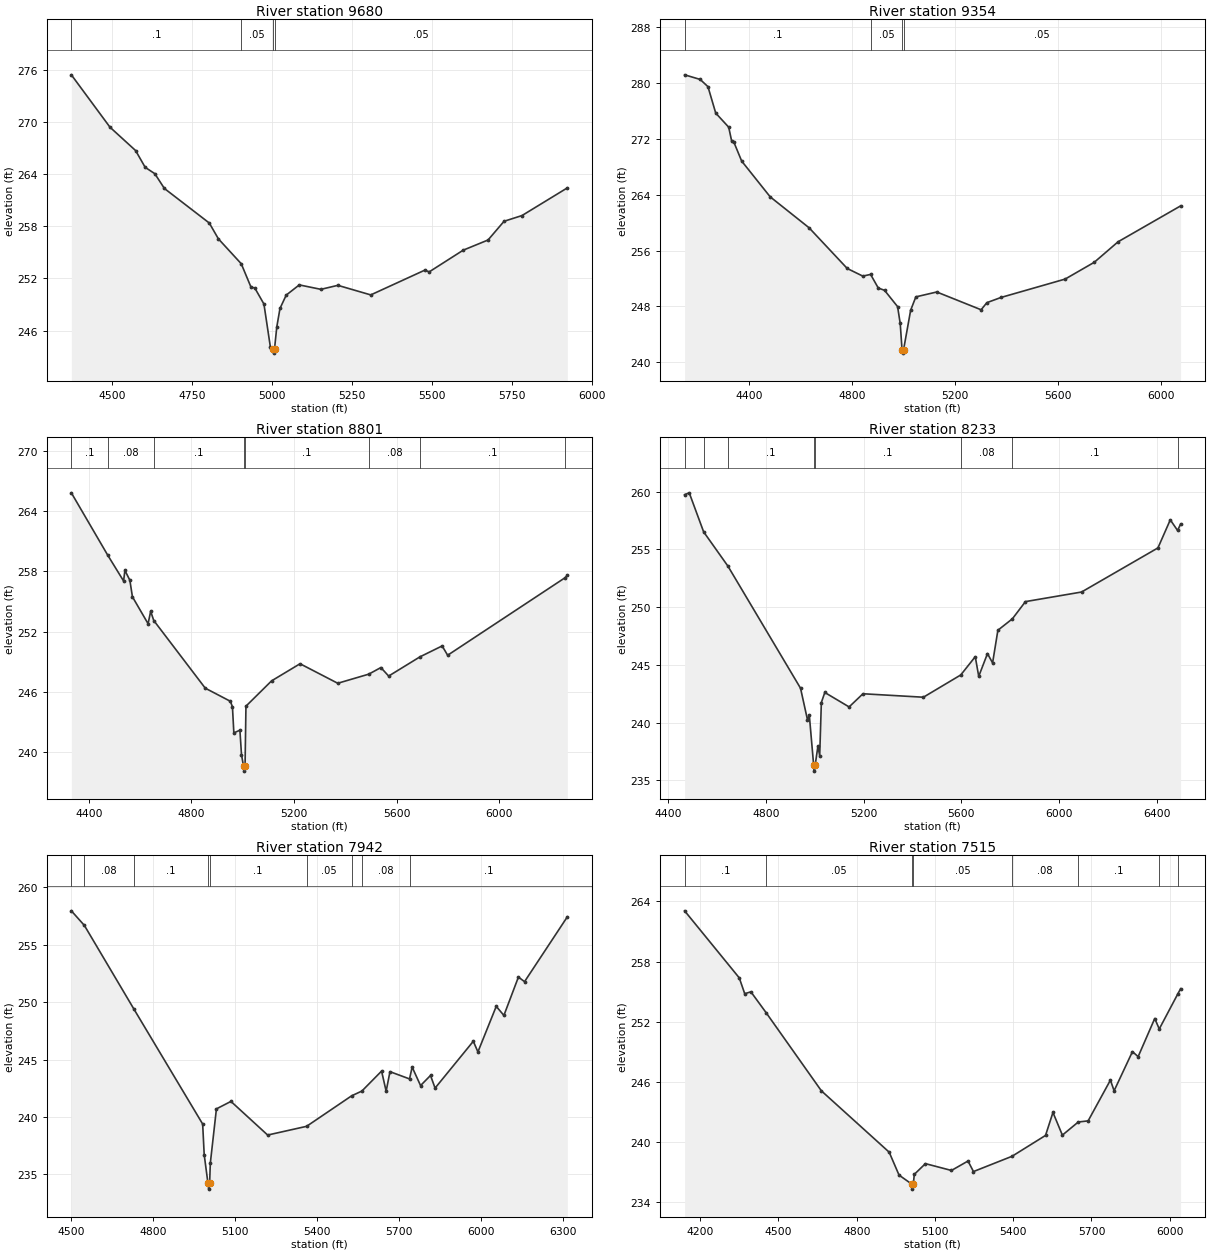
Type RM Length L Ch R = 1 ,9680    ,326,326,326
BEGIN DESCRIPTION:
UNT008 IN NURI 18.0
END DESCRIPTION:
XS GIS Cut Line= 4
      2290018.46     13339532.85      2289660.39       13339522.
      2289085.31     13339576.26      2288673.01     13340031.95
#Sta/Elev= 30
  4372.6  275.39  4493.4  269.37  4573.4  266.69  4603.4  264.76  4633.5  264.03
  4663.5  262.33  4803.8  258.36  4832.3  256.54  4903.7  253.68  4934.4  250.97
  4945.8  250.91  4974.6  249.05  4994.7  244.12  5001.7  243.91  5004.5  243.41
  5007.7  243.91  5014.8  246.43  5024.8  248.55  5044.3  250.08  5085.1  251.25
  5152.7  250.74  5205.6   251.2  5308.5   250.1  5477.1  252.94  5491.3  252.75
  5597.4  255.24  5675.1  256.41  5725.1  258.56  5781.3  259.22    5923   262.4
#Mann= 4 ,-1 , 0
  4372.6      .1       0  4903.7     .05       0  5001.7     .03       0
  5007.7     .05       0
Bank Sta=5001.7,5007.7
XS Rating Curve= 0 ,0
Exp/Cntr=0.3,0.1

Type RM Length L Ch R = 1 ,9354    ,553,553,553
BEGIN DESCRIPTION:
UNT008 IN NURI 17.0
END DESCRIPTION:
XS GIS Cut Line= 4
      2290137.79     13339294.13      2289530.19     13339218.18
       2288955.1     13339315.84      2288488.53     13339880.07
#Sta/Elev= 30
    4150  281.21  4210.5  280.55  4240.8  279.51    4271  275.72  4321.4   273.7
  4333.1  271.68  4341.6  271.54  4371.8  268.84  4482.6  263.71  4633.8  259.27
  4782.2  253.43  4842.5  252.34  4872.9  252.58  4902.7  250.63  4927.1   250.3
  4977.8  247.96    4988  245.54  4995.1  241.79  4997.9  241.29  5001.1  241.79
  5028.6  247.45  5048.8  249.36    5130  250.06  5302.4  247.51  5324.8  248.53
  5380.1  249.28  5628.9  251.91  5742.2  254.32  5834.7  257.26  6077.8  262.41
#Mann= 4 ,-1 , 0
    4150      .1       0  4872.9     .05       0  4995.1     .03       0
  5001.1     .05       0
Bank Sta=4995.1,5001.1
XS Rating Curve= 0 ,0
Exp/Cntr=0.3,0.1

Type RM Length L Ch R = 1 ,8801    ,568,568,568
BEGIN DESCRIPTION:
UNT008 IN NURI 16.0
END DESCRIPTION:
XS GIS Cut Line= 4
      2289812.33     13338556.29      2289443.38      13338621.4
      2288781.49     13338903.51      2288325.75     13339608.82
#Sta/Elev= 30
  4331.6  265.86  4473.2  259.64  4535.3  257.05  4540.4  258.11  4559.7  257.13
  4569.8  255.47  4630.8  252.78  4640.9  254.02    4653   253.1  4853.7  246.34
  4951.6  245.03  4959.7  244.48  4965.2  241.87  4988.8  242.14    4995   239.7
  5002.9  238.55  5005.7  238.05  5008.9  238.55  5012.4  244.54  5112.3  247.07
  5223.3  248.78  5370.3  246.83  5491.2  247.74  5538.4   248.4  5568.8  247.55
  5690.8  249.47  5777.3  250.56  5798.8  249.63  6255.6  257.36  6265.5  257.61
#Mann= 8 ,-1 , 0
  4331.6      .1       0  4473.2     .08       0    4653      .1       0
  5002.9     .07       0  5008.9      .1       0  5491.2     .08       0
  5690.8      .1       0  6255.6     .05       0
Bank Sta=5002.9,5008.9
XS Rating Curve= 0 ,0
Exp/Cntr=0.3,0.1

Type RM Length L Ch R = 1 ,8233    ,291,291,291
BEGIN DESCRIPTION:
UNT008 IN NURI 15.0
END DESCRIPTION:
XS GIS Cut Line= 4
      2289356.59     13338187.37      2288987.65     13338230.77
      2288271.51     13339022.87      2288195.55     13339608.84
#Sta/Elev= 30
  4467.6  259.74  4486.6   259.9  4545.5  256.52  4644.7  253.56  4942.1  242.98
  4970.5  240.25    4978  240.66  4995.9   236.3  4998.7   235.8  5001.9   236.3
  5013.1  237.94  5020.6  237.15  5027.3  241.74  5041.5  242.61  5140.9  241.36
  5197.7   242.5    5445   242.2    5598  244.13  5657.3  245.71  5671.5  244.01
  5707.3  245.98  5728.2  245.17  5749.9     248  5809.2  248.99  5862.7  250.48
  6092.4  251.31    6405  255.13  6455.5  257.56  6485.4  256.64  6497.8   257.2
#Mann= 8 ,-1 , 0
  4467.6      .1       0  4545.5     .08       0  4644.7      .1       0
  4995.9     .07       0  5001.9      .1       0    5598     .08       0
  5809.2      .1       0  6485.4     .05       0
Bank Sta=4995.9,5001.9
XS Rating Curve= 0 ,0
Exp/Cntr=0.3,0.1

Type RM Length L Ch R = 1 ,7942    ,427,427,427
BEGIN DESCRIPTION:
UNT008 IN NURI 14.0
END DESCRIPTION:
XS GIS Cut Line= 3
      2289087.76     13337896.83      2288687.72     13338146.85
       2287487.7     13338746.86
#Sta/Elev= 30
  4501.6  257.96  4549.2  256.69  4730.4   249.4  4981.7  239.39  4987.3  236.73
  5001.1  234.22  5003.8  233.72  5007.1  234.22  5009.7  235.98    5032  240.71
  5085.1  241.36  5219.3  238.43  5361.7  239.19  5526.5  241.85  5563.7  242.26
  5635.8     244  5652.5  242.25  5666.5  243.95    5738  243.32  5747.6  244.35
  5778.3  242.74  5814.7  243.62  5831.4  242.52  5971.2   246.6    5988  245.67
    6055  249.64    6083  248.85  6136.1  252.19  6158.5  251.79    6315  257.44
#Mann= 9 ,-1 , 0
  4501.6      .1       0  4549.2     .08       0  4730.4      .1       0
  5001.1     .07       0  5007.1      .1       0  5361.7     .05       0
  5526.5      .1       0  5563.7     .08       0    5738      .1       0
Bank Sta=5001.1,5007.1
XS Rating Curve= 0 ,0
Exp/Cntr=0.3,0.1

Type RM Length L Ch R = 1 ,7515    ,433,433,433
BEGIN DESCRIPTION:
UNT008 IN NURI 13.0
END DESCRIPTION:
XS GIS Cut Line= 3
      2289137.72     13337646.86      2288337.72     13337896.85
      2287537.69     13338596.88
#Sta/Elev= 30
  4140.4  263.05  4349.9  256.37  4370.9  254.79  4394.5  254.98  4452.9   252.9
  4664.8  245.11  4924.6     239  4962.3  236.72  5011.1  235.82  5013.9  235.32
  5017.1  235.82  5020.8  236.79  5063.5  237.86  5163.2  237.18  5226.7  238.12
  5247.6  237.07  5395.3  238.59  5523.8  240.67  5552.3  242.96  5588.4   240.7
  5649.4  242.01  5687.1  242.12  5772.5  246.18  5786.7  245.12    5857  249.02
  5878.8  248.52  5942.4  252.32  5959.8  251.28  6031.2  254.79  6041.6  255.29
#Mann= 8 ,-1 , 0
  4140.4      .1       0  4452.9     .05       0  5011.1     .03       0
  5017.1     .05       0  5395.3     .08       0  5649.4      .1       0
  5959.8     .08       0  6031.2      .1       0
Bank Sta=5011.1,5017.1
XS Rating Curve= 0 ,0
Exp/Cntr=0.3,0.1

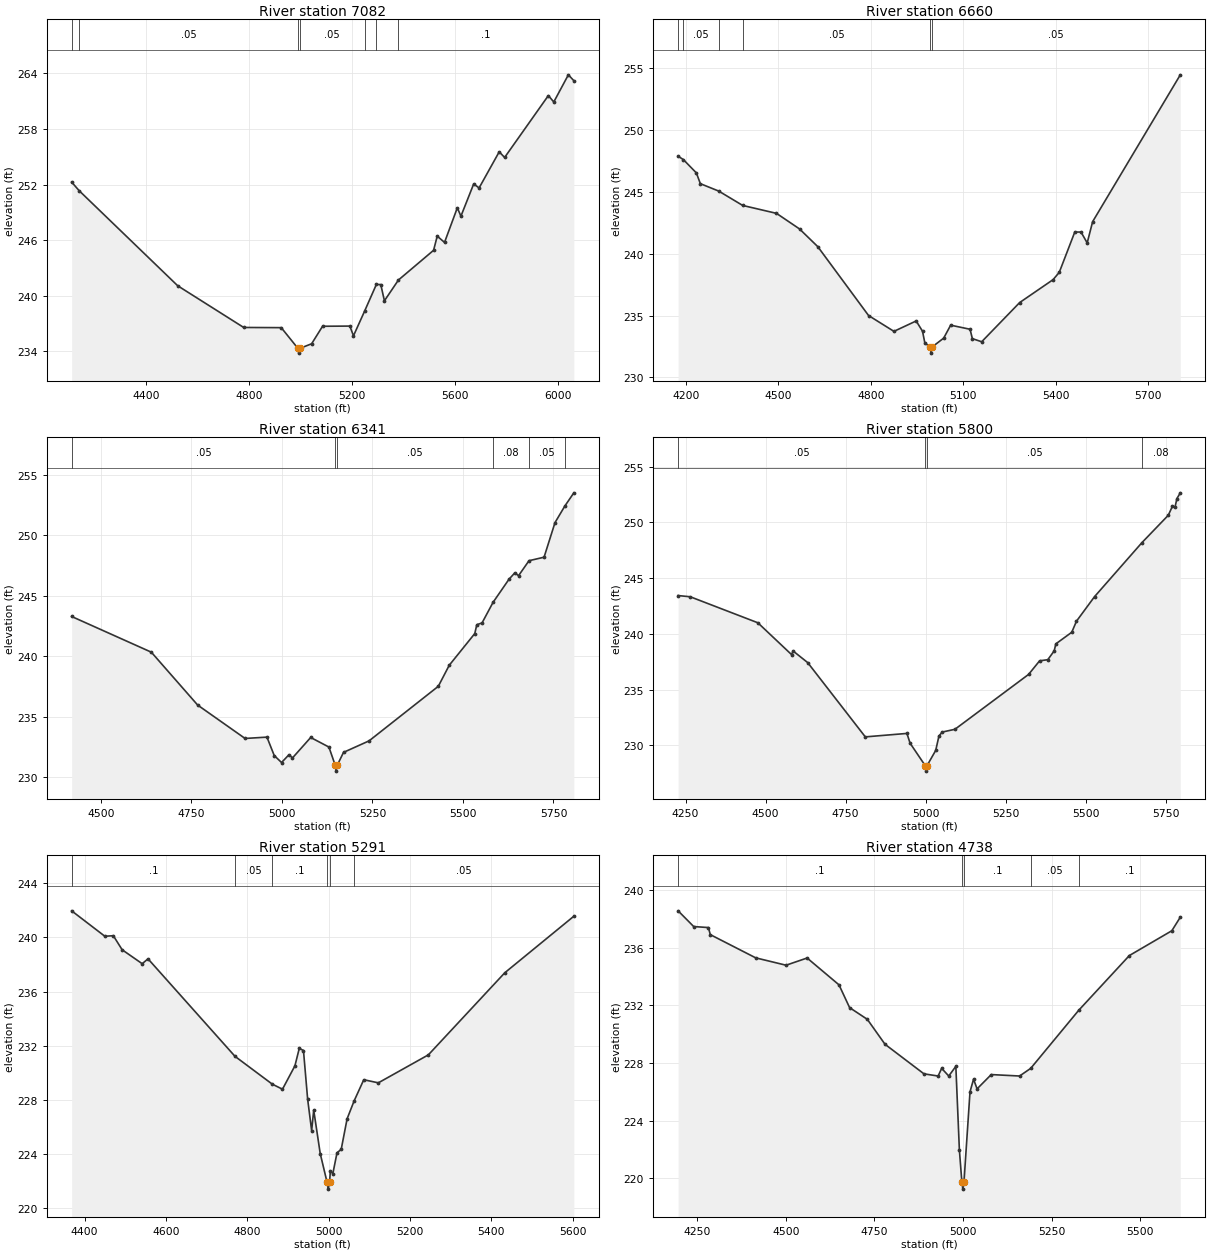
Type RM Length L Ch R = 1 ,7082    ,422,422,422
BEGIN DESCRIPTION:
UNT008 IN NURI 12.0
END DESCRIPTION:
XS GIS Cut Line= 3
      2288737.71     13337496.86      2287937.72     13337796.85
       2287187.7     13338596.88
#Sta/Elev= 30
  4111.8  252.27  4141.1  251.34  4523.9  241.08  4780.2  236.58  4926.1  236.56
  4991.3  234.31    4994  233.81  4997.3  234.31  5044.1  234.82  5086.6  236.71
  5192.6  236.73  5206.7  235.68  5249.7  238.33  5295.6  241.22  5312.8  241.21
  5326.9  239.46  5381.3   241.7  5517.9  244.91  5532.1  246.44  5560.4  245.76
  5610.2   249.5  5624.1  248.59  5673.7  252.07  5694.7  251.64  5772.9  255.54
  5793.9  254.93  5963.8  261.61  5984.9  260.92  6041.5  263.85  6062.8  263.22
#Mann= 7 ,-1 , 0
  4111.8      .1       0  4141.1     .05       0  4991.3     .03       0
  4997.3     .05       0  5249.7     .08       0  5295.6     .05       0
  5381.3      .1       0
Bank Sta=4991.3,4997.3
XS Rating Curve= 0 ,0
Exp/Cntr=0.3,0.1

Type RM Length L Ch R = 1 ,6660    ,319,319,319
BEGIN DESCRIPTION:
UNT008 IN NURI 11.0
END DESCRIPTION:
XS GIS Cut Line= 3
      2288537.73     13337246.85      2287737.72     13337446.85
      2286937.67     13337546.86
#Sta/Elev= 30
  4174.2  247.88  4191.1  247.61  4233.5  246.53  4246.4  245.66  4306.2  245.06
  4383.9   243.9  4493.7  243.26  4568.5     242  4627.7  240.57  4792.7     235
  4875.1  233.72  4947.3  234.56  4967.9  233.73  4975.6  232.77  4993.2  232.46
    4996  231.96  4999.2  232.46  5036.6  233.17  5059.3  234.22  5122.3  233.89
  5129.8  233.13  5160.1  232.88  5283.5  236.05  5391.9   237.9    5412  238.49
  5462.4  241.75  5482.6  241.75  5502.7  240.87  5520.4  242.59  5805.1  254.46
#Mann= 6 ,-1 , 0
  4174.2      .1       0  4191.1     .05       0  4306.2      .1       0
  4383.9     .05       0  4993.2     .03       0  4999.2     .05       0
Bank Sta=4993.2,4999.2
XS Rating Curve= 0 ,0
Exp/Cntr=0.3,0.1

Type RM Length L Ch R = 1 ,6341    ,541,541,541
BEGIN DESCRIPTION:
UNT008 IN NURI 10.0
END DESCRIPTION:
XS GIS Cut Line= 3
      2288293.23     13337178.26      2288054.49      13337102.3
      2286926.01     13337232.51
#Sta/Elev= 30
  4419.7  243.27  4639.7  240.32  4767.6  235.95  4898.5  233.19  4958.9   233.3
    4979  231.78  4999.2   231.2  5019.8  231.85  5029.4  231.58  5079.7  233.27
    5130  232.48  5147.2  230.99  5149.9  230.49  5153.2  230.99  5170.3  232.04
  5240.8  232.99    5432   237.5  5462.2  239.24  5532.7  241.86  5538.3  242.59
  5552.8  242.74  5583.2  244.44  5627.2  246.35  5643.4  246.88  5653.5  246.64
  5682.4  247.88    5724  248.17  5754.2  251.03  5781.6  252.41  5806.2  253.49
#Mann= 6 ,-1 , 0
  4419.7     .05       0  5147.2     .03       0  5153.2     .05       0
  5583.2     .08       0  5682.4     .05       0  5781.6      .1       0
Bank Sta=5147.2,5153.2
XS Rating Curve= 0 ,0
Exp/Cntr=0.3,0.1

Type RM Length L Ch R = 1 ,5800    ,509,509,509
BEGIN DESCRIPTION:
UNT008 IN NURI 9.0
END DESCRIPTION:
XS GIS Cut Line= 4
      2288282.35     13336852.73      2287967.69     13336711.67
      2287132.18     13336722.52      2286817.53     13336950.38
#Sta/Elev= 30
  4226.8  243.44  4264.8  243.33  4475.9     241  4581.1  238.15  4586.1  238.47
  4631.6  237.43  4811.6  230.77  4941.6  231.08  4951.6   230.2  4998.6   228.2
  5001.4   227.7  5004.6   228.2  5031.6  229.56  5041.6  230.84  5051.6   231.2
  5091.6  231.45  5321.7  236.37  5356.2  237.59  5381.7  237.69  5401.7  238.48
  5406.9  239.11  5456.6  240.15  5471.3  241.14  5527.7  243.34    5676  248.19
  5758.2  250.64  5770.8  251.43  5779.1  251.36  5785.2  252.14  5795.7  252.65
#Mann= 4 ,-1 , 0
  4226.8     .05       0  4998.6    .035       0  5004.6     .05       0
    5676     .08       0
Bank Sta=4998.6,5004.6
XS Rating Curve= 0 ,0
Exp/Cntr=0.3,0.1

Type RM Length L Ch R = 1 ,5291    ,553,553,553
BEGIN DESCRIPTION:
UNT008 IN NURI 8.0
END DESCRIPTION:
XS GIS Cut Line= 3
      2288282.36     13336527.21      2288087.04      13336353.6
      2287143.08      13336114.9
#Sta/Elev= 30
    4368  241.97  4449.6  240.09  4470.5  240.13  4492.2  239.09  4541.5  238.06
  4555.8  238.42  4769.7  231.21  4861.5  229.15  4886.5  228.78  4917.1  230.51
  4927.8   231.8  4938.1  231.64  4948.4  228.03  4958.2  225.72  4963.3  227.23
  4979.3  224.02  4996.2  221.89  4998.9  221.39  5002.2  221.89  5004.3  222.75
  5010.3  222.53  5020.6  224.08  5030.9  224.33  5045.4  226.59  5062.6  227.91
  5086.4  229.48  5122.2  229.25  5245.3  231.32  5433.2  237.39    5603  241.57
#Mann= 6 ,-1 , 0
    4368      .1       0  4769.7     .05       0  4861.5      .1       0
  4996.2     .07       0  5002.2      .1       0  5062.6     .05       0
Bank Sta=4996.2,5002.2
XS Rating Curve= 0 ,0
Exp/Cntr=0.3,0.1

Type RM Length L Ch R = 1 ,4738    ,939,939,939
BEGIN DESCRIPTION:
UNT008 IN NURI 7.0
END DESCRIPTION:
XS GIS Cut Line= 3
       2288358.3     13336136.57      2288217.25     13335811.07
      2287153.86     13335821.92
#Sta/Elev= 30
  4195.5  238.55  4239.5  237.46    4281  237.39  4286.4   236.9  4414.7  235.29
  4500.3  234.78  4559.8  235.28  4649.8  233.42  4679.8  231.84  4729.8  231.03
  4779.8   229.3  4889.8  227.25  4929.8   227.1  4939.8  227.63  4959.8   227.1
  4979.8  227.77  4989.8  221.98  4996.8  219.76  4999.6  219.26  5002.8  219.76
  5019.8     226  5029.8  226.88  5039.8  226.21  5079.8   227.2  5159.8   227.1
  5191.2  227.63  5326.6  231.65  5469.8  235.45  5589.8  237.17  5613.7  238.11
#Mann= 5 ,-1 , 0
  4195.5      .1       0  4996.8     .07       0  5002.8      .1       0
  5191.2     .05       0  5326.6      .1       0
Bank Sta=4996.8,5002.8
XS Rating Curve= 0 ,0
Exp/Cntr=0.3,0.1

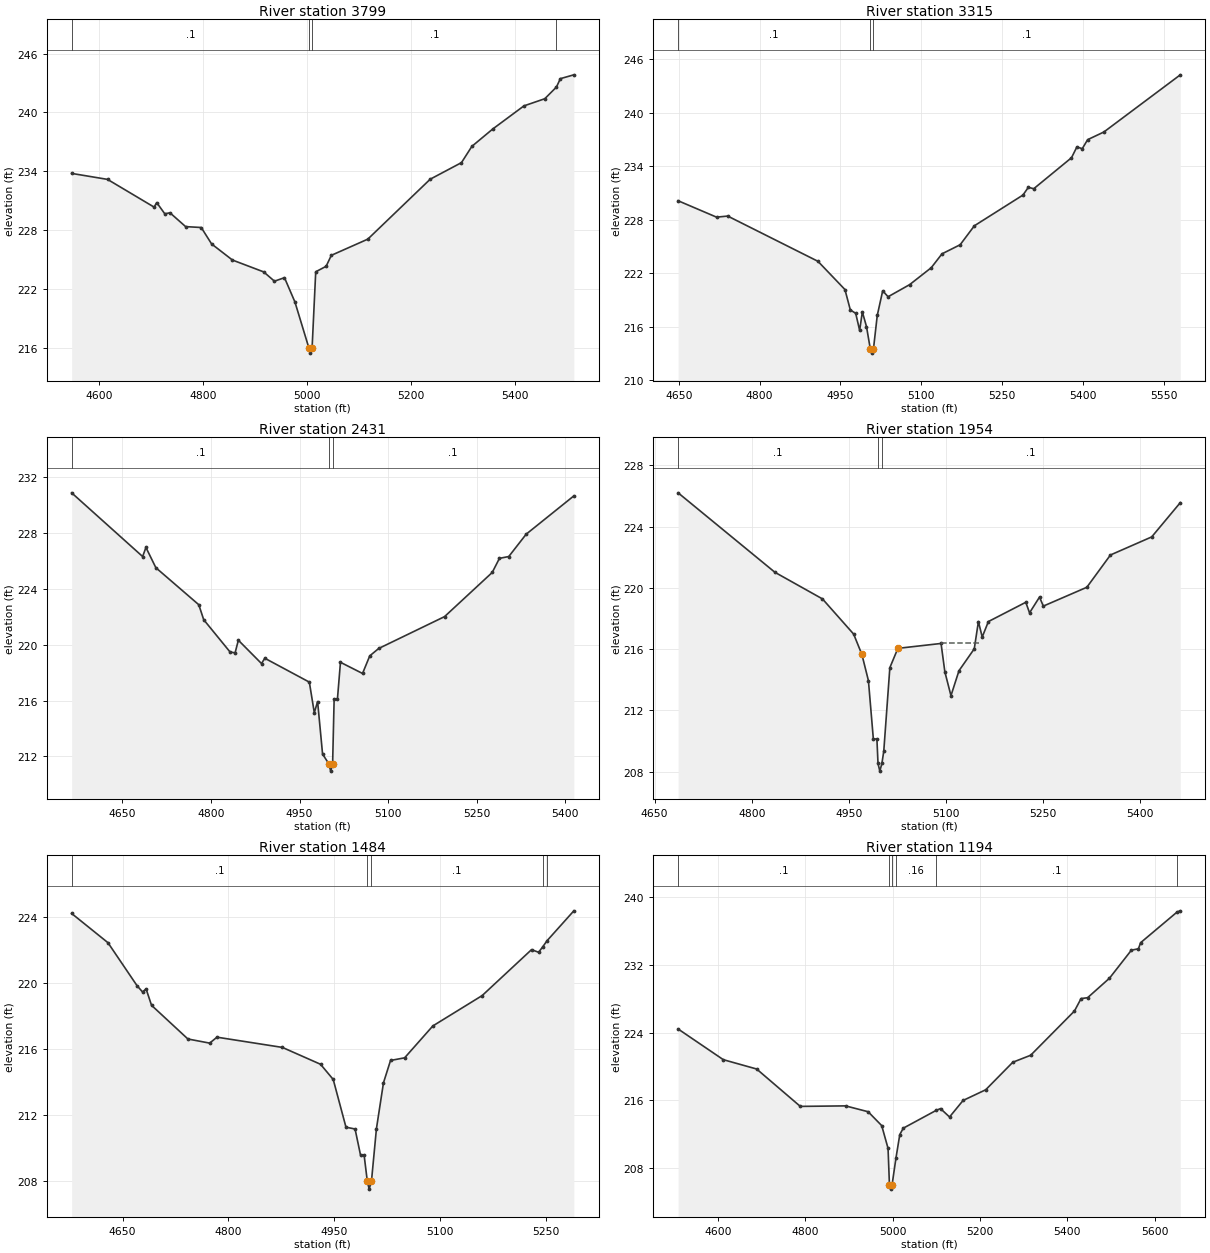
Type RM Length L Ch R = 1 ,3799    ,484,484,484
BEGIN DESCRIPTION:
UNT008 IN NURI 6.0
END DESCRIPTION:
XS GIS Cut Line= 2
      2287826.66     13335149.17      2286861.83     13335105.81
#Sta/Elev= 30
  4547.7  233.77  4616.7  233.16  4706.3  230.33  4711.3  230.79  4726.8  229.65
  4736.8  229.75  4766.9  228.34  4796.9  228.25  4816.9  226.57  4856.9  224.93
    4917  223.72  4937.7  222.77    4957  223.13  4977.1  220.65  5004.1  215.93
  5006.8  215.43  5010.1  215.93  5017.1  223.73  5037.1  224.29  5047.1  225.41
  5117.2  227.06  5237.3  233.18  5297.4  234.87  5317.4  236.53  5357.5   238.3
  5417.5  240.66  5457.6  241.39    5480  242.58  5487.6  243.44  5513.5  243.83
#Mann= 4 ,-1 , 0
  4547.7      .1       0  5004.1     .07       0  5010.1      .1       0
    5480     .05       0
Bank Sta=5004.1,5010.1
XS Rating Curve= 0 ,0
Exp/Cntr=0.3,0.1

Type RM Length L Ch R = 1 ,3315    ,884,884,884
BEGIN DESCRIPTION:
UNT008 IN NURI 5.0
END DESCRIPTION:
XS GIS Cut Line= 3
      2287826.66     13334747.73      2287718.12     13334660.89
      2286926.01      13334704.3
#Sta/Elev= 30
  4648.9  230.12  4720.2  228.28    4741   228.4  4908.5  223.32  4958.6  220.15
  4968.6  217.86  4978.6  217.48  4985.9  215.56  4990.9  217.64  4998.6     216
  5005.6  213.51  5008.4  213.01  5011.6  213.51  5018.6  217.24  5028.7  220.01
  5038.7  219.34  5078.7   220.7  5118.8   222.6  5138.8  224.16  5172.5  225.18
  5198.9  227.31  5289.1  230.76  5299.1  231.63  5309.1  231.47  5379.2  234.95
  5389.2  236.16  5399.2  235.97  5409.2  236.98  5439.3  237.84  5581.2  244.26
#Mann= 3 ,-1 , 0
  4648.9      .1       0  5005.6     .07       0  5011.6      .1       0
Bank Sta=5005.6,5011.6
XS Rating Curve= 0 ,0
Exp/Cntr=0.3,0.1

Type RM Length L Ch R = 1 ,2431    ,477,477,477
BEGIN DESCRIPTION:
UNT008 IN NURI 4.0
END DESCRIPTION:
XS GIS Cut Line= 3
      2287737.76     13333646.84      2287337.72     13333846.85
      2286987.69     13334046.87
#Sta/Elev= 30
    4564  230.87  4684.2  226.31  4689.8  226.96  4706.6  225.51  4779.3  222.86
  4787.6  221.79  4832.4  219.47  4840.8  219.42  4846.3  220.32  4885.5  218.65
  4891.1  219.03  4966.5  217.32  4974.9  215.13  4980.5  215.93  4988.9  212.17
  4999.9  211.45  5002.6  210.95  5005.9  211.45  5008.5  216.12  5014.1  216.12
  5019.2  218.74  5056.6  217.94  5068.8   219.2    5084  219.73  5195.5  222.01
  5276.2  225.17  5288.4  226.18  5304.2  226.31  5333.7  227.91  5414.4  230.65
#Mann= 3 ,-1 , 0
    4564      .1       0  4999.9     .07       0  5005.9      .1       0
Bank Sta=4999.9,5005.9
XS Rating Curve= 0 ,0
Exp/Cntr=0.3,0.1

Type RM Length L Ch R = 1 ,1954    ,470,470,470
BEGIN DESCRIPTION:
UNT008 IN NURI 3.0
END DESCRIPTION:
XS GIS Cut Line= 3
      2287687.73     13333346.85      2287387.72     13333396.85
      2286987.76     13333146.88
#Sta/Elev= 30
  4686.2  226.21  4835.7  221.02  4909.2  219.28  4957.4  216.98  4970.1  215.65
  4980.2  213.94  4987.8  210.13  4993.3  210.13    4995  208.53  4997.8  208.03
    5001  208.53  5003.9  209.33  5013.3  214.79  5025.7  216.05  5092.4  216.37
  5098.3  214.51  5107.7  212.96  5120.1  214.59  5143.7  216.02  5150.1   217.8
    5156  216.79  5165.5   217.8  5223.3  219.06  5229.1  218.37  5244.5   219.4
  5250.4  218.81  5317.6  220.04  5354.1  222.15  5417.8  223.33    5462  225.57
#Mann= 3 ,-1 , 0
  4686.2      .1       0    4995     .07       0    5001      .1       0
#XS Ineff= 1 ,-1
 5092.19 5150.78  216.39
Permanent Ineff=
       F
Bank Sta=4970.1,5025.7
XS Rating Curve= 0 ,0
Exp/Cntr=0.3,0.1

Type RM Length L Ch R = 1 ,1484    ,290,290,290
BEGIN DESCRIPTION:
UNT008 IN NURI 2.0
END DESCRIPTION:
XS GIS Cut Line= 3
      2287737.68     13333046.85      2287337.72     13332946.85
      2287037.69     13332946.85
#Sta/Elev= 30
  4577.8  224.21  4629.3  222.44  4670.5  219.84  4678.3  219.46  4683.4  219.64
  4691.1  218.65  4742.7  216.61  4773.6  216.36  4783.9  216.72  4876.7   216.1
  4930.8  215.08  4948.8  214.16  4966.9  211.27  4979.8  211.16  4987.5  209.59
  4992.6  209.59  4997.1  208.02  4999.8  207.52  5003.1  208.02  5010.1  211.18
  5020.1  213.96  5030.1  215.31  5050.1  215.47  5090.1   217.4  5160.1  219.24
  5230.1  222.02  5240.1  221.86  5245.8  222.18  5252.1  222.56  5290.1  224.37
#Mann= 5 ,-1 , 0
  4577.8      .1       0  4997.1     .07       0  5003.1      .1       0
  5245.8     .16       0  5252.1      .1       0
Bank Sta=4997.1,5003.1
XS Rating Curve= 0 ,0
Exp/Cntr=0.3,0.1

Type RM Length L Ch R = 1 ,1194    ,403,403,403
BEGIN DESCRIPTION:
Mapping XS d88cfcda
END DESCRIPTION:
XS GIS Cut Line= 4
      2287795.14     13332929.32      2287713.24     13332756.44
      2287135.42     13332601.75      2286776.03     13332629.04
#Sta/Elev= 30
  4508.6  224.42  4612.1   220.8  4688.4   219.7  4788.4  215.29    4892  215.35
  4943.7  214.66  4974.8  213.02  4989.3  210.34  4992.5  206.03  4995.2  205.53
  4998.5  206.03  5007.4  209.19  5016.2  211.97  5024.2  212.72  5099.5  214.82
  5109.4  215.03  5130.1  214.04  5161.1  215.99  5212.9  217.25    5275   220.5
  5315.8  221.32  5416.1  226.54  5431.3  228.01  5446.2  228.11  5496.3  230.41
  5546.5  233.72  5562.6  233.88  5567.6   234.6  5651.4  238.23  5658.5  238.36
#Mann= 6 ,-1 , 0
  4508.6      .1       0  4992.5     .07       0  4998.5      .1       0
  5007.4     .16       0  5099.5      .1       0  5651.4     .05       0
Bank Sta=4992.5,4998.5
XS Rating Curve= 0 ,0
Exp/Cntr=0.3,0.1

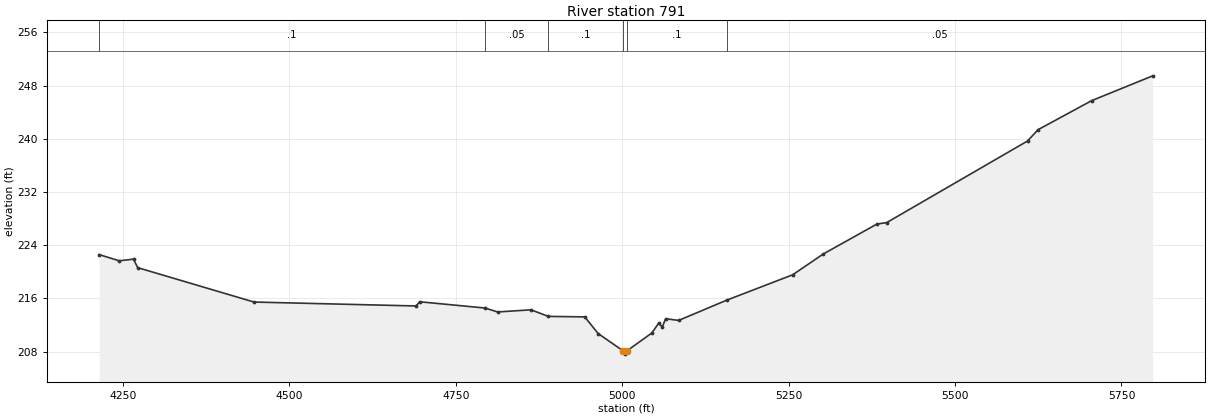
Type RM Length L Ch R = 1 ,791     ,0,0,0
BEGIN DESCRIPTION:
UNT008 IN NURI 1.0
END DESCRIPTION:
XS GIS Cut Line= 3
      2287858.83     13332806.48       2287535.8     13332265.06
      2286591.11     13332383.15
#Sta/Elev= 30
  4214.5  222.59  4244.6  221.66    4266  221.91  4272.3  220.63    4447  215.46
  4690.3  214.87  4696.1   215.5  4794.1  214.56  4812.9  213.97  4863.2  214.29
  4889.2   213.3  4943.8  213.23    4964  210.72  5001.3  208.13    5004  207.63
  5007.3  208.13  5044.6  210.81  5054.7  212.25  5060.3  211.73  5065.4  212.95
  5084.9   212.7    5157  215.74  5256.2  219.56  5302.2  222.69  5382.8  227.19
  5397.3   227.4  5608.9  239.67  5624.7  241.37  5705.3  245.74    5797  249.47
#Mann= 6 ,-1 , 0
  4214.5      .1       0  4794.1     .05       0  4889.2      .1       0
  5001.3     .07       0  5007.3      .1       0    5157     .05       0
Bank Sta=5001.3,5007.3
XS Rating Curve= 0 ,0
Exp/Cntr=0.3,0.1

Chan Stop Cuts=-1
Use User Specified Reach Order=0
Composite Channel Slope=5