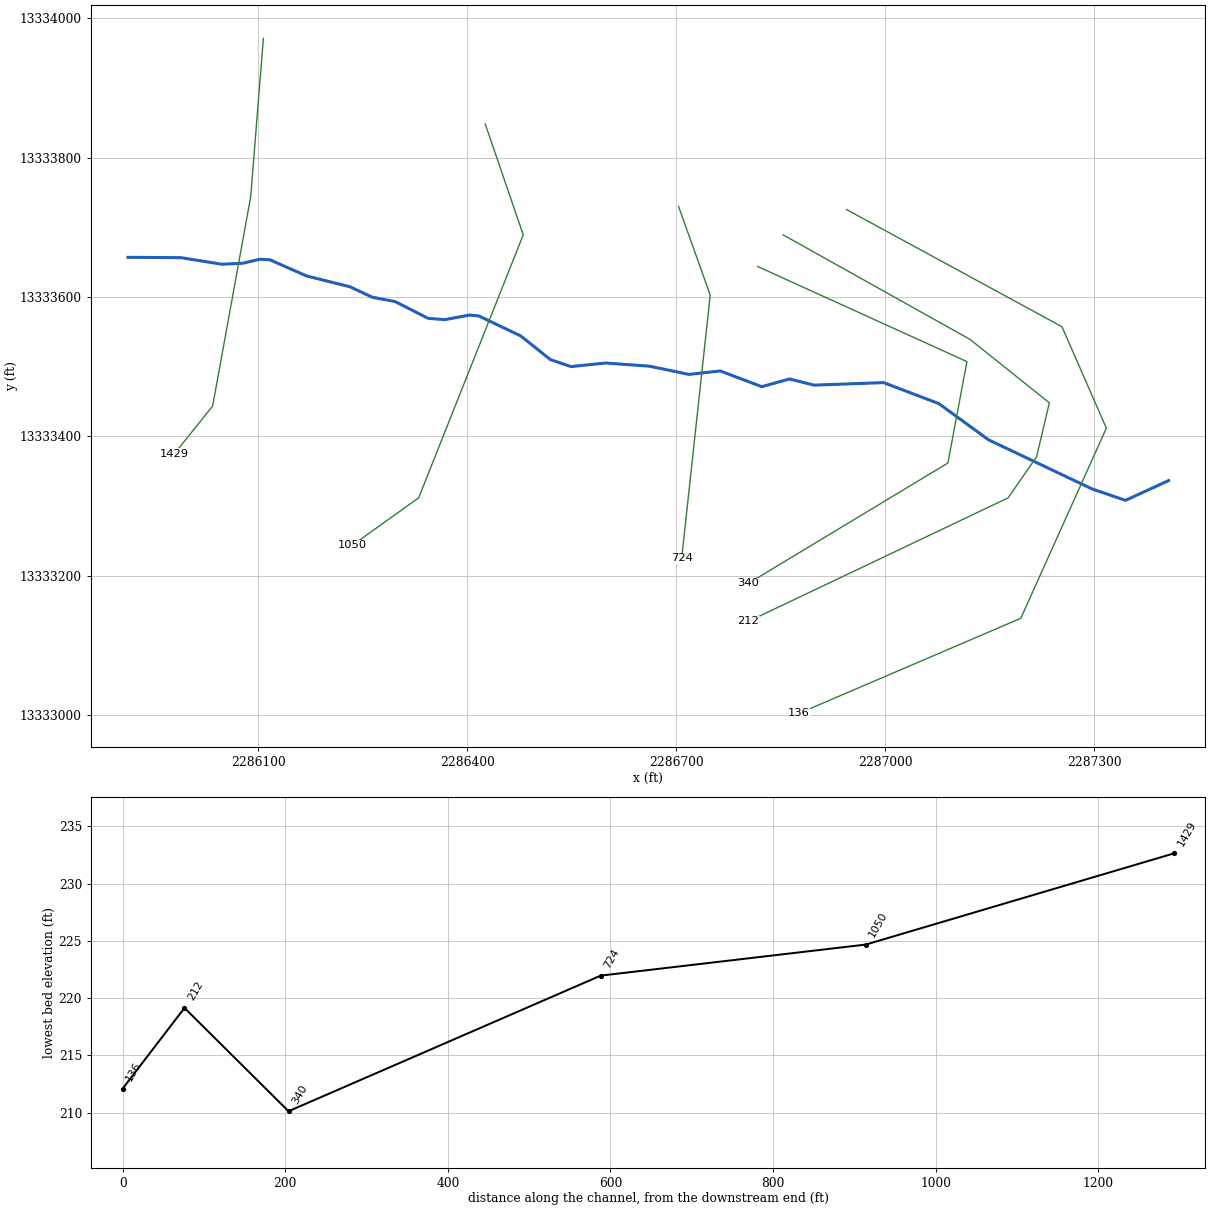
--- UNT009 IN NURI.prj (project) ---

Proj Title=UNT009 IN NURI Base Level Engineering
Current Plan=p01
Default Exp/Contr=0.3,0.1
English Units
Geom File=g01
Flow File=f01
Plan File=p01
BEGIN DESCRIPTION:
UNT009 IN NURI
END DESCRIPTION:

--- UNT009 IN NURI.p01 (plan) ---

Plan Title=Multiple Run
Short Identifier=Multiple
Geom File=g01
Flow File=f01
Subcritical Flow
K Sum by GR= 0
Std Step Tol= 0.01
Critical Tol= 0.01
Num of Std Step Trials= 20
Max Error Tol= 0.3
Flow Tol Ratio= 0.001
Split Flow NTrial= 30
Split Flow Tol= 0.02
Split Flow Ratio= 0.02
Log Output Level= 0
Friction Slope Method= 1
Unsteady Friction Slope Method= 2
Unsteady Bridges Friction Slope Method= 1
Parabolic Critical Depth
Global Vel Dist=  1 , 1 , 1
Global Log Level= 0
CheckData=True
Encroach Param= -1, 0, 0, 0
BEGIN DESCRIPTION:
Multiple Run
END DESCRIPTION:

--- UNT009 IN NURI.f01 (steady flow) ---

Flow Title=Multiple
Number of Profiles=7
Profile Names=10-year,25-year,50-year,1pct_min,100-year,1pct_plu,500-year
River Rch & RM= UNT009 IN NURI,Reach-1,1429
      62      79      93      80     108     146     149
Boundary for River Rch & Prof#=UNT009 IN NURI,Reach-1,1
Up Type=0
Dn Type=3
Dn Slope=0.005
Boundary for River Rch & Prof#=UNT009 IN NURI,Reach-1,2
Up Type=0
Dn Type=3
Dn Slope=0.005
Boundary for River Rch & Prof#=UNT009 IN NURI,Reach-1,3
Up Type=0
Dn Type=3
Dn Slope=0.005
Boundary for River Rch & Prof#=UNT009 IN NURI,Reach-1,4
Up Type=0
Dn Type=3
Dn Slope=0.005
Boundary for River Rch & Prof#=UNT009 IN NURI,Reach-1,5
Up Type=0
Dn Type=3
Dn Slope=0.005
Boundary for River Rch & Prof#=UNT009 IN NURI,Reach-1,6
Up Type=0
Dn Type=3
Dn Slope=0.005
Boundary for River Rch & Prof#=UNT009 IN NURI,Reach-1,7
Up Type=0
Dn Type=3
Dn Slope=0.005

--- UNT009 IN NURI.g01 (geometry) ---

Geom Title=Existing Conditions

River Reach=UNT009 IN NURI,Reach-1
Reach XY= 30
      2285912.72     13333656.85      2285988.56     13333656.38
      2286047.84     13333646.93      2286077.25     13333648.33
      2286102.42     13333654.12      2286116.61     13333653.28
      2286169.04     13333630.19      2286231.75     13333614.52
      2286263.32     13333599.63      2286296.29     13333593.34
      2286343.80     13333569.22      2286367.58     13333567.39
      2286403.22     13333573.99      2286416.37     13333572.71
      2286476.56     13333544.10      2286519.18     13333510.06
      2286548.74     13333500.02      2286598.58     13333505.10
      2286661.50     13333500.59      2286718.05     13333488.78
      2286763.09     13333493.71      2286822.75     13333471.16
      2286862.66     13333482.26      2286897.70     13333473.38
      2286997.66     13333476.97      2287076.87     13333446.86
      2287148.48     13333394.77      2287297.14     13333324.24
      2287344.88     13333307.97      2287406.84     13333336.35

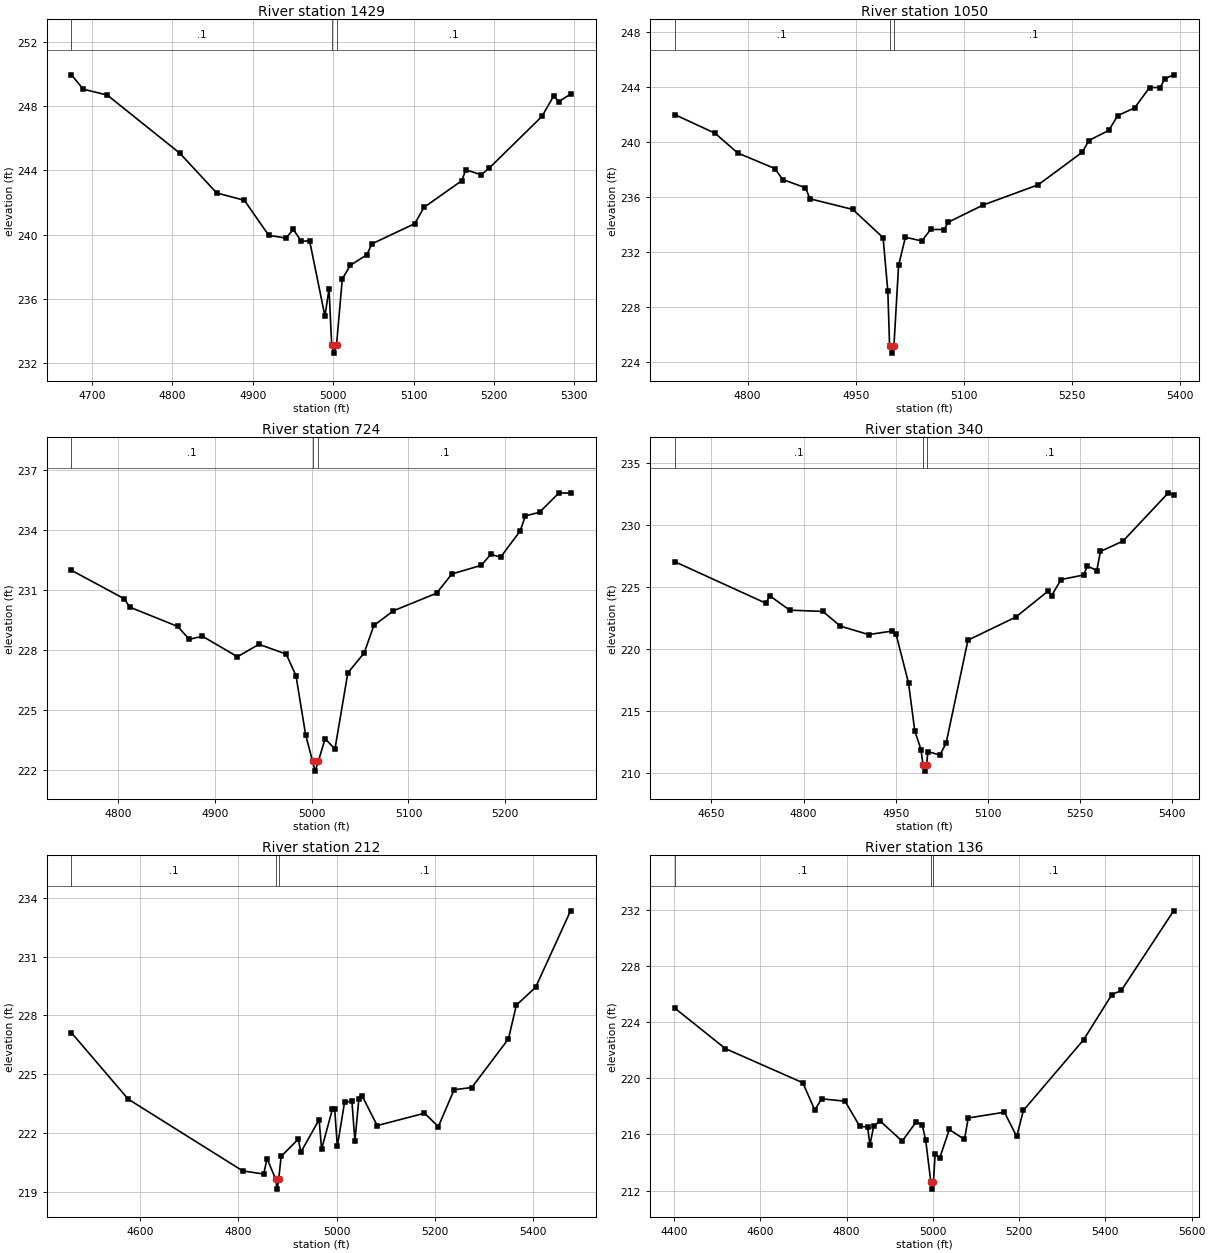
Type RM Length L Ch R = 1,1429,379,379,379
BEGIN DESCRIPTION:
UNT009 IN NURI 3.0
END DESCRIPTION:
XS GIS Cut Line= 4
      2286107.17     13333971.26      2286088.97     13333743.74
      2286034.37     13333443.46      2285979.75     13333375.17
#Sta/Elev= 30
  4674.5  249.95  4689.0  249.06  4719.0  248.69  4809.3  245.07  4855.1  242.60
  4889.6  242.14  4919.9  239.96  4941.5  239.79  4950.4  240.33  4960.6  239.58
  4970.7  239.63  4989.8  234.93  4994.9  236.63  4998.2  233.13  5001.0  232.63
  5004.2  233.13  5011.4  237.25  5021.5  238.10  5041.9  238.75  5048.2  239.43
  5101.6  240.69  5113.0  241.70  5160.0  243.36  5165.1  244.04  5184.2  243.73
  5194.3  244.15  5259.9  247.37  5274.3  248.63  5280.7  248.28  5295.4  248.75
#Mann=3,-1,0
  4674.5     0.1       0  4998.2    0.07       0  5004.2     0.1       0
Bank Sta=4998.2,5004.2
Exp/Cntr=0.3,0.1

Type RM Length L Ch R = 1,1050,326,326,326
BEGIN DESCRIPTION:
UNT009 IN NURI 2.0
END DESCRIPTION:
XS GIS Cut Line= 4
      2286425.66     13333848.38      2286480.25     13333689.14
      2286330.11     13333311.51      2286234.59     13333243.29
#Sta/Elev= 30
  4698.8  241.99  4755.0  240.63  4786.3  239.20  4837.8  238.07  4848.8  237.27
  4880.4  236.67  4886.6  235.87  4946.0  235.10  4988.0  233.05  4994.6  229.15
  4997.0  225.17  4999.7  224.67  5003.0  225.17  5009.5  231.04  5018.9  233.08
  5041.8  232.81  5053.9  233.65  5072.8  233.64  5078.2  234.17  5126.8  235.42
  5203.2  236.89  5264.4  239.26  5273.3  240.10  5301.0  240.84  5313.4  241.91
  5336.8  242.47  5357.6  243.95  5372.4  243.95  5378.5  244.58  5390.9  244.87
#Mann=3,-1,0
  4698.8     0.1       0  4997.0    0.07       0  5003.0     0.1       0
Bank Sta=4997,5003
Exp/Cntr=0.3,0.1

Type RM Length L Ch R = 1,724,384,384,384
BEGIN DESCRIPTION:
Mapping XS 432fb7db
END DESCRIPTION:
XS GIS Cut Line= 3
      2286703.20     13333730.07      2286748.69     13333602.70
      2286707.74     13333225.06
#Sta/Elev= 30
  4752.2  231.98  4806.8  230.56  4812.1  230.15  4861.8  229.18  4873.7  228.54
  4887.4  228.69  4923.5  227.67  4945.7  228.29  4973.8  227.80  4983.9  226.72
  4993.9  223.76  5001.0  222.46  5003.7  221.96  5007.0  222.46  5014.0  223.58
  5024.1  223.06  5037.4  226.86  5054.3  227.86  5064.3  229.23  5084.4  229.96
  5129.0  230.84  5144.8  231.80  5175.0  232.23  5185.0  232.78  5195.1  232.64
  5215.2  233.94  5220.7  234.70  5235.3  234.88  5255.4  235.85  5267.3  235.83
#Mann=3,-1,0
  4752.2     0.1       0  5001.0    0.07       0  5007.0     0.1       0
Bank Sta=5001,5007
Exp/Cntr=0.3,0.1

Type RM Length L Ch R = 1,340,128,128,128
BEGIN DESCRIPTION:
Mapping XS 15a3283c
END DESCRIPTION:
XS GIS Cut Line= 4
      2286816.95     13333643.64      2287117.22     13333507.15
      2287089.92     13333361.56      2286803.30     13333188.67
#Sta/Elev= 30
  4589.9  227.03  4739.1  223.66  4744.6  224.28  4777.5  223.11  4831.4  223.01
  4860.0  221.82  4906.1  221.14  4944.8  221.43  4950.6  221.18  4970.9  217.23
  4981.1  213.37  4991.3  211.85  4994.4  210.62  4997.1  210.12  5000.4  210.62
  5002.5  211.70  5021.8  211.42  5032.0  212.35  5067.7  220.69  5145.5  222.55
  5197.9  224.64  5203.8  224.27  5219.3  225.58  5256.2  225.95  5262.0  226.68
  5277.5  226.31  5283.4  227.85  5320.3  228.69  5394.0  232.58  5402.6  232.44
#Mann=3,-1,0
  4589.9     0.1       0  4994.4    0.07       0  5000.4     0.1       0
Bank Sta=4994.4,5000.4
Exp/Cntr=0.3,0.1

Type RM Length L Ch R = 1,212,76,76,76
BEGIN DESCRIPTION:
Mapping XS fdc55d38
END DESCRIPTION:
XS GIS Cut Line= 6
      2286853.35     13333689.13      2287121.77     13333539.00
      2287235.52     13333448.01      2287217.32     13333370.66
      2287176.37     13333311.51      2286803.33     13333134.09
#Sta/Elev= 30
  4459.5  227.11  4575.1  223.73  4808.6  220.07  4851.5  219.91  4858.2  220.70
  4876.0  219.64  4878.8  219.14  4882.0  219.64  4887.0  220.81  4922.0  221.69
  4927.1  221.02  4964.4  222.68  4969.5  221.18  4991.6  223.22  4996.2  223.22
  5001.6  221.32  5016.4  223.58  5031.3  223.62  5037.4  221.59  5045.5  223.75
  5052.2  223.89  5082.9  222.38  5179.3  223.01  5207.6  222.33  5239.8  224.21
  5275.7  224.32  5350.5  226.80  5366.6  228.52  5405.9  229.43  5477.2  233.33
#Mann=3,-1,0
  4459.5     0.1       0  4876.0    0.07       0  4882.0     0.1       0
Bank Sta=4876,4882
Exp/Cntr=0.3,0.1

Type RM Length L Ch R = 1,136,0,0,0
BEGIN DESCRIPTION:
UNT009 IN NURI 1.0
END DESCRIPTION:
XS GIS Cut Line= 5
      2286944.31     13333725.55      2287253.71     13333557.20
      2287317.41     13333411.61      2287194.57     13333138.62
      2286876.10     13333002.13
#Sta/Elev= 30
  4401.2  225.01  4519.1  222.11  4698.6  219.68  4726.2  217.74  4742.3  218.53
  4796.4  218.37  4830.7  216.57  4848.7  216.53  4854.1  215.26  4863.0  216.59
  4877.5  216.96  4928.9  215.52  4961.4  216.89  4975.2  216.70  4983.4  215.59
  4995.4  212.60  4998.1  212.10  5001.4  212.60  5005.3  214.59  5016.0  214.32
  5038.2  216.35  5073.3  215.64  5082.1  217.17  5165.9  217.58  5194.5  215.85
  5209.9  217.71  5349.7  222.75  5415.0  225.96  5437.1  226.26  5558.2  231.93
#Mann=3,-1,0
  4401.2     0.1       0  4995.4    0.07       0  5001.4     0.1       0
Bank Sta=4995.4,5001.4
Exp/Cntr=0.3,0.1

Chan Stop Cuts=-1