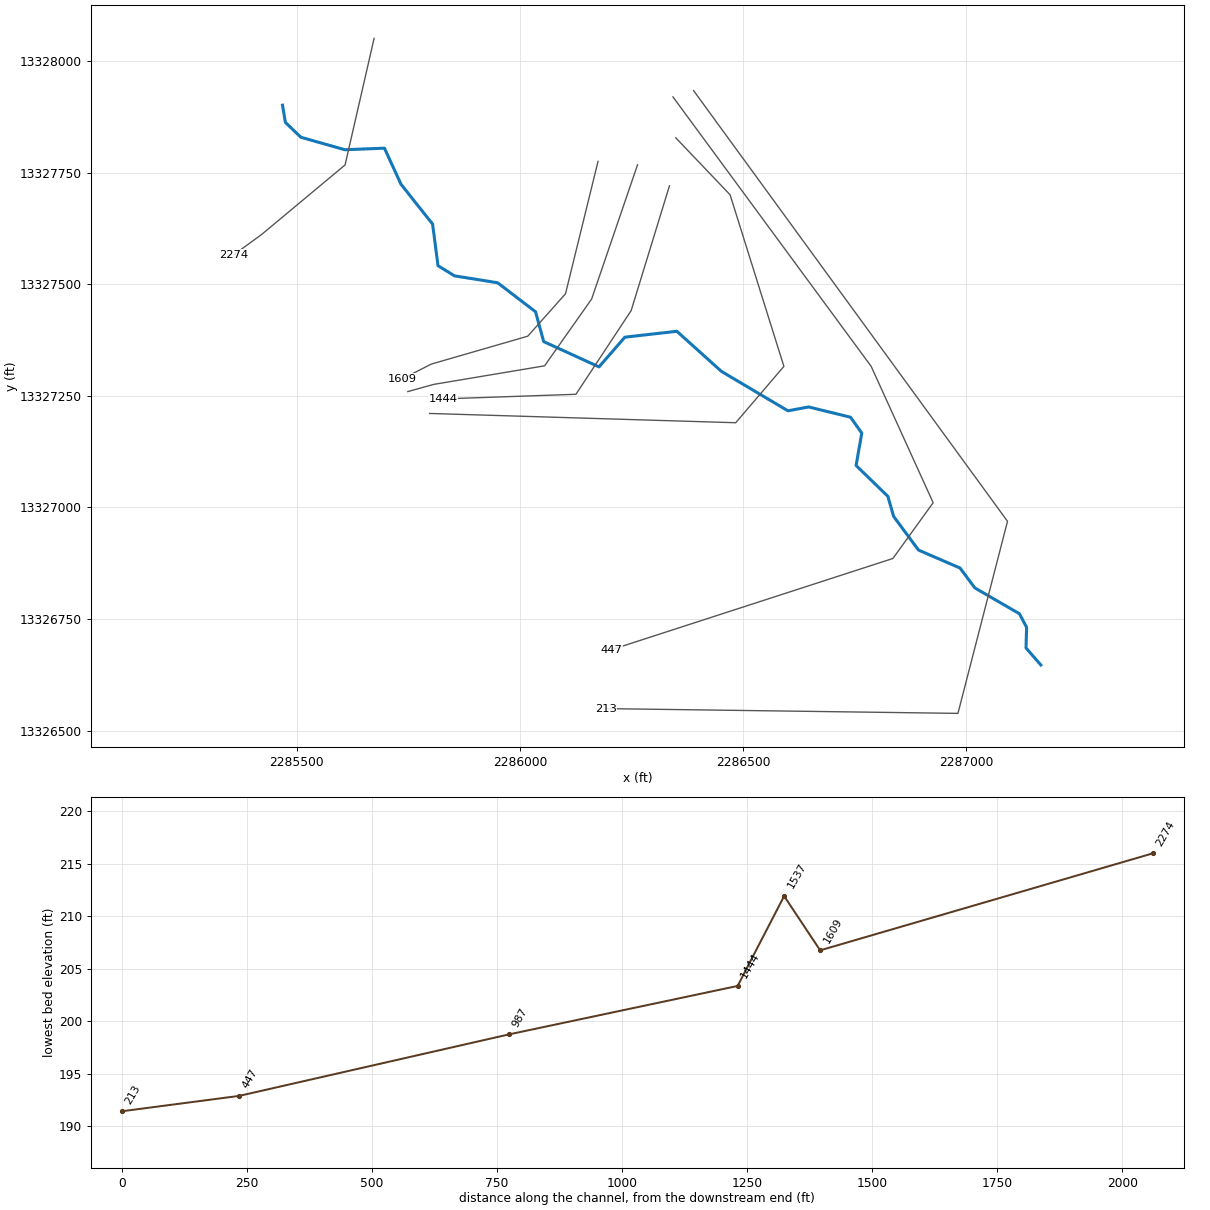
--- UNT010 IN NURI.prj (project) ---

Proj Title=UNT010 IN NURI Base Level Engineering
Current Plan=p01
Default Exp/Contr=0.3,0.1
English Units
Geom File=g01
Flow File=f01
Plan File=p01
BEGIN DESCRIPTION:
UNT010 IN NURI
END DESCRIPTION:

--- UNT010 IN NURI.p01 (plan) ---

Plan Title=Multiple Run
Short Identifier=Multiple
Geom File=g01
Flow File=f01
Subcritical Flow
K Sum by GR= 0
Std Step Tol= 0.01
Critical Tol= 0.01
Num of Std Step Trials= 20
Max Error Tol= 0.3
Flow Tol Ratio= 0.001
Split Flow NTrial= 30
Split Flow Tol= 0.02
Split Flow Ratio= 0.02
Log Output Level= 0
Friction Slope Method= 1
Unsteady Friction Slope Method= 2
Unsteady Bridges Friction Slope Method= 1
Parabolic Critical Depth
Global Vel Dist=  1 , 1 , 1
Global Log Level= 0
CheckData=True
Encroach Param= -1, 0, 0, 0
BEGIN DESCRIPTION:
Multiple Run
END DESCRIPTION:

--- UNT010 IN NURI.f01 (steady flow) ---

Flow Title=Multiple
Number of Profiles=7
Profile Names=10-year,25-year,50-year,1pct_min,100-year,1pct_plu,500-year
River Rch & RM= UNT010 IN NURI,Reach-1,2274
      42      51      57      48      64      87      83
Boundary for River Rch & Prof#=UNT010 IN NURI,Reach-1,1
Up Type=0
Dn Type=3
Dn Slope=0.005
Boundary for River Rch & Prof#=UNT010 IN NURI,Reach-1,2
Up Type=0
Dn Type=3
Dn Slope=0.005
Boundary for River Rch & Prof#=UNT010 IN NURI,Reach-1,3
Up Type=0
Dn Type=3
Dn Slope=0.005
Boundary for River Rch & Prof#=UNT010 IN NURI,Reach-1,4
Up Type=0
Dn Type=3
Dn Slope=0.005
Boundary for River Rch & Prof#=UNT010 IN NURI,Reach-1,5
Up Type=0
Dn Type=3
Dn Slope=0.005
Boundary for River Rch & Prof#=UNT010 IN NURI,Reach-1,6
Up Type=0
Dn Type=3
Dn Slope=0.005
Boundary for River Rch & Prof#=UNT010 IN NURI,Reach-1,7
Up Type=0
Dn Type=3
Dn Slope=0.005

--- UNT010 IN NURI.g01 (geometry) ---

Geom Title=Existing Conditions

River Reach=UNT010 IN NURI,Reach-1
Reach XY= 30
      2285467.72     13327901.85      2285474.24     13327863.09
      2285508.78     13327829.99      2285607.48     13327801.91
      2285696.24     13327805.44      2285733.35     13327724.52
      2285804.14     13327635.32      2285816.31     13327542.00
      2285853.32     13327519.19      2285949.92     13327503.77
      2286034.98     13327438.67      2286053.21     13327371.83
      2286177.21     13327315.15      2286235.29     13327381.81
      2286351.74     13327394.93      2286451.62     13327305.07
      2286600.73     13327216.68      2286647.16     13327225.34
      2286741.10     13327202.28      2286766.28     13327166.76
      2286753.51     13327094.16      2286824.71     13327024.98
      2286837.66     13326979.94      2286893.41     13326904.52
      2286986.56     13326864.21      2287019.71     13326819.71
      2287119.79     13326761.68      2287135.78     13326731.29
      2287134.47     13326685.09      2287167.72     13326646.86

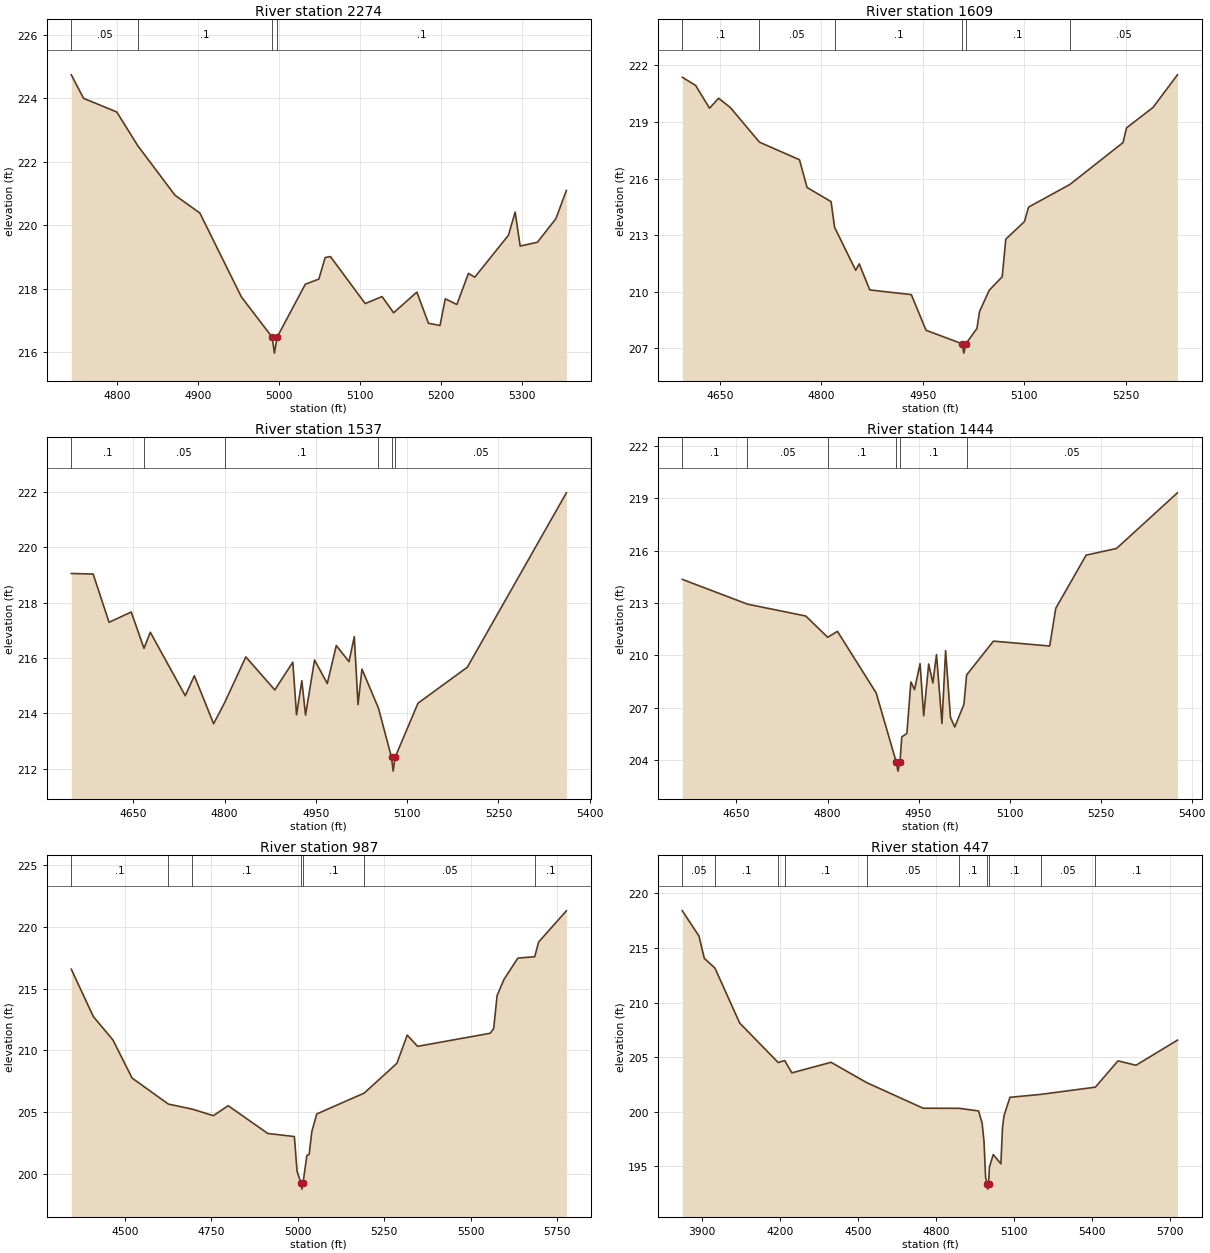
Type RM Length L Ch R = 1,2274,665,665,665
BEGIN DESCRIPTION:
UNT010 IN NURI 2.0
END DESCRIPTION:
XS GIS Cut Line= 4
      2285673.07     13328051.67      2285607.97     13327767.85
      2285420.47     13327611.60      2285358.74     13327566.68
#Sta/Elev= 30
  4743.2  224.74  4758.4  224.00  4799.4  223.57  4825.3  222.51  4871.3  220.95
  4902.0  220.39  4953.3  217.75  4991.4  216.48  4994.1  215.98  4997.4  216.48
  5032.3  218.15  5049.0  218.31  5056.8  218.99  5063.3  219.02  5106.3  217.54
  5127.1  217.76  5141.4  217.25  5170.1  217.90  5184.4  216.92  5198.7  216.85
  5205.2  217.69  5219.5  217.51  5233.8  218.49  5241.6  218.37  5283.2  219.69
  5291.5  220.42  5297.7  219.35  5319.0  219.47  5341.8  220.21  5354.8  221.10
#Mann=4,-1,0
  4743.2    0.05       0  4825.3     0.1       0  4991.4    0.07       0
  4997.4     0.1       0
Bank Sta=4991.4,4997.4
Exp/Cntr=0.3,0.1

Type RM Length L Ch R = 1,1609,72,72,72
BEGIN DESCRIPTION:
Mapping XS 58580859
END DESCRIPTION:
XS GIS Cut Line= 5
      2286175.03     13327775.87      2286102.11     13327479.01
      2286017.48     13327383.96      2285801.33     13327321.46
      2285735.62     13327287.99
#Sta/Elev= 30
  4594.8  221.37  4614.4  220.94  4635.0  219.73  4648.4  220.26  4665.9  219.76
  4708.8  217.93  4767.9  217.00  4779.1  215.53  4814.6  214.78  4819.8  213.42
  4851.0  211.14  4856.2  211.48  4871.8  210.10  4933.2  209.85  4955.0  207.96
  5008.0  207.25  5010.8  206.75  5014.0  207.25  5030.2  208.06  5034.0  208.95
  5048.3  210.08  5067.6  210.80  5072.8  212.79  5100.4  213.72  5106.5  214.49
  5167.6  215.69  5246.1  217.91  5251.3  218.69  5290.4  219.77  5326.5  221.50
#Mann=6,-1,0
  4594.8     0.1       0  4708.8    0.05       0  4819.8     0.1       0
  5008.0    0.07       0  5014.0     0.1       0  5167.6    0.05       0
Bank Sta=5008,5014
Exp/Cntr=0.3,0.1

Type RM Length L Ch R = 1,1537,93,93,93
BEGIN DESCRIPTION:
Mapping XS f763a20a
END DESCRIPTION:
XS GIS Cut Line= 5
      2286263.58     13327768.10      2286160.71     13327467.29
      2286055.24     13327317.55      2285806.54     13327275.88
      2285748.67     13327259.78
#Sta/Elev= 30
  4548.3  219.05  4584.2  219.03  4610.3  217.29  4646.8  217.66  4667.7  216.35
  4678.1  216.93  4735.5  214.64  4750.4  215.36  4782.1  213.63  4800.2  214.39
  4835.0  216.04  4882.6  214.85  4912.2  215.85  4918.3  213.95  4927.0  215.18
  4933.1  213.94  4947.9  215.93  4968.8  215.08  4983.6  216.45  5004.5  215.87
  5013.2  216.77  5019.3  214.32  5025.8  215.60  5052.9  214.19  5074.3  212.42
  5077.0  211.92  5080.3  212.42  5117.8  214.37  5198.9  215.67  5361.6  221.96
#Mann=6,-1,0
  4548.3     0.1       0  4667.7    0.05       0  4800.2     0.1       0
  5052.9    0.05       0  5074.3    0.07       0  5080.3    0.05       0
Bank Sta=5074.3,5080.3
Exp/Cntr=0.3,0.1

Type RM Length L Ch R = 1,1444,457,457,457
BEGIN DESCRIPTION:
Mapping XS d5b74e86
END DESCRIPTION:
XS GIS Cut Line= 4
      2286335.18     13327721.18      2286249.25     13327441.25
      2286125.55     13327253.75      2285827.38     13327243.33
#Sta/Elev= 30
  4560.8  214.35  4668.1  212.93  4764.1  212.25  4800.4  211.03  4816.4  211.37
  4880.2  207.84  4913.4  203.86  4916.1  203.36  4919.4  203.86  4922.4  205.32
  4930.8  205.52  4937.4  208.47  4943.4  208.03  4952.5  209.52  4958.5  206.53
  4966.7  209.50  4973.6  208.41  4979.6  210.04  4988.6  206.09  4994.6  210.27
  5002.6  206.44  5009.7  205.89  5024.8  207.19  5029.2  208.87  5073.4  210.81
  5166.1  210.53  5176.1  212.69  5226.2  215.74  5276.2  216.12  5376.6  219.31
#Mann=6,-1,0
  4560.8     0.1       0  4668.1    0.05       0  4800.4     0.1       0
  4913.4    0.07       0  4919.4     0.1       0  5029.2    0.05       0
Bank Sta=4913.4,4919.4
Exp/Cntr=0.3,0.1

Type RM Length L Ch R = 1,987,540,540,540
BEGIN DESCRIPTION:
Mapping XS a24cc669
END DESCRIPTION:
XS GIS Cut Line= 5
      2286349.32     13327828.69      2286471.10     13327700.88
      2286591.70     13327316.25      2286483.63     13327189.95
      2285797.40     13327210.78
#Sta/Elev= 30
  4345.0  216.57  4408.8  212.73  4465.4  210.84  4520.9  207.75  4625.9  205.64
  4695.4  205.23  4756.0  204.70  4798.9  205.51  4913.5  203.26  4990.4  203.01
  4998.1  200.20  5009.4  199.25  5012.1  198.75  5015.4  199.25  5026.6  201.47
  5033.2  201.57  5040.9  203.42  5055.2  204.84  5192.3  206.53  5286.9  208.94
  5316.9  211.23  5346.9  210.32  5557.0  211.38  5567.0  211.76  5577.0  214.44
  5597.0  215.75  5637.0  217.47  5685.7  217.58  5697.0  218.77  5777.4  221.30
#Mann=7,-1,0
  4345.0     0.1       0  4625.9    0.05       0  4695.4     0.1       0
  5009.4    0.07       0  5015.4     0.1       0  5192.3    0.05       0
  5685.7     0.1       0
Bank Sta=5009.4,5015.4
Exp/Cntr=0.3,0.1

Type RM Length L Ch R = 1,447,234,234,234
BEGIN DESCRIPTION:
Mapping XS 51e7f3ac
END DESCRIPTION:
XS GIS Cut Line= 5
      2286342.96     13327920.37      2286787.40     13327316.21
      2286926.29     13327010.65      2286836.01     13326885.65
      2286205.66     13326681.31
#Sta/Elev= 30
  3825.2  218.41  3888.9  216.11  3909.7  214.05  3950.5  213.16  4045.5  208.12
  4193.5  204.50  4218.6  204.68  4246.1  203.55  4396.5  204.52  4534.2  202.65
  4750.3  200.31  4889.4  200.30  4963.5  200.06  4977.2  198.93  4984.3  197.29
  4990.5  194.00  4996.0  193.39  4998.8  192.89  5002.0  193.39  5005.2  194.91
  5019.9  196.06  5049.3  195.21  5055.5  198.51  5061.2  199.62  5084.3  201.31
  5203.3  201.58  5412.3  202.24  5499.2  204.65  5568.5  204.25  5727.7  206.55
#Mann=10,-1,0
  3825.2    0.05       0  3950.5     0.1       0  4193.5    0.05       0
  4218.6     0.1       0  4534.2    0.05       0  4889.4     0.1       0
  4996.0    0.07       0  5002.0     0.1       0  5203.3    0.05       0
  5412.3     0.1       0
Bank Sta=4996,5002
Exp/Cntr=0.3,0.1

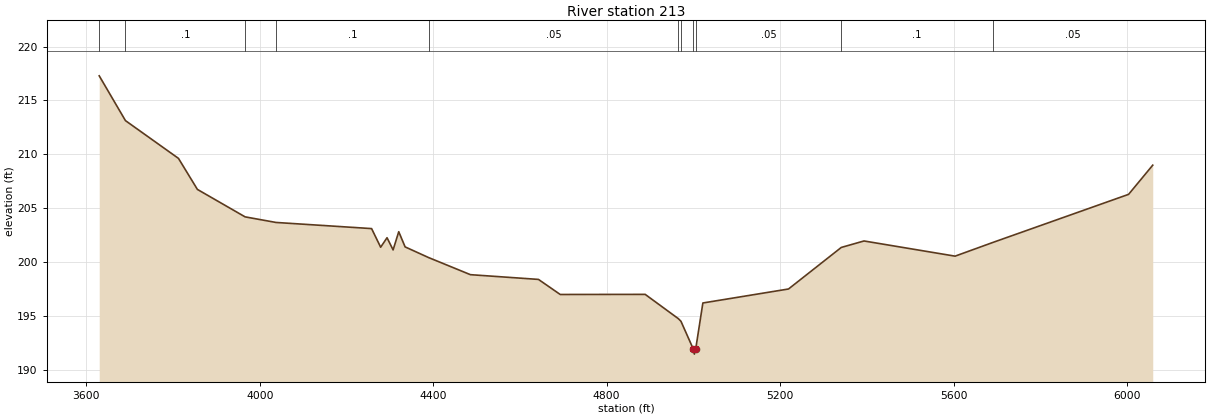
Type RM Length L Ch R = 1,213,0,0,0
BEGIN DESCRIPTION:
UNT010 IN NURI 1.0
END DESCRIPTION:
XS GIS Cut Line= 4
      2286389.19     13327934.56      2287092.96     13326968.99
      2286981.85     13326538.43      2286192.01     13326549.10
#Sta/Elev= 30
  3629.8  217.28  3690.3  213.12  3812.6  209.61  3856.2  206.73  3966.2  204.18
  4037.5  203.66  4257.9  203.09  4278.8  201.36  4293.5  202.24  4307.5  201.11
  4320.5  202.80  4335.2  201.39  4389.3  200.40  4485.8  198.81  4642.7  198.37
  4692.9  196.97  4888.8  196.98  4965.4  194.72  4971.3  194.48  4999.4  191.93
  5002.2  191.43  5005.4  191.93  5021.8  196.18  5219.3  197.48  5341.0  201.34
  5393.4  201.94  5603.4  200.53  5690.3  201.80  6003.5  206.27  6059.2  208.98
#Mann=11,-1,0
  3629.8    0.05       0  3690.3     0.1       0  3966.2    0.05       0
  4037.5     0.1       0  4389.3    0.05       0  4965.4     0.1       0
  4971.3    0.05       0  4999.4    0.03       0  5005.4    0.05       0
  5341.0     0.1       0  5690.3    0.05       0
Bank Sta=4999.4,5005.4
Exp/Cntr=0.3,0.1

Chan Stop Cuts=-1