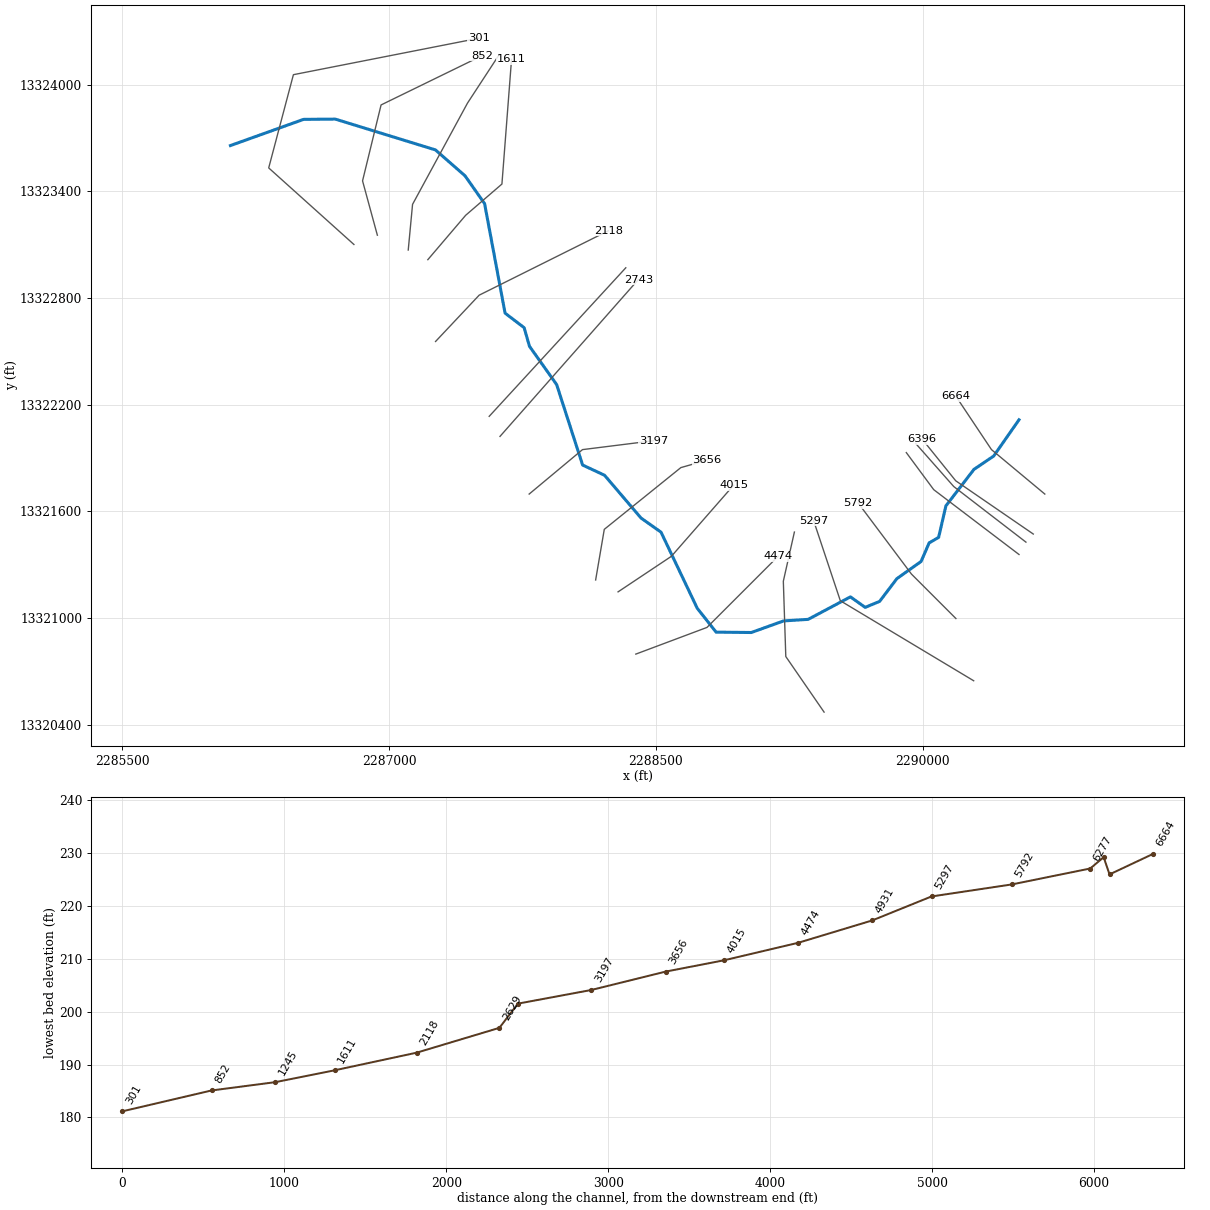
--- UNT011 IN NURI.prj (project) ---

Proj Title=UNT011 IN NURI Base Level Engineering
Current Plan=p01
Default Exp/Contr=0.3,0.1
English Units
Geom File=g01
Flow File=f01
Plan File=p01
Y Axis Title=Elevation
X Axis Title(PF)=Main Channel Distance
X Axis Title(XS)=Station
BEGIN DESCRIPTION:
UNT011 IN NURI
END DESCRIPTION:
DSS Export Rating Curves= 0
DSS Export Rating Curve Sorted= 0
DSS Export Volume Flow Curves= 0
DXF OffsetX= 0
DXF OffsetY= 0
DXF ScaleX= 1
DXF ScaleY= 10

--- UNT011 IN NURI.p01 (plan) ---

Plan Title=Multiple Run
Short Identifier=Multiple
Geom File=g01
Flow File=f01
Subcritical Flow
K Sum by GR= 0
Std Step Tol= 0.01
Critical Tol= 0.01
Num of Std Step Trials= 20
Max Error Tol= 0.3
Flow Tol Ratio= 0.001
Split Flow NTrial= 30
Split Flow Tol= 0.02
Split Flow Ratio= 0.02
Log Output Level= 0
Friction Slope Method= 1
Unsteady Friction Slope Method= 2
Unsteady Bridges Friction Slope Method= 1
Parabolic Critical Depth
Global Vel Dist=  1 , 1 , 1
Global Log Level= 0
CheckData=True
Encroach Param= -1, 0, 0, 0
BEGIN DESCRIPTION:
Multiple Run
END DESCRIPTION:

--- UNT011 IN NURI.f01 (steady flow) ---

Flow Title=Multiple
Program Version=4.10
Number of Profiles= 7
Profile Names=10-year,25-year,50-year,1pct_min,100-year,1pct_plu,500-year
River Rch & RM=UNT011 IN NURI,Reach-1         ,6664
     593     845    1057     968    1309    1770    2012
River Rch & RM=UNT011 IN NURI,Reach-1         ,5297
     570     812    1018     933    1262    1707    1952
River Rch & RM=UNT011 IN NURI,Reach-1         ,2629
     572     816    1024     940    1271    1719    1972
River Rch & RM=UNT011 IN NURI,Reach-1         ,1611
     636     915    1154    1065    1440    1947    2259
River Rch & RM=UNT011 IN NURI,Reach-1         ,1245
     636     915    1154    1065    1440    1947    2259
Boundary for River Rch & Prof#=UNT011 IN NURI,Reach-1         , 1
Up Type= 0
Dn Type= 3
Dn Slope=0.005
Boundary for River Rch & Prof#=UNT011 IN NURI,Reach-1         , 2
Up Type= 0
Dn Type= 3
Dn Slope=0.005
Boundary for River Rch & Prof#=UNT011 IN NURI,Reach-1         , 3
Up Type= 0
Dn Type= 3
Dn Slope=0.005
Boundary for River Rch & Prof#=UNT011 IN NURI,Reach-1         , 4
Up Type= 0
Dn Type= 3
Dn Slope=0.005
Boundary for River Rch & Prof#=UNT011 IN NURI,Reach-1         , 5
Up Type= 0
Dn Type= 3
Dn Slope=0.005
Boundary for River Rch & Prof#=UNT011 IN NURI,Reach-1         , 6
Up Type= 0
Dn Type= 3
Dn Slope=0.005
Boundary for River Rch & Prof#=UNT011 IN NURI,Reach-1         , 7
Up Type= 0
Dn Type= 3
Dn Slope=0.005
DSS Import GetInterval= 0
DSS Import GetPeak= 0
DSS Import FillOption= 0

--- UNT011 IN NURI.g01 (geometry) ---

Geom Title=Existing Conditions
Program Version=4.10

River Reach=UNT011 IN NURI  ,Reach-1
Reach XY= 30
      2290542.53     13322114.49      2290400.08     13321910.51
      2290289.16     13321835.64      2290131.54     13321630.63
      2290090.47     13321453.15       2290037.3     13321422.39
      2289991.83      13321317.6      2289856.03     13321221.48
      2289758.65     13321093.23      2289677.44     13321059.64
      2289594.49     13321118.66      2289356.61      13320992.1
      2289218.79     13320983.44      2289037.03     13320918.21
      2288839.22      13320920.3      2288733.08     13321054.36
      2288529.37     13321482.44      2288416.47     13321562.38
      2288211.81     13321802.56      2288088.39     13321860.07
      2287942.28     13322312.67      2287789.57     13322527.81
      2287759.52     13322632.49       2287652.3     13322714.28
      2287537.07     13323330.18      2287427.11     13323486.59
      2287260.67      13323632.4      2286697.24      13323805.7
      2286518.88     13323804.06      2286107.72     13323656.85

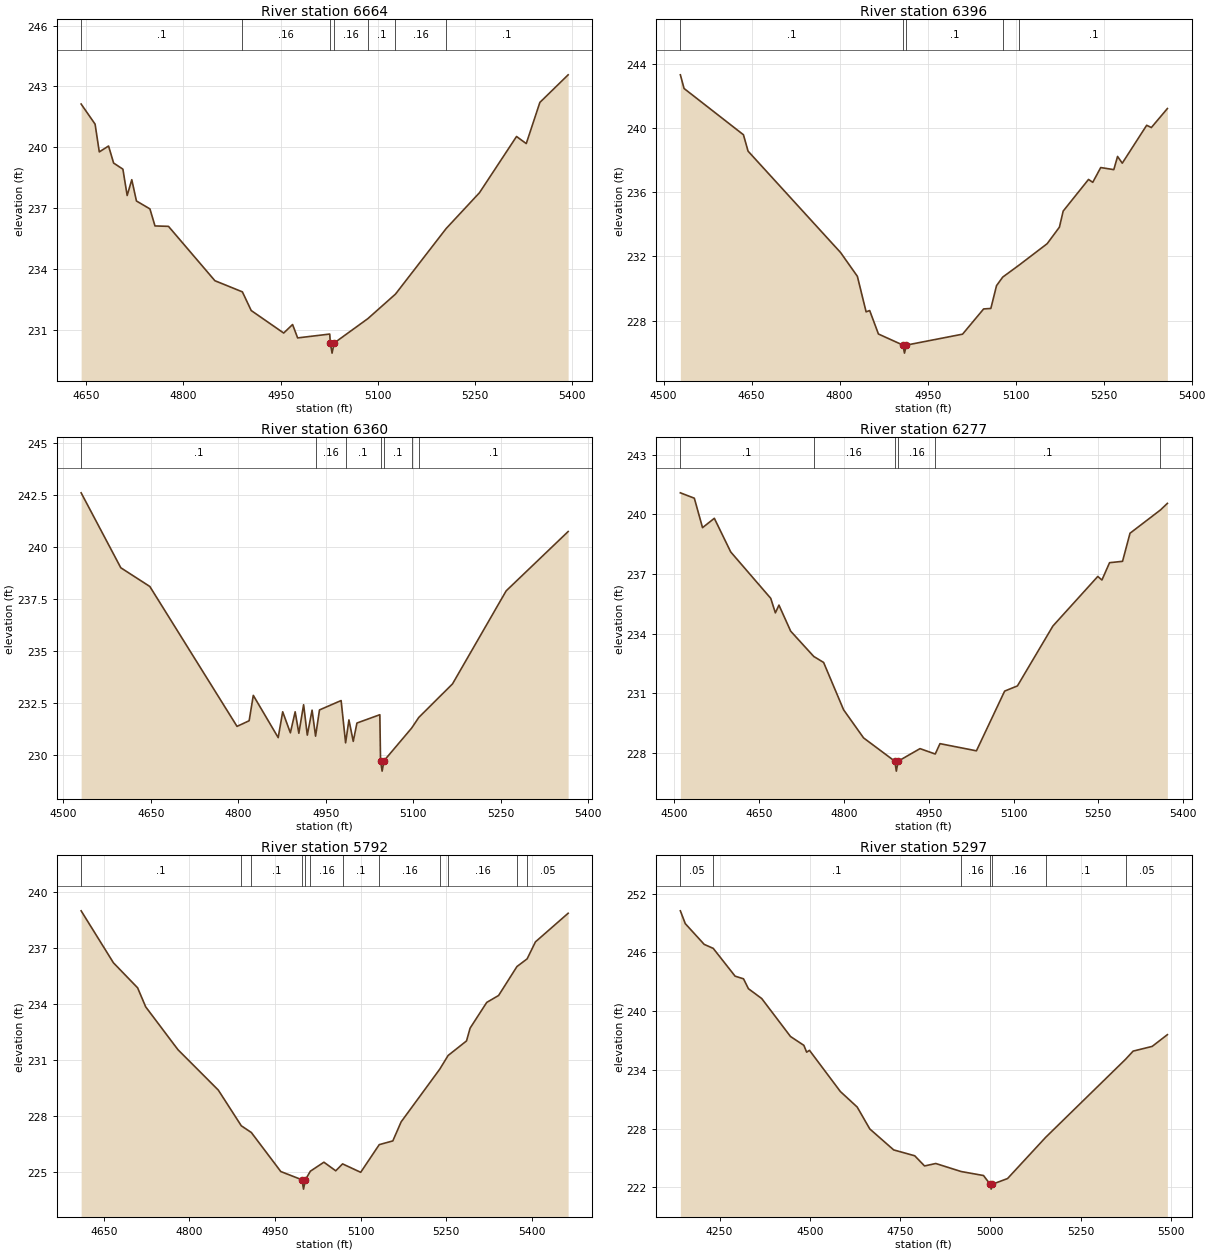
Type RM Length L Ch R = 1 ,6664    ,268,268,268
BEGIN DESCRIPTION:
UNT011 IN NURI 15.0
END DESCRIPTION:
XS GIS Cut Line= 3
      2290687.73     13321696.85      2290387.72     13321946.85
      2290187.71     13322246.87
#Sta/Elev= 30
  4642.3  242.13  4663.8  241.14  4670.3  239.77  4684.6  240.06  4692.4  239.22
  4706.7  238.92  4713.3  237.62  4720.4   238.4  4727.6  237.35  4748.4  236.96
  4756.2  236.12    4777   236.1  4848.6  233.42    4891  232.87  4904.6  231.95
  4954.7  230.84  4968.4  231.26  4976.2   230.6  5025.7  230.79  5026.6  230.35
  5029.3  229.85  5032.6  230.35  5084.5  231.55  5127.1  232.76  5205.2  235.99
  5256.7  237.76  5313.8  240.53  5328.8  240.18  5349.8  242.21  5393.4  243.57
#Mann= 7 ,-1 , 0
  4642.3      .1       0    4891     .16       0  5026.6     .07       0
  5032.6     .16       0  5084.5      .1       0  5127.1     .16       0
  5205.2      .1       0
Bank Sta=5026.6,5032.6
XS Rating Curve= 0 ,0
Exp/Cntr=0.3,0.1

Type RM Length L Ch R = 1 ,6396    ,36,36,36
BEGIN DESCRIPTION:
Mapping XS d7f49c7a
END DESCRIPTION:
XS GIS Cut Line= 3
      2290622.88     13321472.04      2290186.64     13321771.54
      2289997.85      13322005.9
#Sta/Elev= 30
  4528.5   243.3  4534.8  242.45    4636  239.57  4643.9  238.55  4801.6  232.24
  4830.2  230.76  4845.1  228.55  4851.2  228.63  4866.1  227.17  4907.8  226.48
  4910.5  225.98  4913.8  226.48  5009.5  227.16  5045.4  228.73  5057.7  228.76
  5067.4  230.18  5077.9  230.71  5106.3  231.47  5153.7  232.79  5174.6  233.82
    5181  234.82  5224.2  236.79  5231.4  236.61    5245  237.53  5267.3   237.4
  5273.7  238.22  5281.7   237.8  5323.3  240.16  5331.3  240.02  5358.6   241.2
#Mann= 5 ,-1 , 0
  4528.5      .1       0  4907.8     .07       0  4913.8      .1       0
  5077.9     .16       0  5106.3      .1       0
Bank Sta=4907.8,4913.8
XS Rating Curve= 0 ,0
Exp/Cntr=0.3,0.1

Type RM Length L Ch R = 1 ,6360    ,83,83,83
BEGIN DESCRIPTION:
Mapping XS 43a5c14b
END DESCRIPTION:
XS GIS Cut Line= 3
      2290581.57     13321426.52      2290175.79     13321738.99
      2289961.91     13321980.96
#Sta/Elev= 30
  4530.5  242.61  4598.5  239.01  4648.3  238.11  4797.8  231.39  4818.6  231.66
  4825.7  232.88  4868.4  230.85  4876.1  232.09  4889.3  231.08  4897.5  232.09
  4903.8  231.06    4912  232.43  4918.3  230.97  4926.5  232.17  4932.5  230.92
  4939.2  232.18  4976.3  232.63    4984   230.6  4989.7   231.7  4997.1  230.67
  5003.4  231.55  5042.7  231.95  5043.9  229.74  5046.6  229.24  5049.9  229.74
  5097.3  231.31  5109.5  231.82  5167.3  233.43  5259.3   237.9  5365.6  240.75
#Mann= 7 ,-1 , 0
  4530.5      .1       0  4932.5     .16       0    4984      .1       0
  5043.9     .07       0  5049.9      .1       0  5097.3     .16       0
  5109.5      .1       0
Bank Sta=5043.9,5049.9
XS Rating Curve= 0 ,0
Exp/Cntr=0.3,0.1

Type RM Length L Ch R = 1 ,6277    ,485,485,485
BEGIN DESCRIPTION:
UNT011 IN NURI 14.0
END DESCRIPTION:
XS GIS Cut Line= 3
      2290542.55     13321357.04      2290062.94     13321721.63
      2289908.85     13321929.99
#Sta/Elev= 30
  4510.6  241.08  4535.3  240.81  4549.8  239.33  4570.7   239.8  4599.7  238.11
  4670.5  235.78  4678.7  235.05    4685  235.44  4705.8  234.13  4746.6  232.86
    4764  232.56  4799.4  230.18  4834.7  228.77  4889.9   227.6  4892.7   227.1
  4895.9   227.6  4934.6  228.23  4961.5  227.96  4969.9  228.48  5034.4  228.12
  5084.3  231.12  5106.9  231.38  5169.7  234.39  5249.1  236.88  5256.4   236.7
  5269.9  237.57  5292.9  237.64  5306.1  239.05    5360  240.22  5372.2  240.55
#Mann= 6 ,-1 , 0
  4510.6      .1       0  4746.6     .16       0  4889.9     .07       0
  4895.9     .16       0  4961.5      .1       0    5360     .05       0
Bank Sta=4889.9,4895.9
XS Rating Curve= 0 ,0
Exp/Cntr=0.3,0.1

Type RM Length L Ch R = 1 ,5792    ,495,495,495
BEGIN DESCRIPTION:
UNT011 IN NURI 13.0
END DESCRIPTION:
XS GIS Cut Line= 3
      2290187.74     13320996.83      2289937.72     13321246.85
      2289637.71     13321646.87
#Sta/Elev= 30
  4610.1  238.97  4666.7  236.19  4709.1  234.85  4723.3  233.83  4779.8  231.54
  4850.5  229.38  4890.8  227.47  4908.4  227.11  4960.1  225.02  4997.1  224.58
  4999.9  224.08  5003.1  224.58  5011.9  225.04  5035.6  225.52  5056.4  225.06
  5068.3  225.43  5100.1  224.98  5132.6  226.46  5156.4  226.66    5171  227.68
  5238.7   230.5  5253.3  231.23  5285.6  232.01  5291.8  232.69    5321  234.07
  5341.8  234.44    5374  235.99  5391.8   236.4  5406.4  237.31  5463.7  238.84
#Mann= 12 ,-1 , 0
  4610.1      .1       0  4890.8     .16       0  4908.4      .1       0
  4997.1     .07       0  5003.1      .1       0  5011.9     .16       0
  5068.3      .1       0  5132.6     .16       0  5238.7      .1       0
  5253.3     .16       0    5374      .1       0  5391.8     .05       0
Bank Sta=4997.1,5003.1
XS Rating Curve= 0 ,0
Exp/Cntr=0.3,0.1

Type RM Length L Ch R = 1 ,5297    ,366,366,366
BEGIN DESCRIPTION:
UNT011 IN NURI 12.0
END DESCRIPTION:
XS GIS Cut Line= 3
      2290287.68     13320646.88      2289537.72     13321096.85
      2289387.73     13321546.82
#Sta/Elev= 30
  4141.6  250.26  4155.2  248.95  4207.6  246.83  4232.7  246.42  4293.2  243.58
  4316.5  243.31  4330.1   242.3    4367  241.29  4446.7  237.41  4483.6  236.51
  4491.4  235.81  4499.2     236  4584.7  231.79  4631.4   230.2  4666.3  227.96
  4732.4  225.82  4790.7  225.22  4817.9  224.18    4849  224.43  4919.2  223.61
  4981.2   223.2  4999.6  222.31  5002.3  221.81  5005.6  222.31  5047.8  222.89
    5153  227.09  5374.6  235.08  5395.7  235.92  5448.4   236.4  5490.5   237.6
#Mann= 7 ,-1 , 0
  4141.6     .05       0  4232.7      .1       0  4919.2     .16       0
  4999.6     .07       0  5005.6     .16       0    5153      .1       0
  5374.6     .05       0
Bank Sta=4999.6,5005.6
XS Rating Curve= 0 ,0
Exp/Cntr=0.3,0.1

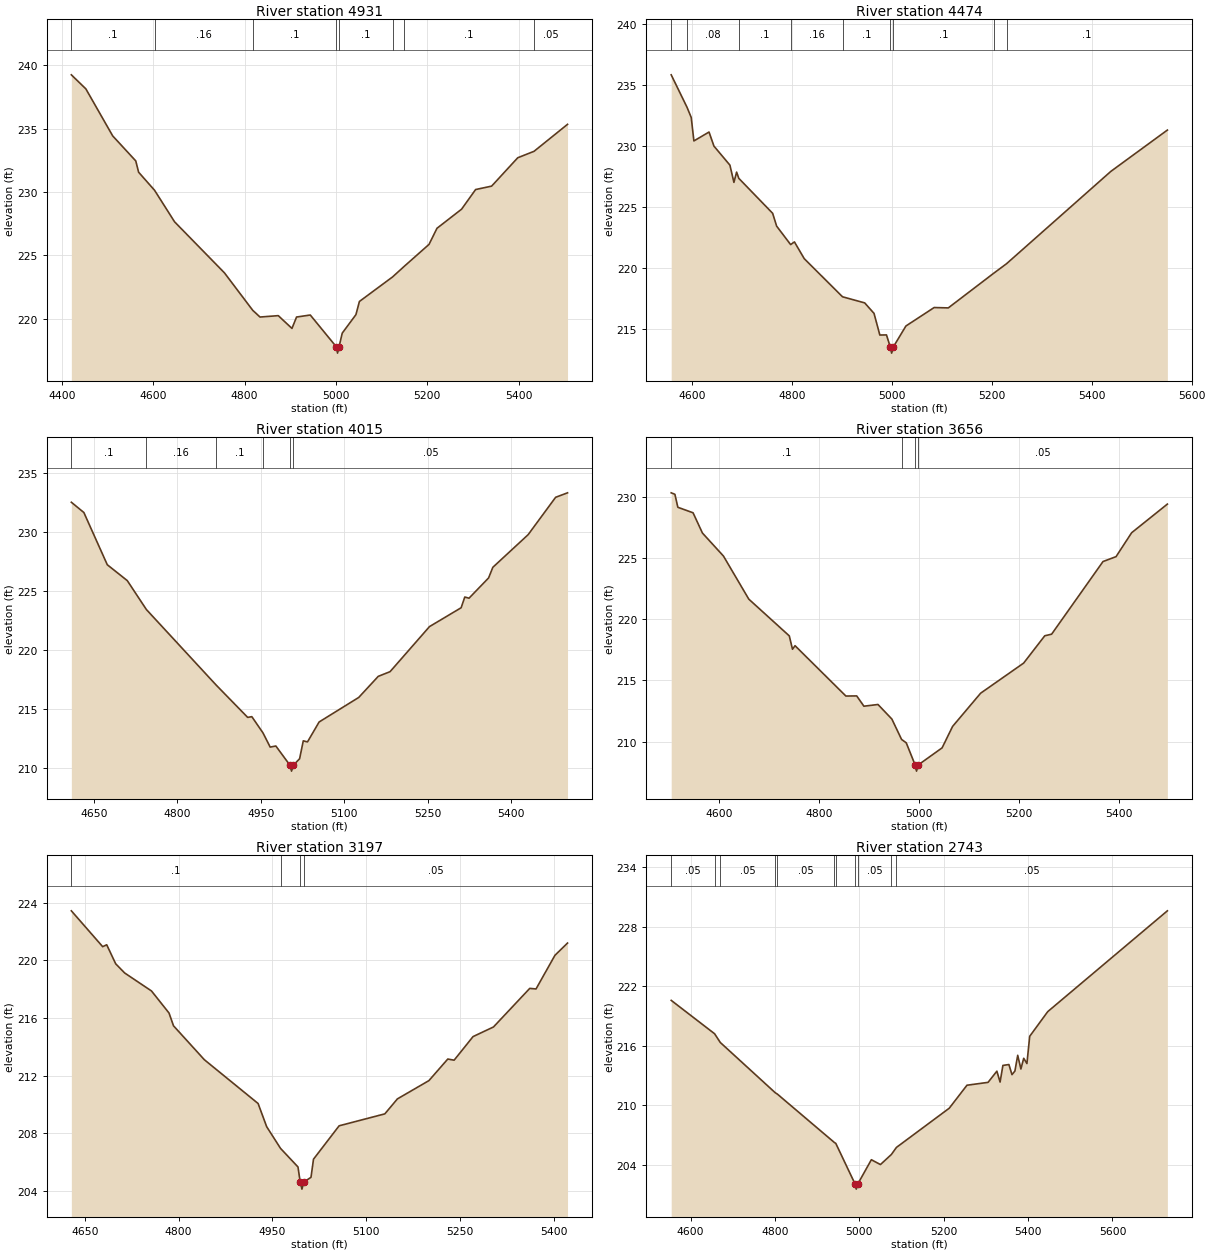
Type RM Length L Ch R = 1 ,4931    ,457,457,457
BEGIN DESCRIPTION:
UNT011 IN NURI 11.0
END DESCRIPTION:
XS GIS Cut Line= 4
      2289446.32     13320470.65      2289231.05     13320783.14
      2289217.16     13321206.75      2289279.37     13321483.24
#Sta/Elev= 30
  4420.4  239.25  4452.2  238.14  4510.9  234.43  4561.5  232.45  4567.7  231.56
  4602.7  230.13  4646.5  227.64  4755.7  223.61  4817.7  220.65  4833.6  220.12
  4873.6  220.23  4903.6  219.22  4913.6  220.12  4943.7  220.28  5000.7  217.77
  5003.4  217.27  5006.7  217.77  5013.7  218.85  5043.7  220.31  5051.3  221.35
    5124  223.29  5148.4  224.09  5203.8  225.86  5221.2  227.13  5275.1  228.64
  5305.8  230.19  5340.9  230.46  5398.1   232.7  5433.8  233.21  5507.1  235.34
#Mann= 8 ,-1 , 0
  4420.4      .1       0  4602.7     .16       0  4817.7      .1       0
  5000.7     .07       0  5006.7      .1       0    5124     .16       0
  5148.4      .1       0  5433.8     .05       0
Bank Sta=5000.7,5006.7
XS Rating Curve= 0 ,0
Exp/Cntr=0.3,0.1

Type RM Length L Ch R = 1 ,4474    ,459,459,459
BEGIN DESCRIPTION:
UNT011 IN NURI 10.0
END DESCRIPTION:
XS GIS Cut Line= 3
      2288387.68     13320796.84      2288787.72     13320946.85
       2289187.7     13321346.84
#Sta/Elev= 30
  4558.5  235.81  4590.1  233.16  4598.6  232.32  4603.9   230.4  4634.2  231.13
    4644  229.98    4676  228.42    4684  227.01  4689.4  227.85  4693.8  227.34
  4761.5  224.48  4769.5  223.43  4797.5  221.92  4805.1  222.14  4824.7  220.77
  4901.3  217.65  4945.7  217.15  4964.4  216.29    4976  214.52  4989.3  214.53
  4996.9  213.54  4999.6  213.04  5002.9  213.54  5028.2  215.26  5084.7  216.77
    5113  216.74  5203.7  219.57  5229.7  220.36  5438.3  227.91  5551.4  231.29
#Mann= 9 ,-1 , 0
  4558.5      .1       0  4590.1     .08       0  4693.8      .1       0
  4797.5     .16       0  4901.3      .1       0  4996.9     .07       0
  5002.9      .1       0  5203.7     .05       0  5229.7      .1       0
Bank Sta=4996.9,5002.9
XS Rating Curve= 0 ,0
Exp/Cntr=0.3,0.1

Type RM Length L Ch R = 1 ,4015    ,359,359,359
BEGIN DESCRIPTION:
UNT011 IN NURI 9.0
END DESCRIPTION:
XS GIS Cut Line= 3
      2288287.73     13321146.86      2288587.72     13321346.85
      2288937.75     13321746.89
#Sta/Elev= 30
  4609.6  232.53  4632.1  231.66  4674.2  227.23  4710.2  225.88  4744.5  223.43
  4869.8  217.03  4926.6  214.28  4934.1  214.34  4954.2  212.96  4967.1  211.76
  4977.3  211.85  5002.7  210.22  5005.5  209.72  5008.7  210.22    5020  210.77
  5026.6  212.29  5034.2   212.2  5055.1  213.89  5126.3  215.97  5161.4  217.76
  5182.7  218.16  5253.5  221.98  5310.4  223.58    5317  224.49  5324.6  224.39
  5359.8  226.11  5367.4  227.01  5430.9  229.78  5480.3  232.95  5501.7  233.33
#Mann= 6 ,-1 , 0
  4609.6      .1       0  4744.5     .16       0  4869.8      .1       0
  4954.2     .05       0  5002.7     .03       0  5008.7     .05       0
Bank Sta=5002.7,5008.7
XS Rating Curve= 0 ,0
Exp/Cntr=0.3,0.1

Type RM Length L Ch R = 1 ,3656    ,459,459,459
BEGIN DESCRIPTION:
UNT011 IN NURI 8.0
END DESCRIPTION:
XS GIS Cut Line= 4
      2288161.61     13321213.72      2288210.21     13321498.42
      2288640.77     13321845.64       2288786.6      13321887.3
#Sta/Elev= 30
    4504  230.31  4511.4  230.19  4517.3  229.13  4547.8  228.68  4566.5  227.03
  4608.6  225.15  4659.4  221.63  4740.5  218.63  4746.9  217.54    4752  217.83
  4853.8  213.72  4875.5  213.73  4889.9  212.89  4918.1  213.03  4945.9  211.84
  4965.3  210.18  4974.7   209.9  4992.5  208.09  4995.3  207.59  4998.5  208.09
  5046.5  209.49  5067.5  211.24  5123.6  213.95  5209.8  216.41  5252.1  218.64
  5265.8  218.77  5368.7   224.7  5394.8   225.1    5426  227.05  5497.6  229.39
#Mann= 4 ,-1 , 0
    4504      .1       0  4965.3     .05       0  4992.5     .03       0
  4998.5     .05       0
Bank Sta=4992.5,4998.5
XS Rating Curve= 0 ,0
Exp/Cntr=0.3,0.1

Type RM Length L Ch R = 1 ,3197    ,454,454,454
BEGIN DESCRIPTION:
UNT011 IN NURI 7.0
END DESCRIPTION:
XS GIS Cut Line= 3
      2287787.72     13321696.86      2288087.72     13321946.85
       2288487.7     13321996.85
#Sta/Elev= 30
  4628.5  223.45  4678.6  220.96  4685.1  221.09  4699.4  219.77  4713.8  219.13
  4756.7  217.88  4784.7  216.35  4791.9  215.46  4841.3   213.1  4927.2  210.06
  4940.9  208.45  4963.1  206.94    4991  205.65  4994.5  204.61  4997.3  204.11
  5000.5  204.61  5011.8  204.93  5015.8  206.19  5056.8  208.51  5129.9  209.34
    5150  210.38  5200.4  211.65  5230.6  213.15  5240.7  213.07    5271  214.71
  5303.7  215.38  5361.7  218.06  5371.7  218.02    5402  220.36  5422.1  221.21
#Mann= 4 ,-1 , 0
  4628.5      .1       0  4963.1     .05       0  4994.5     .03       0
  5000.5     .05       0
Bank Sta=4994.5,5000.5
XS Rating Curve= 0 ,0
Exp/Cntr=0.3,0.1

Type RM Length L Ch R = 1 ,2743    ,114,114,114
BEGIN DESCRIPTION:
UNT011 IN NURI 6.0
END DESCRIPTION:
XS GIS Cut Line= 2
      2287623.71     13322021.11      2288401.63     13322903.04
#Sta/Elev= 30
  4554.1  220.58  4656.9  217.21  4670.4  216.33  4800.5  211.26  4805.6  211.12
  4940.8  206.23  4944.2  206.14  4990.1  202.02  4992.8  201.52  4996.1  202.02
  5028.5  204.49    5050     204    5076  205.02  5087.9  205.73  5213.1  209.69
  5255.1  212.01  5305.1   212.3    5326  213.43  5333.6  212.33  5340.3  214.01
  5354.5   214.1  5361.8  213.08  5368.7  213.44  5375.4  215.03  5382.9  213.65
  5389.6  214.73  5397.2   214.2  5403.8  216.95  5446.5  219.44  5730.1  229.62
#Mann= 11 ,-1 , 0
  4554.1     .05       0  4656.9      .1       0  4670.4     .05       0
  4800.5      .1       0  4805.6     .05       0  4940.8     .08       0
  4944.2     .05       0  4990.1     .03       0  4996.1     .05       0
    5076     .08       0  5087.9     .05       0
Bank Sta=4990.1,4996.1
XS Rating Curve= 0 ,0
Exp/Cntr=0.3,0.1

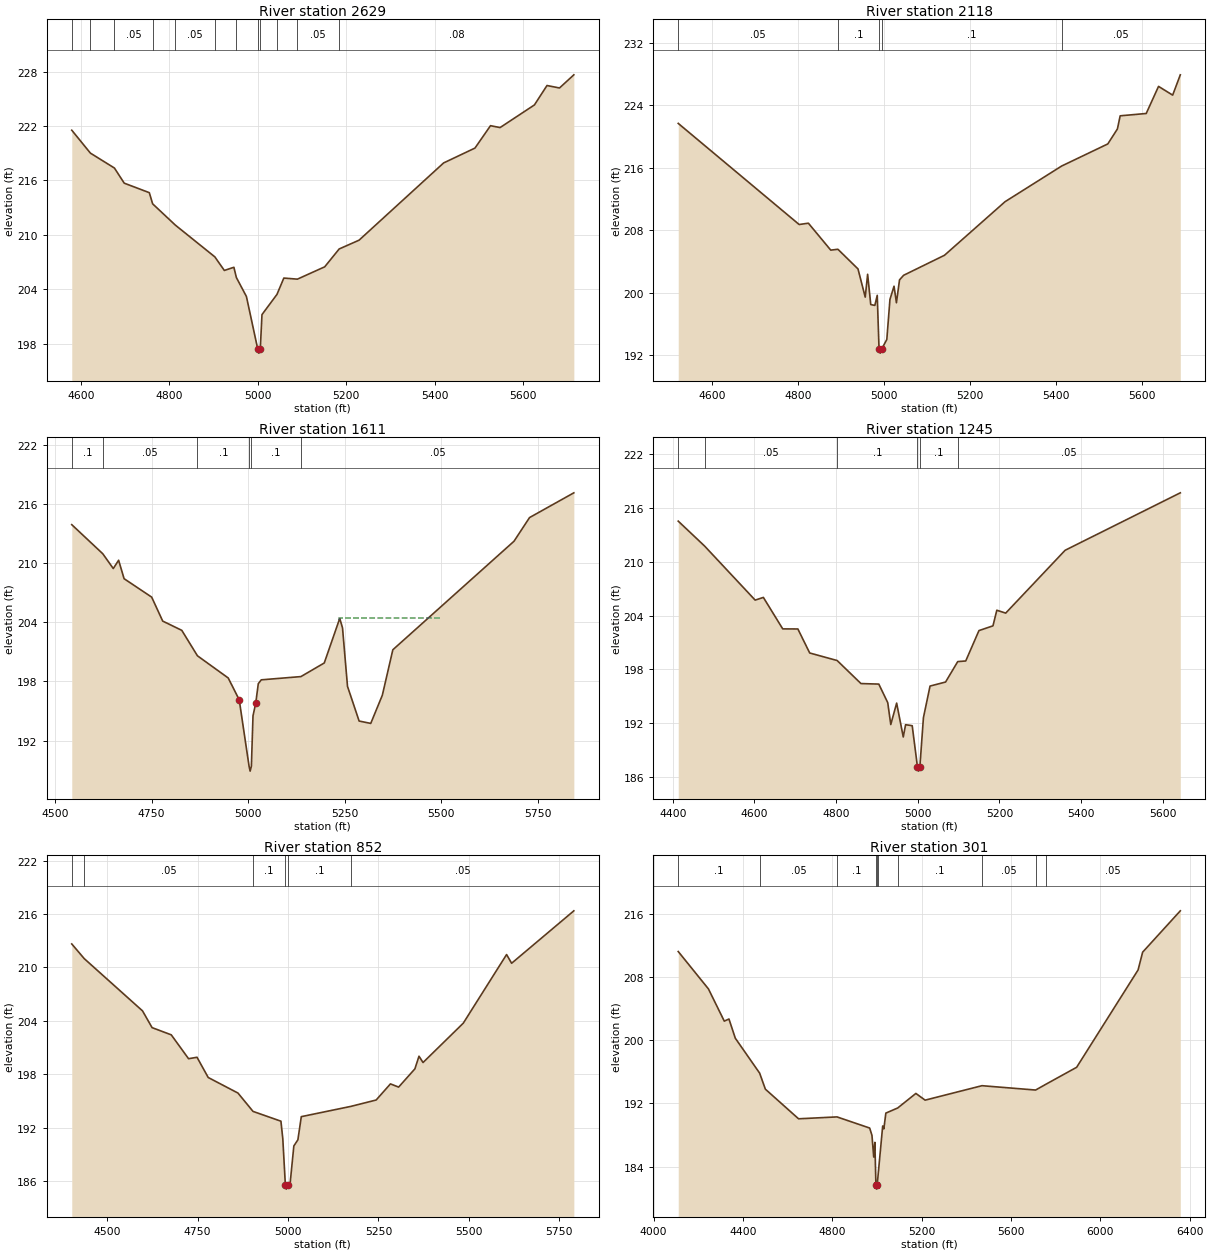
Type RM Length L Ch R = 1 ,2629    ,511,511,511
BEGIN DESCRIPTION:
Mapping XS 672a82d0
END DESCRIPTION:
XS GIS Cut Line= 2
      2287562.95     13322133.97      2288331.18     13322969.47
#Sta/Elev= 30
  4579.6  221.53  4621.8     219    4676  217.36  4698.2  215.69  4754.9  214.64
  4762.4  213.41  4813.8  211.06    4903  207.56  4924.5  206.06  4946.1  206.41
  4951.7  205.28  4974.4  203.19  4999.8  197.44  5002.5  196.94  5005.8  197.44
  5009.6  201.19  5043.5  203.42    5059  205.22  5089.6   205.1  5151.4  206.46
  5184.1  208.43  5229.1   209.4  5420.2  217.92  5491.1  219.56  5526.2  222.03
  5547.8  221.82  5625.5  224.32  5653.9  226.46  5682.2  226.19  5714.6  227.64
#Mann= 12 ,-1 , 0
  4579.6     .05       0  4621.8     .08       0    4676     .05       0
  4762.4     .08       0  4813.8     .05       0    4903     .08       0
  4951.7     .05       0  4999.8     .04       0  5005.8     .05       0
  5043.5     .08       0  5089.6     .05       0  5184.1     .08       0
Bank Sta=4999.8,5005.8
XS Rating Curve= 0 ,0
Exp/Cntr=0.3,0.1

Type RM Length L Ch R = 1 ,2118    ,507,507,507
BEGIN DESCRIPTION:
UNT011 IN NURI 5.0
END DESCRIPTION:
XS GIS Cut Line= 3
      2287261.28     13322554.94      2287506.52     13322815.38
      2288233.11     13323177.59
#Sta/Elev= 30
  4520.8  221.66  4802.5  208.71    4824  208.88  4876.1  205.43  4892.8  205.54
  4939.6  203.02  4956.4  199.41    4962  202.34  4969.3  198.46  4978.8  198.35
  4984.4  199.64  4988.6  192.74  4991.4  192.24  4994.6  192.74  5006.7  193.99
    5014  199.12  5023.5  200.81  5029.1  198.69  5036.3  201.62  5045.9  202.21
    5141  204.77  5282.1  211.63    5414   216.2  5521.5  219.03  5543.9  220.95
  5550.3  222.63    5611  222.93  5639.7   226.4  5672.6  225.28  5690.4  227.88
#Mann= 5 ,-1 , 0
  4520.8     .05       0  4892.8      .1       0  4988.6     .07       0
  4994.6      .1       0    5414     .05       0
Bank Sta=4988.6,4994.6
XS Rating Curve= 0 ,0
Exp/Cntr=0.3,0.1

Type RM Length L Ch R = 1 ,1611    ,366,366,366
BEGIN DESCRIPTION:
UNT011 IN NURI 4.0
END DESCRIPTION:
XS GIS Cut Line= 4
       2287217.9     13323015.05      2287430.57      13323264.6
      2287634.56     13323440.38      2287688.58     13324141.25
#Sta/Elev= 30
  4543.5   213.9  4623.8  210.95    4651  209.45  4664.8  210.29    4679  208.42
  4750.4  206.55    4779  204.12  4828.4  203.18  4868.9   200.6  4948.6  198.35
  4977.1  196.14  5002.6   189.4  5005.4   188.9  5008.6   189.4  5012.8  194.51
  5019.9   195.8  5026.5  197.77  5034.2  198.16  5136.9  198.49  5197.3  199.87
  5237.4  204.39  5244.6  203.43  5257.5   197.5  5287.6  193.98  5317.7  193.74
  5347.7   196.6  5374.9  201.21  5688.7  212.22  5728.9  214.62  5843.6  217.13
#Mann= 6 ,-1 , 0
  4543.5      .1       0  4623.8     .05       0  4868.9      .1       0
  5002.6     .07       0  5008.6      .1       0  5136.9     .05       0
#XS Ineff= 1 ,-1
 5236.25  5502.5  204.39
Permanent Ineff=
       F
Bank Sta=4977.1,5019.9
XS Rating Curve= 0 ,0
Exp/Cntr=0.3,0.1

Type RM Length L Ch R = 1 ,1245    ,393,393,393
BEGIN DESCRIPTION:
UNT011 IN NURI 3.0
END DESCRIPTION:
XS GIS Cut Line= 4
      2287107.65     13323069.27      2287131.95     13323326.23
      2287440.98     13323895.68      2287618.07     13324166.52
#Sta/Elev= 30
  4413.4  214.55  4477.8  211.78  4601.8  205.74  4621.9  206.04  4669.3  202.53
  4706.4  202.52  4735.4  199.84  4802.6     199  4860.9  196.43  4904.6  196.37
  4926.5   194.3  4933.9  191.86  4948.3  194.25  4964.5  190.47  4970.2  191.84
  4986.4  191.73  4999.2  187.16  5001.9  186.66  5005.2  187.16  5013.9  192.63
  5030.1  196.15  5068.1   196.6  5097.9  198.88  5117.5  198.95  5149.9  202.34
  5184.2  202.87  5193.6  204.61  5215.4  204.29  5360.9   211.3    5643  217.71
#Mann= 6 ,-1 , 0
  4413.4      .1       0  4477.8     .05       0  4802.6      .1       0
  4999.2     .07       0  5005.2      .1       0  5097.9     .05       0
Bank Sta=4999.2,5005.2
XS Rating Curve= 0 ,0
Exp/Cntr=0.3,0.1

Type RM Length L Ch R = 1 ,852     ,551,551,551
BEGIN DESCRIPTION:
UNT011 IN NURI 2.0
END DESCRIPTION:
XS GIS Cut Line= 4
      2286934.03     13323152.63       2286850.7     13323458.18
      2286954.87     13323885.26      2287522.35     13324162.08
#Sta/Elev= 30
  4402.3  212.63  4436.8  210.98  4597.9  205.11  4624.3  203.23  4677.3  202.42
  4725.1  199.74  4748.5   199.9  4779.4  197.63  4861.7  195.88  4903.3  193.82
  4980.4  192.72  4985.6  190.74  4992.6  185.59  4995.3  185.09  4998.6  185.59
  5005.8  185.73  5016.1  189.94  5027.3  190.63  5036.7  193.23  5174.4  194.39
  5243.6   195.1  5283.1  196.91  5305.7  196.55  5350.7   198.6    5362  200.02
  5373.2  199.31  5484.4  203.73  5604.1  211.44    5618  210.46    5790  216.35
#Mann= 6 ,-1 , 0
  4402.3      .1       0  4436.8     .05       0  4903.3      .1       0
  4992.6     .07       0  4998.6      .1       0  5174.4     .05       0
Bank Sta=4992.6,4998.6
XS Rating Curve= 0 ,0
Exp/Cntr=0.3,0.1

Type RM Length L Ch R = 1 ,301     ,0,0,0
BEGIN DESCRIPTION:
UNT011 IN NURI 1.0
END DESCRIPTION:
XS GIS Cut Line= 4
      2286802.13     13323100.51      2286322.93     13323531.09
      2286461.82      13324055.4      2287503.14     13324260.19
#Sta/Elev= 30
  4110.6  211.21  4245.8  206.48  4316.8   202.4  4337.7  202.67  4366.1  200.24
  4475.1  195.82  4500.7  193.79  4649.4  190.04  4821.4  190.28  4967.7  188.87
    4978  187.94  4985.8   185.2  4990.9  187.06  4995.7  181.64  4998.5  181.14
  5001.7  181.64  5003.2  182.24    5026  189.13  5031.2  188.77  5040.1  190.76
  5093.2  191.41  5174.6  193.25    5216   192.4  5470.5  194.23  5710.6  193.68
  5758.5  194.44  5894.4  196.56  6169.5  208.88  6189.9  211.13  6358.5  216.36
#Mann= 10 ,-1 , 0
  4110.6      .1       0  4475.1     .05       0  4821.4      .1       0
  4995.7     .07       0  5001.7      .1       0  5003.2     .16       0
  5093.2      .1       0  5470.5     .05       0  5710.6      .1       0
  5758.5     .05       0
Bank Sta=4995.7,5001.7
XS Rating Curve= 0 ,0
Exp/Cntr=0.3,0.1

Chan Stop Cuts=-1
Use User Specified Reach Order=0
Composite Channel Slope=5