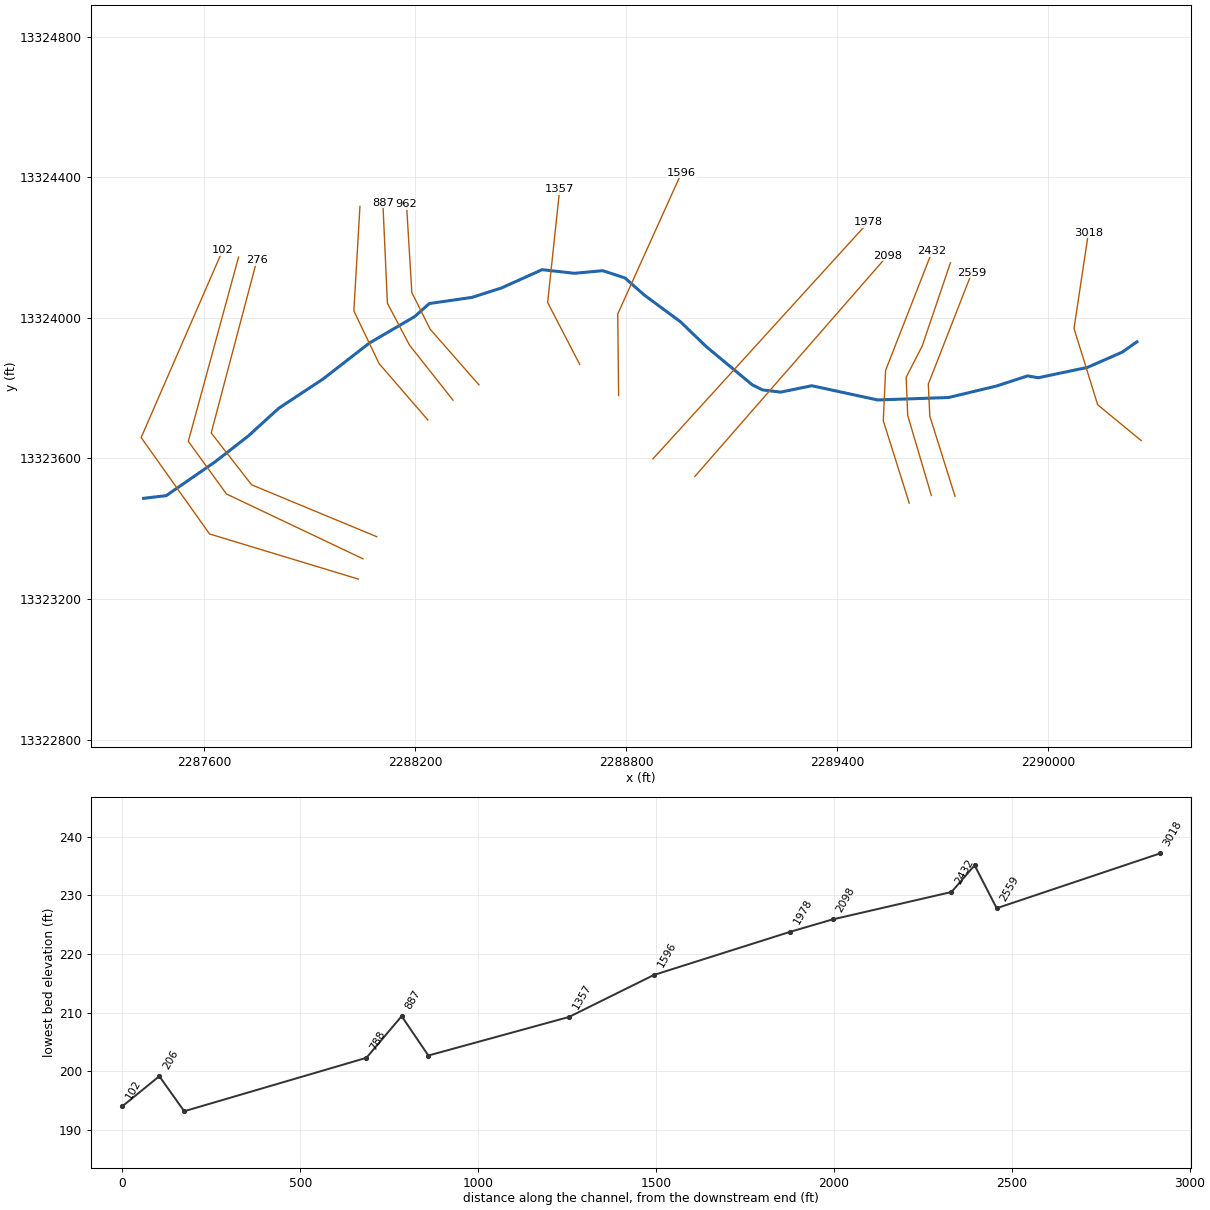
--- UNT012 IN NURI.prj (project) ---

Proj Title=UNT012 IN NURI Base Level Engineering
Current Plan=p01
Default Exp/Contr=0.3,0.1
English Units
Geom File=g01
Flow File=f01
Plan File=p01
Y Axis Title=Elevation
X Axis Title(PF)=Main Channel Distance
X Axis Title(XS)=Station
BEGIN DESCRIPTION:
UNT012 IN NURI
END DESCRIPTION:
DSS Export Rating Curves= 0
DSS Export Rating Curve Sorted= 0
DSS Export Volume Flow Curves= 0
DXF OffsetX= 0
DXF OffsetY= 0
DXF ScaleX= 1
DXF ScaleY= 10

--- UNT012 IN NURI.p01 (plan) ---

Plan Title=Multiple Run
Short Identifier=Multiple
Geom File=g01
Flow File=f01
Subcritical Flow
K Sum by GR= 0
Std Step Tol= 0.01
Critical Tol= 0.01
Num of Std Step Trials= 20
Max Error Tol= 0.3
Flow Tol Ratio= 0.001
Split Flow NTrial= 30
Split Flow Tol= 0.02
Split Flow Ratio= 0.02
Log Output Level= 0
Friction Slope Method= 1
Unsteady Friction Slope Method= 2
Unsteady Bridges Friction Slope Method= 1
Parabolic Critical Depth
Global Vel Dist=  1 , 1 , 1
Global Log Level= 0
CheckData=True
Encroach Param= -1, 0, 0, 0
BEGIN DESCRIPTION:
Multiple Run
END DESCRIPTION:

--- UNT012 IN NURI.f01 (steady flow) ---

Flow Title=Multiple
Number of Profiles=7
Profile Names=10-year,25-year,50-year,1pct_min,100-year,1pct_plu,500-year
River Rch & RM= UNT012 IN NURI,Reach-1,3018
     120     154     181     156     211     286     288
River Rch & RM= UNT012 IN NURI,Reach-1,1978
     164     220     264     234     316     427     455
River Rch & RM= UNT012 IN NURI,Reach-1,206
     770    1113    1408    1301    1760    2380    2765
Boundary for River Rch & Prof#=UNT012 IN NURI,Reach-1,1
Up Type=0
Dn Type=3
Dn Slope=0.005
Boundary for River Rch & Prof#=UNT012 IN NURI,Reach-1,2
Up Type=0
Dn Type=3
Dn Slope=0.005
Boundary for River Rch & Prof#=UNT012 IN NURI,Reach-1,3
Up Type=0
Dn Type=3
Dn Slope=0.005
Boundary for River Rch & Prof#=UNT012 IN NURI,Reach-1,4
Up Type=0
Dn Type=3
Dn Slope=0.005
Boundary for River Rch & Prof#=UNT012 IN NURI,Reach-1,5
Up Type=0
Dn Type=3
Dn Slope=0.005
Boundary for River Rch & Prof#=UNT012 IN NURI,Reach-1,6
Up Type=0
Dn Type=3
Dn Slope=0.005
Boundary for River Rch & Prof#=UNT012 IN NURI,Reach-1,7
Up Type=0
Dn Type=3
Dn Slope=0.005

--- UNT012 IN NURI.g01 (geometry) ---

Geom Title=Existing Conditions
Program Version=4.10

River Reach=UNT012 IN NURI  ,Reach-1
Reach XY= 30
      2290252.72     13323931.85      2290210.26      13323902.1
      2290111.82     13323859.02      2289972.23     13323829.62
      2289941.83     13323834.91      2289853.22     13323806.05
      2289717.11     13323773.41      2289515.02     13323766.47
      2289327.76     13323806.92      2289239.33     13323788.69
       2289188.1     13323794.85      2289158.56     13323809.41
      2289027.79     13323918.02      2288954.21     13323988.89
      2288851.13     13324065.06      2288796.34     13324113.62
      2288733.22     13324134.22      2288652.78     13324126.76
      2288560.68     13324137.07      2288445.58     13324085.22
      2288360.86     13324058.13      2288240.02     13324040.77
      2288197.66     13324003.27      2288069.19     13323928.27
      2287937.25      13323825.8      2287811.55     13323742.86
      2287725.44     13323664.38        2287631.     13323590.77
      2287491.41     13323494.25      2287427.11     13323486.59

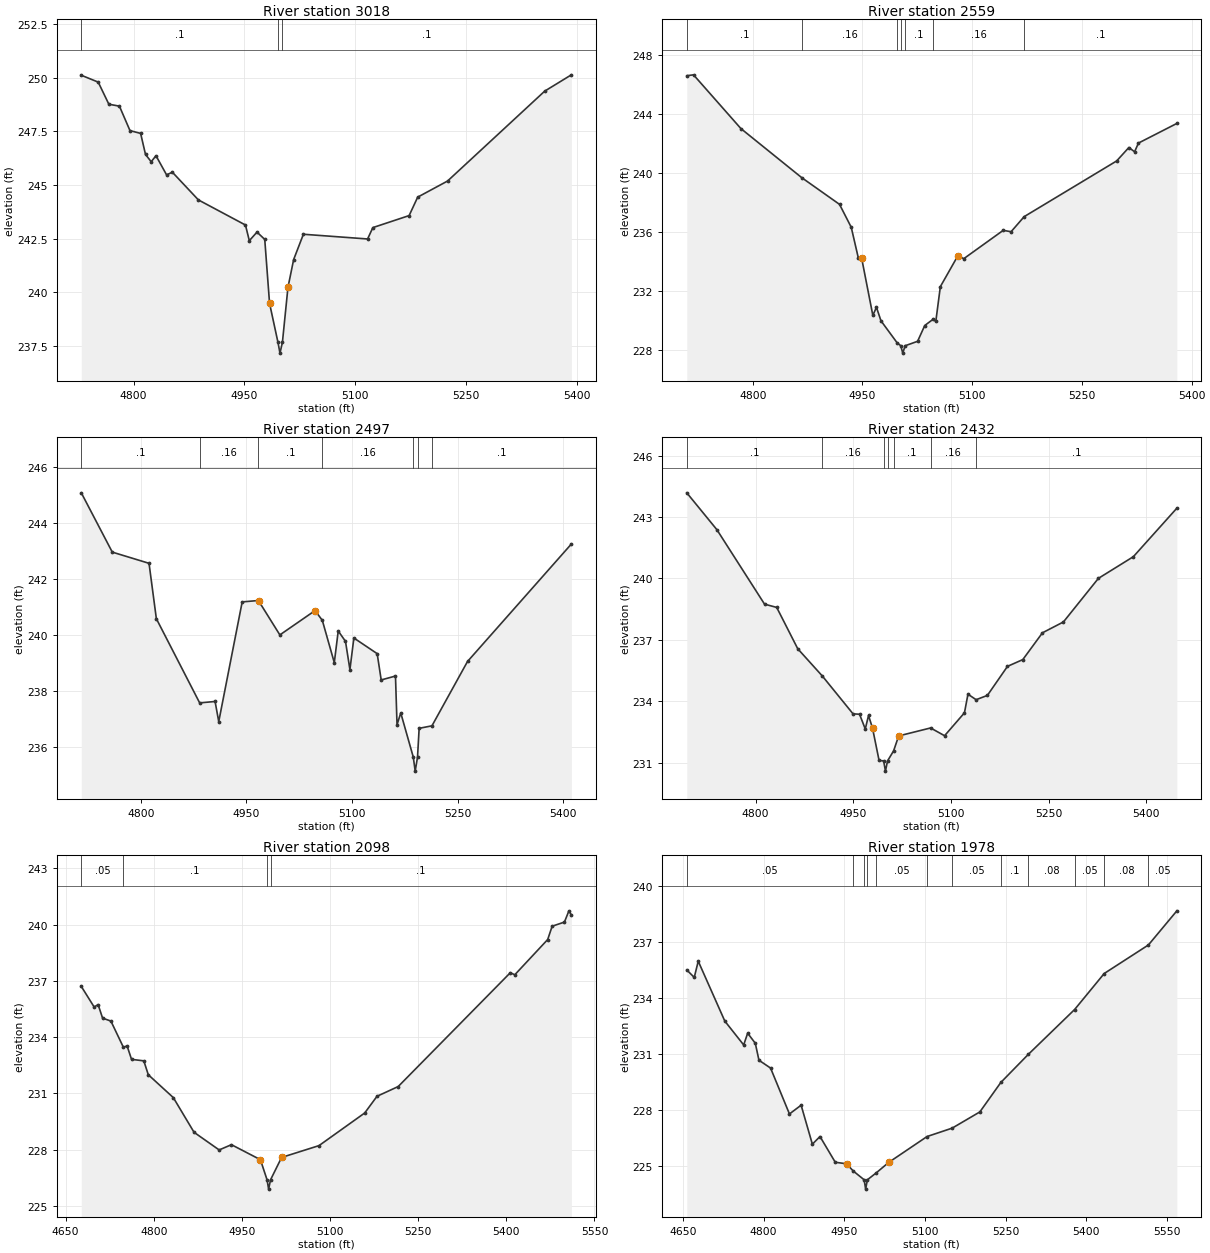
Type RM Length L Ch R = 1 ,3018    ,459,459,459
BEGIN DESCRIPTION:
UNT012 IN NURI 6.0
END DESCRIPTION:
XS GIS Cut Line= 4
      2290264.78     13323650.88      2290141.07     13323752.88
      2290073.79     13323969.89      2290114.91     13324242.57
#Sta/Elev= 30
  4729.3  250.12  4752.2   249.8  4766.6  248.77  4780.9  248.68  4795.2  247.54
  4809.6  247.41  4816.2  246.43  4823.9  246.09  4830.4  246.37  4844.7  245.48
  4852.6   245.6  4887.8  244.31  4951.5  243.14  4956.7  242.41  4967.1  242.81
  4977.6  242.47  4984.1  239.49  4995.5  237.67  4998.2  237.17  5001.5  237.67
    5009  240.23  5016.7  241.53  5029.9  242.71  5116.8  242.49  5123.9  243.02
    5173  243.58  5184.6  244.44    5225  245.19  5356.5  249.38  5392.6  250.14
#Mann= 3 ,-1 , 0
  4729.3      .1       0  4995.5     .07       0  5001.5      .1       0
Bank Sta=4984.1,5009
XS Rating Curve= 0 ,0
Exp/Cntr=0.3,0.1

Type RM Length L Ch R = 1 ,2559    ,62,62,62
BEGIN DESCRIPTION:
Mapping XS da61e716
END DESCRIPTION:
XS GIS Cut Line= 4
      2289735.26     13323492.44      2289663.64     13323720.33
       2289659.3     13323811.47      2289782.87     13324127.98
#Sta/Elev= 30
  4709.9  246.59  4719.1  246.65  4783.9  243.01    4867  239.69  4918.7  237.88
  4934.7  236.33  4944.3  234.27  4948.8  234.27  4964.2  230.37  4969.2  230.91
  4975.3     230  4997.4  228.51  5002.4  228.31  5005.1  227.81  5008.4  228.31
  5025.4  228.61  5035.2  229.68  5046.5   230.1  5050.3  229.96  5056.5  232.31
  5080.2  234.38  5088.7  234.21  5142.4  236.12  5153.2  236.03  5171.1  237.05
  5297.5  240.82  5314.2  241.73    5322  241.44  5327.3  242.03  5379.8  243.36
#Mann= 7 ,-1 , 0
  4709.9      .1       0    4867     .16       0  4997.4      .1       0
  5002.4     .07       0  5008.4      .1       0  5046.5     .16       0
  5171.1      .1       0
Bank Sta=4948.8,5080.2
XS Rating Curve= 0 ,0
Exp/Cntr=0.3,0.1

Type RM Length L Ch R = 1 ,2497    ,65,65,65
BEGIN DESCRIPTION:
Mapping XS 7ffa8ffd
END DESCRIPTION:
XS GIS Cut Line= 5
      2289667.99     13323494.61       2289600.7      13323722.5
      2289596.36     13323831.01      2289641.94     13323919.98
      2289722.24     13324156.55
#Sta/Elev= 30
  4715.5  245.09  4759.5  242.97  4811.7  242.57  4822.1  240.59  4883.6  237.58
  4905.5  237.63  4910.7  236.91    4944  241.19  4966.9  241.24  4967.5  241.22
  4997.5  240.01  5047.5  240.88  5057.8  240.53  5074.8  239.02  5080.4  240.15
  5090.7  239.78    5097  238.77  5102.6   239.9  5135.7  239.34  5141.4   238.4
  5161.7  238.54  5163.9   236.8  5169.2  237.22    5187  235.64  5189.7  235.14
    5193  235.64  5195.3  236.67  5213.5  236.76    5264  239.06  5411.5  243.26
#Mann= 7 ,-1 , 0
  4715.5      .1       0  4883.6     .16       0  4966.9      .1       0
  5057.8     .16       0    5187     .07       0    5193     .16       0
  5213.5      .1       0
Bank Sta=4967.5,5047.5
XS Rating Curve= 0 ,0
Exp/Cntr=0.3,0.1

Type RM Length L Ch R = 1 ,2432    ,334,334,334
BEGIN DESCRIPTION:
Mapping XS 84dc4494
END DESCRIPTION:
XS GIS Cut Line= 4
      2289605.05     13323472.92      2289531.26     13323707.31
      2289537.77     13323850.54      2289670.15     13324189.07
#Sta/Elev= 30
  4694.4  244.18  4740.6  242.38  4813.8  238.74  4832.5  238.58  4864.8  236.56
  4902.5  235.23  4949.7  233.38  4959.7  233.36  4968.5  232.64  4973.5   233.3
  4979.7  232.67  4989.7   231.1  4996.7  231.08  4999.5  230.58  5002.7  231.08
    5012  231.57  5019.8   232.3  5068.8  232.69  5090.3  232.31  5120.8  233.43
  5126.2  234.34  5138.7  234.07    5156  234.28  5186.9   235.7  5210.4  236.03
  5240.6  237.34  5272.8  237.87  5326.5     240  5380.2  241.06    5447  243.43
#Mann= 7 ,-1 , 0
  4694.4      .1       0  4902.5     .16       0  4996.7     .07       0
  5002.7     .16       0    5012      .1       0  5068.8     .16       0
  5138.7      .1       0
Bank Sta=4979.7,5019.8
XS Rating Curve= 0 ,0
Exp/Cntr=0.3,0.1

Type RM Length L Ch R = 1 ,2098    ,120,120,120
BEGIN DESCRIPTION:
UNT012 IN NURI 5.0
END DESCRIPTION:
XS GIS Cut Line= 2
      2288995.22     13323548.87      2289543.49     13324177.32
#Sta/Elev= 30
  4676.7  236.71  4698.6  235.61  4705.3  235.74  4712.9  235.02  4727.1  234.86
  4748.4  233.46  4754.6  233.54  4762.2  232.82  4783.1  232.74  4790.7     232
  4833.3  230.78  4868.6  228.93  4911.3  227.99  4932.2  228.27  4981.5  227.47
  4992.8   226.4  4995.5   225.9  4998.8   226.4  5017.6  227.59  5081.2  228.22
    5159  229.96  5179.9  230.85    5216  231.37  5406.8  237.44  5414.4  237.33
  5470.4  239.21    5478  239.92  5498.9  240.14  5506.5  240.74  5510.7  240.52
#Mann= 4 ,-1 , 0
  4676.7     .05       0  4748.4      .1       0  4992.8     .07       0
  4998.8      .1       0
Bank Sta=4981.5,5017.6
XS Rating Curve= 0 ,0
Exp/Cntr=0.3,0.1

Type RM Length L Ch R = 1 ,1978    ,382,382,382
BEGIN DESCRIPTION:
UNT012 IN NURI 4.0
END DESCRIPTION:
XS GIS Cut Line= 2
      2288875.88      13323598.8      2289489.21     13324272.82
#Sta/Elev= 30
  4657.2  235.52  4671.1  235.12  4678.5  235.99  4727.9  232.78    4763   231.5
  4770.4  232.13  4784.6  231.59  4791.4  230.68    4813  230.26  4848.1   227.8
  4869.8  228.27  4890.7  226.18  4904.9  226.59  4933.3  225.21  4954.2  225.13
  4966.8  224.74    4987  224.27  4989.8  223.77    4993  224.27  5009.4  224.64
  5032.6   225.2    5104  226.59  5150.7  227.04  5202.2  227.91  5241.2  229.49
  5292.1  230.99  5378.4   233.4  5433.4  235.33  5515.6  236.86  5568.5  238.69
#Mann= 12 ,-1 , 0
  4657.2     .05       0  4966.8      .1       0    4987     .07       0
    4993      .1       0  5009.4     .05       0    5104      .1       0
  5150.7     .05       0  5241.2      .1       0  5292.1     .08       0
  5378.4     .05       0  5433.4     .08       0  5515.6     .05       0
Bank Sta=4954.2,5032.6
XS Rating Curve= 0 ,0
Exp/Cntr=0.3,0.1

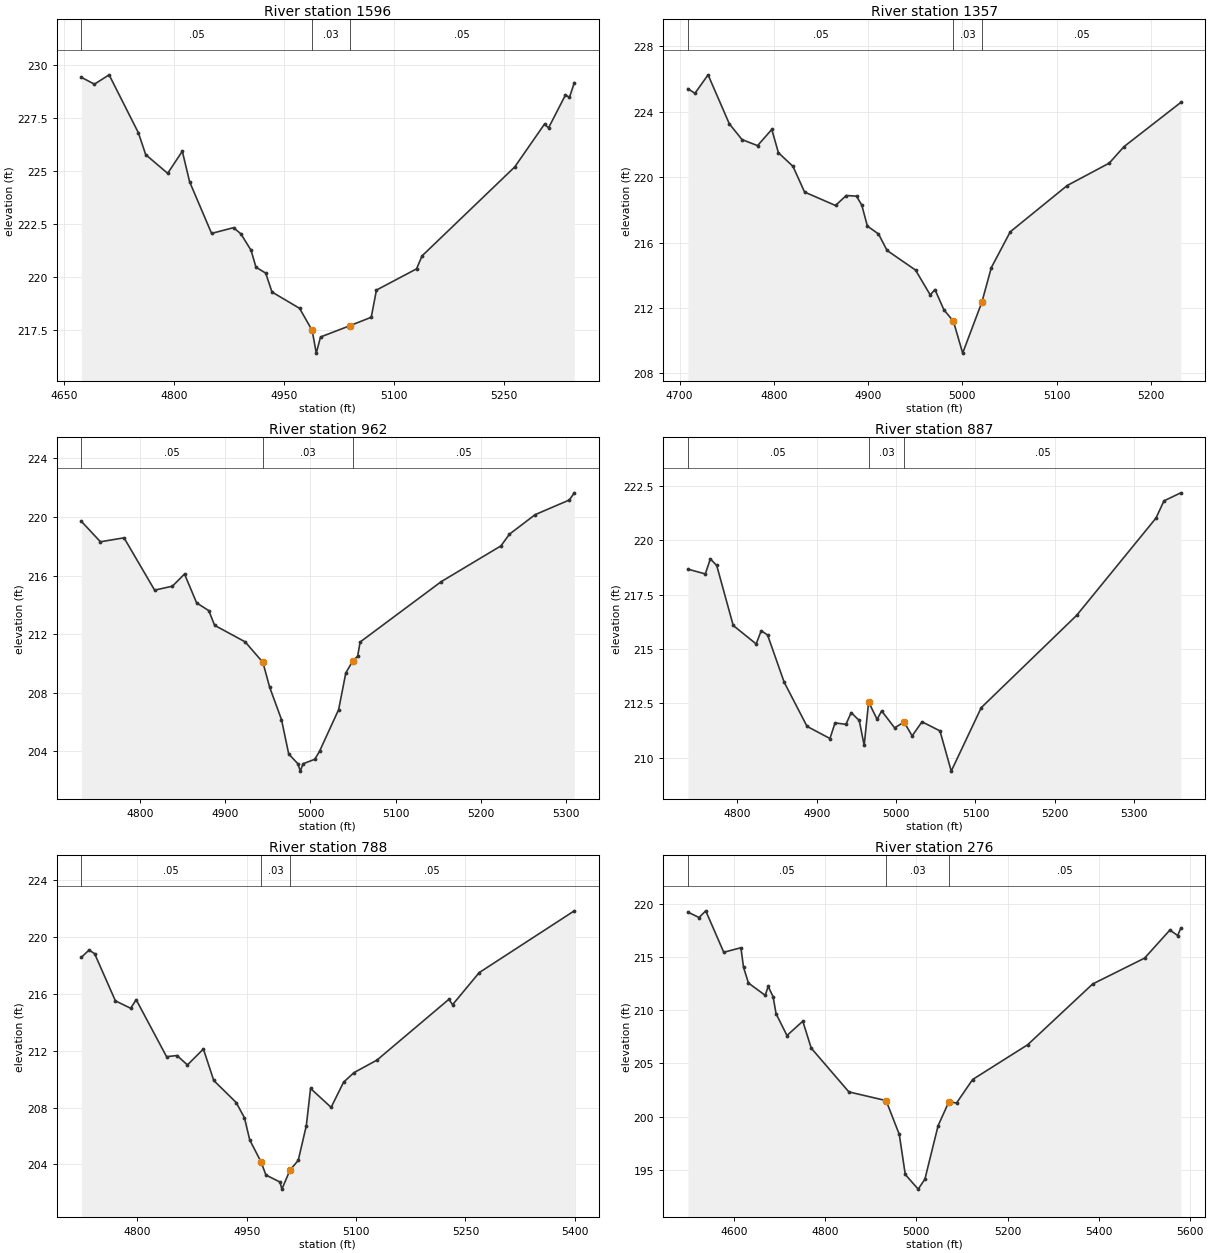
Type RM Length L Ch R = 1 ,1596    ,239,239,239
BEGIN DESCRIPTION:
Mapping XS fc1704c7
END DESCRIPTION:
XS GIS Cut Line= 3
       2288778.4     13323779.06       2288775.8     13324010.86
      2288957.51     13324413.22
#Sta/Elev= 30
  4673.4  229.41  4691.2  229.09  4711.2  229.53  4751.2   226.8  4761.2  225.77
  4791.2  224.89  4811.2  225.93  4821.2  224.49  4851.2  222.06  4881.2  222.33
  4891.2  222.04  4905.2  221.26  4911.8  220.47  4925.1  220.19  4933.7   219.3
  4971.4  218.53  4988.6  217.49  4994.2  216.42    5000  217.18  5040.7  217.72
  5069.3  218.11  5076.4  219.39  5131.2  220.39  5138.7     221  5265.3  225.19
    5306  227.21  5311.5  227.03  5334.6  228.58  5340.1  228.47  5346.7  229.16
#Mann= 3 , 0 , 0
  4673.4     .05       0  4988.6     .03       0  5040.7     .05       0
Bank Sta=4988.6,5040.7
XS Rating Curve= 0 ,0
Exp/Cntr=0.3,0.1

Type RM Length L Ch R = 1 ,1357    ,395,395,395
BEGIN DESCRIPTION:
UNT012 IN NURI 3.0
END DESCRIPTION:
XS GIS Cut Line= 3
      2288667.56     13323867.86       2288576.4     13324043.68
      2288610.84      13324366.7
#Sta/Elev= 30
  4708.8  225.41  4716.3  225.13  4730.2  226.26  4752.7  223.27  4766.2   222.3
  4782.7  221.93  4797.8  222.92  4804.8   221.5  4820.3  220.66  4832.6  219.09
  4865.4  218.27  4876.8  218.88  4887.7  218.84  4893.3  218.29  4899.2  217.01
    4911  216.53  4920.1  215.52  4950.3  214.32  4965.9   212.8  4970.9  213.13
  4980.4  211.89  4990.5  211.19  5000.3  209.24  5020.7  212.36  5030.7  214.47
  5050.8  216.66  5111.2  219.49  5155.8  220.86  5171.5  221.87  5231.7  224.57
#Mann= 3 , 0 , 0
  4708.8     .05       0  4990.5     .03       0  5020.7     .05       0
Bank Sta=4990.5,5020.7
XS Rating Curve= 0 ,0
Exp/Cntr=0.3,0.1

Type RM Length L Ch R = 1 ,962     ,75,75,75
BEGIN DESCRIPTION:
UNT012 IN NURI 2.0
END DESCRIPTION:
XS GIS Cut Line= 4
       2288381.1     13323809.29       2288242.2     13323967.72
      2288190.11     13324071.89      2288174.97     13324322.78
#Sta/Elev= 30
  4731.2   219.7  4753.5  218.31  4781.2  218.58  4817.1  215.01    4838  215.28
  4852.2  216.11  4866.4  214.14  4880.7  213.61  4887.5  212.61  4923.4  211.48
  4944.2  210.08  4952.1  208.39    4966  206.18  4974.5  203.83  4985.3  203.16
  4988.1  202.66  4991.3  203.16  5005.1  203.47  5010.7  204.02  5033.1  206.86
  5041.5  209.36  5049.8  210.19  5055.4   210.5  5058.3  211.47  5153.5  215.59
  5223.6  218.03  5233.6  218.83  5263.7  220.16  5303.8  221.16  5309.7  221.65
#Mann= 3 , 0 , 0
  4731.2     .05       0  4944.2     .03       0  5049.8     .05       0
Bank Sta=4944.2,5049.8
XS Rating Curve= 0 ,0
Exp/Cntr=0.3,0.1

Type RM Length L Ch R = 1 ,887     ,99,99,99
BEGIN DESCRIPTION:
Mapping XS 8e7afb6c
END DESCRIPTION:
XS GIS Cut Line= 4
      2288307.29     13323765.91       2288183.6     13323922.15
      2288120.67     13324041.51      2288107.65     13324328.01
#Sta/Elev= 30
  4737.7  218.67  4759.6  218.45    4766  219.14    4774  218.84  4794.8  216.08
  4823.7  215.23  4830.1  215.84  4838.1  215.64    4859  213.47  4887.8  211.44
  4916.7  210.88  4923.1   211.6  4936.8  211.53  4943.4  212.07  4953.6  211.71
  4959.8  210.56  4965.4  212.56  4976.1  211.76  4981.8  212.15  4998.2  211.37
  5010.1  211.64  5020.2     211  5032.7  211.65  5055.3  211.23  5069.5  209.38
  5107.3   212.3  5227.4  216.54  5327.5  221.02  5337.5  221.81  5358.7  222.18
#Mann= 3 , 0 , 0
  4737.7     .05       0  4965.4     .03       0  5010.1     .05       0
Bank Sta=4965.4,5010.1
XS Rating Curve= 0 ,0
Exp/Cntr=0.3,0.1

Type RM Length L Ch R = 1 ,788     ,512,512,512
BEGIN DESCRIPTION:
Mapping XS 3a76bee7
END DESCRIPTION:
XS GIS Cut Line= 4
      2288235.69     13323709.47       2288096.8     13323870.07
      2288025.18     13324019.81      2288042.54     13324317.09
#Sta/Elev= 30
  4723.3  218.55  4733.8  219.06  4741.4   218.8  4769.9  215.49  4790.8  214.97
  4798.4  215.57  4840.1  211.57  4854.4  211.65  4868.7  210.99  4890.6  212.11
  4904.8   209.9  4935.6  208.35  4946.9  207.28  4954.2  205.72  4969.6  204.19
  4976.4  203.26  4995.6  202.77  4998.3  202.27  5009.4  203.61  5020.7  204.29
  5031.8  206.73  5037.6  209.34  5065.8  208.01  5082.9  209.78  5097.2  210.45
  5128.7  211.33  5227.4   215.6  5232.4  215.22  5268.9  217.47  5399.4  221.81
#Mann= 3 , 0 , 0
  4723.3     .05       0  4969.6     .03       0  5009.4     .05       0
Bank Sta=4969.6,5009.4
XS Rating Curve= 0 ,0
Exp/Cntr=0.3,0.1

Type RM Length L Ch R = 1 ,276     ,70,70,70
BEGIN DESCRIPTION:
Mapping XS 1d542971
END DESCRIPTION:
XS GIS Cut Line= 4
      2288090.28     13323377.45      2287734.38     13323525.02
      2287619.37     13323672.59      2287749.14     13324163.55
#Sta/Elev= 30
  4499.3  219.28  4523.7  218.77  4538.4   219.4  4577.9  215.49  4615.5  215.92
  4621.2  214.08    4632  212.59  4668.7  211.43  4675.3  212.27  4686.1  211.29
  4692.5   209.7  4716.4  207.64  4751.1  208.99  4769.6  206.45  4852.1  202.32
  4933.7   201.5  4962.6  198.31  4975.7  194.53    5004  193.15  5018.7  194.09
  5047.7  199.14  5071.2  201.38  5088.2  201.28  5123.3  203.49    5244  206.77
  5386.4   212.5  5500.2  214.94  5555.7  217.59  5572.6  217.07  5579.5  217.75
#Mann= 3 , 0 , 0
  4499.3     .05       0  4933.7     .03       0  5071.2     .05       0
Bank Sta=4933.7,5071.2
XS Rating Curve= 0 ,0
Exp/Cntr=0.3,0.1

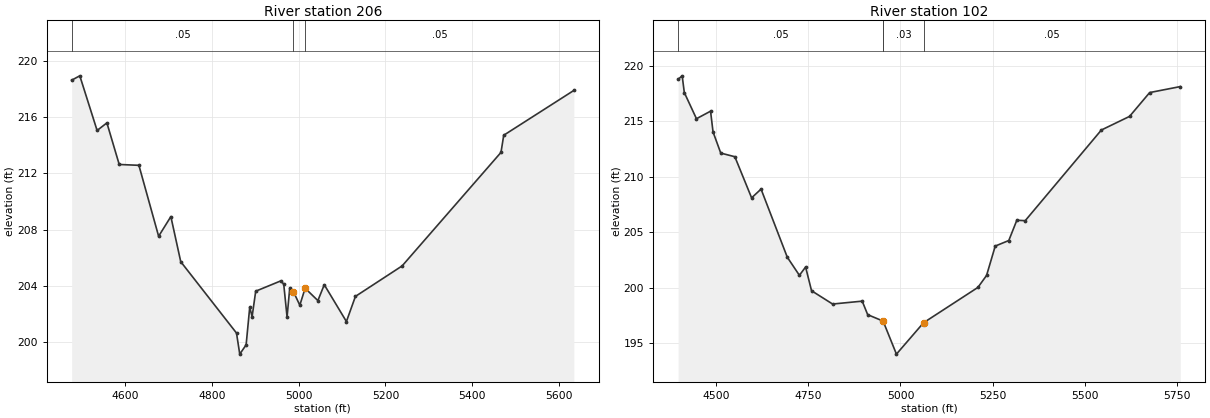
Type RM Length L Ch R = 1 ,206     ,104,104,104
BEGIN DESCRIPTION:
Mapping XS 07bd21ca
END DESCRIPTION:
XS GIS Cut Line= 4
       2288051.2     13323314.52      2287662.77     13323498.97
      2287554.26     13323648.71      2287697.21     13324172.85
#Sta/Elev= 30
  4476.4  218.63  4495.2  218.94  4535.1  215.05  4557.7  215.59  4586.1  212.63
  4631.5  212.57    4677  207.52  4705.2  208.92    4728  205.71  4856.6  200.63
  4864.1  199.13  4878.8  199.79  4887.1  202.47  4892.6   201.8  4900.9  203.61
  4958.5  204.34  4965.5  204.12  4973.2  201.77  4979.4  203.84  4987.9  203.58
  5002.6  202.61  5014.9  203.82  5044.3  202.94    5059  204.07  5110.1  201.45
  5130.9  203.24  5238.6  205.41  5466.6  213.49  5472.9  214.71  5634.6   217.9
#Mann= 3 , 0 , 0
  4476.4     .05       0  4987.9     .03       0  5014.9     .05       0
Bank Sta=4987.9,5014.9
XS Rating Curve= 0 ,0
Exp/Cntr=0.3,0.1

Type RM Length L Ch R = 1 ,102     ,0,0,0
BEGIN DESCRIPTION:
UNT012 IN NURI 1.0
END DESCRIPTION:
XS GIS Cut Line= 4
      2288038.23     13323256.78      2287614.59     13323385.26
      2287420.15     13323659.56      2287652.21     13324192.95
#Sta/Elev= 30
  4397.6  218.79  4408.6   219.1  4414.4  217.59  4447.3  215.23  4485.5  215.91
  4492.2  214.04  4513.1  212.13  4551.3   211.8  4596.7  208.09  4622.3  208.88
  4693.3  202.74  4726.2   201.1    4743  201.85  4759.1  199.71  4816.1  198.51
  4896.4  198.77  4911.2  197.55    4953  196.97  4989.1  193.99  5062.5  196.82
  5209.9  200.01  5233.3  201.09  5256.8  203.74  5293.5  204.24  5315.3  206.07
    5338  206.03  5544.3  214.21  5620.7  215.44  5675.2  217.59  5758.2  218.13
#Mann= 4 ,-1 , 0
  4397.6     .05       0    4953      .1       0    4953     .03       0
  5062.5     .05       0
Bank Sta=4953,5062.5
XS Rating Curve= 0 ,0
Exp/Cntr=0.3,0.1

Chan Stop Cuts=-1
Use User Specified Reach Order=0
Composite Channel Slope=5