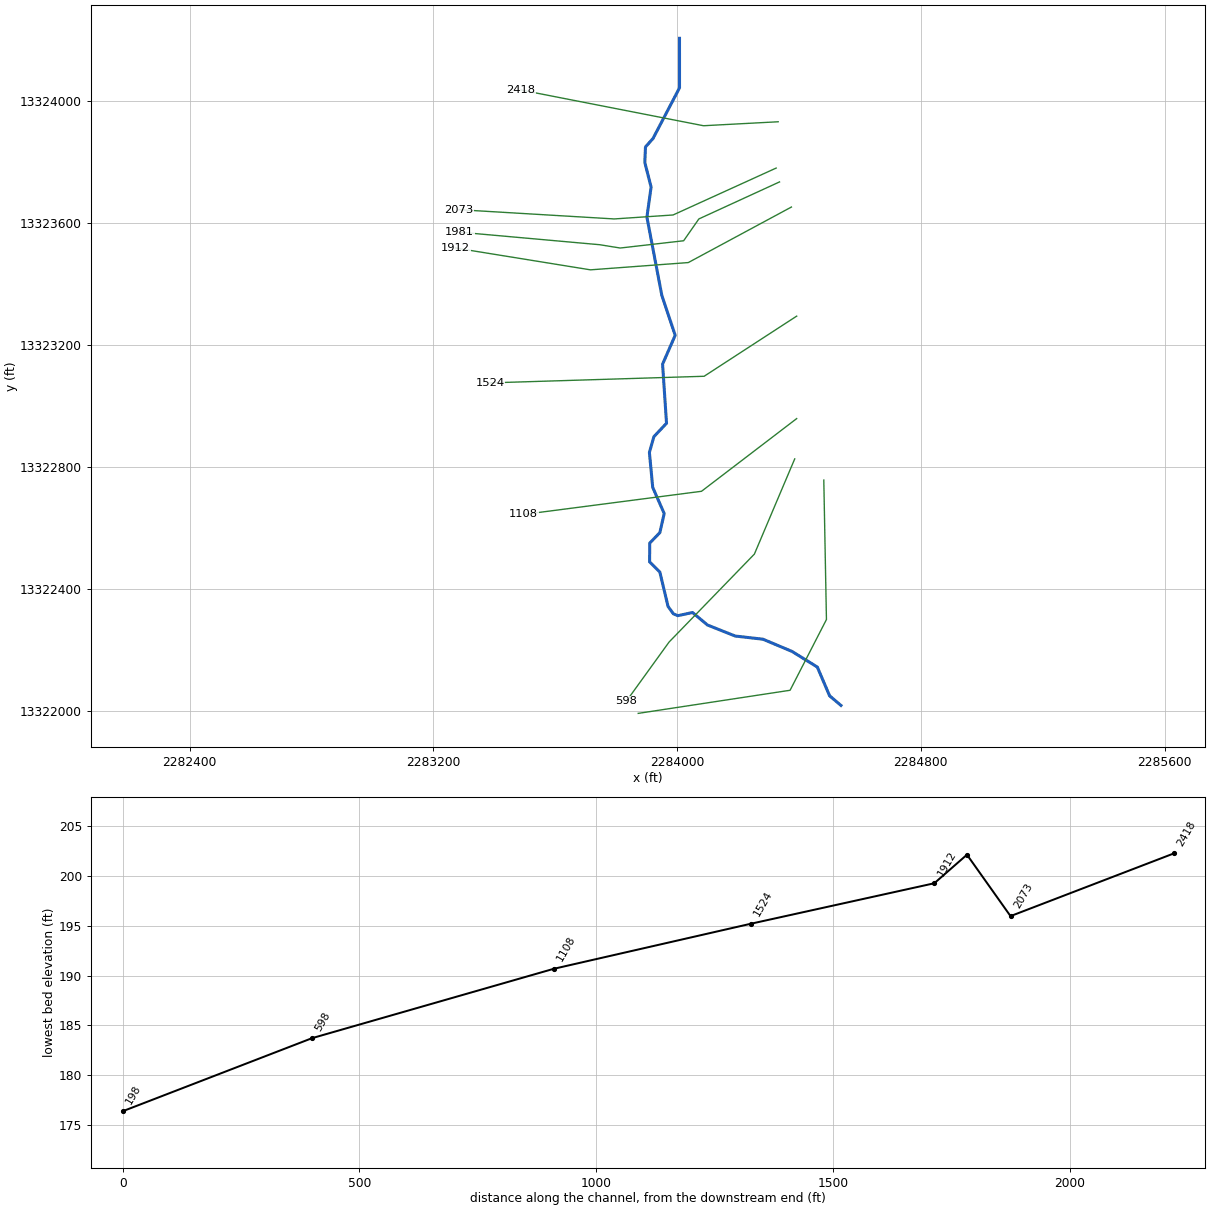
--- UNT013 IN NURI.prj (project) ---

Proj Title=UNT013 IN NURI Base Level Engineering
Current Plan=p01
Default Exp/Contr=0.3,0.1
English Units
Geom File=g01
Flow File=f01
Plan File=p01
Y Axis Title=Elevation
X Axis Title(PF)=Main Channel Distance
X Axis Title(XS)=Station
BEGIN DESCRIPTION:
UNT013 IN NURI
END DESCRIPTION:
DSS Export Rating Curves= 0
DSS Export Rating Curve Sorted= 0
DSS Export Volume Flow Curves= 0
DXF OffsetX= 0
DXF OffsetY= 0
DXF ScaleX= 1
DXF ScaleY= 10

--- UNT013 IN NURI.p01 (plan) ---

Plan Title=Multiple Run
Short Identifier=Multiple
Geom File=g01
Flow File=f01
Subcritical Flow
K Sum by GR= 0
Std Step Tol= 0.01
Critical Tol= 0.01
Num of Std Step Trials= 20
Max Error Tol= 0.3
Flow Tol Ratio= 0.001
Split Flow NTrial= 30
Split Flow Tol= 0.02
Split Flow Ratio= 0.02
Log Output Level= 0
Friction Slope Method= 1
Unsteady Friction Slope Method= 2
Unsteady Bridges Friction Slope Method= 1
Parabolic Critical Depth
Global Vel Dist=  1 , 1 , 1
Global Log Level= 0
CheckData=True
Encroach Param= -1, 0, 0, 0
BEGIN DESCRIPTION:
Multiple Run
END DESCRIPTION:

--- UNT013 IN NURI.f01 (steady flow) ---

Flow Title=Multiple
Program Version=4.10
Number of Profiles= 7
Profile Names=10-year,25-year,50-year,1pct_min,100-year,1pct_plu,500-year
River Rch & RM=UNT013 IN NURI,Reach-1         ,2418
     106     139     166     146     197     267     282
Boundary for River Rch & Prof#=UNT013 IN NURI,Reach-1         , 1
Up Type= 0
Dn Type= 3
Dn Slope=0.005
Boundary for River Rch & Prof#=UNT013 IN NURI,Reach-1         , 2
Up Type= 0
Dn Type= 3
Dn Slope=0.005
Boundary for River Rch & Prof#=UNT013 IN NURI,Reach-1         , 3
Up Type= 0
Dn Type= 3
Dn Slope=0.005
Boundary for River Rch & Prof#=UNT013 IN NURI,Reach-1         , 4
Up Type= 0
Dn Type= 3
Dn Slope=0.005
Boundary for River Rch & Prof#=UNT013 IN NURI,Reach-1         , 5
Up Type= 0
Dn Type= 3
Dn Slope=0.005
Boundary for River Rch & Prof#=UNT013 IN NURI,Reach-1         , 6
Up Type= 0
Dn Type= 3
Dn Slope=0.005
Boundary for River Rch & Prof#=UNT013 IN NURI,Reach-1         , 7
Up Type= 0
Dn Type= 3
Dn Slope=0.005
DSS Import GetInterval= 0
DSS Import GetPeak= 0
DSS Import FillOption= 0

--- UNT013 IN NURI.g01 (geometry) ---

Geom Title=Existing Conditions

River Reach=UNT013 IN NURI,Reach-1
Reach XY= 30
      2284007.64     13324206.89      2284007.72     13324044.44
      2283920.89     13323878.43      2283895.93     13323850.21
      2283893.76     13323799.22      2283914.38     13323718.92
      2283900.66     13323619.79      2283949.67     13323362.76
      2283993.48     13323231.96      2283952.06     13323137.25
      2283965.04     13322943.23      2283923.53     13322899.17
      2283908.82     13322847.38      2283919.70     13322732.82
      2283957.38     13322646.83      2283943.12     13322584.06
      2283909.93     13322549.95      2283909.43     13322488.24
      2283943.17     13322454.42      2283970.06     13322341.83
      2283987.64     13322317.55      2284002.27     13322311.60
      2284050.43     13322321.88      2284099.47     13322280.92
      2284190.51     13322244.73      2284281.60     13322234.30
      2284376.70     13322194.34      2284460.07     13322142.91
      2284500.40     13322048.50      2284537.72     13322016.85

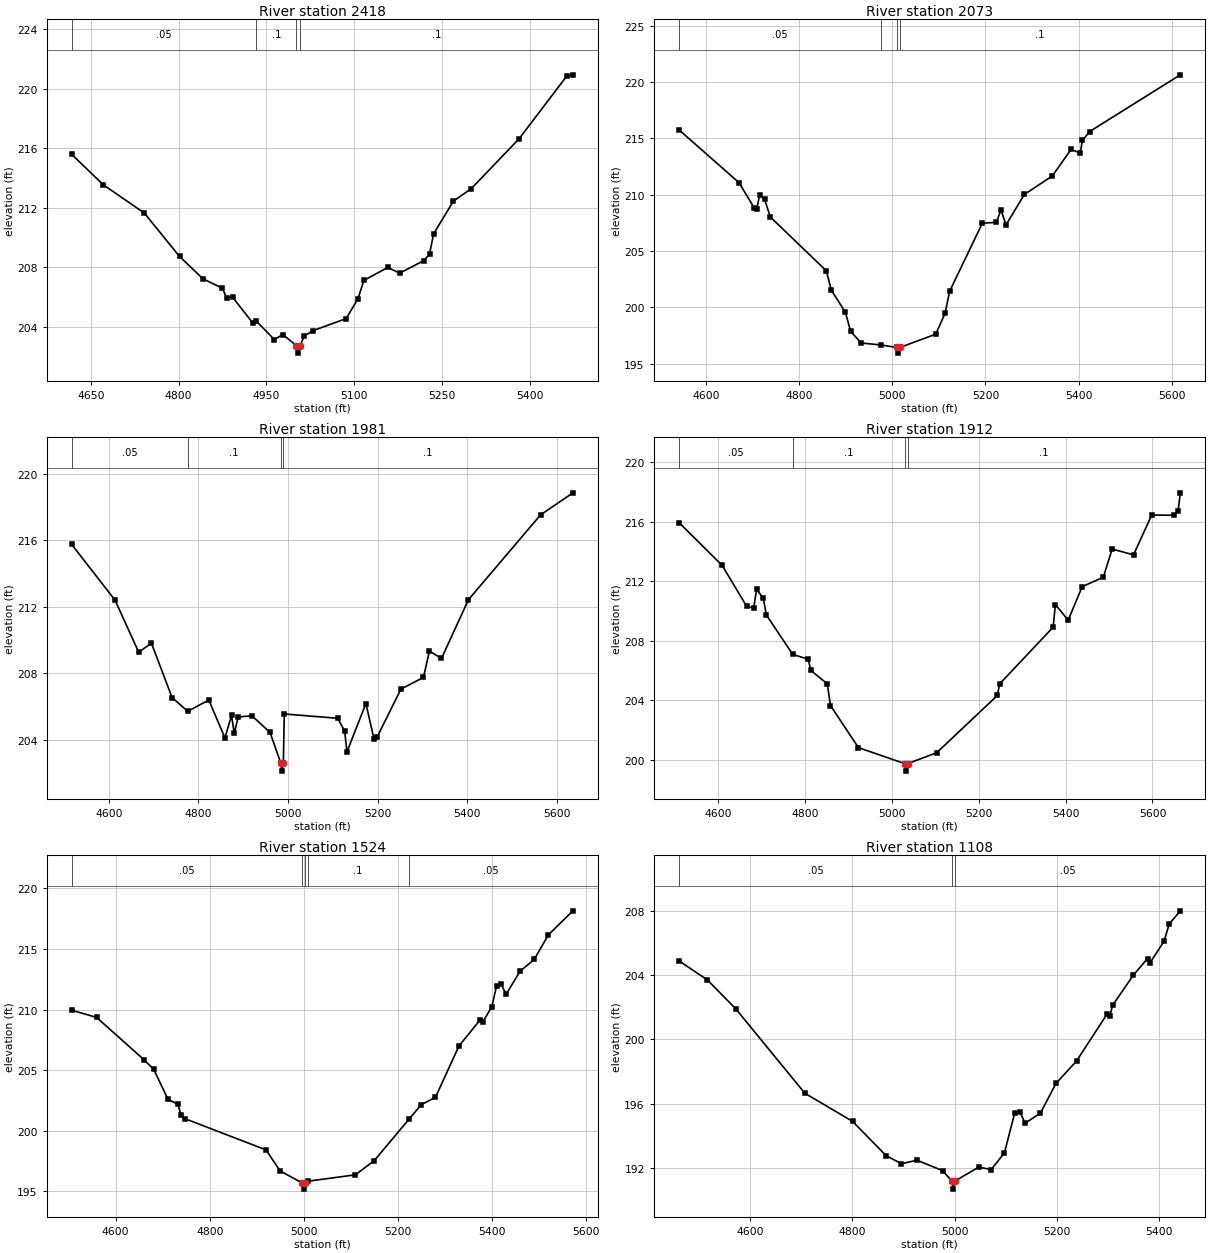
Type RM Length L Ch R = 1,2418,345,345,345
BEGIN DESCRIPTION:
UNT013 IN NURI 6.0
END DESCRIPTION:
XS GIS Cut Line= 3
      2284331.62     13323933.00      2284086.38     13323919.98
      2283487.42     13324037.17
#Sta/Elev= 30
  4617.4  215.60  4671.4  213.55  4741.5  211.65  4801.6  208.73  4841.6  207.23
  4874.8  206.59  4882.0  205.95  4892.2  205.99  4926.3  204.28  4932.6  204.39
  4963.5  203.14  4977.9  203.48  5001.3  202.73  5004.0  202.23  5007.3  202.73
  5014.5  203.37  5029.4  203.74  5086.0  204.55  5106.2  205.88  5116.4  207.12
  5157.1  207.99  5177.5  207.61  5218.3  208.44  5228.4  208.87  5235.4  210.25
  5269.2  212.45  5299.8  213.29  5381.3  216.64  5462.8  220.86  5473.3  220.94
#Mann=4,-1,0
  4617.4    0.05       0  4932.6     0.1       0  5001.3    0.07       0
  5007.3     0.1       0
Bank Sta=5001.3,5007.3
Exp/Cntr=0.3,0.1

Type RM Length L Ch R = 1,2073,92,92,92
BEGIN DESCRIPTION:
UNT013 IN NURI 5.0
END DESCRIPTION:
XS GIS Cut Line= 4
      2284325.06     13323781.08      2283986.55     13323627.01
      2283793.41     13323613.99      2283283.41     13323644.37
#Sta/Elev= 30
  4542.2  215.76  4671.1  211.07  4703.9  208.82  4709.4  208.78  4715.1  209.94
  4726.1  209.61  4738.0  208.04  4858.8  203.24  4868.9  201.56  4899.4  199.58
  4910.7  197.89  4933.0  196.85  4976.5  196.67  5010.2  196.45  5012.9  195.95
  5016.2  196.45  5093.4  197.63  5113.4  199.48  5123.4  201.45  5193.5  207.48
  5223.6  207.55  5233.6  208.66  5244.3  207.32  5283.7  210.03  5343.8  211.67
  5383.9  214.02  5403.5  213.71  5408.5  214.82  5423.9  215.61  5618.6  220.64
#Mann=4,-1,0
  4542.2    0.05       0  4976.5     0.1       0  5010.2    0.07       0
  5016.2     0.1       0
Bank Sta=5010.2,5016.2
Exp/Cntr=0.3,0.1

Type RM Length L Ch R = 1,1981,69,69,69
BEGIN DESCRIPTION:
Mapping XS 22ad6b40
END DESCRIPTION:
XS GIS Cut Line= 6
      2284335.97     13323735.53      2284071.19     13323613.99
      2284021.28     13323542.38      2283812.94     13323518.51
      2283745.67     13323529.36      2283285.58     13323570.59
#Sta/Elev= 30
  4517.1  215.75  4614.2  212.38  4666.7  209.26  4695.2  209.80  4741.2  206.53
  4776.2  205.70  4823.2  206.38  4859.0  204.10  4873.9  205.45  4879.9  204.38
  4888.7  205.36  4919.4  205.43  4959.7  204.43  4983.5  202.60  4986.3  202.10
  4989.5  202.60  4991.5  205.54  5110.7  205.28  5126.2  204.51  5131.3  203.26
  5173.6  206.17  5191.6  204.04  5199.1  204.18  5251.8  207.04  5302.0  207.74
  5315.3  209.33  5342.2  208.88  5402.4  212.42  5563.1  217.52  5635.5  218.85
#Mann=4,-1,0
  4517.1    0.05       0  4776.2     0.1       0  4983.5    0.07       0
  4989.5     0.1       0
Bank Sta=4983.5,4989.5
Exp/Cntr=0.3,0.1

Type RM Length L Ch R = 1,1912,388,388,388
BEGIN DESCRIPTION:
UNT013 IN NURI 4.0
END DESCRIPTION:
XS GIS Cut Line= 4
      2284375.02     13323653.06      2284036.47     13323470.76
      2283715.29     13323446.89      2283272.63     13323518.50
#Sta/Elev= 30
  4509.3  215.95  4608.5  213.08  4665.2  210.32  4681.4  210.20  4688.0  211.46
  4703.3  210.87  4710.7  209.73  4771.3  207.09  4807.2  206.76  4812.9  206.01
  4851.0  205.11  4858.3  203.65  4922.6  200.82  5029.9  199.74  5032.7  199.24
  5035.9  199.74  5103.1  200.48  5242.9  204.33  5247.9  205.10  5371.3  208.92
  5376.4  210.44  5405.9  209.39  5438.1  211.64  5486.9  212.28  5507.2  214.17
  5556.4  213.78  5598.4  216.46  5649.0  216.44  5659.1  216.73  5664.3  217.95
#Mann=4,-1,0
  4509.3    0.05       0  4771.3     0.1       0  5029.9    0.07       0
  5035.9     0.1       0
Bank Sta=5029.9,5035.9
Exp/Cntr=0.3,0.1

Type RM Length L Ch R = 1,1524,416,416,416
BEGIN DESCRIPTION:
UNT013 IN NURI 3.0
END DESCRIPTION:
XS GIS Cut Line= 3
      2284392.37     13323294.98      2284088.55     13323097.50
      2283385.44     13323075.80
#Sta/Elev= 30
  4506.3  209.95  4559.5  209.35  4659.9  205.87  4681.0  205.06  4711.3  202.58
  4732.4  202.19  4738.5  201.32  4747.5  200.99  4919.5  198.42  4949.5  196.69
  4996.5  195.68  4999.3  195.18  5002.5  195.68  5008.0  195.83  5109.6  196.36
  5149.6  197.53  5223.3  200.94  5249.7  202.16  5279.7  202.75  5329.7  206.99
  5375.2  209.17  5380.2  208.97  5399.7  210.24  5409.7  211.96  5419.7  212.09
  5429.8  211.25  5459.8  213.17  5489.8  214.14  5519.8  216.17  5572.1  218.15
#Mann=5,-1,0
  4506.3    0.05       0  4996.5    0.03       0  5002.5    0.05       0
  5008.0     0.1       0  5223.3    0.05       0
Bank Sta=4996.5,5002.5
Exp/Cntr=0.3,0.1

Type RM Length L Ch R = 1,1108,510,510,510
BEGIN DESCRIPTION:
Mapping XS 6c7a1990
END DESCRIPTION:
XS GIS Cut Line= 3
      2284392.36     13322958.60      2284079.87     13322719.89
      2283496.12     13322643.94
#Sta/Elev= 30
  4460.2  204.88  4515.4  203.71  4571.6  201.89  4706.7  196.64  4800.1  194.89
  4865.7  192.76  4895.9  192.25  4926.2  192.47  4976.6  191.82  4994.5  191.17
  4997.3  190.67  5000.5  191.17  5047.2  192.04  5071.6  191.89  5097.6  192.93
  5117.8  195.43  5127.9  195.50  5138.0  194.77  5168.2  195.41  5198.5  197.25
  5238.8  198.65  5298.8  201.58  5303.8  201.42  5309.4  202.11  5349.7  203.98
  5377.9  205.03  5382.9  204.77  5410.2  206.11  5420.3  207.18  5442.1  208.00
#Mann=3,-1,0
  4460.2    0.05       0  4994.5    0.03       0  5000.5    0.05       0
Bank Sta=4994.5,5000.5
Exp/Cntr=0.3,0.1

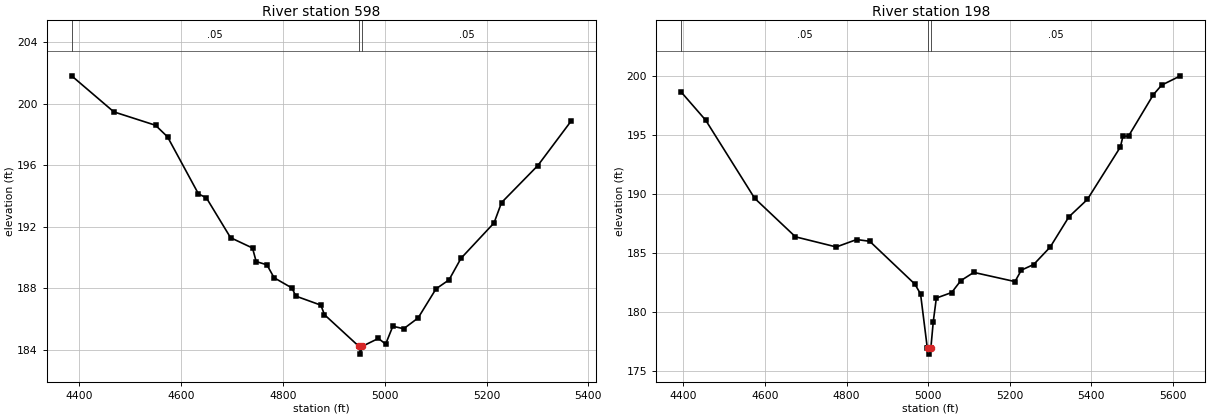
Type RM Length L Ch R = 1,598,400,400,400
BEGIN DESCRIPTION:
UNT013 IN NURI 2.0
END DESCRIPTION:
XS GIS Cut Line= 4
      2284385.86     13322826.23      2284253.48     13322513.73
      2283973.53     13322225.10      2283833.35     13322031.00
#Sta/Elev= 30
  4384.8  201.80  4467.7  199.46  4549.6  198.59  4573.2  197.84  4633.9  194.14
  4649.7  193.87  4697.1  191.29  4740.2  190.62  4747.4  189.74  4768.5  189.53
  4782.6  188.69  4817.9  188.02  4825.1  187.50  4874.5  186.91  4881.6  186.29
  4949.4  184.23  4952.1  183.73  4955.4  184.23  4987.6  184.75  5001.8  184.38
  5015.9  185.54  5037.3  185.38  5065.6  186.08  5100.8  187.97  5126.3  188.55
  5149.8  189.95  5214.8  192.25  5229.5  193.57  5300.7  195.97  5365.7  198.84
#Mann=3,-1,0
  4384.8    0.05       0  4949.4    0.03       0  4955.4    0.05       0
Bank Sta=4949.4,4955.4
Exp/Cntr=0.3,0.1

Type RM Length L Ch R = 1,198,0,0,0
BEGIN DESCRIPTION:
UNT013 IN NURI 1.0
END DESCRIPTION:
XS GIS Cut Line= 4
      2284481.35     13322756.82      2284490.03     13322298.89
      2284370.67     13322066.68      2283872.11     13321990.82
#Sta/Elev= 30
  4394.9  198.66  4454.9  196.27  4574.9  189.64  4674.9  186.37  4774.9  185.51
  4824.9  186.14  4856.9  185.99  4967.6  182.35  4981.4  181.52  4997.9  176.94
  5000.6  176.91  5003.3  176.41  5006.6  176.91  5012.6  179.18  5020.1  181.17
  5057.6  181.64  5080.1  182.65  5111.8  183.35  5212.8  182.57  5228.3  183.54
  5258.6  184.02  5299.1  185.50  5345.0  188.07  5390.1  189.54  5471.0  193.99
  5477.3  194.89  5491.2  194.93  5551.9  198.44  5572.2  199.25  5618.3  200.04
#Mann=3,-1,0
  4394.9    0.05       0  5000.6    0.03       0  5006.6    0.05       0
Bank Sta=5000.6,5006.6
Exp/Cntr=0.3,0.1

Chan Stop Cuts=-1