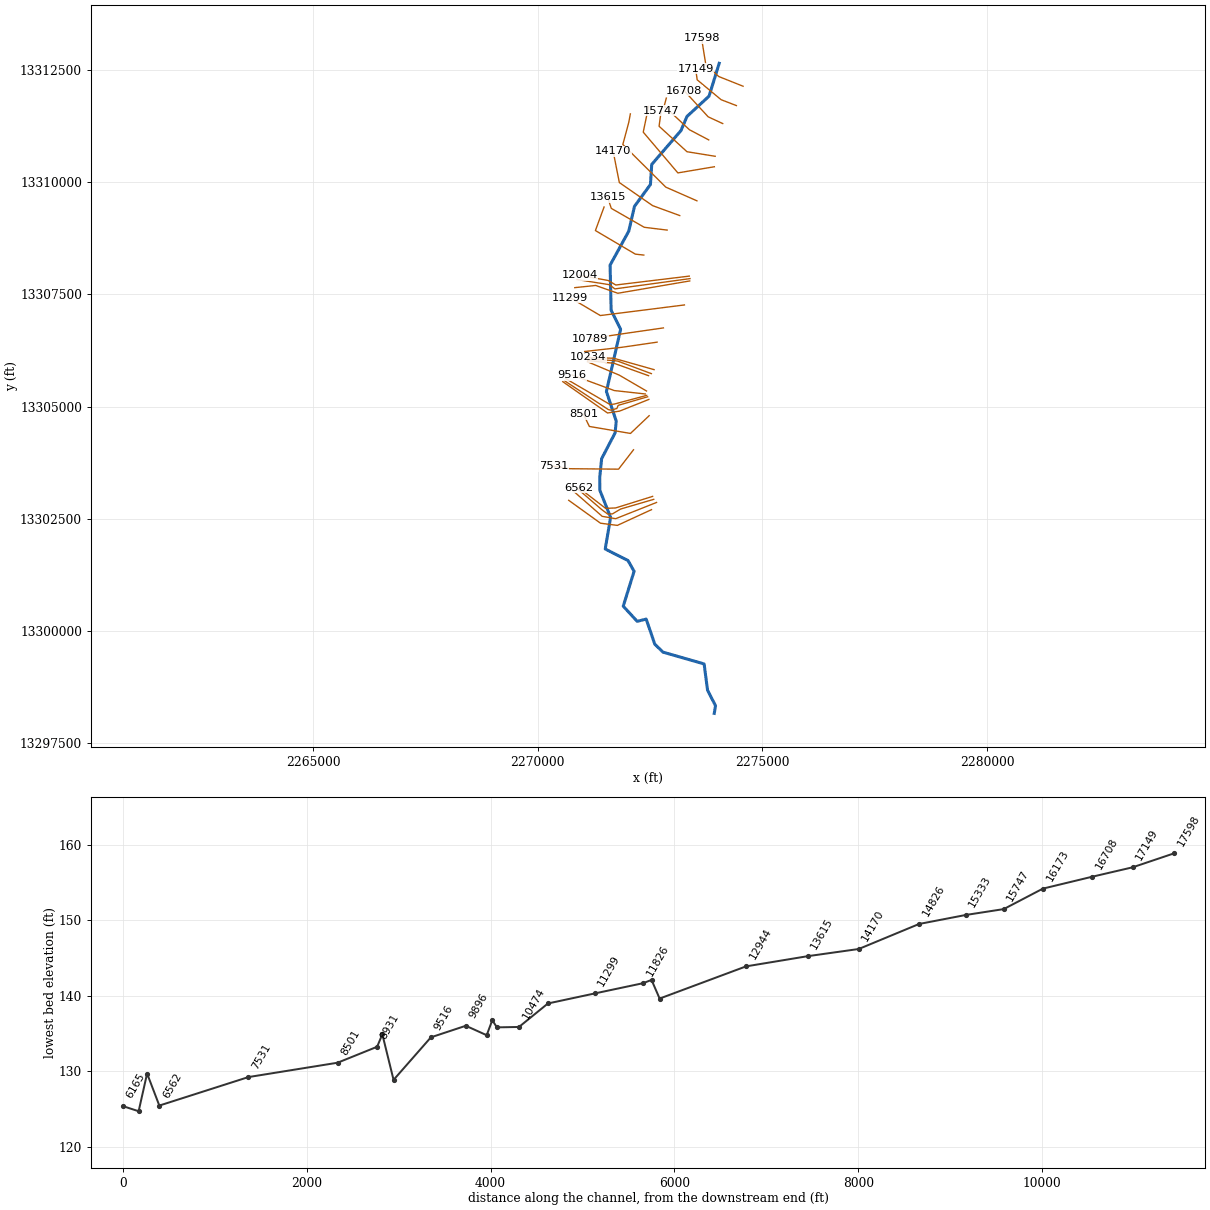
--- UNT015 IN NURI.prj (project) ---

Proj Title=UNT015 IN NURI Base Level Engineering
Current Plan=p01
Default Exp/Contr=0.3,0.1
English Units
Geom File=g01
Flow File=f01
Plan File=p01
Y Axis Title=Elevation
X Axis Title(PF)=Main Channel Distance
X Axis Title(XS)=Station
BEGIN DESCRIPTION:
UNT015 IN NURI
END DESCRIPTION:
DSS Export Rating Curves= 0
DSS Export Rating Curve Sorted= 0
DSS Export Volume Flow Curves= 0
DXF OffsetX= 0
DXF OffsetY= 0
DXF ScaleX= 1
DXF ScaleY= 10

--- UNT015 IN NURI.p01 (plan) ---

Plan Title=Multiple Run
Short Identifier=Multiple
Geom File=g01
Flow File=f01
Subcritical Flow
K Sum by GR= 0
Std Step Tol= 0.01
Critical Tol= 0.01
Num of Std Step Trials= 20
Max Error Tol= 0.3
Flow Tol Ratio= 0.001
Split Flow NTrial= 30
Split Flow Tol= 0.02
Split Flow Ratio= 0.02
Log Output Level= 0
Friction Slope Method= 1
Unsteady Friction Slope Method= 2
Unsteady Bridges Friction Slope Method= 1
Parabolic Critical Depth
Global Vel Dist=  1 , 1 , 1
Global Log Level= 0
CheckData=True
Encroach Param= -1, 0, 0, 0
BEGIN DESCRIPTION:
Multiple Run
END DESCRIPTION:

--- UNT015 IN NURI.f01 (steady flow) ---

Flow Title=Multiple
Program Version=4.10
Number of Profiles= 7
Profile Names=10-year,25-year,50-year,1pct_min,100-year,1pct_plu,500-year
River Rch & RM=UNT015 IN NURI,Reach-1         ,17598
     152     203     243     215     290     393     421
River Rch & RM=UNT015 IN NURI,Reach-1         ,15747
     255     350     426     382     517     699     770
River Rch & RM=UNT015 IN NURI,Reach-1         ,10474
     355     494     610     553     748    1011    1141
Boundary for River Rch & Prof#=UNT015 IN NURI,Reach-1         , 1
Up Type= 0
Dn Type= 3
Dn Slope=0.005
Boundary for River Rch & Prof#=UNT015 IN NURI,Reach-1         , 2
Up Type= 0
Dn Type= 3
Dn Slope=0.005
Boundary for River Rch & Prof#=UNT015 IN NURI,Reach-1         , 3
Up Type= 0
Dn Type= 3
Dn Slope=0.005
Boundary for River Rch & Prof#=UNT015 IN NURI,Reach-1         , 4
Up Type= 0
Dn Type= 3
Dn Slope=0.005
Boundary for River Rch & Prof#=UNT015 IN NURI,Reach-1         , 5
Up Type= 0
Dn Type= 3
Dn Slope=0.005
Boundary for River Rch & Prof#=UNT015 IN NURI,Reach-1         , 6
Up Type= 0
Dn Type= 3
Dn Slope=0.005
Boundary for River Rch & Prof#=UNT015 IN NURI,Reach-1         , 7
Up Type= 0
Dn Type= 3
Dn Slope=0.005
DSS Import GetInterval= 0
DSS Import GetPeak= 0
DSS Import FillOption= 0

--- UNT015 IN NURI.g01 (geometry) ---

Geom Title=Existing Conditions
Program Version=4.10

River Reach=UNT015 IN NURI  ,Reach-1
Reach XY= 30
      2274038.53     13312646.25      2273811.88     13311914.68
      2273321.52      13311463.4      2273186.21     13311146.86
      2272535.96     13310393.76      2272507.72     13309946.86
      2272152.07     13309459.81      2272025.36     13308907.88
      2271609.69     13308151.13      2271632.57     13307143.59
      2271843.94     13306722.12      2271527.61     13305336.93
      2271746.09     13304676.15      2271721.59     13304416.88
      2271421.13     13303838.72      2271378.25     13303414.21
      2271381.51     13303136.43      2271621.09     13302533.57
      2271501.17     13301828.24      2272008.62     13301570.62
      2272143.86     13301331.93      2271902.35     13300554.33
      2272212.71     13300216.78      2272412.94     13300266.78
      2272603.91     13299709.72       2272784.8     13299531.56
      2273702.17     13299268.21      2273778.93     13298682.29
      2273956.68     13298336.86      2273927.72     13298166.85

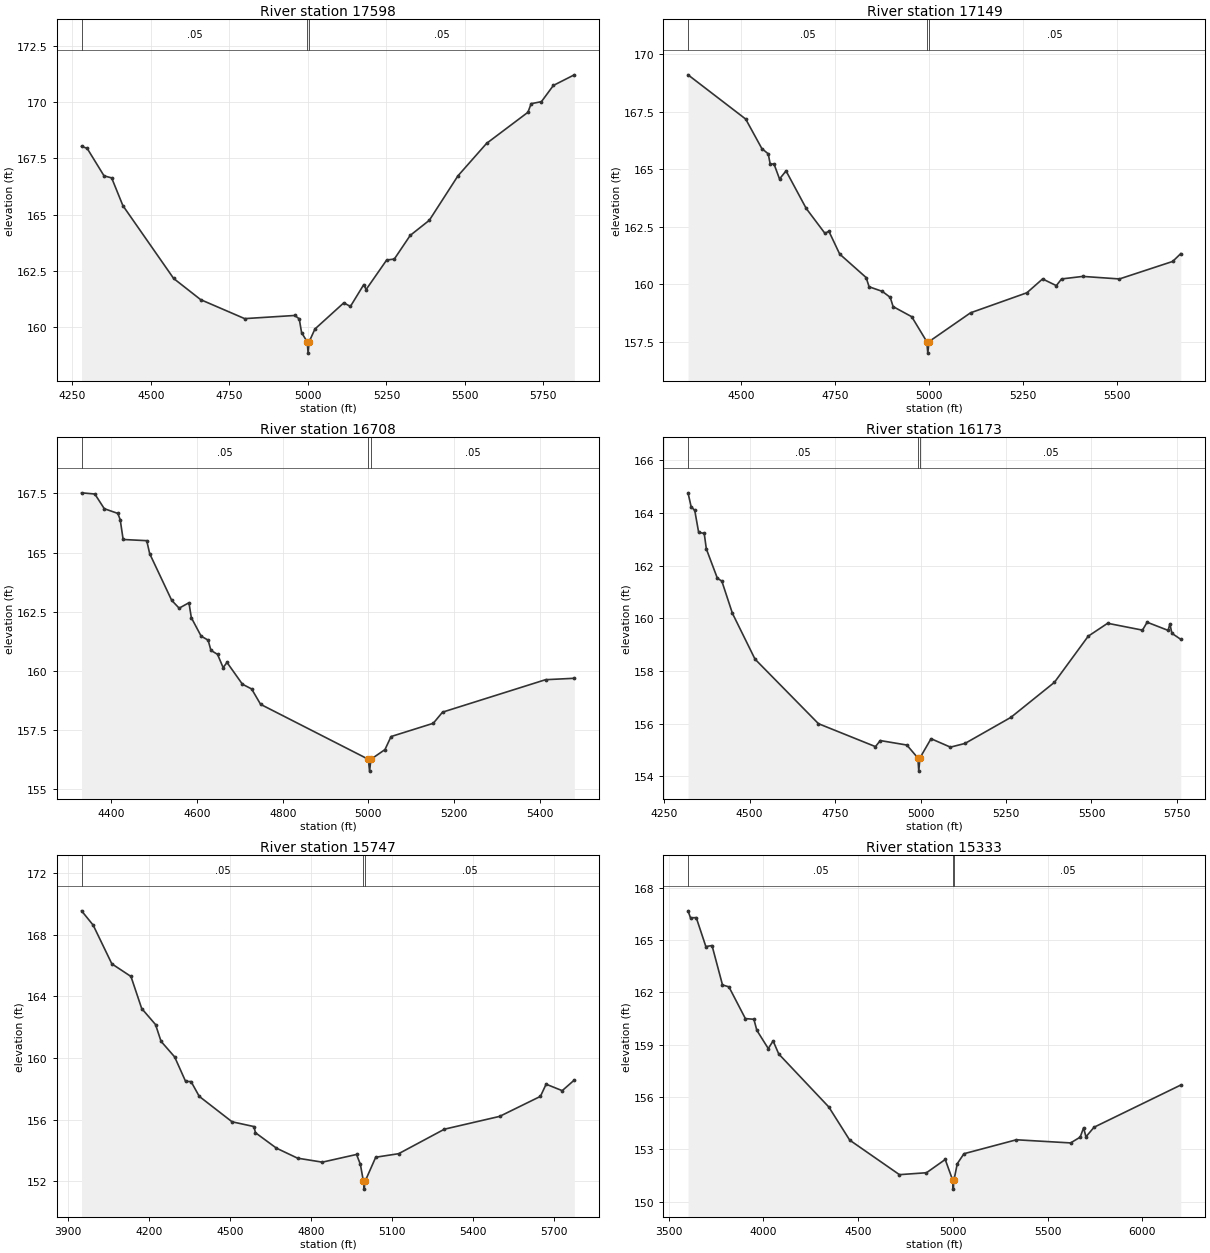
Type RM Length L Ch R = 1 ,17598   ,449,449,449
BEGIN DESCRIPTION:
UNT015 IN NURI 29.0
END DESCRIPTION:
XS GIS Cut Line= 4
      2274569.91     13312135.54       2274027.4     13312352.54
      2273740.94     13312612.96      2273645.56     13313202.55
#Sta/Elev= 30
  4279.6  168.03  4297.4  167.94  4351.2  166.72  4375.4  166.63  4411.2   165.4
  4572.8  162.17  4658.9  161.23  4798.9  160.39  4958.5  160.53  4972.6  160.38
  4980.1  159.77    4998  159.36  5000.8  158.86    5004  159.36  5022.6  159.93
  5114.5  161.09  5135.5  160.93  5178.1   161.9  5185.5  161.68    5251  162.99
  5275.2  163.03  5325.9  164.08  5386.7  164.75  5477.8  166.72    5569  168.16
  5700.7  169.54  5710.8  169.92  5743.6  170.01  5781.7  170.73  5848.3   171.2
#Mann= 3 ,-1 , 0
  4279.6     .05       0    4998     .03       0    5004     .05       0
Bank Sta=4998,5004
XS Rating Curve= 0 ,0
Exp/Cntr=0.3,0.1

Type RM Length L Ch R = 1 ,17149   ,441,441,441
BEGIN DESCRIPTION:
Mapping XS 552e334f
END DESCRIPTION:
XS GIS Cut Line= 4
      2274420.63     13311704.77      2274080.02     13311836.24
      2273548.24     13312278.39      2273512.56     13312528.17
#Sta/Elev= 30
  4359.3   169.1  4512.5  167.18  4555.4   165.9  4572.4  165.67  4577.8  165.21
  4587.5  165.24  4602.4  164.58  4619.7  164.93  4673.3   163.3    4723  162.22
  4733.5  162.31  4762.2  161.32  4832.5   160.3  4840.3   159.9  4875.5   159.7
  4896.5  159.44  4904.1  159.04  4953.6   158.6  4993.5  157.52  4996.3  157.02
  4999.5  157.52  5109.8  158.77  5259.5  159.64  5301.2  160.24  5337.7  159.95
  5351.6  160.24    5408  160.35  5505.3  160.24  5646.8     161  5668.3  161.34
#Mann= 3 ,-1 , 0
  4359.3     .05       0  4993.5     .03       0  4999.5     .05       0
Bank Sta=4993.5,4999.5
XS Rating Curve= 0 ,0
Exp/Cntr=0.3,0.1

Type RM Length L Ch R = 1 ,16708   ,535,535,535
BEGIN DESCRIPTION:
UNT015 IN NURI 28.0
END DESCRIPTION:
XS GIS Cut Line= 3
      2274115.88     13311304.45      2273793.22     13311453.83
      2273255.45      13312039.4
#Sta/Elev= 30
  4330.3  167.52  4361.3  167.47  4383.4  166.85  4415.1  166.65  4420.6  166.38
  4427.4  165.55  4482.5   165.5  4489.4  164.95  4540.8  162.98  4558.2  162.65
  4581.1  162.88  4586.6  162.25  4609.5  161.47  4625.8   161.3  4632.4  160.87
  4647.8   160.7  4660.9  160.14  4669.9  160.36  4705.9  159.44  4727.4  159.24
  4748.4  158.59    5000  156.27  5002.8  155.77    5006  156.27  5038.8  156.68
    5053  157.23  5151.6  157.79  5173.2  158.26  5413.7  159.63  5480.9  159.69
#Mann= 3 ,-1 , 0
  4330.3     .05       0    5000     .03       0    5006     .05       0
Bank Sta=5000,5006
XS Rating Curve= 0 ,0
Exp/Cntr=0.3,0.1

Type RM Length L Ch R = 1 ,16173   ,426,426,426
BEGIN DESCRIPTION:
UNT015 IN NURI 27.0
END DESCRIPTION:
XS GIS Cut Line= 4
      2273805.15     13310939.98      2273374.96     13311167.03
      2272813.31     13311692.83      2272861.08     13311871.98
#Sta/Elev= 30
    4320  164.76    4329  164.24  4339.7  164.09  4351.1  163.26  4367.4  163.22
  4373.6  162.63  4405.8  161.52  4418.9  161.41  4449.8  160.19  4515.9  158.45
  4701.5     156  4868.2  155.13  4882.3  155.36    4960  155.19  4992.2   154.7
  4994.9   154.2  4998.2   154.7  5030.8  155.43  5087.5  155.11    5130  155.25
  5264.3  156.24  5391.7  157.57  5490.5  159.32  5547.2  159.81  5649.2  159.55
  5662.8  159.85  5724.2  159.54  5729.4  159.79  5735.2  159.43  5761.2   159.2
#Mann= 3 ,-1 , 0
    4320     .05       0  4992.2     .03       0  4998.2     .05       0
Bank Sta=4992.2,4998.2
XS Rating Curve= 0 ,0
Exp/Cntr=0.3,0.1

Type RM Length L Ch R = 1 ,15747   ,414,414,414
BEGIN DESCRIPTION:
UNT015 IN NURI 26.0
END DESCRIPTION:
XS GIS Cut Line= 4
      2273948.53      13310575.5      2273321.19     13310677.07
      2272699.78      13311244.7      2272747.58     13311591.28
#Sta/Elev= 30
  3950.1  169.55  3993.2  168.62  4062.4  166.11  4133.3  165.29  4173.1  163.21
  4224.4  162.17  4244.9  161.08  4295.3  160.07  4335.9  158.48  4356.1  158.47
  4386.5  157.51  4508.1  155.86  4589.2  155.55  4594.9  155.15  4672.6  154.15
  4750.9   153.5  4842.8  153.24  4969.8  153.74    4984  153.09  4995.2  151.99
    4998  151.49  5001.2  151.99  5040.8  153.56  5125.9  153.79  5295.5  155.38
  5500.1  156.21  5651.5  157.51  5672.5   158.3  5732.3  157.88  5777.1  158.57
#Mann= 3 ,-1 , 0
  3950.1     .05       0  4995.2     .03       0  5001.2     .05       0
Bank Sta=4995.2,5001.2
XS Rating Curve= 0 ,0
Exp/Cntr=0.3,0.1

Type RM Length L Ch R = 1 ,15333   ,507,507,507
BEGIN DESCRIPTION:
UNT015 IN NURI 25.0
END DESCRIPTION:
XS GIS Cut Line= 4
      2273930.64     13310342.47      2273118.04     13310205.04
      2272347.25     13311113.25      2272466.76      13311686.9
#Sta/Elev= 30
    3602  166.67  3615.1  166.27  3645.5  166.28  3696.2  164.62  3728.7  164.68
    3784  162.42  3817.9  162.31  3904.8  160.49  3949.8  160.45  3965.2  159.82
  4025.7  158.77  4051.2  159.21    4081  158.46  4345.3  155.42  4455.6  153.52
  4718.1  151.54  4860.9  151.65  4959.8  152.41  4999.6  151.21  5002.4  150.71
  5005.6  151.21  5023.5  152.17  5058.6  152.74  5335.4  153.54  5621.7  153.36
  5672.1  153.69  5690.3  154.23  5702.7  153.71  5745.5  154.26  6203.3  156.68
#Mann= 3 ,-1 , 0
    3602     .05       0  4999.6     .03       0  5005.6     .05       0
Bank Sta=4999.6,5005.6
XS Rating Curve= 0 ,0
Exp/Cntr=0.3,0.1

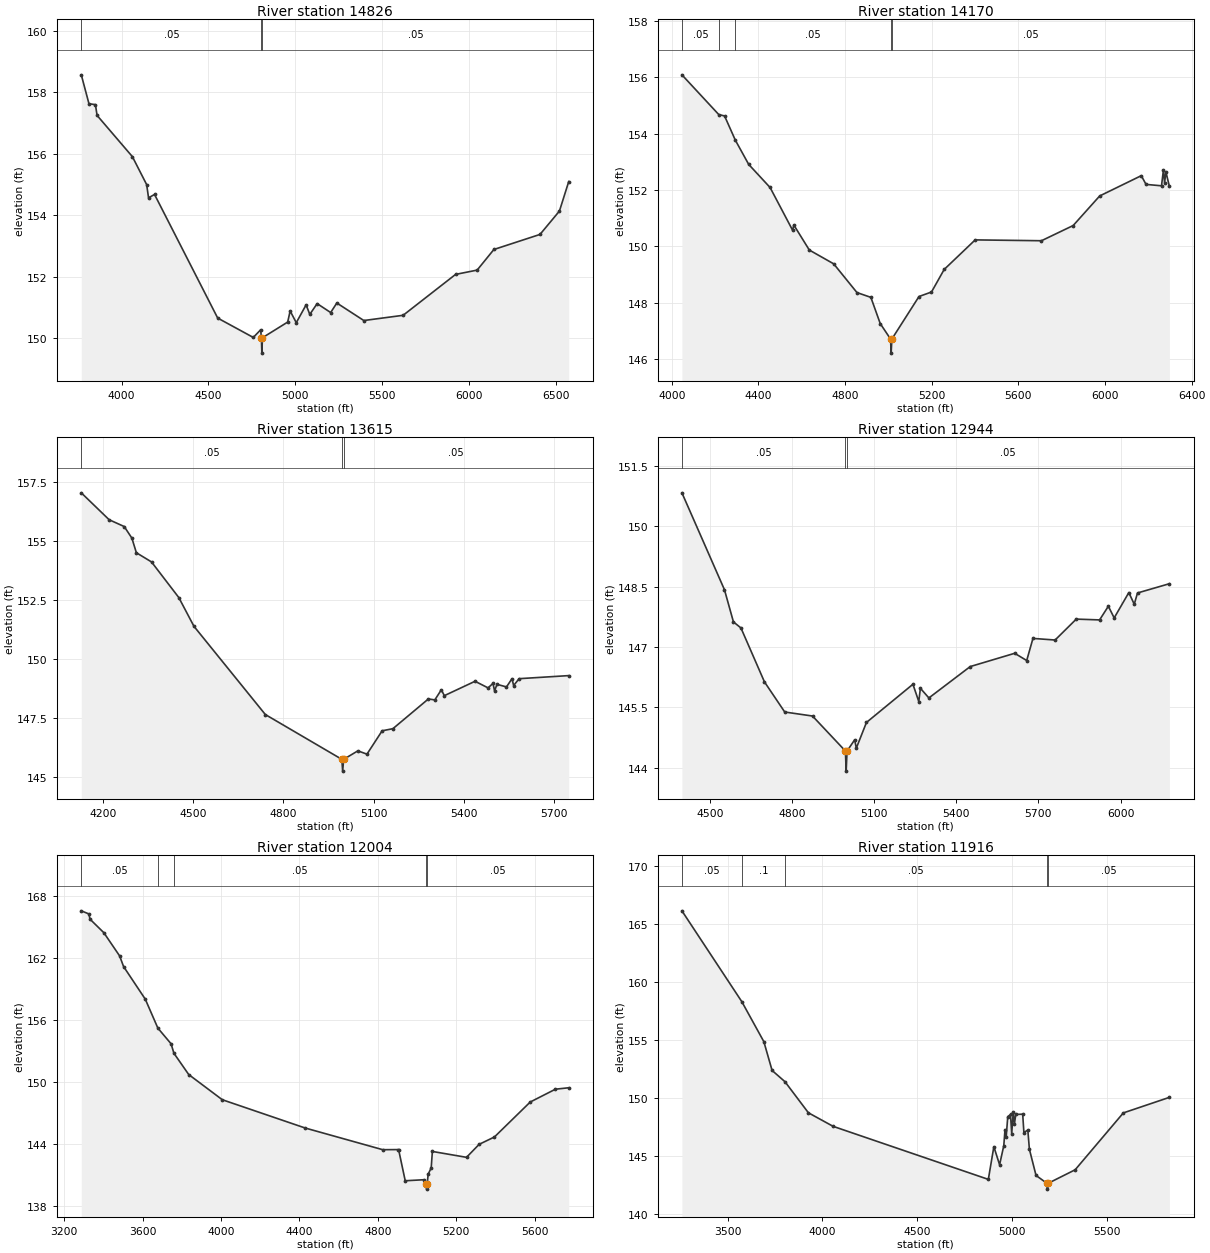
Type RM Length L Ch R = 1 ,14826   ,656,656,656
BEGIN DESCRIPTION:
UNT015 IN NURI 24.0
END DESCRIPTION:
XS GIS Cut Line= 5
      2273542.27     13309583.63      2272849.16     13309888.36
      2271893.15      13310838.4       2272024.6     13311328.35
      2272060.44     13311519.52
#Sta/Elev= 30
  3768.2  158.57  3812.4  157.63  3849.6   157.6  3859.1  157.25  4062.3  155.91
  4144.6     155  4155.5  154.57    4190  154.68  4553.6  150.66  4758.6  150.03
  4801.1  150.28  4805.2  150.02  4807.9  149.52  4811.2  150.02  4956.6  150.53
  4970.8  150.89  5006.1  150.51  5062.7  151.09  5083.9  150.78  5126.3  151.13
  5204.1  150.84  5239.5  151.15    5395  150.58  5621.3  150.75  5923.3  152.08
  6047.5  152.22  6143.8  152.89  6409.4  153.38  6521.3  154.14  6574.9   155.1
#Mann= 3 ,-1 , 0
  3768.2     .05       0  4805.2     .03       0  4811.2     .05       0
Bank Sta=4805.2,4811.2
XS Rating Curve= 0 ,0
Exp/Cntr=0.3,0.1

Type RM Length L Ch R = 1 ,14170   ,555,555,555
BEGIN DESCRIPTION:
UNT015 IN NURI 22.0
END DESCRIPTION:
XS GIS Cut Line= 4
       2273159.9     13309254.99      2272556.38     13309476.09
      2271815.47     13309989.94      2271678.16     13310682.45
#Sta/Elev= 30
  4046.7  156.09  4216.7  154.68  4243.6  154.63  4293.3  153.77    4355  152.91
  4453.7  152.09  4557.9  150.57  4563.2  150.76  4634.8  149.87  4747.4  149.38
  4854.8  148.36    4919  148.19  4962.2  147.26  5009.9  146.71  5012.6  146.21
  5015.9  146.71  5141.2  148.22  5198.9  148.38  5257.4  149.18  5400.6  150.23
  5706.6   150.2    5853  150.74  5975.4  151.79  6167.4  152.51  6189.4   152.2
  6260.8  152.15  6269.8  152.72  6274.9  152.26  6281.2  152.64  6297.1  152.13
#Mann= 5 ,-1 , 0
  4046.7     .05       0  4216.7      .1       0  4293.3     .05       0
  5009.9     .03       0  5015.9     .05       0
Bank Sta=5009.9,5015.9
XS Rating Curve= 0 ,0
Exp/Cntr=0.3,0.1

Type RM Length L Ch R = 1 ,13615   ,671,671,671
BEGIN DESCRIPTION:
UNT015 IN NURI 21.0
END DESCRIPTION:
XS GIS Cut Line= 4
       2272879.5     13308931.38      2272369.88     13308993.79
      2271636.65     13309415.01       2271553.9     13309663.25
#Sta/Elev= 30
  4128.3  157.06  4220.8  155.92  4271.1  155.63  4296.5  155.14  4311.4  154.52
  4361.8  154.13  4452.5  152.62  4502.9   151.4  4740.2  147.66  4994.6  145.76
  4997.3  145.26  5000.6  145.76  5047.9  146.12  5078.1  145.98  5128.6  146.97
  5164.4  147.06  5282.3  148.32  5303.8  148.28  5325.4  148.71  5335.4  148.46
  5437.5  149.07  5480.7  148.79  5497.2  148.98  5502.4  148.66  5510.4  148.94
    5542  148.83  5560.4  149.18  5565.7  148.89  5584.1  149.18    5749  149.31
#Mann= 3 ,-1 , 0
  4128.3     .05       0  4994.6     .03       0  5000.6     .05       0
Bank Sta=4994.6,5000.6
XS Rating Curve= 0 ,0
Exp/Cntr=0.3,0.1

Type RM Length L Ch R = 1 ,12944   ,940,940,940
BEGIN DESCRIPTION:
UNT015 IN NURI 20.0
END DESCRIPTION:
XS GIS Cut Line= 4
      2272359.52     13308374.95      2272172.28     13308395.76
      2271283.03     13308920.98      2271475.43     13309446.18
#Sta/Elev= 30
  4397.9  150.83  4553.3  148.42  4586.1  147.62  4613.5  147.47  4699.3  146.13
  4773.4  145.38  4874.9  145.28  4995.1  144.41  4997.8  143.91  5001.1  144.41
    5029  144.69  5034.8  144.48  5071.9  145.12  5241.7  146.07  5263.1  145.64
  5268.9  145.97    5300  145.73    5451  146.51  5613.4  146.84  5657.3  146.66
  5680.1  147.21    5761  147.17  5838.3  147.69  5923.5  147.67  5955.5  148.01
  5976.8  147.72  6030.3  148.35  6050.1  148.06    6062  148.34  6178.4  148.57
#Mann= 3 ,-1 , 0
  4397.9     .05       0  4995.1     .03       0  5001.1     .05       0
Bank Sta=4995.1,5001.1
XS Rating Curve= 0 ,0
Exp/Cntr=0.3,0.1

Type RM Length L Ch R = 1 ,12004   ,88,88,88
BEGIN DESCRIPTION:
UNT015 IN NURI 19.0
END DESCRIPTION:
XS GIS Cut Line= 4
        2273372.     13307906.36       2271736.6     13307708.44
      2271566.46     13307809.14       2270934.5     13307923.72
#Sta/Elev= 30
  3286.8  166.61  3325.3  166.31  3331.4   165.8  3401.9  164.49  3482.5  162.24
  3502.6  161.21  3613.4  158.05  3677.5  155.25  3744.9  153.73  3759.5  152.81
    3835  150.75  4006.3  148.31  4429.4  145.57  4824.9  143.47  4901.7  143.48
  4906.8   143.4  4939.7  140.46  5035.3  140.56    5046  140.15  5048.8  139.65
    5052  140.15  5056.7   141.1  5072.3   141.7  5078.2   143.3  5252.5  142.73
  5316.9  143.99  5394.8   144.7  5577.7  148.09  5706.2  149.33  5774.1  149.47
#Mann= 5 ,-1 , 0
  3286.8     .05       0  3677.5      .1       0  3759.5     .05       0
    5046    .035       0    5052     .05       0
Bank Sta=5046,5052
XS Rating Curve= 0 ,0
Exp/Cntr=0.3,0.1

Type RM Length L Ch R = 1 ,11916   ,90,90,90
BEGIN DESCRIPTION:
Mapping XS 12362f07
END DESCRIPTION:
XS GIS Cut Line= 4
      2273389.39     13307850.81      2271715.76     13307621.64
      2271594.24     13307715.39      2270872.39     13307829.91
#Sta/Elev= 30
  3258.1  166.11  3574.3  158.28  3690.7  154.83  3734.2  152.35  3802.2  151.38
  3925.9   148.7  4056.7  147.53  4875.9  142.96    4905  145.78  4935.3  144.22
  4957.5  145.87  4963.9  147.25  4970.3  146.65  4978.4  148.36  4992.9  148.56
  4999.3   146.9  5007.4  148.77  5013.8  147.76  5020.7  148.56  5057.3  148.58
  5063.6     147  5084.4  147.21  5092.6  145.56  5127.7   143.3  5185.4  142.62
  5188.2  142.12  5191.4  142.62  5334.4  143.79  5588.6  148.69  5831.7  150.03
#Mann= 5 ,-1 , 0
  3258.1     .05       0  3574.3      .1       0  3802.2     .05       0
  5185.4    .035       0  5191.4     .05       0
Bank Sta=5185.4,5191.4
XS Rating Curve= 0 ,0
Exp/Cntr=0.3,0.1

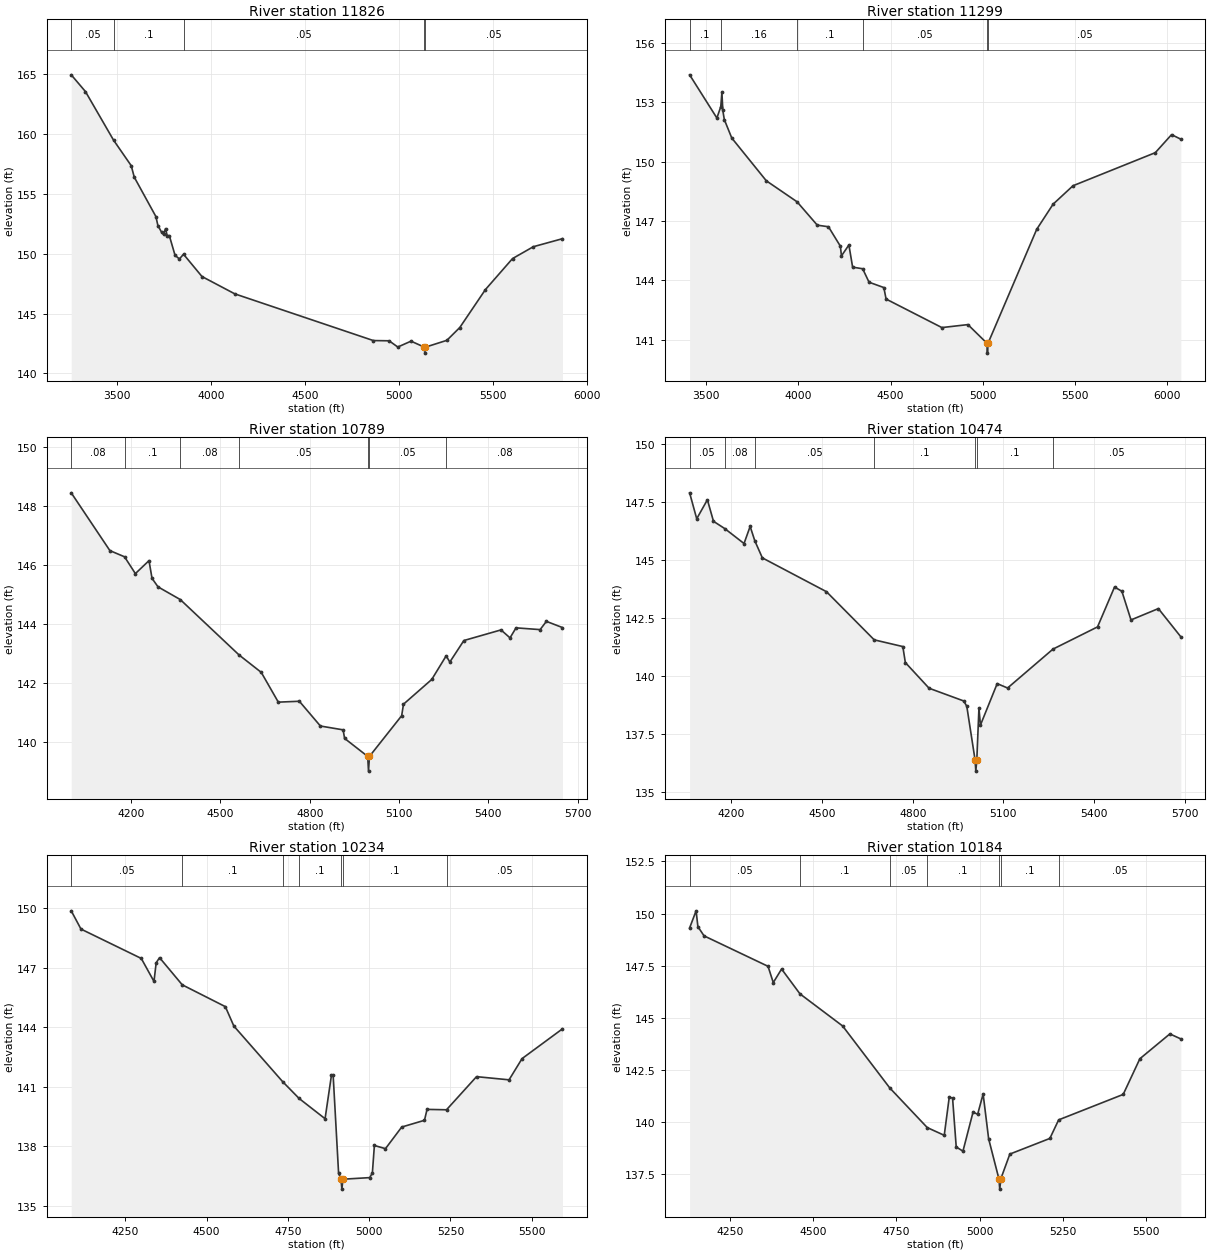
Type RM Length L Ch R = 1 ,11826   ,527,527,527
BEGIN DESCRIPTION:
UNT015 IN NURI 18.0
END DESCRIPTION:
XS GIS Cut Line= 4
      2273382.38     13307798.71      2271781.74     13307524.42
      2271288.68     13307698.03      2270823.42     13307649.42
#Sta/Elev= 30
  3255.6  164.94  3331.4  163.54  3480.6  159.49  3574.9  157.35  3591.1  156.39
  3706.2   153.1  3716.9  152.35  3737.2  151.77  3747.3  151.61  3757.5  152.09
  3766.2  151.51  3777.8   151.5  3808.2  149.86  3831.3  149.56  3853.4  149.95
  3951.4  148.09  4126.4  146.64  4863.4  142.74  4947.4  142.72  4993.7   142.2
  5064.1  142.69  5134.9  142.19  5137.7  141.69  5140.9  142.19  5254.9  142.76
  5323.7  143.83  5460.1     147  5604.4  149.59    5715  150.58  5870.1  151.25
#Mann= 5 ,-1 , 0
  3255.6     .05       0  3480.6      .1       0  3853.4     .05       0
  5134.9     .03       0  5140.9     .05       0
Bank Sta=5134.9,5140.9
XS Rating Curve= 0 ,0
Exp/Cntr=0.3,0.1

Type RM Length L Ch R = 1 ,11299   ,510,510,510
BEGIN DESCRIPTION:
Mapping XS 3d94f555
END DESCRIPTION:
XS GIS Cut Line= 3
      2273264.38       13307264.      2271392.85     13307027.89
      2270724.33     13307422.77
#Sta/Elev= 30
  3410.4  154.38  3558.2   152.2  3579.3  152.77  3585.4   153.5  3590.4  152.58
  3598.5  152.12  3638.9  151.19  3826.2  149.03  3992.8  147.97  4102.5  146.79
    4163  146.71  4227.5  145.73  4233.5  145.24  4273.8  145.79    4294  144.67
  4348.4  144.59    4383  143.91  4463.2  143.64  4475.4  143.06  4777.8  141.62
  4918.9  141.77  5022.1  140.83  5024.8  140.33  5028.1  140.83  5291.8  146.58
  5380.7  147.85  5488.5  148.78  5934.7  150.45  6022.8  151.36  6073.2  151.13
#Mann= 6 ,-1 , 0
  3410.4      .1       0  3579.3     .16       0  3992.8      .1       0
  4348.4     .05       0  5022.1    .035       0  5028.1     .05       0
Bank Sta=5022.1,5028.1
XS Rating Curve= 0 ,0
Exp/Cntr=0.3,0.1

Type RM Length L Ch R = 1 ,10789   ,315,315,315
BEGIN DESCRIPTION:
Mapping XS 6a32fa94
END DESCRIPTION:
XS GIS Cut Line= 3
      2272796.31     13306752.48      2272000.67     13306638.07
      2271163.45     13306513.27
#Sta/Elev= 30
  3998.9  148.44  4128.8  146.48    4178  146.27  4214.4   145.7  4260.2  146.14
  4270.3  145.54  4290.5  145.25  4365.2  144.82  4562.8  142.94  4637.3  142.35
  4694.6  141.34  4765.3  141.37    4836  140.53  4912.3   140.4  4917.3  140.11
  4994.8   139.5  4997.6     139  5000.8   139.5    5109  140.88  5115.1  141.27
  5210.1  142.11  5258.5  142.91  5270.8   142.7    5318  143.43  5442.7  143.79
    5473  143.52  5493.2  143.86  5574.1   143.8  5595.2  144.08  5649.2  143.87
#Mann= 7 ,-1 , 0
  3998.9     .08       0    4178      .1       0  4365.2     .08       0
  4562.8     .05       0  4994.8     .04       0  5000.8     .05       0
  5258.5     .08       0
Bank Sta=4994.8,5000.8
XS Rating Curve= 0 ,0
Exp/Cntr=0.3,0.1

Type RM Length L Ch R = 1 ,10474   ,240,240,240
BEGIN DESCRIPTION:
Mapping XS acab3530
END DESCRIPTION:
XS GIS Cut Line= 3
      2272655.92     13306435.26      2271870.66     13306320.85
       2271043.8     13306227.25
#Sta/Elev= 30
  4061.5  147.91    4085  146.79  4120.3  147.61  4140.5  146.68  4178.4  146.36
  4241.6  145.72  4261.8  146.46  4277.2  145.84  4302.2   145.1  4514.4  143.64
  4672.4  141.56  4767.1  141.27  4775.4  140.58    4854  139.47  4968.7  138.92
  4978.8  138.69    5006  136.39  5008.7  135.89    5012  136.39    5019  138.61
    5024  137.88  5079.4  139.67  5113.8  139.48    5264  141.16  5411.5  142.12
  5467.7  143.84    5492  143.66  5522.2  142.42  5612.8  142.91  5687.2  141.69
#Mann= 7 ,-1 , 0
  4061.5     .05       0  4178.4     .08       0  4277.2     .05       0
  4672.4      .1       0    5006     .07       0    5012      .1       0
    5264     .05       0
Bank Sta=5006,5012
XS Rating Curve= 0 ,0
Exp/Cntr=0.3,0.1

Type RM Length L Ch R = 1 ,10234   ,50,50,50
BEGIN DESCRIPTION:
Mapping XS 23f877e0
END DESCRIPTION:
XS GIS Cut Line= 3
       2272589.2     13305823.02      2271690.74     13306076.93
      2271113.46     13306094.29
#Sta/Elev= 30
  4083.3  149.87  4113.3  148.95  4298.8  147.47  4337.9  146.31  4344.6  147.25
    4355  147.51  4424.8  146.14  4557.4  145.04  4583.6  144.06  4733.6  141.26
  4784.4  140.41  4864.2  139.39  4883.9  141.59  4889.1  141.57  4905.8  136.64
  4913.2  136.34  4915.9  135.84  4919.2  136.34  5001.4  136.42  5009.7  136.65
  5015.9  138.04    5050  137.88    5100  138.97    5170  139.31  5177.9  139.86
  5237.8  139.84  5330.1  141.51  5430.2  141.35  5470.2  142.42  5594.5  143.92
#Mann= 7 ,-1 , 0
  4083.3     .05       0  4424.8      .1       0  4733.6     .05       0
  4784.4      .1       0  4913.2     .07       0  4919.2      .1       0
  5237.8     .05       0
Bank Sta=4913.2,4919.2
XS Rating Curve= 0 ,0
Exp/Cntr=0.3,0.1

Type RM Length L Ch R = 1 ,10184   ,61,61,61
BEGIN DESCRIPTION:
UNT015 IN NURI 17.0
END DESCRIPTION:
XS GIS Cut Line= 4
      2272528.41     13305734.05      2271784.05     13306011.83
      2271679.89     13306027.02      2271104.75      13306057.4
#Sta/Elev= 30
    4129  149.31  4148.5  150.13  4153.9  149.37  4172.4  148.93  4364.6  147.47
  4380.3  146.69  4405.3  147.34  4460.5  146.15  4588.7  144.61  4730.3  141.64
  4842.9  139.74  4893.9  139.37  4908.9  141.19  4918.9  141.16  4929.9  138.81
  4950.1  138.61  4980.4  140.48  4994.3  140.38  5010.7  141.35  5027.3   139.2
    5058  137.29  5060.7  136.79    5064  137.29    5091  138.47  5211.2  139.22
  5237.6  140.11  5431.5  141.33  5481.6  143.04  5571.7  144.23  5604.7  143.99
#Mann= 7 ,-1 , 0
    4129     .05       0  4460.5      .1       0  4730.3     .05       0
  4842.9      .1       0    5058     .07       0    5064      .1       0
  5237.6     .05       0
Bank Sta=5058,5064
XS Rating Curve= 0 ,0
Exp/Cntr=0.3,0.1

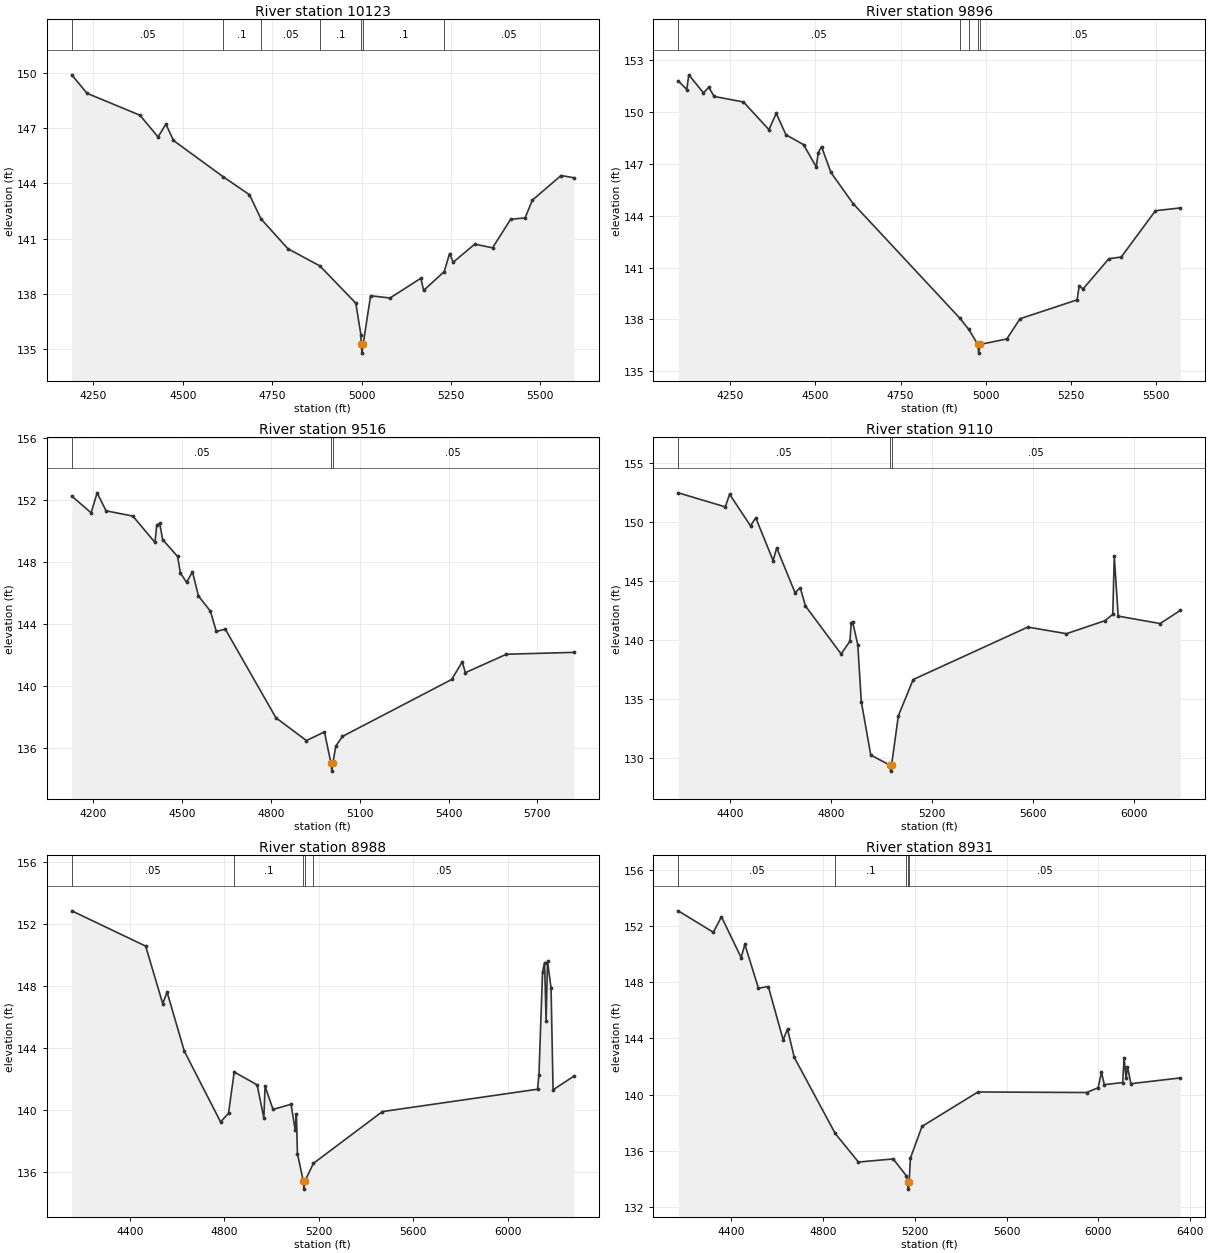
Type RM Length L Ch R = 1 ,10123   ,227,227,227
BEGIN DESCRIPTION:
Mapping XS 4aab63f8
END DESCRIPTION:
XS GIS Cut Line= 3
       2272465.5     13305688.47      2271699.42     13305964.09
      2271111.99     13306024.78
#Sta/Elev= 30
  4189.3  149.89  4231.8  148.89    4380   147.7  4430.8  146.52  4452.6  147.22
  4473.9  146.33  4613.2  144.36  4686.4  143.39  4718.7  142.08  4794.1  140.46
  4883.4  139.53    4984  137.51  4998.4  135.78  4998.7   135.3  5001.4   134.8
  5004.7   135.3  5025.3  137.91  5079.8  137.79    5166  138.86  5173.7   138.2
  5231.3  139.22  5246.4   140.2  5256.5  139.73  5316.8  140.71  5366.5  140.51
  5417.3  142.06  5457.6  142.13  5477.7  143.09  5558.1  144.43    5594  144.31
#Mann= 7 ,-1 , 0
  4189.3     .05       0  4613.2      .1       0  4718.7     .05       0
  4883.4      .1       0  4998.7     .07       0  5004.7      .1       0
  5231.3     .05       0
Bank Sta=4998.7,5004.7
XS Rating Curve= 0 ,0
Exp/Cntr=0.3,0.1

Type RM Length L Ch R = 1 ,9896    ,380,380,380
BEGIN DESCRIPTION:
UNT015 IN NURI 16.0
END DESCRIPTION:
XS GIS Cut Line= 3
      2272420.65     13305347.03      2271812.99     13305701.21
       2271104.7      13305999.8
#Sta/Elev= 30
  4098.2   151.8  4123.3   151.3  4129.1  152.15  4172.1  151.11  4187.8  151.43
  4203.5   150.9  4289.5  150.58    4364  148.98  4385.5  149.92  4414.1  148.68
  4465.7  148.11  4502.9  146.82  4508.7  147.65  4518.3     148  4545.9   146.5
  4610.9   144.7    4923  138.09  4950.2  137.42  4976.4  136.55  4979.2  136.05
  4982.4  136.55  5061.5  136.87  5100.3  138.04  5267.5  139.13  5273.9  139.95
  5284.8  139.76  5360.7  141.51    5397  141.61  5497.3  144.29  5570.2  144.45
#Mann= 5 ,-1 , 0
  4098.2     .05       0    4923      .1       0  4950.2     .05       0
  4976.4     .03       0  4982.4     .05       0
Bank Sta=4976.4,4982.4
XS Rating Curve= 0 ,0
Exp/Cntr=0.3,0.1

Type RM Length L Ch R = 1 ,9516    ,406,406,406
BEGIN DESCRIPTION:
UNT015 IN NURI 15.0
END DESCRIPTION:
XS GIS Cut Line= 3
       2272392.8     13305281.08      2271701.88     13305357.46
      2270764.22     13305704.36
#Sta/Elev= 30
  4128.2  152.26  4193.7  151.18  4213.8  152.47    4244  151.31  4334.5  150.97
  4409.1  149.27    4415  150.38  4425.1   150.5  4435.1  149.45  4485.4  148.37
  4494.9   147.3  4515.6   146.7  4535.7  147.37  4555.9  145.82  4596.1  144.84
  4616.2  143.53  4646.4  143.68  4817.5  137.96  4920.4  136.49  4981.2  137.05
  5003.3  135.02  5006.1  134.52  5009.3  135.02  5019.7  136.14    5042  136.76
  5410.6  140.43  5446.4  141.57  5456.8  140.87  5595.5  142.06  5823.1  142.18
#Mann= 3 ,-1 , 0
  4128.2     .05       0  5003.3    .035       0  5009.3     .05       0
Bank Sta=5003.3,5009.3
XS Rating Curve= 0 ,0
Exp/Cntr=0.3,0.1

Type RM Length L Ch R = 1 ,9110    ,122,122,122
BEGIN DESCRIPTION:
Mapping XS b85bce4a
END DESCRIPTION:
XS GIS Cut Line= 4
      2272424.12     13305249.83      2271701.88     13305055.38
      2271604.65     13305048.43      2270618.58      13305624.8
#Sta/Elev= 30
  4195.3   152.5  4381.5  151.31  4398.7  152.38  4481.5   149.7  4502.3  150.38
  4570.9  146.75  4585.1  147.83  4657.6  144.03  4678.3  144.45    4699   142.9
  4840.1  138.83  4874.9  139.91  4880.1  141.48  4885.4  141.56  4906.1  139.62
    4920  134.79  4957.5  130.25  5033.7  129.39  5036.4  128.89  5039.7  129.39
  5066.7  133.59  5125.4  136.66  5579.2  141.11  5732.2  140.55  5884.2  141.65
  5915.6  142.19  5921.4  147.12  5937.1  142.04  6103.2  141.41  6182.9  142.53
#Mann= 3 ,-1 , 0
  4195.3     .05       0  5033.7    .035       0  5039.7     .05       0
Bank Sta=5033.7,5039.7
XS Rating Curve= 0 ,0
Exp/Cntr=0.3,0.1

Type RM Length L Ch R = 1 ,8988    ,57,57,57
BEGIN DESCRIPTION:
UNT015 IN NURI 14.0
END DESCRIPTION:
XS GIS Cut Line= 6
      2272444.94     13305218.57      2271788.68      13305027.6
       2271760.9     13304958.15      2271628.96     13304919.96
      2271569.93     13304933.85      2270594.27     13305576.19
#Sta/Elev= 30
  4154.5  152.83  4467.1  150.56  4539.3  146.86  4557.8   147.6  4630.7   143.8
  4784.3  139.24  4817.8  139.81  4841.8  142.46  4938.8  141.63  4967.2   139.5
  4972.4  141.54    5006  140.05  5082.2  140.38  5099.9  138.74    5105  139.75
  5109.3  137.21  5134.4  135.42  5137.1  134.92  5140.4  135.42  5177.1  136.58
  5468.7  139.91  6125.3  141.35  6131.3  142.29  6146.4  148.89    6155   149.5
  6161.5  145.77  6167.5  149.59  6182.5  147.87    6191  141.31  6278.9  142.19
#Mann= 5 ,-1 , 0
  4154.5     .05       0  4841.8      .1       0  5134.4     .07       0
  5140.4      .1       0  5177.1     .05       0
Bank Sta=5134.4,5140.4
XS Rating Curve= 0 ,0
Exp/Cntr=0.3,0.1

Type RM Length L Ch R = 1 ,8931    ,430,430,430
BEGIN DESCRIPTION:
Mapping XS 0b808530
END DESCRIPTION:
XS GIS Cut Line= 4
      2272472.68     13305159.53      2271819.93     13304899.13
      2271552.57     13304857.46      2270556.03     13305555.39
#Sta/Elev= 30
  4167.7  153.09  4320.9  151.56  4356.1  152.67  4442.2  149.76  4458.3   150.7
  4517.6  147.58  4560.6   147.7  4625.4   143.9  4644.3  144.67  4673.9  142.65
  4852.2  137.24  4953.7   135.2  5105.5  135.42  5163.1  134.21  5168.8  133.77
  5171.6  133.27  5174.8  133.77  5180.5  135.48  5231.1  137.74  5475.2  140.19
  5948.6  140.15  5999.2  140.49  6013.8   141.6  6026.2  140.71  6106.4  140.86
  6112.5  142.61  6121.2  141.16  6127.3  141.98  6142.2  140.78  6357.7  141.19
#Mann= 5 ,-1 , 0
  4167.7     .05       0  4852.2      .1       0  5163.1     .05       0
  5168.8     .07       0  5174.8     .05       0
Bank Sta=5168.8,5174.8
XS Rating Curve= 0 ,0
Exp/Cntr=0.3,0.1

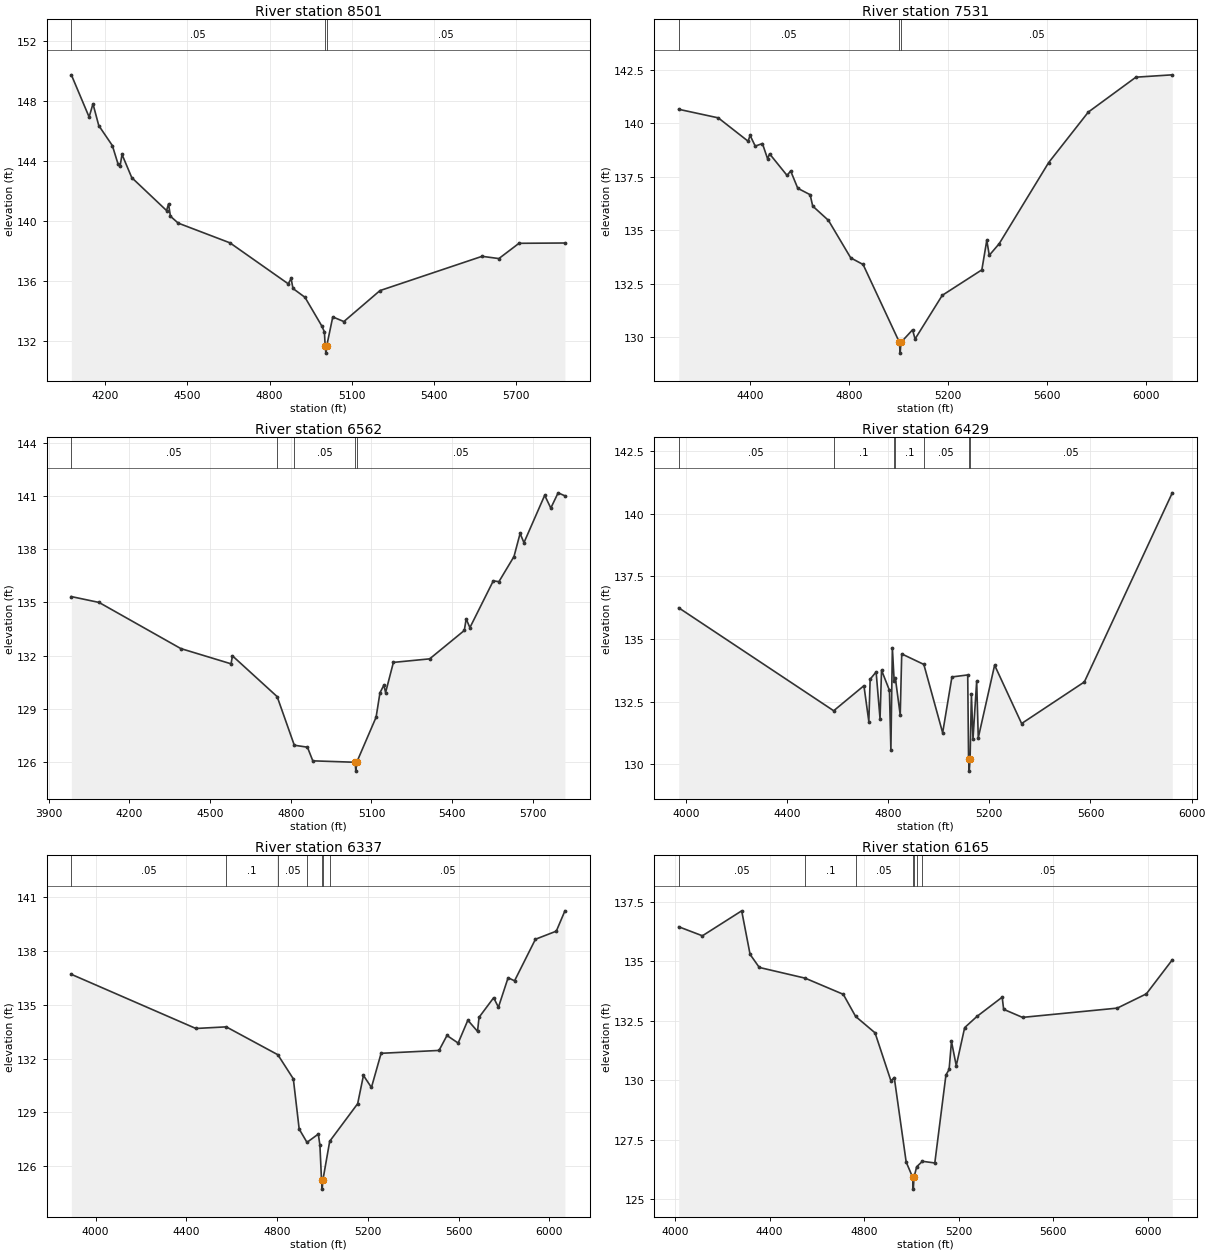
Type RM Length L Ch R = 1 ,8501    ,970,970,970
BEGIN DESCRIPTION:
UNT015 IN NURI 13.0
END DESCRIPTION:
XS GIS Cut Line= 4
      2272479.07     13304797.16      2272063.07     13304401.96
      2271147.82     13304557.97      2271017.81      13304828.4
#Sta/Elev= 30
  4076.4  149.76  4141.3  146.94  4155.4  147.82  4176.5  146.37  4226.2  145.03
  4247.2  143.78  4254.5  143.67  4261.4  144.44    4297  142.89    4424  140.69
  4431.3  141.13  4438.2  140.31  4466.5  139.85  4655.6  138.53  4868.6  135.79
  4878.8  136.15  4885.7  135.48  4929.5  134.89  4990.4  132.99  5000.5  132.58
  5003.1  131.66  5005.9  131.16  5009.1  131.66    5031  133.58  5071.5  133.27
  5203.4  135.34  5576.2  137.63  5637.5  137.48    5711   138.5  5878.7  138.52
#Mann= 3 ,-1 , 0
  4076.4     .05       0  5003.1    .035       0  5009.1     .05       0
Bank Sta=5003.1,5009.1
XS Rating Curve= 0 ,0
Exp/Cntr=0.3,0.1

Type RM Length L Ch R = 1 ,7531    ,969,969,969
BEGIN DESCRIPTION:
UNT015 IN NURI 12.0
END DESCRIPTION:
XS GIS Cut Line= 4
      2272130.67     13304037.94      2271797.86     13303606.32
        2270711.     13303616.72      2270352.46     13303673.88
#Sta/Elev= 30
  4112.9  140.65  4272.7  140.25  4393.2  139.16  4401.4  139.43  4422.2  138.93
  4451.2  139.05    4472  138.34  4480.2  138.57  4550.8  137.56  4565.3  137.77
  4594.1  136.96  4644.1  136.66  4654.4  136.13  4718.1  135.46  4808.1  133.71
  4858.1   133.4  5005.1  129.76  5007.8  129.26  5011.1  129.76  5058.1  130.35
  5068.1  129.92  5178.1  131.96  5338.1  133.15  5358.1  134.53  5368.1  133.83
  5408.1  134.37  5608.1  138.16  5768.4  140.52  5960.8  142.15  6107.9  142.26
#Mann= 3 ,-1 , 0
  4112.9     .05       0  5005.1    .035       0  5011.1     .05       0
Bank Sta=5005.1,5011.1
XS Rating Curve= 0 ,0
Exp/Cntr=0.3,0.1

Type RM Length L Ch R = 1 ,6562    ,133,133,133
BEGIN DESCRIPTION:
Mapping XS 6f93ece3
END DESCRIPTION:
XS GIS Cut Line= 4
        2272556.     13302999.81      2271733.13     13302742.88
       2271510.9     13302732.46      2270917.14      13303190.8
#Sta/Elev= 30
  3984.4  135.33  4087.4     135  4391.2   132.4    4578  131.54  4583.2  131.99
  4749.4  129.69  4813.1  126.95  4861.9  126.84  4881.9  126.07  5039.1  125.99
  5041.8  125.49  5045.1  125.99  5117.1  128.53  5131.6  129.91  5146.1  130.34
  5152.4  129.92  5181.4  131.62  5316.3  131.82    5445  133.42  5451.9  134.07
  5465.8  133.58  5552.8  136.22  5573.6  136.17  5629.7  137.59  5652.4  138.89
  5666.7  138.37  5743.8  141.04  5766.5  140.32  5793.7  141.18    5819  141.01
#Mann= 5 ,-1 , 0
  3984.4     .05       0  4749.4      .1       0  4813.1     .05       0
  5039.1    .035       0  5045.1     .05       0
Bank Sta=5039.1,5045.1
XS Rating Curve= 0 ,0
Exp/Cntr=0.3,0.1

Type RM Length L Ch R = 1 ,6429    ,92,92,92
BEGIN DESCRIPTION:
Mapping XS 20dbfe2e
END DESCRIPTION:
XS GIS Cut Line= 6
       2272580.4     13302933.86      2271844.24     13302718.57
      2271663.68     13302610.93      2271559.51     13302603.99
      2271420.63     13302708.15      2270893.49     13303162.46
#Sta/Elev= 30
  3972.4  136.25    4585  132.14  4704.5  133.14  4723.9  131.71  4729.1   133.4
  4752.7  133.69  4768.2  131.82  4774.1  133.76  4805.2  132.96  4811.1  130.57
  4816.9  134.65    4824  133.33  4828.9  133.43    4848  131.97  4853.9  134.41
  4941.3  133.99  5015.7  131.26  5052.4  133.49  5114.8  133.57  5118.1  130.23
  5120.8  129.73  5124.1  130.23  5129.4   132.8  5135.6  131.01  5150.2  133.32
  5156.5  131.06  5221.1  133.96  5327.8  131.63  5575.8  133.29  5923.5  140.84
#Mann= 7 ,-1 , 0
  3972.4     .05       0    4585      .1       0    4824     .05       0
  4828.9      .1       0  4941.3     .05       0  5118.1    .035       0
  5124.1     .05       0
Bank Sta=5118.1,5124.1
XS Rating Curve= 0 ,0
Exp/Cntr=0.3,0.1

Type RM Length L Ch R = 1 ,6337    ,172,172,172
BEGIN DESCRIPTION:
Mapping XS a01c3a0d
END DESCRIPTION:
XS GIS Cut Line= 4
      2272642.89     13302864.42      2271733.13     13302503.29
      2271434.51     13302555.38      2270761.79     13303144.88
#Sta/Elev= 30
  3892.7  136.68  4441.7  133.67  4575.7  133.76  4803.3  132.21  4871.5  130.87
  4897.3  128.08  4931.7  127.34  4981.6   127.8  4988.7  127.19  4995.8  125.24
  4998.6  124.74  5001.8  125.24  5031.9   127.4  5155.2  129.49  5180.7  131.06
  5215.9  130.39  5258.6  132.29  5513.9  132.45    5549  133.28  5598.3  132.86
    5641  134.13  5683.7  133.51  5690.4  134.29  5754.9  135.38  5775.8  134.85
  5818.5  136.49    5847  136.32    5939  138.63  6031.1  139.08  6069.1  140.21
#Mann= 7 ,-1 , 0
  3892.7     .05       0  4575.7      .1       0  4803.3     .05       0
  4931.7      .1       0  4995.8     .07       0  5001.8      .1       0
  5031.9     .05       0
Bank Sta=4995.8,5001.8
XS Rating Curve= 0 ,0
Exp/Cntr=0.3,0.1

Type RM Length L Ch R = 1 ,6165    ,437,437,437
BEGIN DESCRIPTION:
UNT015 IN NURI 11.0
END DESCRIPTION:
XS GIS Cut Line= 4
      2272531.76     13302704.69      2271771.32     13302353.99
      2271396.32      13302402.6      2270688.82     13302912.41
#Sta/Elev= 30
  4015.4  136.45  4115.6  136.07  4281.7  137.12  4317.2  135.29  4356.1  134.74
  4549.9  134.29  4711.4  133.61  4763.6  132.68  4845.8  131.99    4913  129.97
    4927  130.11  4977.4  126.56  5004.7  125.92  5007.5  125.42  5010.7  125.92
  5021.8  126.36  5046.1  126.59  5098.5  126.52  5145.6  130.22    5159  130.45
    5169  131.63  5189.2  130.61  5224.8  132.21  5276.7  132.68  5383.5  133.49
  5389.6  132.98  5469.4  132.64  5870.2  133.03  5993.3  133.63    6103  135.06
#Mann= 7 ,-1 , 0
  4015.4     .05       0  4549.9      .1       0  4763.6     .05       0
  5004.7     .03       0  5010.7     .05       0  5021.8      .1       0
  5046.1     .05       0
Bank Sta=5004.7,5010.7
XS Rating Curve= 0 ,0
Exp/Cntr=0.3,0.1