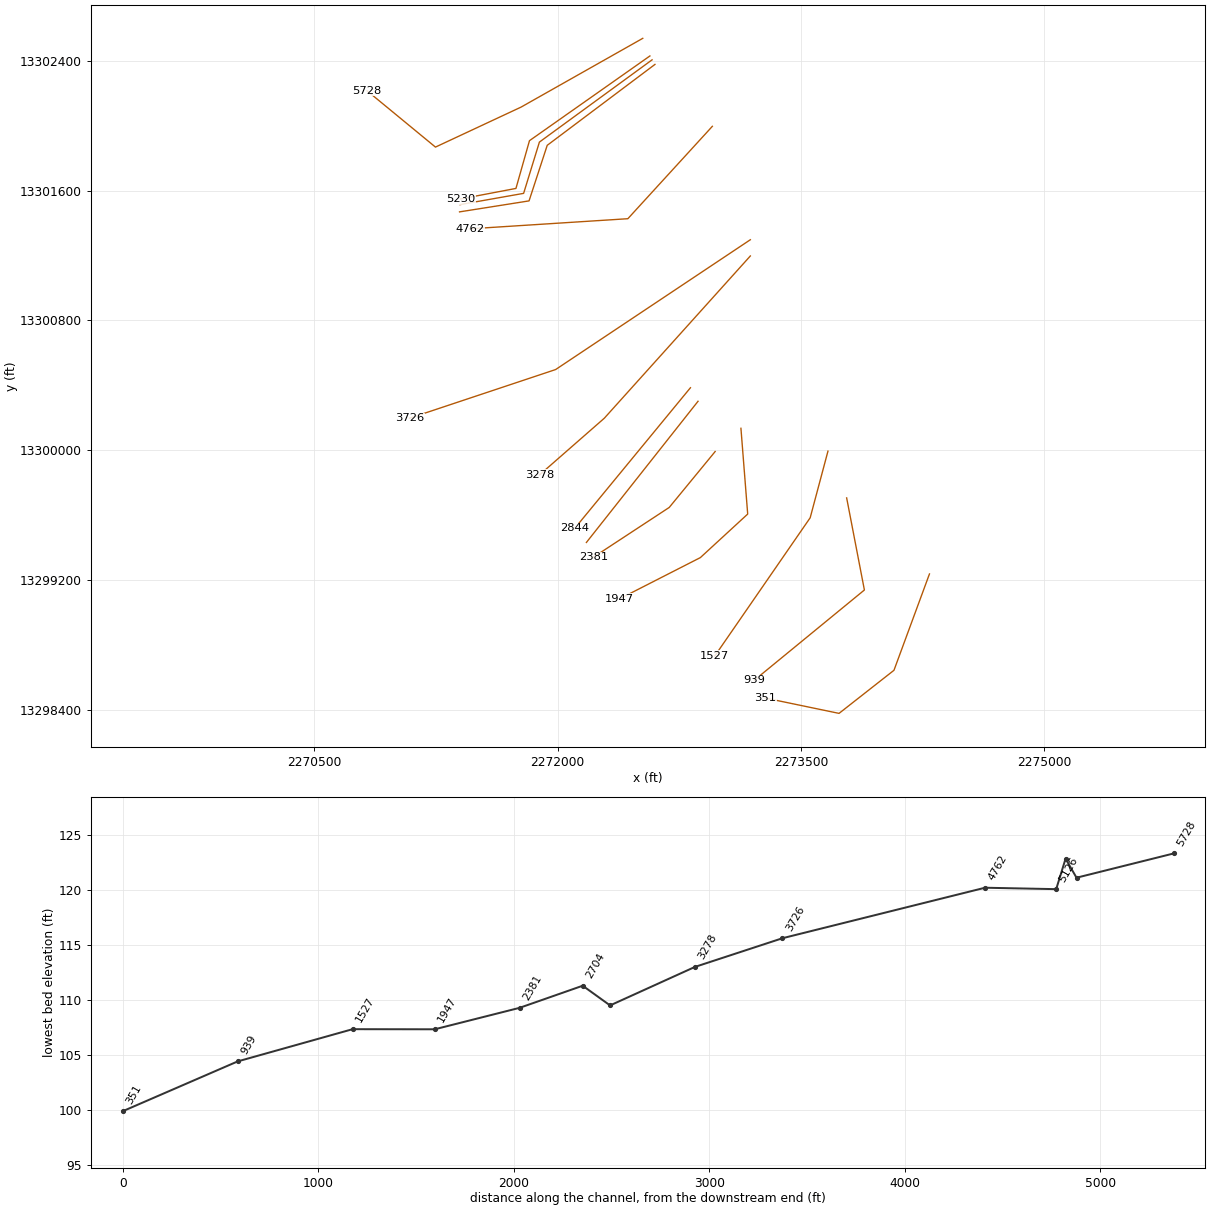
HEC-RAS study UNT015 IN NURI.prj: UNT015 IN NURI Base Level Engineering

--- UNT015 IN NURI.g01 (geometry) --- (continued)

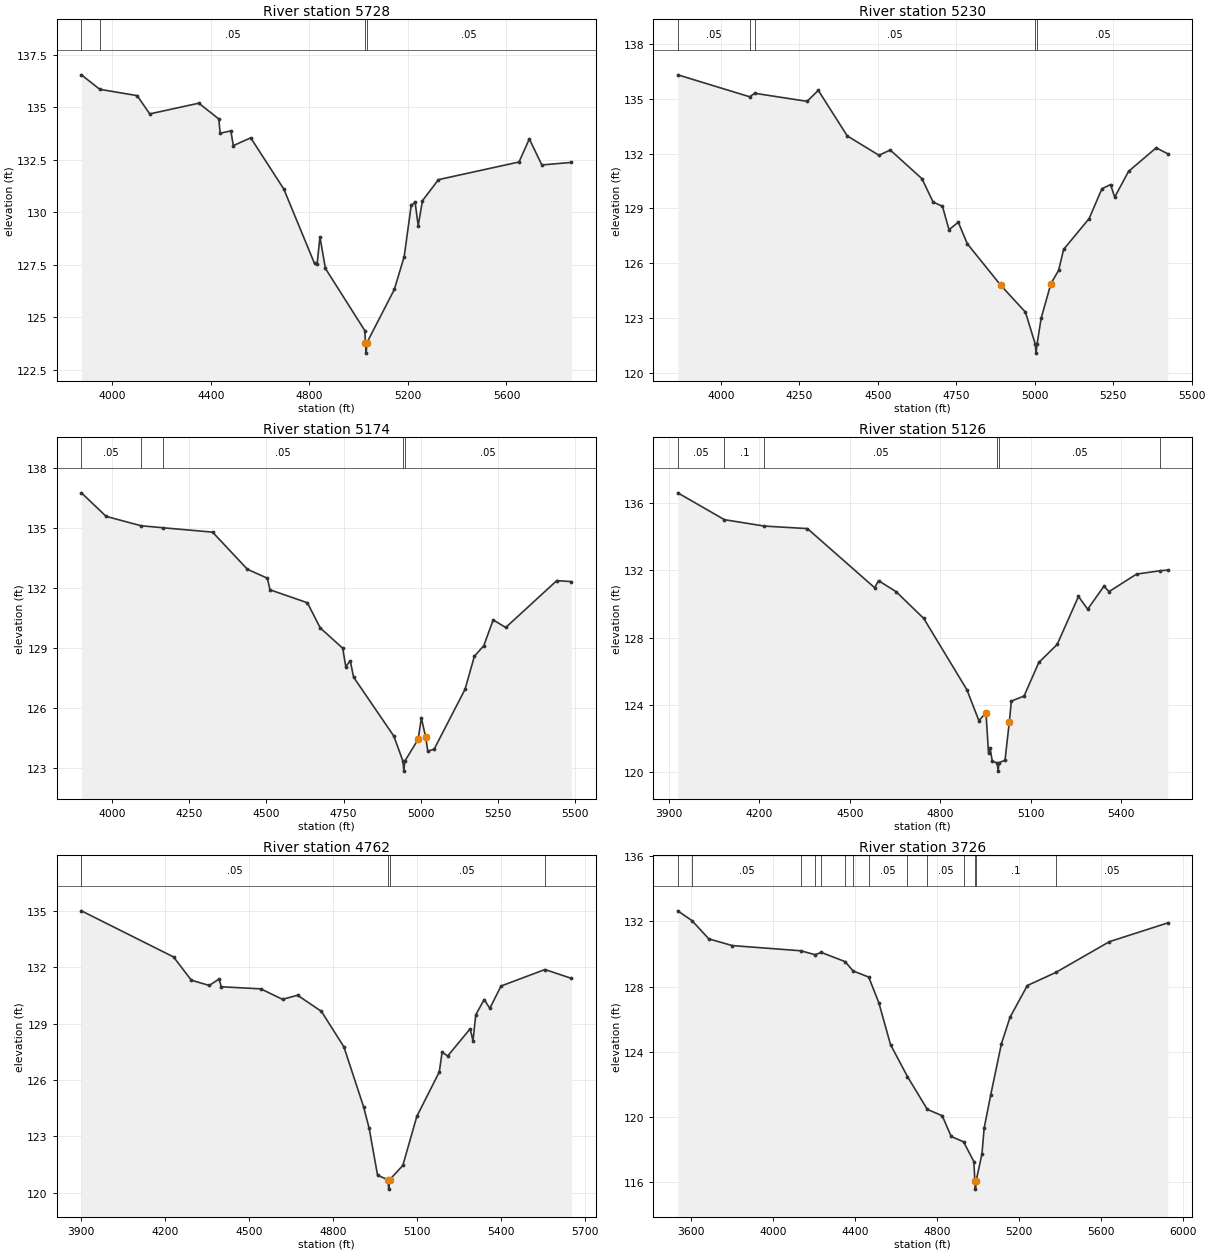
Type RM Length L Ch R = 1 ,5728    ,498,498,498
BEGIN DESCRIPTION:
UNT015 IN NURI 10.0
END DESCRIPTION:
XS GIS Cut Line= 4
      2272524.68     13302538.16      2271774.79      13302114.4
      2271247.01     13301867.88      2270825.81     13302214.58
#Sta/Elev= 30
  3874.1  136.55  3948.6  135.86  4100.3  135.56  4151.6  134.69  4350.9   135.2
  4431.7  134.45  4437.5  133.77  4480.8  133.88  4490.9  133.18  4561.6  133.55
  4695.9  131.11  4820.5  127.57    4831  127.53  4842.6  128.83  4864.9  127.33
  5024.9  124.37  5027.4   123.8  5030.1   123.3  5033.4   123.8  5144.6  126.33
  5184.7   127.9  5213.2  130.34  5228.9  130.48  5241.6  129.37  5258.9  130.56
  5323.9  131.56    5651   132.4  5692.7   133.5  5743.5  132.26  5863.5  132.38
#Mann= 4 ,-1 , 0
  3874.1      .1       0  3948.6     .05       0  5027.4     .03       0
  5033.4     .05       0
Bank Sta=5027.4,5033.4
XS Rating Curve= 0 ,0
Exp/Cntr=0.3,0.1

Type RM Length L Ch R = 1 ,5230    ,56,56,56
BEGIN DESCRIPTION:
Mapping XS a676862b
END DESCRIPTION:
XS GIS Cut Line= 4
      2272568.63     13302429.51      2271826.44     13301907.37
      2271743.11      13301613.1      2271401.71      13301548.2
#Sta/Elev= 30
    3863  136.31  4091.9  135.11  4108.4   135.3  4274.9  134.86  4310.6  135.46
  4402.9  132.97    4504  131.91  4539.7   132.2  4640.8  130.63  4676.5  129.35
  4706.1  129.12    4727  127.84  4756.6  128.25  4785.3  127.07  4892.4  124.79
  4970.6  123.33  5001.6  121.59  5004.3  121.09  5007.6  121.59  5020.4  122.99
  5051.6  124.89  5076.3  125.62    5092  126.76  5173.4  128.45  5214.1  130.08
  5241.6  130.31  5254.8  129.62  5298.9  131.03  5387.1  132.32  5423.8  131.99
#Mann= 5 ,-1 , 0
    3863     .05       0  4091.9      .1       0  4108.4     .05       0
  5001.6     .03       0  5007.6     .05       0
Bank Sta=4892.4,5051.6
XS Rating Curve= 0 ,0
Exp/Cntr=0.3,0.1

Type RM Length L Ch R = 1 ,5174    ,48,48,48
BEGIN DESCRIPTION:
Mapping XS 8b0504a3
END DESCRIPTION:
XS GIS Cut Line= 4
      2272582.12     13302405.67      2271887.64     13301898.69
      2271790.42     13301582.72      2271398.05     13301513.27
#Sta/Elev= 30
    3900  136.77  3980.1  135.59  4093.5  135.12  4163.8  135.02  4325.3   134.8
  4438.1  132.94    4503  132.49  4511.5  131.91  4632.7  131.26  4674.5     130
  4747.4  128.98  4757.2  128.06  4771.8  128.35  4782.7  127.53    4913  124.58
  4942.7  123.32  4945.5  122.82  4948.7  123.32  4991.9  124.41  5002.4  125.48
  5016.3  124.53  5023.3  123.82  5043.8  123.92    5144  126.92  5174.4  128.58
  5204.9  129.11  5235.3   130.4    5276  130.02  5441.6  132.37  5488.9  132.32
#Mann= 5 ,-1 , 0
    3900     .05       0  4093.5      .1       0  4163.8     .05       0
  4942.7     .03       0  4948.7     .05       0
Bank Sta=4991.9,5016.3
XS Rating Curve= 0 ,0
Exp/Cntr=0.3,0.1

Type RM Length L Ch R = 1 ,5126    ,364,364,364
BEGIN DESCRIPTION:
Mapping XS 0d376c28
END DESCRIPTION:
XS GIS Cut Line= 4
      2272599.85      13302377.4      2271935.82     13301878.73
      2271823.84     13301536.28      2271395.48     13301468.57
#Sta/Elev= 30
  3929.7  136.62  4084.4  135.02  4216.7  134.64  4359.5  134.49  4582.4  130.97
  4595.2  131.39  4653.2  130.74  4745.2  129.14  4888.4  124.89  4928.1  123.05
  4951.5  123.54  4959.9  121.12  4965.2  121.41  4972.5  120.63  4988.8  120.55
  4991.6  120.05  4994.8  120.55  5014.6   120.7  5028.9  122.99  5035.6  124.22
  5077.7  124.52  5126.6  126.52  5187.4  127.59  5258.2  130.45  5288.6  129.69
  5342.6  131.06  5359.5  130.74  5450.6  131.78  5528.4  131.98  5554.1  132.02
#Mann= 6 ,-1 , 0
  3929.7     .05       0  4084.4      .1       0  4216.7     .05       0
  4988.8     .03       0  4994.8     .05       0  5528.4      .1       0
Bank Sta=4951.5,5028.9
XS Rating Curve= 0 ,0
Exp/Cntr=0.3,0.1

Type RM Length L Ch R = 1 ,4762    ,1036,1036,1036
BEGIN DESCRIPTION:
UNT015 IN NURI 9.0
END DESCRIPTION:
XS GIS Cut Line= 3
      2272953.61     13301995.92      2272432.78     13301426.47
      2271457.09     13301363.97
#Sta/Elev= 30
  3900.8  135.02  4229.8  132.56  4293.3  131.32  4357.5  131.04  4392.6  131.39
    4400  130.97  4541.2  130.86  4618.9   130.3  4672.5  130.52  4757.7  129.66
  4837.9  127.77  4908.1  124.58  4928.1  123.43  4958.2  120.92  4995.2  120.68
    4998  120.18  5001.2  120.68  5048.3  121.44  5098.4  124.06  5178.6  126.43
  5188.6  127.48  5208.7  127.28  5288.8  128.73  5298.9  128.09  5308.9  129.48
  5338.9  130.29    5359  129.82  5399.1  131.01  5555.8  131.89  5650.2  131.42
#Mann= 4 ,-1 , 0
  3900.8     .05       0  4995.2     .03       0  5001.2     .05       0
  5555.8      .1       0
Bank Sta=4995.2,5001.2
XS Rating Curve= 0 ,0
Exp/Cntr=0.3,0.1

Type RM Length L Ch R = 1 ,3726    ,448,448,448
BEGIN DESCRIPTION:
UNT015 IN NURI 8.0
END DESCRIPTION:
XS GIS Cut Line= 3
      2273187.69     13301296.84      2271987.72     13300496.85
      2271087.69     13300196.85
#Sta/Elev= 30
  3535.5  132.65  3604.6  132.05  3687.2  130.93  3801.4  130.52  4136.6   130.2
  4205.5  129.96  4235.7   130.1  4351.4  129.54  4391.8  128.96  4467.1  128.59
  4516.5  127.02  4573.6  124.45  4656.3  122.49  4753.1  120.48    4826  120.09
  4869.5  118.82  4930.1  118.49  4980.3  117.28  4985.2  116.09    4988  115.59
  4991.2  116.09  5019.9  117.75  5030.4  119.32    5062  121.33  5114.7   124.5
  5156.9  126.13  5241.2  128.07  5379.8  128.87  5641.8  130.76  5926.4  131.91
#Mann= 14 ,-1 , 0
  3535.5      .1       0  3604.6     .05       0  4136.6      .1       0
  4205.5     .05       0  4235.7      .1       0  4351.4     .05       0
  4391.8      .1       0  4467.1     .05       0  4656.3      .1       0
  4753.1     .05       0  4930.1      .1       0  4985.2     .07       0
  4991.2      .1       0  5379.8     .05       0
Bank Sta=4985.2,4991.2
XS Rating Curve= 0 ,0
Exp/Cntr=0.3,0.1

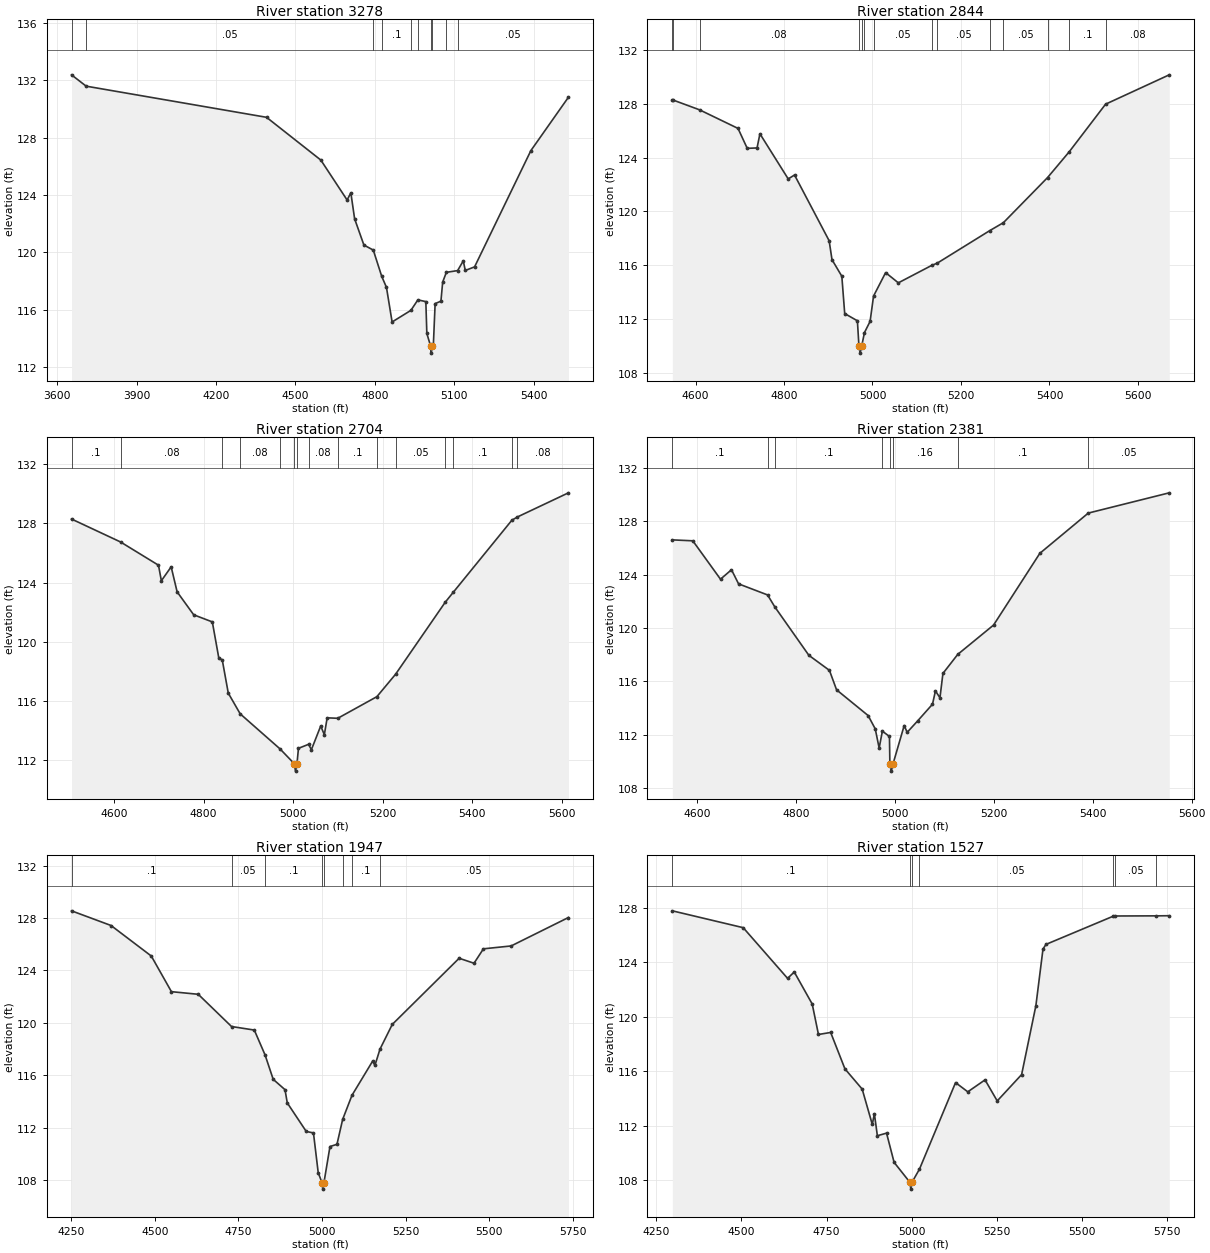
Type RM Length L Ch R = 1 ,3278    ,434,434,434
BEGIN DESCRIPTION:
UNT015 IN NURI 7.0
END DESCRIPTION:
XS GIS Cut Line= 3
       2273187.7     13301196.83      2272287.72     13300196.85
      2271887.75     13299846.88
#Sta/Elev= 30
  3654.4  132.37  3709.7  131.58    4391  129.41  4596.1  126.43  4695.2  123.65
  4709.4  124.15  4723.6  122.34  4758.7  120.51  4794.1  120.16    4826  118.33
  4843.9  117.56  4865.2  115.15  4936.2  115.96  4962.5  116.69  4992.6  116.57
  4996.4  114.35  5010.5  113.48  5013.2  112.98  5016.5  113.48  5021.1  113.58
  5027.7  116.43  5049.6   116.6  5056.2  117.93  5070.1  118.61  5112.6  118.73
    5134  119.41  5141.6  118.74  5176.7  118.99  5389.3  127.09  5531.2  130.81
#Mann= 10 ,-1 , 0
  3654.4      .1       0  3709.7     .05       0  4794.1     .16       0
    4826      .1       0  4936.2     .16       0  4962.5      .1       0
  5010.5     .07       0  5016.5      .1       0  5070.1     .16       0
  5112.6     .05       0
Bank Sta=5010.5,5016.5
XS Rating Curve= 0 ,0
Exp/Cntr=0.3,0.1

Type RM Length L Ch R = 1 ,2844    ,140,140,140
BEGIN DESCRIPTION:
Mapping XS 83fdaf0f
END DESCRIPTION:
XS GIS Cut Line= 2
      2272818.57     13300384.75      2272104.97     13299517.49
#Sta/Elev= 30
  4547.6  128.27  4549.9  128.27  4609.2  127.55  4696.1  126.17  4716.9  124.69
  4739.1  124.72  4745.6  125.77  4809.5  122.42  4823.8  122.71    4902  117.83
  4908.5  116.42  4930.7  115.19  4937.2  112.42  4965.9  111.88  4969.4  109.98
  4972.1  109.48  4975.4  109.98  4981.9  111.01  4994.6  111.84  5002.4  113.72
  5029.7  115.46  5058.4   114.7  5133.5  115.99  5146.7  116.17  5264.6  118.57
  5295.9  119.17  5395.7  122.52    5445  124.45  5526.8  127.97  5670.7  130.15
#Mann= 14 ,-1 , 0
  4547.6     .08       0  4549.9      .1       0  4609.2     .08       0
  4969.4     .07       0  4975.4     .08       0  4981.9      .1       0
  5002.4     .05       0  5133.5     .08       0  5146.7     .05       0
  5264.6     .08       0  5295.9     .05       0  5395.7     .08       0
    5445      .1       0  5526.8     .08       0
Bank Sta=4969.4,4975.4
XS Rating Curve= 0 ,0
Exp/Cntr=0.3,0.1

Type RM Length L Ch R = 1 ,2704    ,323,323,323
BEGIN DESCRIPTION:
UNT015 IN NURI 6.0
END DESCRIPTION:
XS GIS Cut Line= 2
      2272865.41     13300301.37      2272177.24     13299431.07
#Sta/Elev= 30
  4504.9   128.3  4614.4  126.75  4699.1  125.18  4705.5  124.13  4727.4  125.07
  4740.7  123.38  4777.7  121.83  4819.3  121.35  4833.7  118.92  4841.5  118.78
  4854.9  116.54  4881.5  115.14  4970.5  112.77  5002.3  111.77    5005  111.27
  5008.3  111.77  5011.6  112.81  5034.1  113.08  5040.5  112.72  5061.3  114.32
  5069.4  113.73  5075.7  114.87  5099.4  114.84  5186.7   116.3  5228.3  117.81
  5339.3  122.68  5357.2  123.35  5488.1  128.22  5500.5  128.44  5614.4  130.07
#Mann= 15 ,-1 , 0
  4504.9      .1       0  4614.4     .08       0  4841.5     .16       0
  4881.5     .08       0  4970.5      .1       0  5002.3     .07       0
  5008.3      .1       0  5034.1     .08       0  5099.4      .1       0
  5186.7     .08       0  5228.3     .05       0  5339.3     .08       0
  5357.2      .1       0  5488.1     .05       0  5500.5     .08       0
Bank Sta=5002.3,5008.3
XS Rating Curve= 0 ,0
Exp/Cntr=0.3,0.1

Type RM Length L Ch R = 1 ,2381    ,434,434,434
BEGIN DESCRIPTION:
UNT015 IN NURI 5.0
END DESCRIPTION:
XS GIS Cut Line= 3
      2272970.89     13299991.49      2272687.72     13299646.85
      2272220.85     13299340.42
#Sta/Elev= 30
  4550.2  126.61  4591.6  126.54  4647.6  123.66  4669.8  124.37  4684.1  123.31
  4742.7  122.48  4757.4  121.58  4826.2  117.95  4867.8  116.82  4882.2  115.36
    4946  113.43  4960.4  112.43  4968.3  110.99  4974.8  112.26  4989.1  111.86
    4990  109.76  4992.8  109.26    4996  109.76  5018.9  112.68  5024.9  112.17
  5045.9  113.02  5076.1  114.28  5082.1  115.28  5091.2  114.76  5097.2  116.59
  5127.2  118.02  5199.6  120.22  5293.1   125.6    5391  128.62  5554.7  130.14
#Mann= 8 ,-1 , 0
  4550.2      .1       0  4742.7     .16       0  4757.4      .1       0
  4974.8     .16       0    4990     .07       0    4996     .16       0
  5127.2      .1       0    5391     .05       0
Bank Sta=4990,4996
XS Rating Curve= 0 ,0
Exp/Cntr=0.3,0.1

Type RM Length L Ch R = 1 ,1947    ,420,420,420
BEGIN DESCRIPTION:
UNT015 IN NURI 4.0
END DESCRIPTION:
XS GIS Cut Line= 4
      2273129.74     13300134.71      2273171.41     13299606.07
      2272879.74     13299337.84      2272381.25      13299083.4
#Sta/Elev= 30
  4251.1  128.55  4369.3  127.43  4489.7   125.1  4549.9  122.38  4630.1  122.18
  4729.7  119.72  4797.8  119.45    4830  117.55  4854.3  115.69  4889.6   114.9
  4896.4  113.89  4953.2  111.71  4974.7   111.6  4988.9  108.57  5000.1  107.81
  5002.8  107.31  5006.1  107.81  5024.1  110.56    5045  110.73    5062  112.63
  5089.9  114.47  5151.7  117.08  5158.5  116.75  5173.6  117.99  5210.4  119.88
  5410.4  124.93  5454.9  124.55    5483  125.65    5566  125.87  5737.3  128.04
#Mann= 8 ,-1 , 0
  4251.1      .1       0  4729.7     .05       0    4830      .1       0
  5000.1     .07       0  5006.1      .1       0    5062     .05       0
  5089.9      .1       0  5173.6     .05       0
Bank Sta=5000.1,5006.1
XS Rating Curve= 0 ,0
Exp/Cntr=0.3,0.1

Type RM Length L Ch R = 1 ,1527    ,588,588,588
BEGIN DESCRIPTION:
UNT015 IN NURI 3.0
END DESCRIPTION:
XS GIS Cut Line= 3
      2273666.19     13299994.06      2273556.54     13299583.21
      2272968.57     13298731.48
#Sta/Elev= 30
  4296.8   127.8  4505.1  126.56  4635.5  122.83  4655.1   123.3  4707.9  120.94
  4726.2   118.7  4762.1  118.85    4804  116.17  4854.7  114.68  4884.4  112.08
  4890.5  112.87  4899.3  111.25  4926.3  111.44  4948.5  109.29    4995  107.82
  4997.7  107.32    5001  107.82    5023  108.79  5129.1  115.16    5165  114.48
  5215.7  115.36  5251.5  113.81  5323.2  115.75  5365.1  120.82    5386  124.99
  5394.8  125.33  5592.9  127.41  5598.7  127.42    5718  127.43    5757  127.44
#Mann= 7 ,-1 , 0
  4296.8      .1       0    4995     .07       0    5001      .1       0
    5023     .05       0  5592.9      .1       0  5598.7     .05       0
    5718     .08       0
Bank Sta=4995,5001
XS Rating Curve= 0 ,0
Exp/Cntr=0.3,0.1

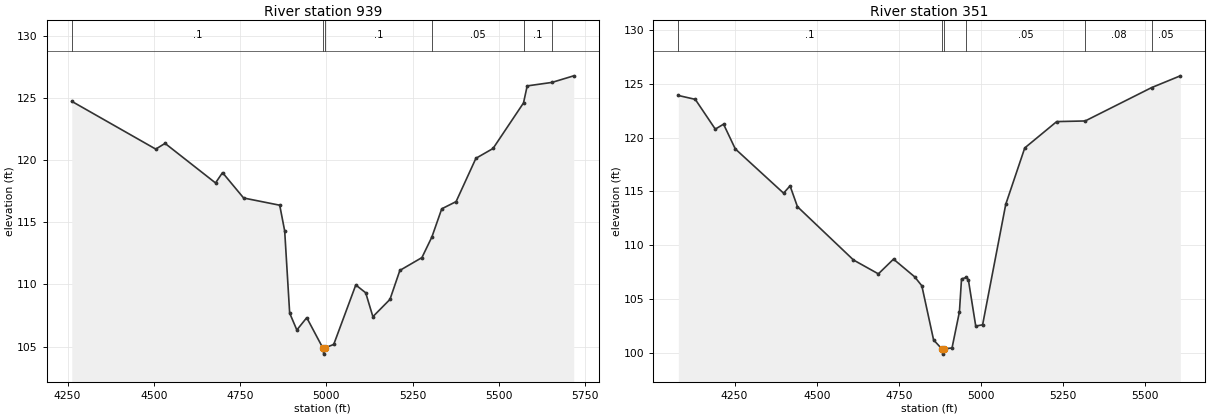
Type RM Length L Ch R = 1 ,939     ,588,588,588
BEGIN DESCRIPTION:
UNT015 IN NURI 2.0
END DESCRIPTION:
XS GIS Cut Line= 3
      2273781.31     13299705.79      2273890.68      13299138.1
      2273213.08     13298582.64
#Sta/Elev= 30
  4262.2  124.71  4505.5  120.87  4532.5  121.33  4678.7  118.15    4699  118.98
  4760.1  116.94  4864.7  116.36  4879.1  114.29  4893.5  107.69  4914.3  106.33
    4943  107.32  4989.5  104.89  4992.2  104.39  4995.5  104.89  5021.2  105.17
  5085.1  109.95  5113.8  109.32  5134.6   107.4  5184.1  108.79  5212.8  111.12
  5276.7  112.15  5305.6  113.81  5334.1  116.07  5375.7  116.65  5433.1  120.13
  5482.7  120.92    5571  124.58  5581.7  125.95  5653.3  126.23  5716.5  126.76
#Mann= 6 ,-1 , 0
  4262.2      .1       0  4989.5     .07       0  4995.5      .1       0
  5305.6     .05       0    5571      .1       0  5653.3     .08       0
Bank Sta=4989.5,4995.5
XS Rating Curve= 0 ,0
Exp/Cntr=0.3,0.1

Type RM Length L Ch R = 1 ,351     ,0,0,0
BEGIN DESCRIPTION:
UNT015 IN NURI 1.0
END DESCRIPTION:
XS GIS Cut Line= 4
      2274291.71     13299237.04      2274072.97     13298643.31
      2273734.43     13298377.69       2273279.3     13298472.25
#Sta/Elev= 30
  4078.8  123.93  4130.3  123.57  4191.2   120.8  4216.4  121.26  4252.1  118.96
  4399.1  114.84  4418.8  115.52  4441.3  113.58  4611.9  108.62  4687.6  107.33
  4733.7   108.7  4797.9  107.06  4819.9  106.22  4855.7  101.18  4880.5  100.36
  4883.2   99.86  4886.5  100.36  4911.8  100.43  4934.3  103.79  4940.7  106.85
  4955.4     107  4961.5  106.79    4984  102.47  5004.9  102.59  5075.4  113.81
  5133.2  119.05  5230.4   121.5  5317.2  121.56    5519  124.66  5606.7  125.76
#Mann= 6 ,-1 , 0
  4078.8      .1       0  4880.5    .035       0  4886.5      .1       0
  4955.4     .05       0  5317.2     .08       0    5519     .05       0
Bank Sta=4880.5,4886.5
XS Rating Curve= 0 ,0
Exp/Cntr=0.3,0.1

Chan Stop Cuts=-1
Use User Specified Reach Order=0
Composite Channel Slope=5