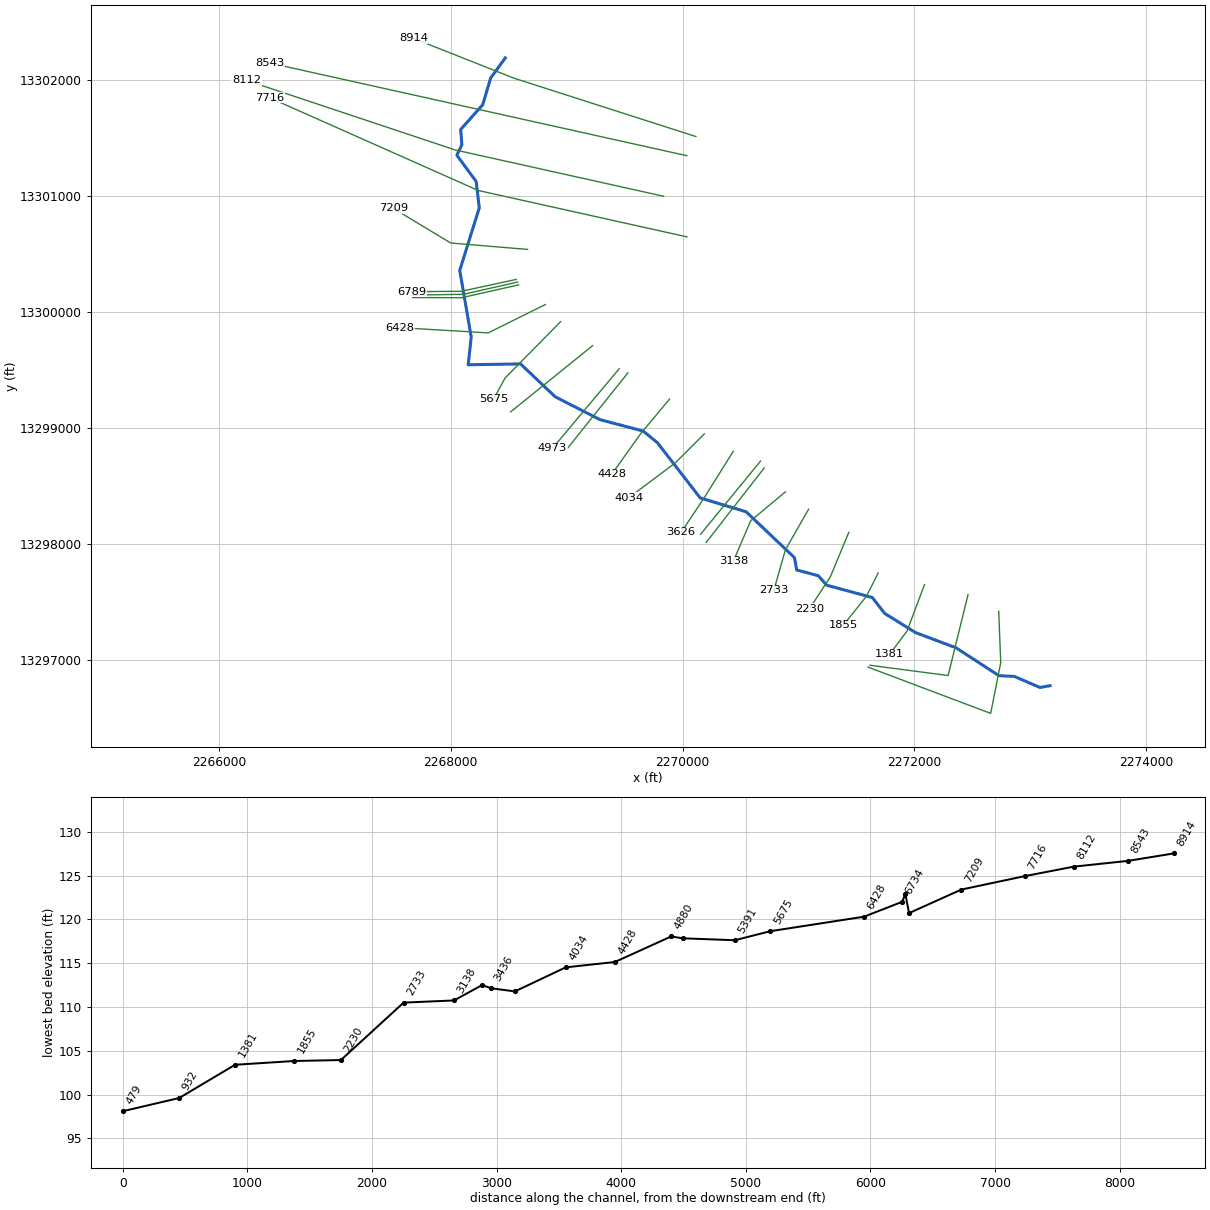
--- UNT016 IN NURI.prj (project) ---

Proj Title=UNT016 IN NURI Base Level Engineering
Current Plan=p01
Default Exp/Contr=0.3,0.1
English Units
Geom File=g01
Flow File=f01
Plan File=p01
Y Axis Title=Elevation
X Axis Title(PF)=Main Channel Distance
X Axis Title(XS)=Station
BEGIN DESCRIPTION:
UNT016 IN NURI
END DESCRIPTION:
DSS Export Rating Curves= 0
DSS Export Rating Curve Sorted= 0
DSS Export Volume Flow Curves= 0
DXF OffsetX= 0
DXF OffsetY= 0
DXF ScaleX= 1
DXF ScaleY= 10

--- UNT016 IN NURI.p01 (plan) ---

Plan Title=Multiple Run
Short Identifier=Multiple
Geom File=g01
Flow File=f01
Subcritical Flow
K Sum by GR= 0
Std Step Tol= 0.01
Critical Tol= 0.01
Num of Std Step Trials= 20
Max Error Tol= 0.3
Flow Tol Ratio= 0.001
Split Flow NTrial= 30
Split Flow Tol= 0.02
Split Flow Ratio= 0.02
Log Output Level= 0
Friction Slope Method= 1
Unsteady Friction Slope Method= 2
Unsteady Bridges Friction Slope Method= 1
Parabolic Critical Depth
Global Vel Dist=  1 , 1 , 1
Global Log Level= 0
CheckData=True
Encroach Param= -1, 0, 0, 0
BEGIN DESCRIPTION:
Multiple Run
END DESCRIPTION:

--- UNT016 IN NURI.f01 (steady flow) ---

Flow Title=Multiple
Program Version=4.10
Number of Profiles= 7
Profile Names=10-year,25-year,50-year,1pct_min,100-year,1pct_plu,500-year
River Rch & RM=UNT016 IN NURI,Reach-1         ,8914
     243     330     399     356     481     651     709
Boundary for River Rch & Prof#=UNT016 IN NURI,Reach-1         , 1
Up Type= 0
Dn Type= 3
Dn Slope=0.005
Boundary for River Rch & Prof#=UNT016 IN NURI,Reach-1         , 2
Up Type= 0
Dn Type= 3
Dn Slope=0.005
Boundary for River Rch & Prof#=UNT016 IN NURI,Reach-1         , 3
Up Type= 0
Dn Type= 3
Dn Slope=0.005
Boundary for River Rch & Prof#=UNT016 IN NURI,Reach-1         , 4
Up Type= 0
Dn Type= 3
Dn Slope=0.005
Boundary for River Rch & Prof#=UNT016 IN NURI,Reach-1         , 5
Up Type= 0
Dn Type= 3
Dn Slope=0.005
Boundary for River Rch & Prof#=UNT016 IN NURI,Reach-1         , 6
Up Type= 0
Dn Type= 3
Dn Slope=0.005
Boundary for River Rch & Prof#=UNT016 IN NURI,Reach-1         , 7
Up Type= 0
Dn Type= 3
Dn Slope=0.005
DSS Import GetInterval= 0
DSS Import GetPeak= 0
DSS Import FillOption= 0

--- UNT016 IN NURI.g01 (geometry) ---

Geom Title=Existing Conditions

River Reach=UNT016 IN NURI,Reach-1
Reach XY= 30
      2268470.95     13302190.64      2268345.08     13302018.11
      2268275.64     13301785.91      2268085.97     13301573.23
      2268096.18     13301442.57      2268053.01     13301350.79
      2268219.78     13301124.20      2268246.25     13300896.49
      2268077.84     13300357.62      2268176.93     13299782.09
      2268150.77     13299543.30      2268602.36     13299550.68
      2268901.32     13299267.00      2269288.85     13299069.58
      2269660.12     13298971.28      2269783.51     13298870.68
      2270152.71     13298394.08      2270548.06     13298275.09
      2270965.62     13297879.52      2270985.44     13297772.39
      2271170.48     13297723.74      2271244.61     13297641.13
      2271637.06     13297535.22      2271744.33     13297397.85
      2272011.79     13297231.71      2272360.20     13297101.10
      2272730.01     13296860.71      2272861.79     13296854.72
      2273083.72     13296758.99      2273171.47     13296774.49

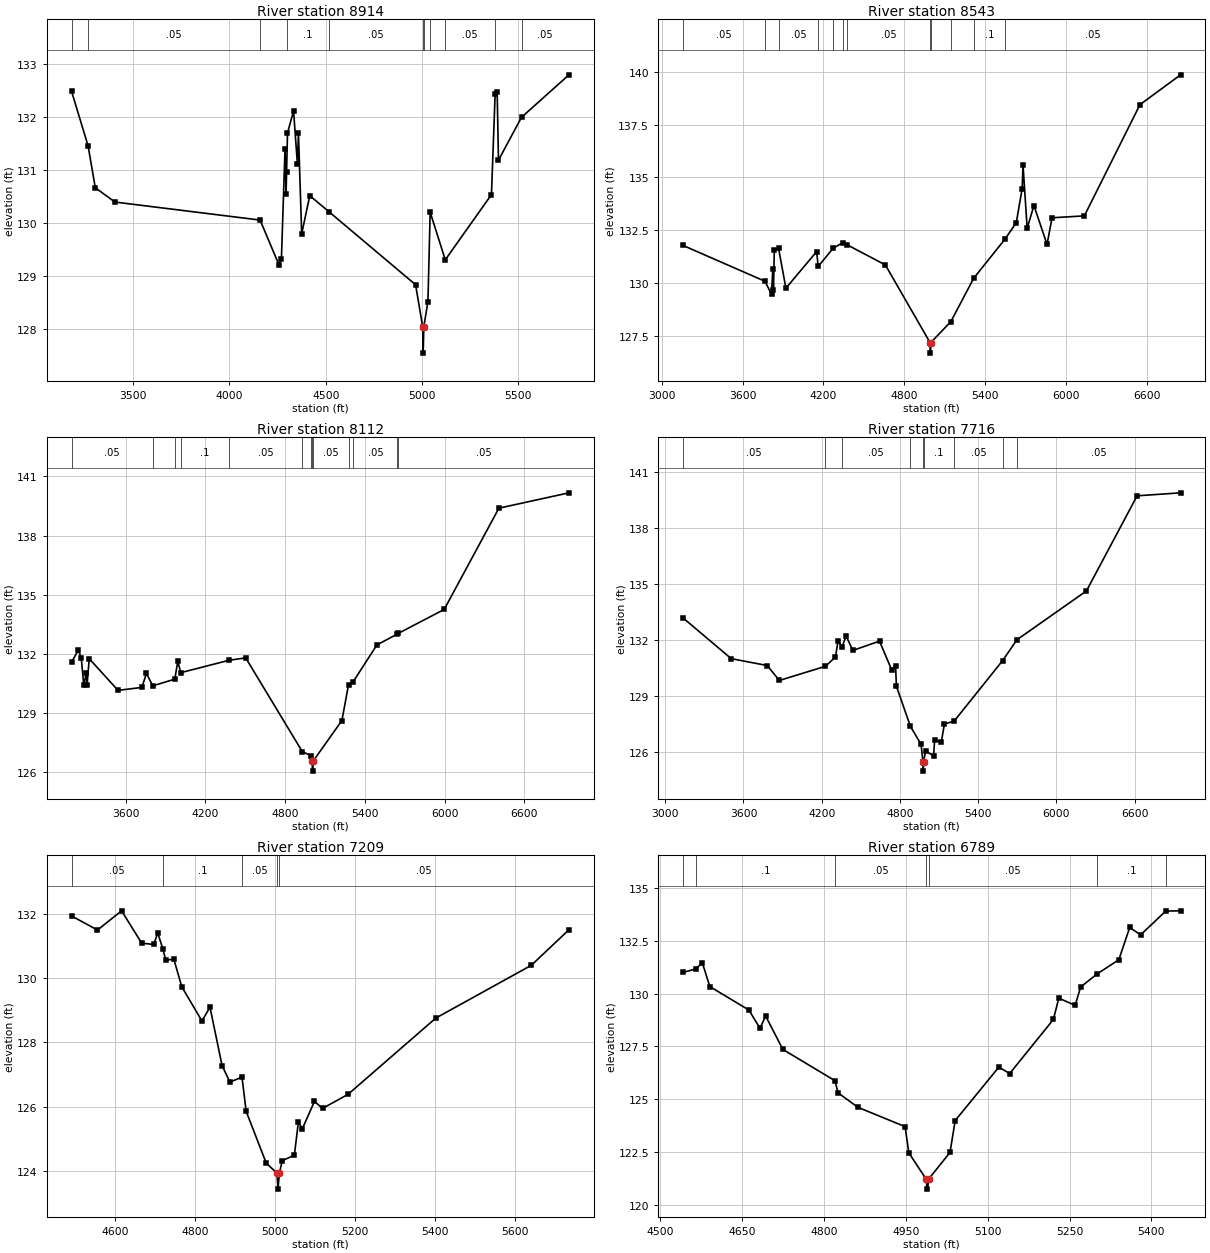
Type RM Length L Ch R = 1,8914,371,371,371
BEGIN DESCRIPTION:
UNT016 IN NURI 20.0
END DESCRIPTION:
XS GIS Cut Line= 3
      2270115.09     13301512.39      2268545.68     13302015.85
      2267677.65     13302359.59
#Sta/Elev= 30
  3180.6  132.49  3266.5  131.46  3303.9  130.67  3405.8  130.40  4159.3  130.06
  4256.7  129.22  4270.0  129.33  4288.8  131.41  4294.1  130.56  4296.7  130.96
  4301.5  131.70  4333.0  132.12  4353.1  131.11  4358.3  131.71  4375.1  129.80
  4417.1  130.52  4515.9  130.22  4966.4  128.84  5003.1  128.05  5005.8  127.55
  5009.1  128.05  5030.4  128.52  5042.0  130.21  5120.4  129.31  5360.1  130.54
  5379.3  132.44  5389.8  132.47  5396.6  131.19  5516.4  132.00  5762.4  132.80
#Mann=11,-1,0
  3180.6     0.1       0  3266.5    0.05       0  4159.3    0.08       0
  4296.7     0.1       0  4515.9    0.05       0  5003.1   0.035       0
  5009.1    0.05       0  5042.0    0.08       0  5120.4    0.05       0
  5379.3    0.08       0  5516.4    0.05       0
Bank Sta=5003.1,5009.1
Exp/Cntr=0.3,0.1

Type RM Length L Ch R = 1,8543,431,431,431
BEGIN DESCRIPTION:
UNT016 IN NURI 19.0
END DESCRIPTION:
XS GIS Cut Line= 3
      2270037.70     13301346.86      2268237.72     13301746.85
      2266437.72     13302146.86
#Sta/Elev= 30
  3159.8  131.78  3766.0  130.09  3815.4  129.47  3824.4  130.66  3829.5  129.67
  3835.9  131.58  3867.3  131.65  3921.7  129.76  4149.6  131.49  4161.1  130.79
  4272.3  131.65  4342.1  131.91  4373.6  131.82  4659.2  130.86  4990.4  127.19
  4993.2  126.69  4996.4  127.19  5144.6  128.18  5314.0  130.23  5545.9  132.08
  5629.8  132.86  5673.4  134.47  5679.8  135.58  5710.5  132.59  5760.5  133.67
  5857.8  131.83  5894.9  133.09  6134.4  133.18  6546.7  138.44  6847.6  139.85
#Mann=12,-1,0
  3159.8    0.05       0  3766.0    0.08       0  3867.3    0.05       0
  4161.1     0.1       0  4272.3    0.05       0  4342.1     0.1       0
  4373.6    0.05       0  4990.4    0.03       0  4996.4    0.05       0
  5144.6    0.08       0  5314.0     0.1       0  5545.9    0.05       0
Bank Sta=4990.4,4996.4
Exp/Cntr=0.3,0.1

Type RM Length L Ch R = 1,8112,396,396,396
BEGIN DESCRIPTION:
UNT016 IN NURI 18.0
END DESCRIPTION:
XS GIS Cut Line= 3
      2269837.73     13300996.85      2268037.72     13301396.85
      2266237.70     13301996.86
#Sta/Elev= 30
  3193.8  131.57  3245.0  132.19  3266.8  131.80  3286.0  130.39  3305.2  131.04
  3310.3  130.40  3327.0  131.75  3543.4  130.14  3722.7  130.29  3757.2  131.00
  3804.7  130.37  3970.3  130.71  3992.8  131.61  4015.6  131.04  4379.6  131.67
  4503.8  131.79  4929.6  127.03  4996.5  126.82  5004.0  126.54  5006.7  126.04
  5010.0  126.54  5227.5  128.61  5277.1  130.43  5313.2  130.59  5491.0  132.45
  5644.5  133.00  5650.3  133.03  5996.9  134.25  6408.0  139.39  6935.1  140.17
#Mann=13,-1,0
  3193.8    0.05       0  3804.7     0.1       0  3970.3    0.05       0
  4015.6     0.1       0  4379.6    0.05       0  4929.6     0.1       0
  4996.5    0.05       0  5004.0    0.03       0  5010.0    0.05       0
  5277.1    0.08       0  5313.2    0.05       0  5644.5     0.1       0
  5650.3    0.05       0
Bank Sta=5004,5010
Exp/Cntr=0.3,0.1

Type RM Length L Ch R = 1,7716,507,507,507
BEGIN DESCRIPTION:
UNT016 IN NURI 17.0
END DESCRIPTION:
XS GIS Cut Line= 3
      2270037.70     13300646.86      2268237.72     13301046.85
      2266437.68     13301846.87
#Sta/Elev= 30
  3137.5  133.16  3506.3  130.98  3782.8  130.61  3875.0  129.81  4228.7  130.57
  4305.3  131.07  4325.8  131.95  4355.6  131.60  4387.2  132.19  4438.5  131.42
  4643.3  131.92  4735.5  130.39  4766.3  130.61  4772.7  129.50  4880.1  127.35
  4962.2  126.38  4975.8  125.45  4978.6  124.95  4981.8  125.45  4995.8  126.04
  5058.0  125.76  5065.5  126.60  5117.5  126.53  5140.7  127.47  5216.4  127.64
  5587.5  130.88  5696.4  131.99  6229.6  134.61  6618.1  139.71  6951.2  139.87
#Mann=9,-1,0
  3137.5    0.05       0  4228.7     0.1       0  4355.6    0.05       0
  4880.1     0.1       0  4975.8    0.07       0  4981.8     0.1       0
  5216.4    0.05       0  5587.5    0.08       0  5696.4    0.05       0
Bank Sta=4975.8,4981.8
Exp/Cntr=0.3,0.1

Type RM Length L Ch R = 1,7209,420,420,420
BEGIN DESCRIPTION:
UNT016 IN NURI 16.0
END DESCRIPTION:
XS GIS Cut Line= 3
      2268662.30     13300538.57      2267999.62     13300593.86
      2267505.34     13300892.16
#Sta/Elev= 30
  4491.8  131.95  4556.6  131.51  4616.8  132.11  4667.0  131.10  4697.1  131.06
  4707.1  131.42  4719.6  130.93  4727.2  130.57  4747.3  130.60  4767.1  129.74
  4817.5  128.67  4837.6  129.10  4867.7  127.28  4887.4  126.76  4917.5  126.92
  4927.9  125.85  4978.1  124.23  5004.8  123.92  5007.5  123.42  5010.8  123.92
  5018.2  124.31  5048.3  124.48  5058.3  125.51  5068.4  125.31  5098.5  126.16
  5118.6  125.94  5182.4  126.38  5401.5  128.76  5640.2  130.41  5734.1  131.52
#Mann=5,-1,0
  4491.8    0.05       0  4719.6     0.1       0  4917.5    0.05       0
  5004.8   0.035       0  5010.8    0.05       0
Bank Sta=5004.8,5010.8
Exp/Cntr=0.3,0.1

Type RM Length L Ch R = 1,6789,30,30,30
BEGIN DESCRIPTION:
Mapping XS a1fa5791
END DESCRIPTION:
XS GIS Cut Line= 3
      2268565.55     13300279.61      2268091.63     13300177.19
      2267664.50     13300173.72
#Sta/Elev= 30
  4541.5  131.00  4564.8  131.17  4576.7  131.46  4590.4  130.33  4662.0  129.22
  4682.5  128.35  4692.7  128.94  4724.4  127.35  4819.8  125.87  4825.7  125.29
  4861.9  124.61  4948.5  123.69  4955.3  122.45  4986.4  121.23  4989.2  120.73
  4992.4  121.23  5030.8  122.47  5040.3  123.98  5120.3  126.51  5140.3  126.21
  5220.3  128.77  5230.3  129.78  5260.3  129.44  5270.3  130.31  5300.6  130.93
  5340.3  131.60  5360.3  133.13  5380.3  132.78  5426.4  133.91  5453.5  133.92
#Mann=7,-1,0
  4541.5    0.05       0  4564.8     0.1       0  4819.8    0.05       0
  4986.4   0.035       0  4992.4    0.05       0  5300.6     0.1       0
  5426.4    0.05       0
Bank Sta=4986.4,4992.4
Exp/Cntr=0.3,0.1

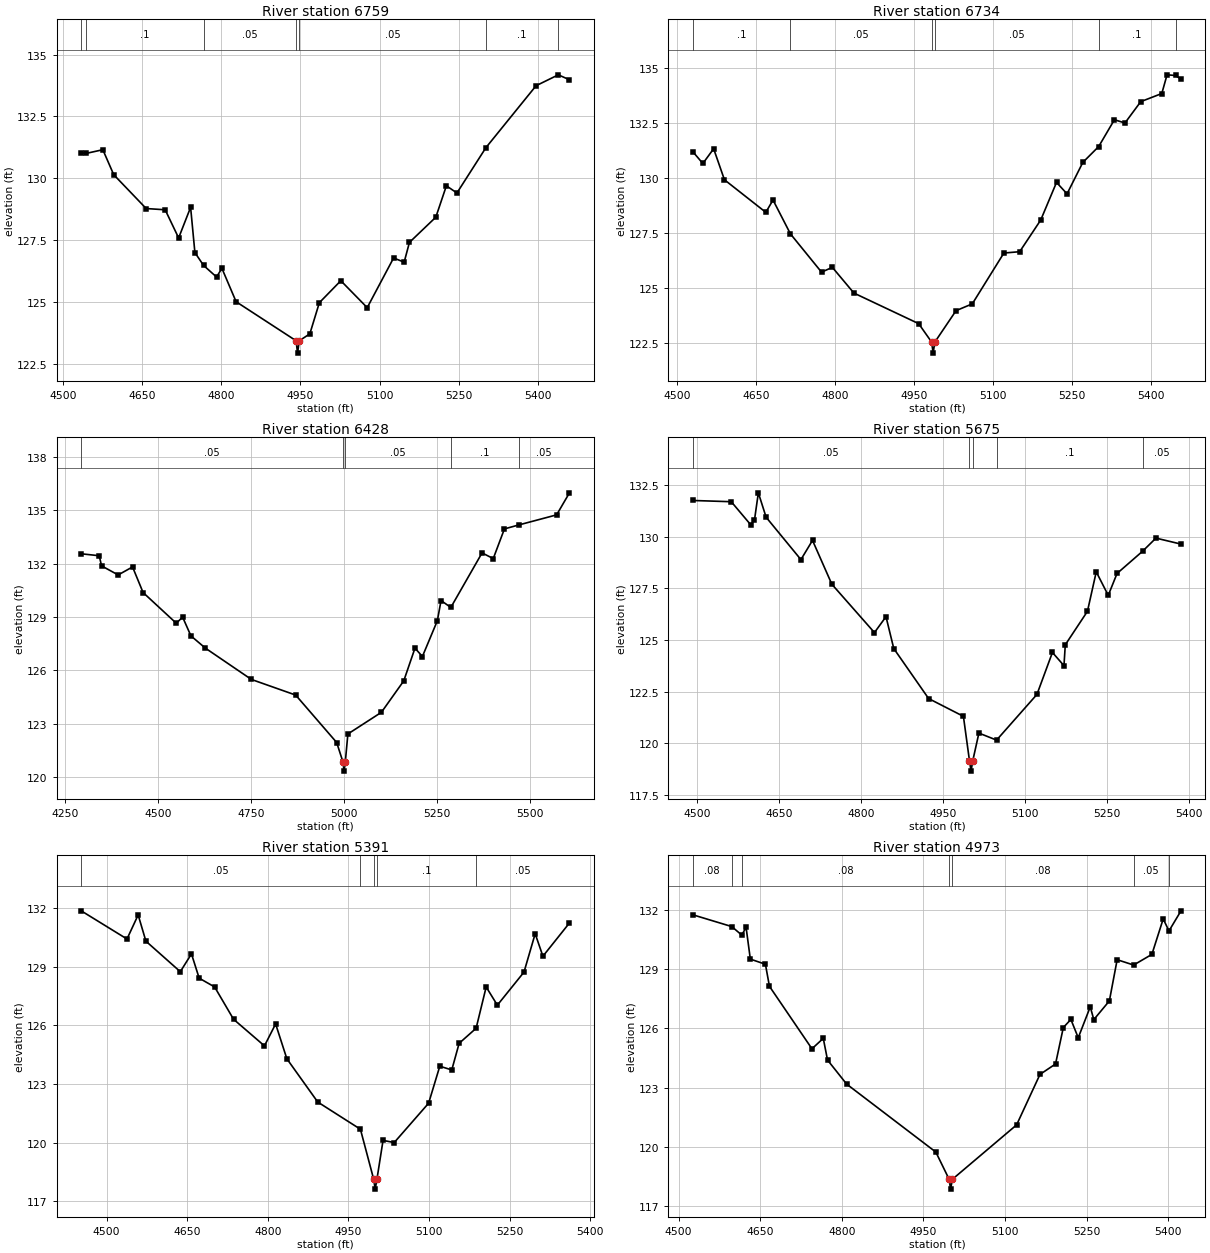
Type RM Length L Ch R = 1,6759,25,25,25
BEGIN DESCRIPTION:
UNT016 IN NURI 15.0
END DESCRIPTION:
XS GIS Cut Line= 3
      2268577.75     13300257.06      2268110.73     13300151.15
      2267664.56     13300144.21
#Sta/Elev= 30
  4534.6  131.03  4543.8  131.00  4575.6  131.15  4596.2  130.14  4657.7  128.77
  4693.7  128.72  4719.2  127.58  4741.9  128.82  4750.0  126.99  4766.4  126.47
  4791.0  126.00  4801.2  126.35  4828.1  125.00  4941.8  123.42  4944.5  122.92
  4947.8  123.42  4967.8  123.70  4985.8  124.96  5026.5  125.85  5076.5  124.76
  5126.5  126.77  5146.5  126.60  5156.5  127.40  5206.5  128.42  5226.5  129.69
  5246.5  129.40  5301.3  131.23  5396.5  133.74  5438.6  134.18  5459.7  133.98
#Mann=7,-1,0
  4534.6    0.05       0  4543.8     0.1       0  4766.4    0.05       0
  4941.8   0.035       0  4947.8    0.05       0  5301.3     0.1       0
  5438.6    0.05       0
Bank Sta=4941.8,4947.8
Exp/Cntr=0.3,0.1

Type RM Length L Ch R = 1,6734,306,306,306
BEGIN DESCRIPTION:
Mapping XS 0276423e
END DESCRIPTION:
XS GIS Cut Line= 3
      2268586.44     13300232.75      2268093.37     13300121.64
      2267671.21     13300123.37
#Sta/Elev= 30
  4529.8  131.18  4549.0  130.64  4569.5  131.31  4590.0  129.90  4668.6  128.42
  4682.3  128.98  4715.4  127.44  4774.5  125.70  4795.0  125.92  4836.0  124.75
  4959.0  123.36  4983.7  122.52  4986.5  122.02  4989.7  122.52  5030.0  123.95
  5060.9  124.26  5120.9  126.57  5150.9  126.63  5190.9  128.07  5220.9  129.78
  5240.9  129.26  5270.9  130.69  5301.0  131.41  5330.9  132.63  5350.9  132.48
  5380.9  133.45  5420.9  133.82  5430.9  134.67  5447.1  134.64  5457.4  134.47
#Mann=6,-1,0
  4529.8     0.1       0  4715.4    0.05       0  4983.7   0.035       0
  4989.7    0.05       0  5301.0     0.1       0  5447.1    0.05       0
Bank Sta=4983.7,4989.7
Exp/Cntr=0.3,0.1

Type RM Length L Ch R = 1,6428,753,753,753
BEGIN DESCRIPTION:
UNT016 IN NURI 14.0
END DESCRIPTION:
XS GIS Cut Line= 3
      2268816.68     13300063.05      2268323.62     13299818.25
      2267563.25     13299863.39
#Sta/Elev= 30
  4294.1  132.55  4342.5  132.44  4348.8  131.87  4393.4  131.36  4432.1  131.81
  4460.4  130.37  4549.7  128.64  4566.6  128.99  4589.0  127.93  4627.9  127.24
  4751.4  125.48  4870.5  124.60  4980.7  121.93  4997.8  120.82  5000.5  120.32
  5003.8  120.82  5010.8  122.41  5100.9  123.63  5161.0  125.40  5191.1  127.24
  5211.1  126.77  5251.2  128.78  5261.2  129.92  5287.5  129.53  5371.4  132.60
  5401.5  132.28  5431.5  133.95  5469.6  134.17  5571.8  134.74  5606.3  135.98
#Mann=5,-1,0
  4294.1    0.05       0  4997.8   0.035       0  5003.8    0.05       0
  5287.5     0.1       0  5469.6    0.05       0
Bank Sta=4997.8,5003.8
Exp/Cntr=0.3,0.1

Type RM Length L Ch R = 1,5675,284,284,284
BEGIN DESCRIPTION:
UNT016 IN NURI 13.0
END DESCRIPTION:
XS GIS Cut Line= 3
      2268948.65     13299915.50      2268469.45     13299429.36
      2268368.75     13299245.32
#Sta/Elev= 30
  4492.2  131.75  4562.6  131.69  4598.0  130.58  4605.0  130.80  4612.1  132.12
  4626.3  130.94  4689.9  128.89  4711.1  129.82  4746.4  127.70  4824.3  125.36
  4845.4  126.13  4859.6  124.59  4923.3  122.17  4986.9  121.31  4998.0  119.16
  5000.8  118.66  5004.0  119.16  5015.2  120.50  5047.5  120.16  5121.3  122.37
  5149.6  124.40  5170.7  123.76  5173.1  124.77  5213.6  126.39  5229.7  128.30
  5251.6  127.16  5267.7  128.22  5314.6  129.30  5338.8  129.93  5384.6  129.64
#Mann=5,-1,0
  4492.2    0.05       0  4998.0   0.035       0  5004.0    0.05       0
  5047.5     0.1       0  5314.6    0.05       0
Bank Sta=4998,5004
Exp/Cntr=0.3,0.1

Type RM Length L Ch R = 1,5391,418,418,418
BEGIN DESCRIPTION:
Mapping XS dbf31615
END DESCRIPTION:
XS GIS Cut Line= 2
      2269224.68     13299708.89      2268518.07     13299137.70
#Sta/Elev= 30
  4452.9  131.85  4538.1  130.41  4558.9  131.64  4573.3  130.30  4637.3  128.74
  4658.1  129.65  4672.4  128.41  4701.2  127.96  4736.4  126.31  4793.9  124.95
  4814.7  126.07  4835.6  124.29  4893.1  122.08  4972.5  120.69  4997.2  118.13
  5000.0  117.63  5003.2  118.13  5014.6  120.12  5035.4  120.01  5099.4  122.02
  5120.2  123.91  5142.5  123.72  5156.2  125.08  5187.8  125.85  5206.5  127.96
  5227.3  127.03  5276.9  128.72  5297.7  130.68  5312.1  129.53  5361.5  131.23
#Mann=5,-1,0
  4452.9    0.05       0  4972.5     0.1       0  4997.2    0.07       0
  5003.2     0.1       0  5187.8    0.05       0
Bank Sta=4997.2,5003.2
Exp/Cntr=0.3,0.1

Type RM Length L Ch R = 1,4973,93,93,93
BEGIN DESCRIPTION:
UNT016 IN NURI 12.0
END DESCRIPTION:
XS GIS Cut Line= 2
      2269453.80     13299509.19      2268877.51     13298821.81
#Sta/Elev= 30
  4526.1  131.77  4597.9  131.17  4616.1  130.74  4624.1  131.13  4631.9  129.52
  4659.6  129.26  4667.0  128.14  4745.1  124.97  4765.9  125.50  4773.7  124.40
  4808.8  123.18  4972.7  119.73  4997.1  118.35  4999.8  117.85  5003.1  118.35
  5121.1  121.11  5164.0  123.67  5192.6  124.20  5206.9  126.05  5220.8  126.46
  5234.3  125.53  5256.4  127.10  5262.9  126.45  5291.5  127.40  5305.8  129.49
  5336.1  129.22  5369.6  129.76  5390.4  131.56  5401.0  130.95  5423.1  131.97
#Mann=7,-1,0
  4526.1    0.08       0  4597.9    0.05       0  4616.1    0.08       0
  4997.1    0.07       0  5003.1    0.08       0  5336.1    0.05       0
  5401.0    0.08       0
Bank Sta=4997.1,5003.1
Exp/Cntr=0.3,0.1

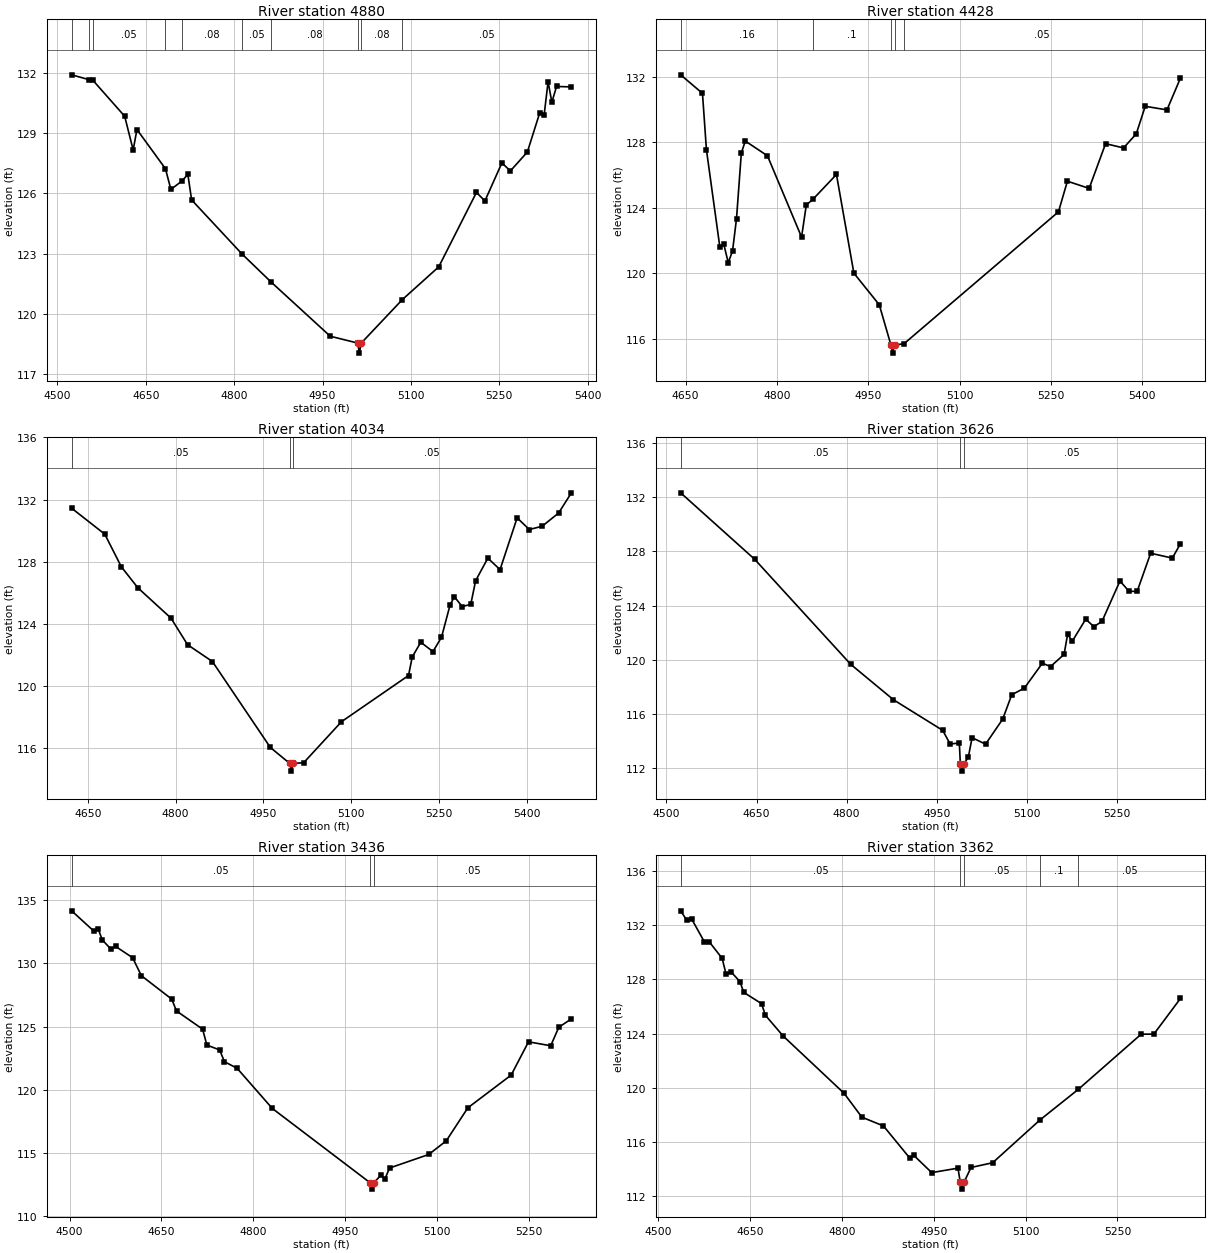
Type RM Length L Ch R = 1,4880,452,452,452
BEGIN DESCRIPTION:
UNT016 IN NURI 11.0
END DESCRIPTION:
XS GIS Cut Line= 2
      2269528.46     13299472.74      2268998.17     13298810.75
#Sta/Elev= 30
  4524.1  131.90  4553.6  131.66  4559.8  131.64  4614.1  129.84  4628.5  128.16
  4634.9  129.18  4683.3  127.23  4692.5  126.20  4711.3  126.62  4721.3  126.95
  4727.7  125.68  4812.9  123.00  4862.8  121.59  4963.0  118.90  5009.6  118.56
  5012.4  118.06  5015.6  118.56  5085.3  120.72  5147.1  122.35  5211.1  126.05
  5225.5  125.63  5254.3  127.52  5268.7  127.12  5297.5  128.06  5318.3  129.99
  5326.0  129.90  5332.7  131.56  5339.1  130.54  5347.1  131.32  5372.3  131.30
#Mann=10,-1,0
  4524.1    0.05       0  4553.6    0.16       0  4559.8    0.05       0
  4683.3     0.1       0  4711.3    0.08       0  4812.9    0.05       0
  4862.8    0.08       0  5009.6    0.07       0  5015.6    0.08       0
  5085.3    0.05       0
Bank Sta=5009.6,5015.6
Exp/Cntr=0.3,0.1

Type RM Length L Ch R = 1,4428,394,394,394
BEGIN DESCRIPTION:
UNT016 IN NURI 10.0
END DESCRIPTION:
XS GIS Cut Line= 3
      2269887.71     13299246.84      2269637.72     13298946.85
      2269387.72     13298596.86
#Sta/Elev= 30
  4641.8  132.12  4677.6  130.99  4684.1  127.55  4706.2  121.59  4712.7  121.77
  4719.9  120.66  4727.0  121.38  4733.5  123.35  4741.4  127.35  4747.9  128.08
  4784.3  127.18  4840.3  122.22  4848.1  124.18  4858.8  124.52  4897.6  126.04
  4926.2  120.02  4967.9  118.09  4987.0  115.64  4989.7  115.14  4993.0  115.64
  5008.4  115.71  5262.1  123.76  5276.8  125.63  5312.5  125.19  5339.5  127.92
  5369.0  127.66  5389.9  128.52  5404.6  130.20  5440.3  129.98  5462.4  131.92
#Mann=5,-1,0
  4641.8    0.16       0  4858.8     0.1       0  4987.0    0.07       0
  4993.0     0.1       0  5008.4    0.05       0
Bank Sta=4987,4993
Exp/Cntr=0.3,0.1

Type RM Length L Ch R = 1,4034,408,408,408
BEGIN DESCRIPTION:
UNT016 IN NURI 9.0
END DESCRIPTION:
XS GIS Cut Line= 3
      2270187.72     13298946.86      2269937.72     13298696.85
      2269537.69     13298396.83
#Sta/Elev= 30
  4622.6  131.44  4679.2  129.77  4707.5  127.67  4735.7  126.32  4792.3  124.37
  4820.6  122.66  4863.0  121.58  4962.0  116.05  4995.0  115.03  4997.8  114.53
  5001.0  115.03  5018.9  115.07  5083.5  117.71  5198.0  120.68  5204.3  121.87
  5218.9  122.82  5239.7  122.22  5254.3  123.14  5268.9  125.21  5276.2  125.75
  5289.7  125.11  5304.3  125.26  5312.6  126.78  5333.5  128.23  5354.3  127.49
  5383.5  130.82  5404.3  130.07  5426.2  130.28  5454.3  131.13  5476.2  132.43
#Mann=3,-1,0
  4622.6    0.05       0  4995.0    0.03       0  5001.0    0.05       0
Bank Sta=4995,5001
Exp/Cntr=0.3,0.1

Type RM Length L Ch R = 1,3626,190,190,190
BEGIN DESCRIPTION:
UNT016 IN NURI 8.0
END DESCRIPTION:
XS GIS Cut Line= 3
      2270437.75     13298796.90      2270187.72     13298396.85
      2269987.72     13298096.86
#Sta/Elev= 30
  4523.7  132.33  4647.0  127.42  4806.8  119.67  4878.1  117.05  4960.1  114.79
  4972.5  113.78  4987.8  113.86  4989.5  112.28  4992.3  111.78  4995.5  112.28
  5003.0  112.86  5009.0  114.25  5031.5  113.77  5060.0  115.62  5075.1  117.42
  5096.1  117.91  5126.1  119.75  5139.7  119.50  5162.2  120.40  5168.2  121.90
  5175.7  121.36  5198.3  123.00  5211.8  122.45  5225.3  122.83  5255.3  125.82
  5270.4  125.06  5283.9  125.05  5306.4  127.87  5342.5  127.51  5356.0  128.57
#Mann=3,-1,0
  4523.7    0.05       0  4989.5    0.03       0  4995.5    0.05       0
Bank Sta=4989.5,4995.5
Exp/Cntr=0.3,0.1

Type RM Length L Ch R = 1,3436,74,74,74
BEGIN DESCRIPTION:
Mapping XS 88bb5509
END DESCRIPTION:
XS GIS Cut Line= 2
      2270672.99     13298712.33      2270155.73     13298080.70
#Sta/Elev= 30
  4503.3  134.15  4539.0  132.57  4546.9  132.69  4553.3  131.85  4567.7  131.11
  4575.0  131.34  4602.9  130.44  4617.2  129.02  4666.7  127.17  4674.6  126.23
  4717.2  124.79  4724.2  123.53  4745.0  123.15  4752.9  122.22  4773.7  121.69
  4831.1  118.52  4991.0  112.64  4993.8  112.14  4997.0  112.64  5008.4  113.24
  5014.9  112.94  5022.7  113.81  5086.6  114.88  5115.3  115.96  5150.5  118.57
  5221.3  121.16  5249.6  123.79  5285.9  123.48  5299.1  124.94  5319.7  125.61
#Mann=3,-1,0
  4503.3    0.05       0  4991.0    0.04       0  4997.0    0.05       0
Bank Sta=4991,4997
Exp/Cntr=0.3,0.1

Type RM Length L Ch R = 1,3362,224,224,224
BEGIN DESCRIPTION:
Mapping XS e7a2ee68
END DESCRIPTION:
XS GIS Cut Line= 2
      2270705.56     13298653.75      2270203.96     13298010.51
#Sta/Elev= 30
  4537.1  133.07  4547.0  132.38  4555.1  132.46  4575.9  130.77  4583.9  130.77
  4604.8  129.56  4611.2  128.39  4619.3  128.56  4633.8  127.84  4640.1  127.04
  4669.1  126.21  4675.4  125.35  4704.3  123.82  4803.9  119.58  4832.8  117.82
  4868.1  117.17  4911.5  114.77  4917.8  114.99  4946.8  113.72  4989.7  114.05
  4993.5  113.00  4996.3  112.50  4999.5  113.00  5011.0  114.10  5046.3  114.45
  5124.0  117.63  5186.0  119.87  5288.7  123.95  5309.5  123.96  5352.8  126.59
#Mann=5,-1,0
  4537.1    0.05       0  4993.5    0.04       0  4999.5    0.05       0
  5124.0     0.1       0  5186.0    0.05       0
Bank Sta=4993.5,4999.5
Exp/Cntr=0.3,0.1

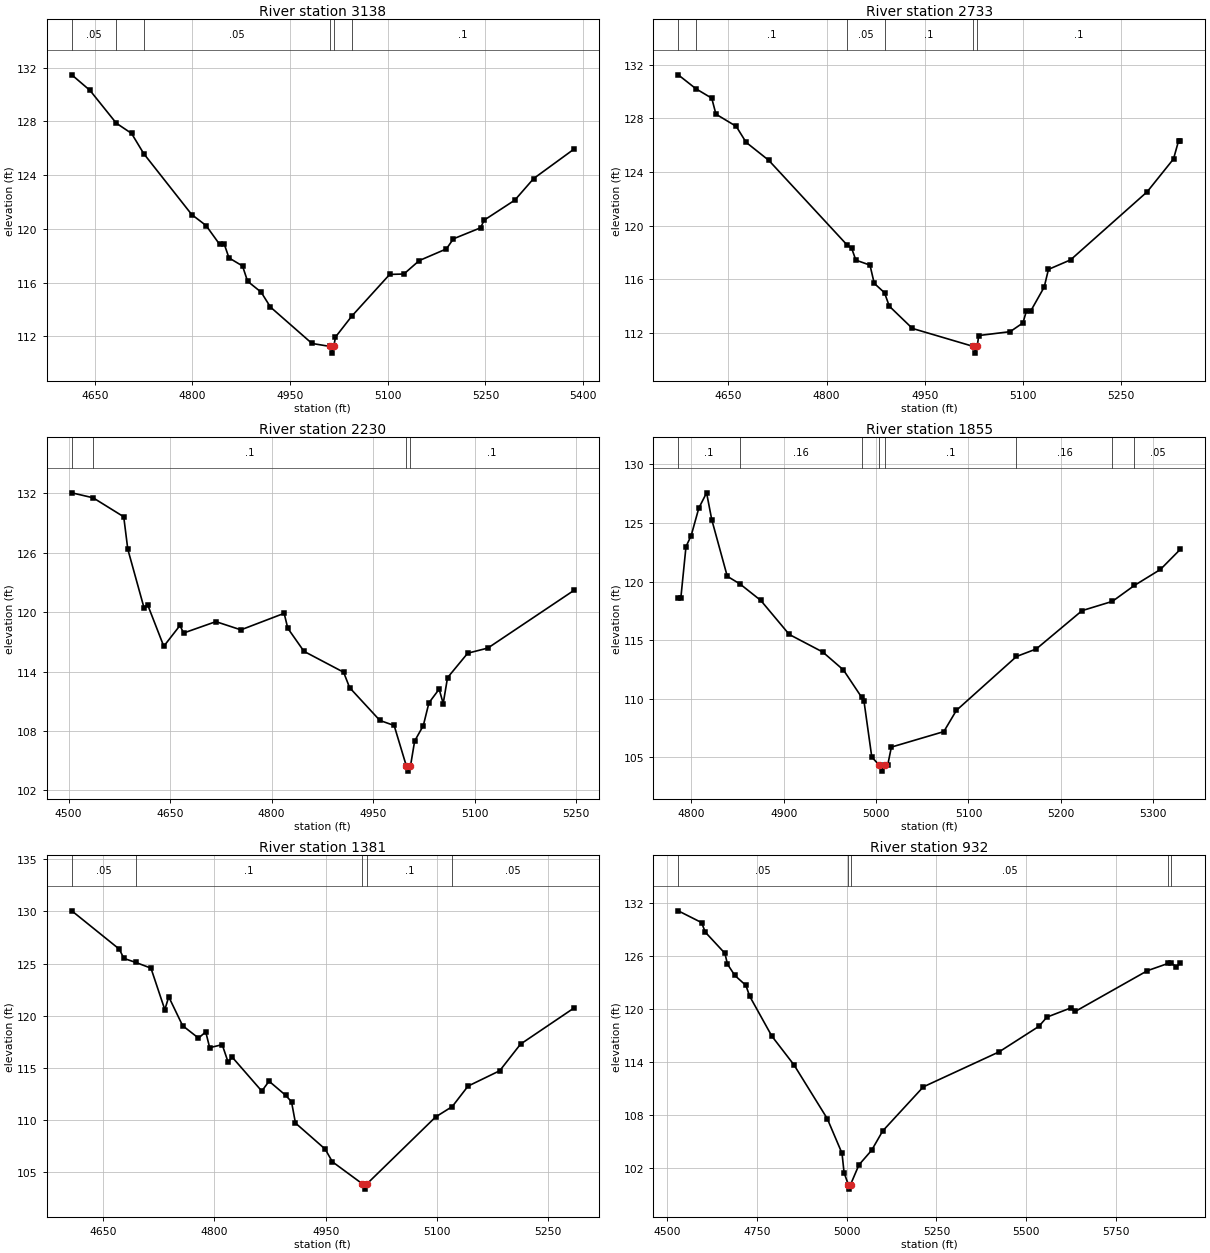
Type RM Length L Ch R = 1,3138,405,405,405
BEGIN DESCRIPTION:
UNT016 IN NURI 7.0
END DESCRIPTION:
XS GIS Cut Line= 3
      2270887.72     13298446.85      2270587.72     13298196.85
      2270437.72     13297846.85
#Sta/Elev= 30
  4614.6  131.47  4642.6  130.31  4683.0  127.87  4706.4  127.11  4725.2  125.60
  4798.8  121.07  4820.9  120.25  4841.7  118.85  4848.9  118.86  4856.1  117.84
  4876.9  117.24  4884.7  116.10  4905.5  115.29  4919.8  114.18  4983.6  111.47
  5011.2  111.25  5013.9  110.75  5017.2  111.25  5019.6  111.94  5044.7  113.50
  5103.0  116.61  5124.8  116.64  5148.4  117.64  5190.1  118.51  5200.9  119.26
  5242.6  120.08  5248.1  120.65  5295.2  122.14  5324.2  123.75  5385.9  125.93
#Mann=6,-1,0
  4614.6    0.05       0  4683.0     0.1       0  4725.2    0.05       0
  5011.2    0.03       0  5017.2    0.05       0  5044.7     0.1       0
Bank Sta=5011.2,5017.2
Exp/Cntr=0.3,0.1

Type RM Length L Ch R = 1,2733,503,503,503
BEGIN DESCRIPTION:
UNT016 IN NURI 6.0
END DESCRIPTION:
XS GIS Cut Line= 3
      2271087.74     13298296.90      2270887.72     13297946.85
      2270787.71     13297596.82
#Sta/Elev= 30
  4573.3  131.24  4600.4  130.20  4624.5  129.50  4630.9  128.31  4661.9  127.40
  4677.0  126.21  4711.6  124.87  4831.5  118.55  4838.2  118.33  4844.7  117.43
  4866.3  117.06  4872.8  115.70  4888.5  115.00  4895.8  114.00  4931.1  112.34
  5024.2  111.00  5026.9  110.50  5030.2  111.00  5032.4  111.81  5080.5  112.10
  5100.0  112.75  5105.2  113.62  5111.7  113.62  5132.5  115.42  5139.0  116.74
  5172.8  117.45  5289.8  122.52  5330.1  124.97  5337.9  126.33  5340.5  126.33
#Mann=6,-1,0
  4573.3    0.05       0  4600.4     0.1       0  4831.5    0.05       0
  4888.5     0.1       0  5024.2    0.07       0  5030.2     0.1       0
Bank Sta=5024.2,5030.2
Exp/Cntr=0.3,0.1

Type RM Length L Ch R = 1,2230,375,375,375
BEGIN DESCRIPTION:
UNT016 IN NURI 5.0
END DESCRIPTION:
XS GIS Cut Line= 3
      2271434.73     13298097.75      2271275.88     13297714.95
      2271097.13     13297440.35
#Sta/Elev= 30
  4504.7  132.05  4536.2  131.55  4581.5  129.63  4587.5  126.36  4611.4  120.46
  4616.8  120.75  4640.7  116.55  4664.6  118.65  4670.0  117.89  4717.7  119.04
  4754.7  118.21  4818.6  119.88  4824.0  118.37  4847.9  116.04  4906.5  113.93
  4915.4  112.37  4960.1  109.06  4981.2  108.55  4999.3  104.44  5002.1  103.94
  5005.3  104.44  5011.5  106.98  5024.3  108.54  5032.6  110.84  5047.7  112.22
  5053.7  110.77  5060.1  113.38  5089.9  115.85  5119.7  116.37  5246.8  122.19
#Mann=4,-1,0
  4504.7    0.05       0  4536.2     0.1       0  4999.3    0.07       0
  5005.3     0.1       0
Bank Sta=4999.3,5005.3
Exp/Cntr=0.3,0.1

Type RM Length L Ch R = 1,1855,474,474,474
BEGIN DESCRIPTION:
UNT016 IN NURI 4.0
END DESCRIPTION:
XS GIS Cut Line= 3
      2271687.71     13297746.83      2271587.72     13297546.85
      2271387.75     13297296.89
#Sta/Elev= 30
  4785.7  118.59  4788.5  118.59  4794.1  122.98  4799.7  123.92  4808.0  126.27
  4816.4  127.57  4822.0  125.28  4838.8  120.45  4852.5  119.80  4875.1  118.39
  4905.9  115.49  4942.2  113.99  4964.6  112.46  4984.3  110.13  4986.9  109.77
  4995.3  105.03  5003.5  104.33  5006.2  103.83  5009.5  104.33  5012.5  104.33
  5016.5  105.88  5073.3  107.20  5086.9  109.01  5152.0  113.61  5173.4  114.25
  5223.0  117.52  5255.8  118.31  5279.7  119.67  5307.8  121.03  5329.4  122.75
#Mann=8,-1,0
  4785.7     0.1       0  4852.5    0.16       0  4984.3     0.1       0
  5003.5    0.07       0  5009.5     0.1       0  5152.0    0.16       0
  5255.8     0.1       0  5279.7    0.05       0
Bank Sta=5003.5,5009.5
Exp/Cntr=0.3,0.1

Type RM Length L Ch R = 1,1381,449,449,449
BEGIN DESCRIPTION:
UNT016 IN NURI 3.0
END DESCRIPTION:
XS GIS Cut Line= 3
      2272087.71     13297646.84      2271937.72     13297246.85
      2271787.71     13297046.84
#Sta/Elev= 30
  4607.5  130.06  4671.6  126.39  4677.8  125.50  4693.7  125.12  4714.3  124.57
  4733.0  120.59  4738.3  121.82  4757.0  119.06  4778.4  117.87  4788.2  118.46
  4793.5  116.95  4810.4  117.24  4818.4  115.56  4823.8  116.05  4863.8  112.79
  4873.6  113.74  4895.8  112.40  4903.9  111.77  4909.2  109.73  4949.2  107.24
  4959.0  106.02  4999.6  103.90  5002.4  103.40  5005.6  103.90  5098.2  110.31
  5120.7  111.31  5142.0  113.27  5184.7  114.74  5212.8  117.29  5284.7  120.74
#Mann=5,-1,0
  4607.5    0.05       0  4693.7     0.1       0  4999.6    0.07       0
  5005.6     0.1       0  5120.7    0.05       0
Bank Sta=4999.6,5005.6
Exp/Cntr=0.3,0.1

Type RM Length L Ch R = 1,932,453,453,453
BEGIN DESCRIPTION:
UNT016 IN NURI 2.0
END DESCRIPTION:
XS GIS Cut Line= 3
      2272463.37     13297559.99      2272291.50     13296862.09
      2271617.04     13296950.63
#Sta/Elev= 30
  4530.7  131.09  4595.7  129.76  4606.0  128.68  4660.8  126.28  4667.8  125.06
  4688.4  123.78  4719.3  122.65  4729.6  121.44  4791.4  116.92  4853.2  113.66
  4945.9  107.58  4987.1  103.65  4992.8  101.46  5004.7  100.10  5007.4   99.60
  5010.7  100.10  5034.3  102.35  5069.5  103.99  5100.4  106.18  5213.6  111.17
  5424.7  115.13  5535.7  118.02  5557.9  119.06  5626.4  120.13  5636.7  119.70
  5838.2  124.32  5895.8  125.14  5904.3  125.17  5918.9  124.77  5929.7  125.16
#Mann=5,-1,0
  4530.7    0.05       0  5004.7   0.035       0  5010.7    0.05       0
  5895.8     0.1       0  5904.3    0.05       0
Bank Sta=5004.7,5010.7
Exp/Cntr=0.3,0.1

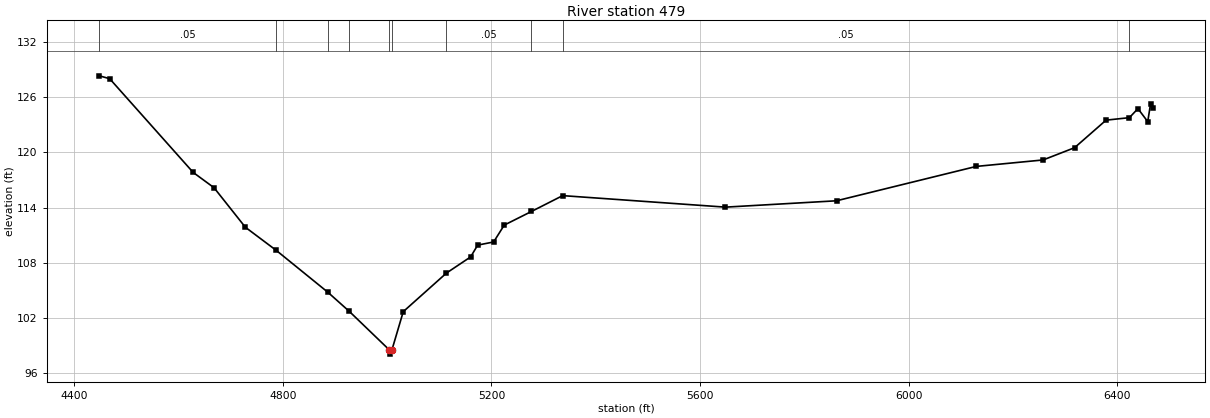
Type RM Length L Ch R = 1,479,0,0,0
BEGIN DESCRIPTION:
UNT016 IN NURI 1.0
END DESCRIPTION:
XS GIS Cut Line= 4
      2272727.96     13297416.61      2272745.32     13296973.89
      2272658.52     13296535.53      2271601.11     13296934.22
#Sta/Elev= 30
  4448.1  128.29  4467.9  127.98  4628.0  117.81  4668.0  116.15  4728.1  111.86
  4787.5  109.34  4886.2  104.81  4927.4  102.73  5003.4   98.59  5006.2   98.09
  5009.4   98.59  5030.9  102.70  5113.8  106.89  5160.1  108.64  5173.6  109.92
  5204.2  110.26  5224.5  112.09  5276.7  113.57  5336.6  115.29  5648.8  114.04
  5861.7  114.73  6129.7  118.46  6257.8  119.16  6318.2  120.49  6378.6  123.48
  6423.3  123.75  6439.7  124.73  6458.5  123.32  6463.9  125.25  6468.1  124.77
#Mann=10,-1,0
  4448.1    0.05       0  4787.5     0.1       0  4886.2    0.05       0
  4927.4     0.1       0  5003.4    0.07       0  5009.4     0.1       0
  5113.8    0.05       0  5276.7     0.1       0  5336.6    0.05       0
  6423.3     0.1       0
Bank Sta=5003.4,5009.4
Exp/Cntr=0.3,0.1

Chan Stop Cuts=-1