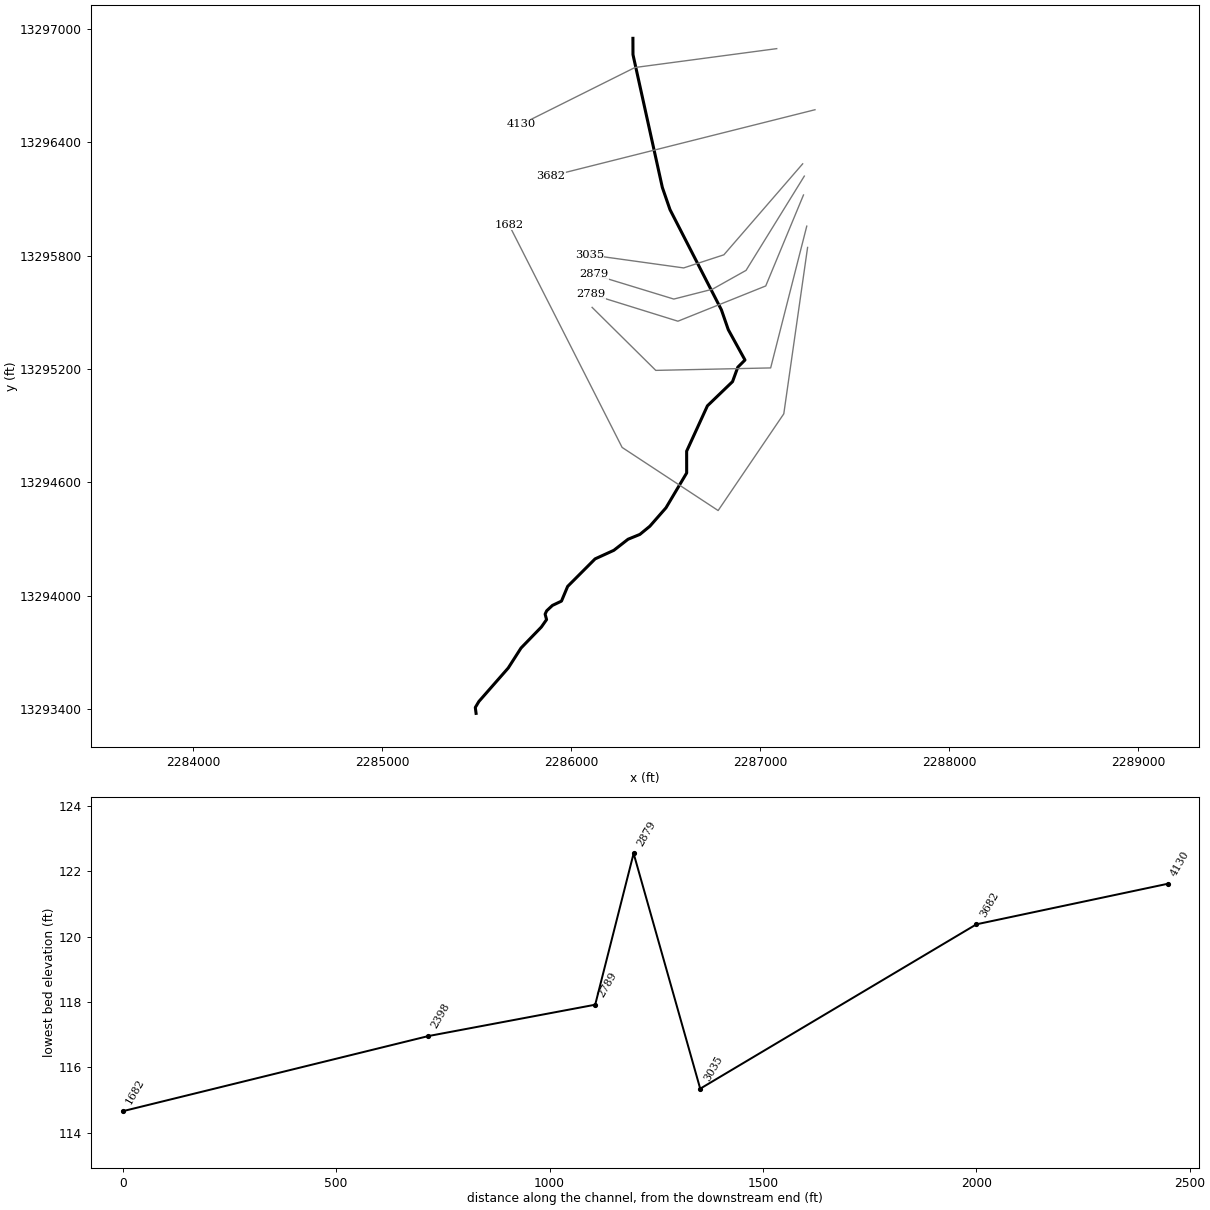
--- UNT017 IN NURI.prj (project) ---

Proj Title=UNT017 IN NURI Base Level Engineering
Current Plan=p01
Default Exp/Contr=0.3,0.1
English Units
Geom File=g01
Flow File=f01
Plan File=p01
BEGIN DESCRIPTION:
UNT017 IN NURI
END DESCRIPTION:

--- UNT017 IN NURI.p01 (plan) ---

Plan Title=Multiple Run
Short Identifier=Multiple
Geom File=g01
Flow File=f01
Subcritical Flow
K Sum by GR= 0
Std Step Tol= 0.01
Critical Tol= 0.01
Num of Std Step Trials= 20
Max Error Tol= 0.3
Flow Tol Ratio= 0.001
Split Flow NTrial= 30
Split Flow Tol= 0.02
Split Flow Ratio= 0.02
Log Output Level= 0
Friction Slope Method= 1
Unsteady Friction Slope Method= 2
Unsteady Bridges Friction Slope Method= 1
Parabolic Critical Depth
Global Vel Dist=  1 , 1 , 1
Global Log Level= 0
CheckData=True
Encroach Param= -1, 0, 0, 0
BEGIN DESCRIPTION:
Multiple Run
END DESCRIPTION:

--- UNT017 IN NURI.f01 (steady flow) ---

Flow Title=Multiple
Number of Profiles=7
Profile Names=10-year,25-year,50-year,1pct_min,100-year,1pct_plu,500-year
River Rch & RM= UNT017 IN NURI,Reach-1,4130
     186     249     298     263     356     481     513
Boundary for River Rch & Prof#=UNT017 IN NURI,Reach-1,1
Up Type=0
Dn Type=3
Dn Slope=0.005
Boundary for River Rch & Prof#=UNT017 IN NURI,Reach-1,2
Up Type=0
Dn Type=3
Dn Slope=0.005
Boundary for River Rch & Prof#=UNT017 IN NURI,Reach-1,3
Up Type=0
Dn Type=3
Dn Slope=0.005
Boundary for River Rch & Prof#=UNT017 IN NURI,Reach-1,4
Up Type=0
Dn Type=3
Dn Slope=0.005
Boundary for River Rch & Prof#=UNT017 IN NURI,Reach-1,5
Up Type=0
Dn Type=3
Dn Slope=0.005
Boundary for River Rch & Prof#=UNT017 IN NURI,Reach-1,6
Up Type=0
Dn Type=3
Dn Slope=0.005
Boundary for River Rch & Prof#=UNT017 IN NURI,Reach-1,7
Up Type=0
Dn Type=3
Dn Slope=0.005

--- UNT017 IN NURI.g01 (geometry) ---

Geom Title=Existing Conditions

River Reach=UNT017 IN NURI,Reach-1
Reach XY= 30
      2286327.17     13296951.40      2286327.55     13296865.19
      2286482.83     13296161.85      2286523.26     13296044.53
      2286795.25     13295513.62      2286831.64     13295408.47
      2286919.91     13295248.01      2286881.94     13295210.08
      2286854.08     13295133.56      2286721.16     13295005.38
      2286611.34     13294765.29      2286611.50     13294649.88
      2286502.08     13294465.43      2286416.74     13294367.79
      2286364.00     13294324.53      2286301.49     13294298.99
      2286226.33     13294240.32      2286127.14     13294194.93
      2285982.01     13294049.17      2285949.41     13293971.39
      2285901.50     13293948.50      2285871.29     13293920.22
      2285862.83     13293902.41      2285870.55     13293873.56
      2285842.95     13293834.06      2285735.53     13293723.03
      2285667.74     13293617.03      2285512.44     13293439.72
      2285493.63     13293408.03      2285497.72     13293376.86

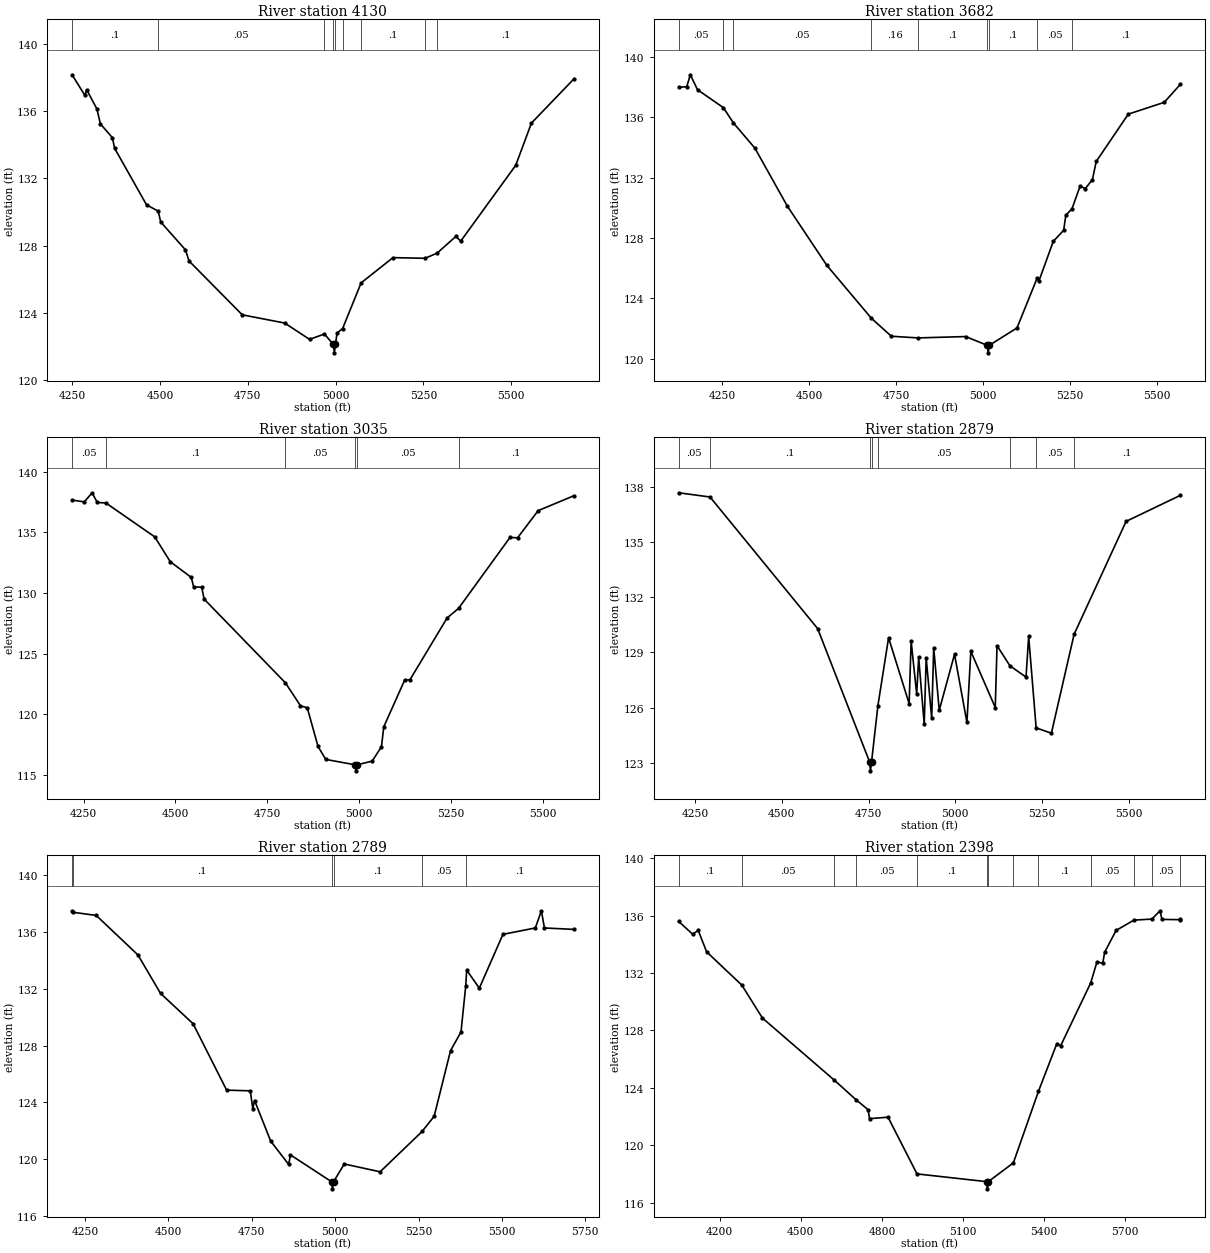
Type RM Length L Ch R = 1,4130,448,448,448
BEGIN DESCRIPTION:
UNT017 IN NURI 2.0
END DESCRIPTION:
XS GIS Cut Line= 3
      2287087.73     13296896.86      2286337.72     13296796.85
      2285737.69     13296496.84
#Sta/Elev= 30
  4250.1  138.15  4286.7  136.92  4291.7  137.26  4320.7  136.12  4330.8  135.23
  4364.9  134.41  4371.2  133.78  4462.0  130.42  4495.4  130.04  4502.3  129.40
  4572.9  127.74  4583.0  127.08  4734.4  123.88  4855.4  123.39  4926.0  122.42
  4968.2  122.74  4993.7  122.12  4996.4  121.62  4999.7  122.12  5004.2  122.80
  5019.9  123.06  5072.7  125.78  5163.3  127.28  5254.7  127.24  5289.1  127.55
  5342.2  128.54  5356.1  128.26  5512.7  132.77  5557.4  135.28  5677.6  137.89
#Mann=9,-1,0
  4250.1     0.1       0  4495.4    0.05       0  4968.2    0.16       0
  4993.7    0.07       0  4999.7    0.16       0  5019.9    0.05       0
  5072.7     0.1       0  5254.7    0.05       0  5289.1     0.1       0
Bank Sta=4993.7,4999.7
Exp/Cntr=0.3,0.1

Type RM Length L Ch R = 1,3682,647,647,647
BEGIN DESCRIPTION:
Mapping XS 20bfedf2
END DESCRIPTION:
XS GIS Cut Line= 2
      2287290.09     13296573.34      2285892.73     13296221.83
#Sta/Elev= 30
  4125.3  137.99  4148.4  138.03  4158.7  138.82  4179.3  137.83  4253.7  136.64
  4282.4  135.63  4344.3  133.95  4437.1  130.12  4550.5  126.19  4678.5  122.68
  4736.1  121.48  4812.7  121.37  4949.4  121.46  5011.5  120.88  5014.3  120.38
  5017.5  120.88  5097.0  122.03  5154.6  125.32  5160.1  125.15  5201.2  127.77
  5231.1  128.51  5237.2  129.50  5255.1  129.94  5278.3  131.44  5293.0  131.27
  5313.6  131.86  5324.6  133.07  5416.7  136.21  5519.8  136.99  5566.2  138.18
#Mann=9,-1,0
  4125.3    0.05       0  4253.7     0.1       0  4282.4    0.05       0
  4678.5    0.16       0  4812.7     0.1       0  5011.5    0.07       0
  5017.5     0.1       0  5154.6    0.05       0  5255.1     0.1       0
Bank Sta=5011.5,5017.5
Exp/Cntr=0.3,0.1

Type RM Length L Ch R = 1,3035,156,156,156
BEGIN DESCRIPTION:
Mapping XS 24adf252
END DESCRIPTION:
XS GIS Cut Line= 4
      2287224.94     13296286.86      2286808.28     13295805.10
      2286595.60     13295735.66      2286096.48     13295805.10
#Sta/Elev= 30
  4218.7  137.66  4252.2  137.51  4273.1  138.26  4287.3  137.46  4310.7  137.42
  4443.5  134.63  4485.9  132.58  4542.9  131.29  4549.5  130.51  4571.4  130.48
  4578.0  129.50  4799.2  122.60  4840.1  120.71  4858.6  120.54  4887.8  117.36
  4908.8  116.29  4988.3  115.85  4991.1  115.35  4994.3  115.85  5035.1  116.15
  5060.4  117.34  5066.6  118.97  5123.5  122.83  5137.8  122.85  5238.8  127.94
  5270.2  128.74  5410.0  134.58  5430.6  134.55  5486.7  136.79  5583.3  138.01
#Mann=6,-1,0
  4218.7    0.05       0  4310.7     0.1       0  4799.2    0.05       0
  4988.3   0.033       0  4994.3    0.05       0  5270.2     0.1       0
Bank Sta=4988.3,4994.3
Exp/Cntr=0.3,0.1

Type RM Length L Ch R = 1,2879,90,90,90
BEGIN DESCRIPTION:
Mapping XS 3b4252a4
END DESCRIPTION:
XS GIS Cut Line= 5
      2287233.65     13296221.80      2286925.47     13295722.64
      2286747.51     13295622.81      2286543.52     13295570.73
      2286118.22     13295700.92
#Sta/Elev= 30
  4202.7  137.70  4293.0  137.47  4603.2  130.30  4752.7  123.05  4755.5  122.55
  4758.7  123.05  4776.9  126.10  4807.7  129.80  4867.0  126.21  4872.7  129.62
  4888.7  126.73  4894.4  128.73  4910.4  125.10  4916.1  128.69  4932.0  125.42
  4937.8  129.25  4953.7  125.85  4997.8  128.90  5033.5  125.19  5044.8  129.06
  5115.2  126.00  5120.3  129.37  5157.6  128.27  5203.9  127.66  5211.5  129.87
  5233.1  124.89  5277.0  124.60  5342.5  129.99  5492.3  136.14  5648.7  137.56
#Mann=8,-1,0
  4202.7    0.05       0  4293.0     0.1       0  4752.7   0.033       0
  4758.7     0.1       0  4776.9    0.05       0  5157.6     0.1       0
  5233.1    0.05       0  5342.5     0.1       0
Bank Sta=4752.7,4758.7
Exp/Cntr=0.3,0.1

Type RM Length L Ch R = 1,2789,391,391,391
BEGIN DESCRIPTION:
Mapping XS 02c43541
END DESCRIPTION:
XS GIS Cut Line= 4
      2287229.28     13296121.93      2287029.63     13295640.17
      2286565.22     13295453.54      2286105.20     13295596.75
#Sta/Elev= 30
  4211.3  137.45  4213.0  137.40  4283.9  137.17  4408.8  134.39  4476.6  131.68
  4574.0  129.55  4674.7  124.87  4745.6  124.82  4753.1  123.57  4758.4  124.14
  4806.8  121.28  4860.6  119.64  4866.0  120.31  4989.3  118.42  4992.0  117.92
  4995.3  118.42  5027.3  119.67  5134.8  119.12  5260.7  121.96  5296.8  123.03
  5345.9  127.65  5377.3  128.97  5391.4  132.20  5394.4  133.32  5432.2  132.05
  5503.0  135.84  5600.1  136.29  5618.2  137.50  5627.4  136.29  5715.1  136.19
#Mann=6,-1,0
  4211.3    0.05       0  4213.0     0.1       0  4989.3    0.07       0
  4995.3     0.1       0  5260.7    0.05       0  5391.4     0.1       0
Bank Sta=4989.3,4995.3
Exp/Cntr=0.3,0.1

Type RM Length L Ch R = 1,2398,716,716,716
BEGIN DESCRIPTION:
Mapping XS 047261e8
END DESCRIPTION:
XS GIS Cut Line= 4
      2287246.63     13295956.96      2287055.67     13295206.14
      2286448.03     13295193.12      2286111.43     13295526.70
#Sta/Elev= 30
  4048.1  135.59  4099.6  134.70  4120.4  134.96  4151.4  133.47  4281.8  131.15
  4357.8  128.86  4624.0  124.53  4704.2  123.17  4749.2  122.47  4754.3  121.85
  4822.8  121.95  4930.0  118.00  5187.9  117.46  5190.6  116.96  5193.9  117.46
  5286.6  118.77  5379.6  123.76  5447.6  127.08  5461.7  126.93  5572.7  131.30
  5596.1  132.78  5617.3  132.67  5624.4  133.44  5666.8  134.96  5732.7  135.68
  5799.1  135.75  5829.4  136.33  5836.5  135.73  5902.4  135.71  5904.5  135.74
#Mann=13,-1,0
  4048.1     0.1       0  4281.8    0.05       0  4624.0     0.1       0
  4704.2    0.05       0  4930.0     0.1       0  5187.9    0.07       0
  5193.9     0.1       0  5286.6    0.05       0  5379.6     0.1       0
  5572.7    0.05       0  5732.7     0.1       0  5799.1    0.05       0
  5902.4     0.1       0
Bank Sta=5187.9,5193.9
Exp/Cntr=0.3,0.1

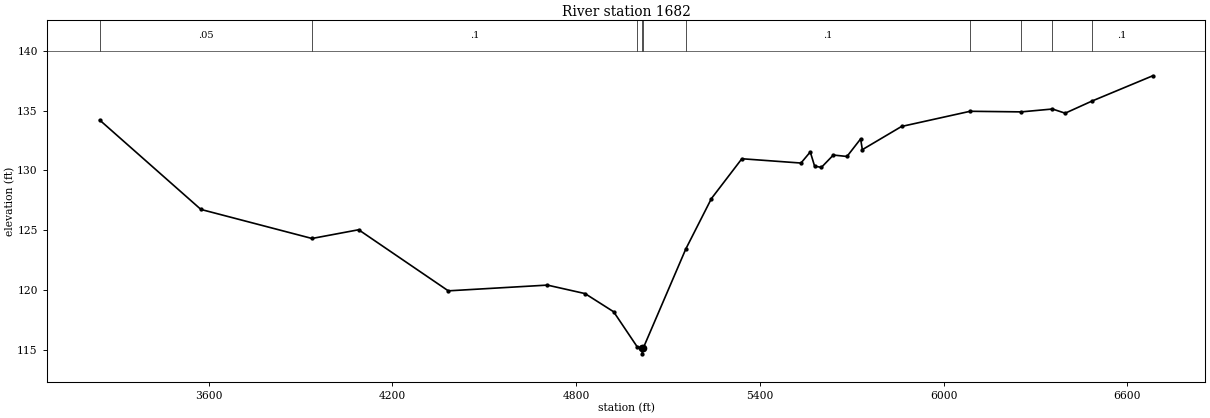
Type RM Length L Ch R = 1,1682,0,0,0
BEGIN DESCRIPTION:
UNT017 IN NURI 1.0
END DESCRIPTION:
XS GIS Cut Line= 5
      2287250.99     13295844.20      2287125.12     13294963.09
      2286777.90     13294450.93      2286270.08     13294785.14
      2285671.91     13295964.14
#Sta/Elev= 30
  3244.5  134.22  3575.2  126.74  3937.9  124.31  4090.3  125.04  4383.0  119.93
  4706.5  120.41  4829.5  119.70  4922.9  118.18  4999.5  115.26  5013.9  115.16
  5016.6  114.66  5019.9  115.16  5158.5  123.43  5242.2  127.65  5341.6  130.98
  5534.6  130.62  5565.0  131.55  5579.1  130.36  5601.4  130.26  5640.3  131.29
  5684.8  131.17  5729.4  132.64  5735.0  131.74  5863.0  133.68  6087.0  134.95
  6253.8  134.90  6355.8  135.14  6397.3  134.79  6484.4  135.80  6683.3  137.92
#Mann=10,-1,0
  3244.5    0.05       0  3937.9     0.1       0  4999.5    0.05       0
  5013.9    0.04       0  5019.9    0.05       0  5158.5     0.1       0
  6087.0    0.05       0  6253.8     0.1       0  6355.8    0.05       0
  6484.4     0.1       0
Bank Sta=5013.9,5019.9
Exp/Cntr=0.3,0.1

Chan Stop Cuts=-1