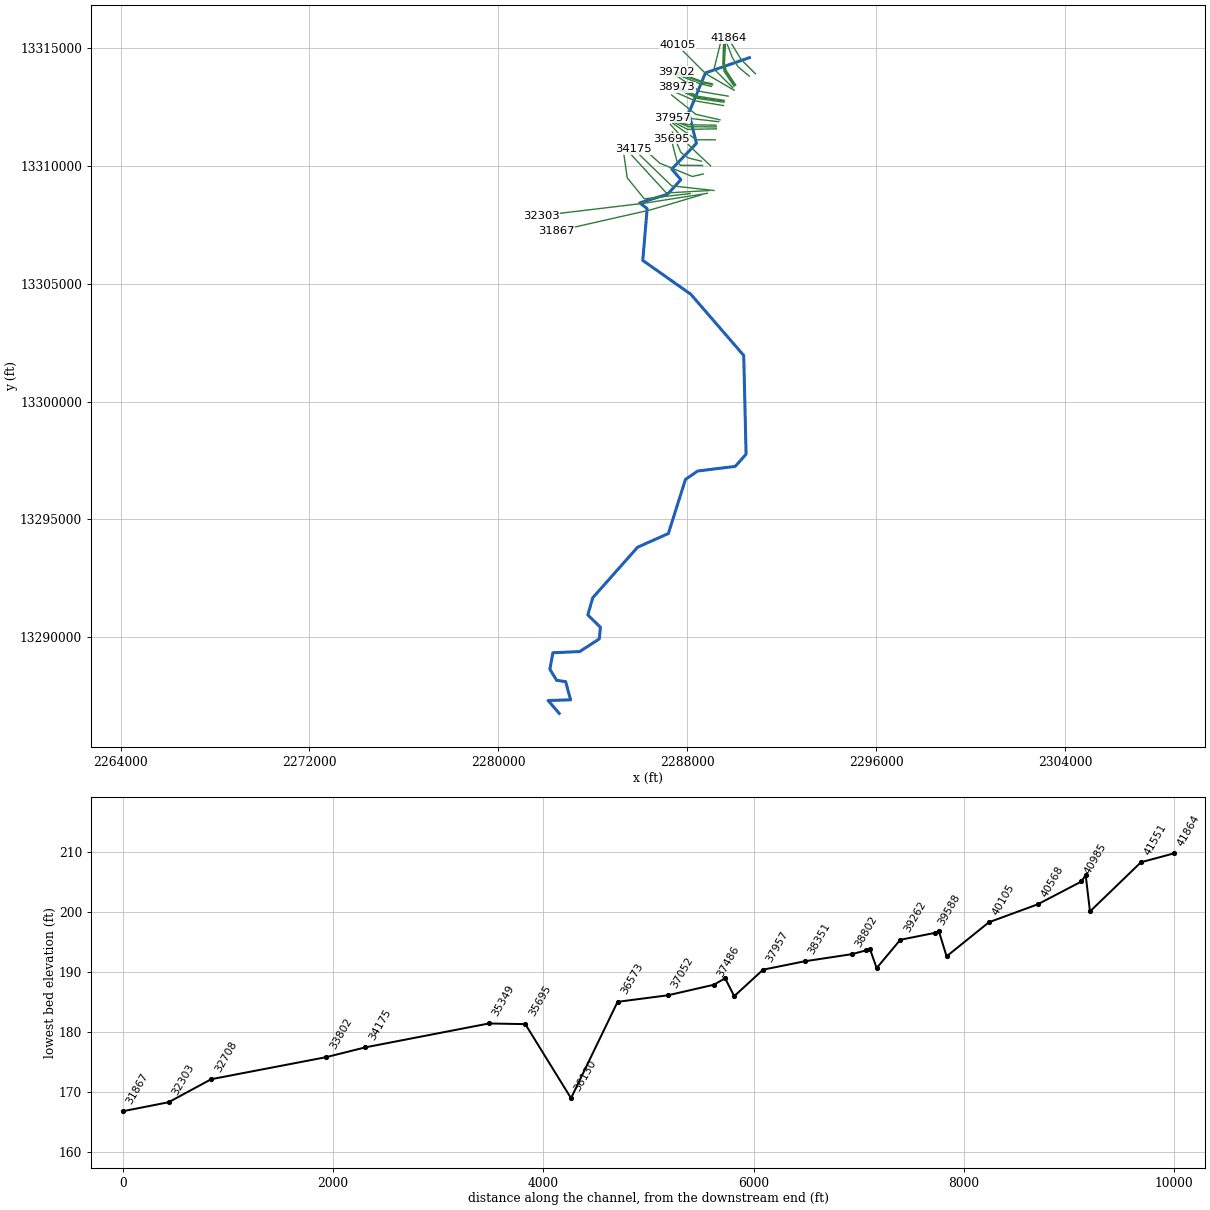
--- UNT018 IN NURI.prj (project) ---

Proj Title=UNT018 IN NURI Base Level Engineering
Current Plan=p01
Default Exp/Contr=0.3,0.1
English Units
Geom File=g01
Flow File=f01
Plan File=p01
Y Axis Title=Elevation
X Axis Title(PF)=Main Channel Distance
X Axis Title(XS)=Station
BEGIN DESCRIPTION:
UNT018 IN NURI
END DESCRIPTION:
DSS Export Rating Curves= 0
DSS Export Rating Curve Sorted= 0
DSS Export Volume Flow Curves= 0
DXF OffsetX= 0
DXF OffsetY= 0
DXF ScaleX= 1
DXF ScaleY= 10

--- UNT018 IN NURI.p01 (plan) ---

Plan Title=Multiple Run
Short Identifier=Multiple
Geom File=g01
Flow File=f01
Subcritical Flow
K Sum by GR= 0
Std Step Tol= 0.01
Critical Tol= 0.01
Num of Std Step Trials= 20
Max Error Tol= 0.3
Flow Tol Ratio= 0.001
Split Flow NTrial= 30
Split Flow Tol= 0.02
Split Flow Ratio= 0.02
Log Output Level= 0
Friction Slope Method= 1
Unsteady Friction Slope Method= 2
Unsteady Bridges Friction Slope Method= 1
Parabolic Critical Depth
Global Vel Dist=  1 , 1 , 1
Global Log Level= 0
CheckData=True
Encroach Param= -1, 0, 0, 0
BEGIN DESCRIPTION:
Multiple Run
END DESCRIPTION:

--- UNT018 IN NURI.f01 (steady flow) ---

Flow Title=Multiple
Program Version=4.10
Number of Profiles= 7
Profile Names=10-year,25-year,50-year,1pct_min,100-year,1pct_plu,500-year
River Rch & RM=UNT018 IN NURI,Reach-1         ,41864
     597     848    1059     967    1307    1768    2002
River Rch & RM=UNT018 IN NURI,Reach-1         ,41066
     575     818    1025     939    1270    1718    1972
River Rch & RM=UNT018 IN NURI,Reach-1         ,29521
     832    1204    1523    1410    1907    2579    3022
River Rch & RM=UNT018 IN NURI,Reach-1         ,22302
    1682    2494    3208    3006    4066    5498    6592
River Rch & RM=UNT018 IN NURI,Reach-1         ,13745
    1702    2526    3251    3050    4125    5579    6710
River Rch & RM=UNT018 IN NURI,Reach-1         ,12059
    1702    2526    3251    3050    4125    5579    6710
River Rch & RM=UNT018 IN NURI,Reach-1         ,6651
    1727    2559    3290    3085    4173    5643    6788
Boundary for River Rch & Prof#=UNT018 IN NURI,Reach-1         , 1
Up Type= 0
Dn Type= 3
Dn Slope=0.001
Boundary for River Rch & Prof#=UNT018 IN NURI,Reach-1         , 2
Up Type= 0
Dn Type= 3
Dn Slope=0.001
Boundary for River Rch & Prof#=UNT018 IN NURI,Reach-1         , 3
Up Type= 0
Dn Type= 3
Dn Slope=0.001
Boundary for River Rch & Prof#=UNT018 IN NURI,Reach-1         , 4
Up Type= 0
Dn Type= 3
Dn Slope=0.001
Boundary for River Rch & Prof#=UNT018 IN NURI,Reach-1         , 5
Up Type= 0
Dn Type= 3
Dn Slope=0.001
Boundary for River Rch & Prof#=UNT018 IN NURI,Reach-1         , 6
Up Type= 0
Dn Type= 3
Dn Slope=0.001
Boundary for River Rch & Prof#=UNT018 IN NURI,Reach-1         , 7
Up Type= 0
Dn Type= 3
Dn Slope=0.001
DSS Import GetInterval= 0
DSS Import GetPeak= 0
DSS Import FillOption= 0

--- UNT018 IN NURI.g01 (geometry) ---

Geom Title=Existing Conditions
Program Version=4.10

River Reach=UNT018 IN NURI  ,Reach-1
Reach XY= 30
      2290637.43     13314577.67      2288772.75     13313929.83
       2288070.1     13312236.86      2288391.09     13310944.15
      2287347.13     13309857.01      2287730.58     13309403.82
      2287167.72     13308786.86      2285991.02     13308423.66
      2286303.52     13308179.52      2286119.16     13305981.27
      2288154.42     13304546.76      2290394.75     13301954.04
      2290494.69     13297768.12       2290036.2     13297250.52
      2288443.68     13297054.55      2287926.56     13296697.85
       2287202.1     13294403.85      2285899.07     13293825.16
      2283998.25     13291678.71      2283790.43     13290952.66
      2284324.05     13290433.57      2284276.83      13289936.6
      2283446.19      13289400.6      2282311.26      13289350.1
      2282183.71     13288650.55      2282469.08      13288181.8
      2282851.03     13288126.46      2283061.05     13287353.76
      2282107.58     13287325.98      2282579.09     13286780.37

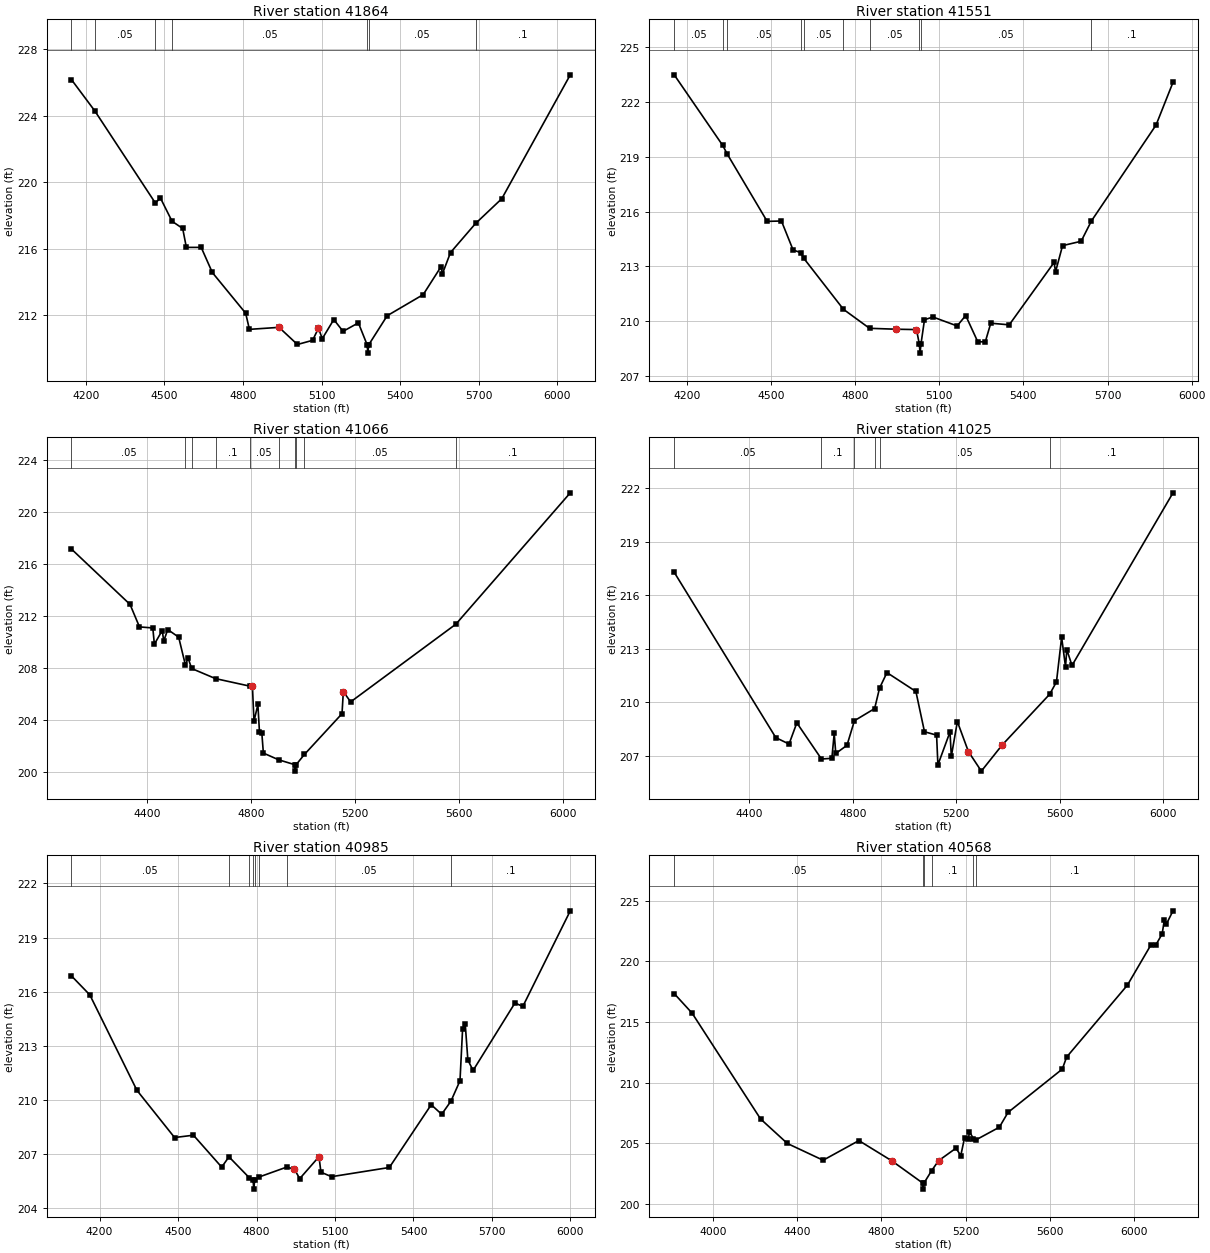
Type RM Length L Ch R = 1 ,41864   ,313,313,313
BEGIN DESCRIPTION:
UNT018 IN NURI 56.0
END DESCRIPTION:
XS GIS Cut Line= 3
      2290887.74     13313896.83      2290287.72     13314496.85
      2289737.73     13315396.85
#Sta/Elev= 30
  4145.8  226.17  4234.8  224.29  4465.8  218.75  4485.2  219.05  4529.6  217.65
  4570.1  217.22  4584.2  216.08  4640.8  216.08  4683.2  214.57  4810.5  212.12
  4824.7  211.15  4937.8  211.27  5007.9  210.24    5066  210.49  5088.1  211.22
  5102.8  210.59  5146.7  211.74  5182.1  211.03  5240.5  211.54    5274  210.22
  5276.7  209.72    5280  210.22  5350.5  211.97  5487.9  213.24  5555.6  214.91
  5561.4   214.5  5592.1  215.77  5687.8  217.52  5787.8  219.01  6049.1  226.46
#Mann= 7 ,-1 , 0
  4145.8      .1       0  4234.8     .05       0  4465.8      .1       0
  4529.6     .05       0    5274    .035       0    5280     .05       0
  5687.8      .1       0
Bank Sta=4937.8,5088.1
XS Rating Curve= 0 ,0
Exp/Cntr=0.3,0.1

Type RM Length L Ch R = 1 ,41551   ,485,485,485
BEGIN DESCRIPTION:
UNT018 IN NURI 55.0
END DESCRIPTION:
XS GIS Cut Line= 4
       2290632.3     13313794.01      2290150.54      13314193.3
      2289903.14     13314601.29      2289665.03     13315233.37
#Sta/Elev= 30
  4155.2   223.5  4328.2  219.63  4344.6  219.15  4486.6  215.47  4537.5  215.49
  4579.1   213.9  4606.1  213.76  4617.5  213.44  4758.6  210.65  4851.5  209.61
  4946.6  209.56    5019  209.54    5029  208.75  5031.7  208.25    5035  208.75
  5047.5  210.08  5077.5  210.23  5163.8  209.74  5194.4  210.31  5237.5  208.87
  5264.3  208.87  5283.8  209.89  5349.6   209.8  5509.5  213.22  5514.8  212.71
  5539.7  214.14    5606  214.38  5642.5  215.49  5873.1  220.75  5933.5  223.09
#Mann= 10 ,-1 , 0
  4155.2     .05       0  4328.2      .1       0  4344.6     .05       0
  4606.1      .1       0  4617.5     .05       0  4758.6      .1       0
  4851.5     .05       0    5029    .035       0    5035     .05       0
  5642.5      .1       0
Bank Sta=4946.6,5019
XS Rating Curve= 0 ,0
Exp/Cntr=0.3,0.1

Type RM Length L Ch R = 1 ,41066   ,41,41,41
BEGIN DESCRIPTION:
Mapping XS e6654e21
END DESCRIPTION:
XS GIS Cut Line= 4
      2290055.07     13313412.03      2289647.07     13314037.05
      2289577.62     13314349.55      2289625.37     13315200.29
#Sta/Elev= 30
  4108.7  217.15    4334  212.89  4370.2  211.16  4421.5  211.08  4427.5  209.83
  4457.7  210.88  4463.7  210.07  4478.8  210.96    4521  210.37  4547.1  208.21
  4557.2  208.77  4570.8  207.96  4662.8  207.18  4794.9   206.6  4804.7   206.6
  4810.6  203.89  4825.7  205.19  4831.7   203.1  4840.9  202.98  4846.8  201.45
  4905.8  200.93    4967  200.56  4969.8  200.06    4973  200.56  5004.5  201.34
  5149.3  204.48  5154.4  206.18  5182.5  205.39  5587.2  211.37  6027.3  221.48
#Mann= 10 ,-1 , 0
  4108.7     .05       0  4547.1      .1       0  4570.8     .05       0
  4662.8      .1       0  4794.9     .05       0  4905.8      .1       0
    4967     .07       0    4973      .1       0  5004.5     .05       0
  5587.2      .1       0
Bank Sta=4804.7,5154.4
XS Rating Curve= 0 ,0
Exp/Cntr=0.3,0.1

Type RM Length L Ch R = 1 ,41025   ,40,40,40
BEGIN DESCRIPTION:
UNT018 IN NURI 54.0
END DESCRIPTION:
XS GIS Cut Line= 4
      2290015.99     13313399.03      2289603.66     13314024.03
      2289537.72     13314366.91      2289587.72     13315196.88
#Sta/Elev= 30
  4108.8  217.29  4501.8  208.01    4553  207.65  4583.1  208.84  4678.4  206.81
  4718.6  206.85  4727.7  208.25  4733.7  207.12  4777.1  207.58  4805.9  208.96
    4884  209.64  4903.1  210.79  4931.7  211.66  5043.7   210.6  5076.9  208.34
  5123.7  208.15  5128.8  206.48  5175.6  208.33  5180.7  206.96  5204.1  208.91
  5246.7  207.23  5296.8  206.13    5377  207.59  5561.4  210.45  5587.4  211.14
  5607.4  213.64  5622.4  211.99  5627.4  212.95  5647.5  212.06  6038.2  221.75
#Mann= 6 ,-1 , 0
  4108.8     .05       0  4678.4      .1       0  4805.9      .1       0
    4884      .1       0  4903.1     .05       0  5561.4      .1       0
#XS Ineff= 1 ,-1
  4356.7 4961.83 211.139
Permanent Ineff=
       F
Bank Sta=5246.7,5377
XS Rating Curve= 0 ,0
Exp/Cntr=0.3,0.1

Type RM Length L Ch R = 1 ,40985   ,417,417,417
BEGIN DESCRIPTION:
Mapping XS 33800af2
END DESCRIPTION:
XS GIS Cut Line= 4
      2289981.29     13313372.96       2289564.6     13313993.65
      2289512.52     13314310.49      2289538.56     13315148.21
#Sta/Elev= 30
  4092.6  216.87  4162.7  215.82  4342.7  210.53  4486.7  207.91  4558.8  208.04
  4666.8  206.27  4694.7  206.84  4773.1  205.67  4786.8  205.55  4789.5  205.05
  4792.8  205.55  4811.3  205.73  4915.1  206.27  4944.8  206.16    4965  205.63
  5038.9  206.85  5046.1  205.99  5086.7  205.74  5307.7  206.25  5467.8  209.73
  5507.8   209.2  5543.3  209.93  5577.8  211.06  5587.8  213.94  5597.9  214.19
  5607.9  212.21  5627.9  211.63  5787.9  215.37    5818  215.18  5999.4  220.48
#Mann= 8 ,-1 , 0
  4092.6     .05       0  4694.7      .1       0  4773.1     .05       0
  4786.8    .035       0  4792.8     .05       0  4811.3      .1       0
  4915.1     .05       0  5543.3      .1       0
Bank Sta=4944.8,5038.9
XS Rating Curve= 0 ,0
Exp/Cntr=0.3,0.1

Type RM Length L Ch R = 1 ,40568   ,463,463,463
BEGIN DESCRIPTION:
UNT018 IN NURI 53.0
END DESCRIPTION:
XS GIS Cut Line= 3
      2289937.74     13313296.84      2289137.72     13314096.85
      2289437.71     13315296.83
#Sta/Elev= 30
  3816.4  217.35  3901.3  215.74  4226.5  207.02  4353.8     205  4523.5  203.62
  4693.2  205.24  4848.8  203.58  4996.3  201.74  4999.1  201.24  5002.3  201.74
    5039  202.77  5071.5  203.58    5154  204.61  5177.1  204.01  5195.2  205.49
  5213.2  205.35  5218.4  205.98  5236.9   205.4  5247.2  205.28  5360.1  206.34
  5401.3  207.56    5659  211.13  5679.6  212.12  5968.3  218.05  6079.1  221.34
  6102.3  221.33  6133.2  222.27  6143.5  223.41  6153.8   223.1  6184.7  224.17
#Mann= 6 ,-1 , 0
  3816.4     .05       0  4996.3    .035       0  5002.3     .05       0
    5039      .1       0  5236.9     .05       0  5247.2      .1       0
Bank Sta=4848.8,5071.5
XS Rating Curve= 0 ,0
Exp/Cntr=0.3,0.1

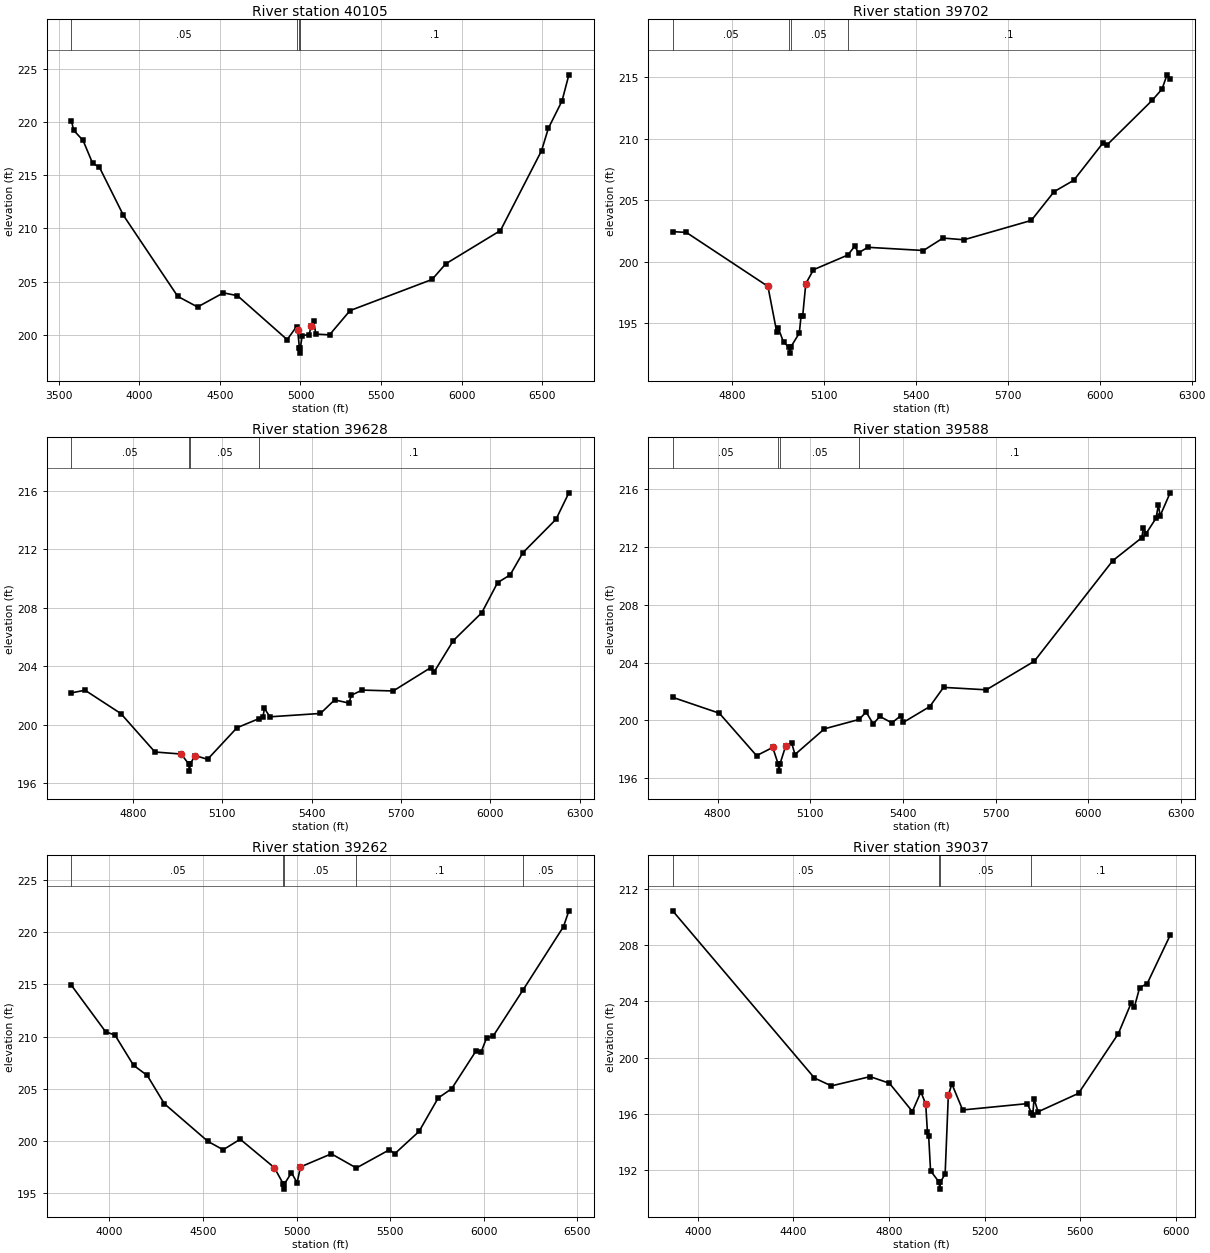
Type RM Length L Ch R = 1 ,40105   ,403,403,403
BEGIN DESCRIPTION:
UNT018 IN NURI 52.0
END DESCRIPTION:
XS GIS Cut Line= 3
       2289987.7     13313196.87      2288787.72     13313896.85
      2287587.71     13315096.87
#Sta/Elev= 30
  3578.8  220.14  3592.4  219.23  3651.1  218.27  3709.8  216.14  3752.8  215.74
  3901.7  211.22  4238.3  203.61  4361.5  202.61  4521.9  203.94  4609.1  203.67
  4917.2  199.54  4975.4  200.76  4982.2  200.48  4993.3  198.77  4996.1  198.27
  4999.3  198.77  5010.4  199.91  5052.9  200.02    5067   200.8  5081.2  201.28
  5095.3  200.06  5180.2  199.99  5307.4  202.27  5816.6   205.2  5901.4  206.67
  6240.8   209.8  6495.4   217.3  6537.8  219.41  6622.7  221.99  6665.1  224.44
#Mann= 4 ,-1 , 0
  3578.8     .05       0  4975.4      .1       0  4993.3     .07       0
  4999.3      .1       0
Bank Sta=4982.2,5067
XS Rating Curve= 0 ,0
Exp/Cntr=0.3,0.1

Type RM Length L Ch R = 1 ,39702   ,74,74,74
BEGIN DESCRIPTION:
Mapping XS 6d651995
END DESCRIPTION:
XS GIS Cut Line= 3
      2289071.09     13313468.28      2288661.39     13313558.56
      2287532.88     13313975.24
#Sta/Elev= 30
  4607.3  202.45  4651.7  202.39  4917.9  198.01  4946.4  194.34  4951.5  194.64
  4969.1  193.46  4986.6  193.09  4989.4  192.59  4992.6  193.09  5020.3  194.21
  5026.1  195.62  5031.4  195.62  5041.5  198.23  5066.6  199.36  5178.4  200.55
  5201.3  201.27  5213.4  200.73  5243.9  201.18  5425.2  200.92  5489.1  201.93
  5557.2  201.79  5776.9  203.36  5851.5   205.7  5915.5  206.62  6011.4  209.67
  6022.7  209.46  6171.3  213.11  6203.3  214.02  6219.7  215.18  6229.8  214.86
#Mann= 4 ,-1 , 0
  4607.3     .05       0  4986.6    .035       0  4992.6     .05       0
  5178.4      .1       0
Bank Sta=4917.9,5041.5
XS Rating Curve= 0 ,0
Exp/Cntr=0.3,0.1

Type RM Length L Ch R = 1 ,39628   ,40,40,40
BEGIN DESCRIPTION:
UNT018 IN NURI 51.0
END DESCRIPTION:
XS GIS Cut Line= 6
      2289067.59     13313419.68       2288772.5       13313503.
      2288723.89     13313464.81      2288668.33     13313485.64
      2288619.72     13313530.78      2287512.43     13313926.49
#Sta/Elev= 30
  4593.1  202.18  4638.8  202.36  4759.2  200.76  4873.5  198.13  4961.6  197.99
  4986.5  197.32  4989.3  196.82  4992.5  197.32  5007.8  197.89  5050.3  197.63
  5148.8  199.79  5223.3  200.42  5235.9  200.51  5241.2  201.12  5259.3  200.54
  5429.2  200.77  5476.8   201.7  5524.7  201.48  5533.1  202.02  5569.2  202.37
  5673.4  202.31  5799.6  203.91  5811.5  203.64  5875.2  205.76  5970.8  207.67
  6023.9  209.73    6066  210.26  6108.8  211.78    6220  214.07  6263.1  215.88
#Mann= 4 ,-1 , 0
  4593.1     .05       0  4986.5    .035       0  4992.5     .05       0
  5223.3      .1       0
Bank Sta=4961.6,5007.8
XS Rating Curve= 0 ,0
Exp/Cntr=0.3,0.1

Type RM Length L Ch R = 1 ,39588   ,326,326,326
BEGIN DESCRIPTION:
Mapping XS f20c0b28
END DESCRIPTION:
XS GIS Cut Line= 3
      2289022.46     13313357.18      2288532.92     13313475.22
      2287505.15     13313884.94
#Sta/Elev= 30
  4654.7   201.6  4805.7   200.5  4926.2  197.56  4978.5  198.13    4996  196.99
  4998.8  196.49    5002  196.99  5020.3  198.22  5040.2  198.42  5050.5  197.64
    5146  199.42  5258.4  200.07  5280.6  200.59  5303.8  199.76  5325.3  200.28
  5364.1  199.83  5393.8  200.34  5400.7  199.86  5486.8  200.96  5531.3  202.29
  5669.8  202.12  5825.1   204.1  6078.9  211.06  6172.9  212.65  6178.3  213.35
  6186.6  212.93  6218.9     214  6226.8  214.93  6232.2  214.16  6264.7  215.76
#Mann= 4 ,-1 , 0
  4654.7     .05       0    4996    .035       0    5002     .05       0
  5258.4      .1       0
Bank Sta=4978.5,5020.3
XS Rating Curve= 0 ,0
Exp/Cntr=0.3,0.1

Type RM Length L Ch R = 1 ,39262   ,225,225,225
BEGIN DESCRIPTION:
UNT018 IN NURI 50.0
END DESCRIPTION:
XS GIS Cut Line= 3
      2289737.68     13312946.86      2288537.72     13313146.85
      2287337.75     13313946.83
#Sta/Elev= 30
  3796.8  214.92  3979.2  210.47  4029.9  210.13  4128.8  207.24  4202.3  206.26
  4293.5  203.55  4526.7  199.93  4607.8  199.13    4699  200.14  4881.5  197.41
  4929.2  195.85    4932  195.35  4935.2  195.85  4972.8  196.92  5003.2  195.97
  5020.8  197.48  5186.1  198.74  5319.6  197.38  5495.6  199.12  5525.6  198.76
  5654.8  200.89    5757   204.1  5829.1  204.99  5958.3  208.59  5986.8  208.52
  6015.4  209.86  6051.4  210.06  6209.7  214.45    6427  220.56  6455.5  222.07
#Mann= 5 ,-1 , 0
  3796.8     .05       0  4929.2    .035       0  4935.2     .05       0
  5319.6      .1       0  6209.7     .05       0
Bank Sta=4881.5,5020.8
XS Rating Curve= 0 ,0
Exp/Cntr=0.3,0.1

Type RM Length L Ch R = 1 ,39037   ,64,64,64
BEGIN DESCRIPTION:
Mapping XS b43e9f29
END DESCRIPTION:
XS GIS Cut Line= 3
      2289564.12     13312768.63      2288463.47     13312938.76
      2287592.88     13313361.92
#Sta/Elev= 30
  3894.7  210.44  4488.1  198.55  4558.9  197.99  4720.8  198.65  4801.7  198.18
  4897.8  196.17  4933.3  197.56  4953.5  196.71  4960.9  194.68  4965.9  194.45
  4973.8  191.96  5009.4  191.15  5012.1  190.65  5015.4  191.15  5034.9  191.74
  5048.2  197.31    5063  198.13  5108.2  196.28  5378.8  196.73  5395.7  196.07
  5401.4   195.9  5406.9  197.07  5423.9  196.15    5593  197.46  5759.8  201.71
    5813  203.87  5826.5  203.58  5848.7  204.97  5880.6  205.27  5976.4   208.7
#Mann= 4 ,-1 , 0
  3894.7     .05       0  5009.4    .035       0  5015.4     .05       0
  5395.7      .1       0
Bank Sta=4953.5,5048.2
XS Rating Curve= 0 ,0
Exp/Cntr=0.3,0.1

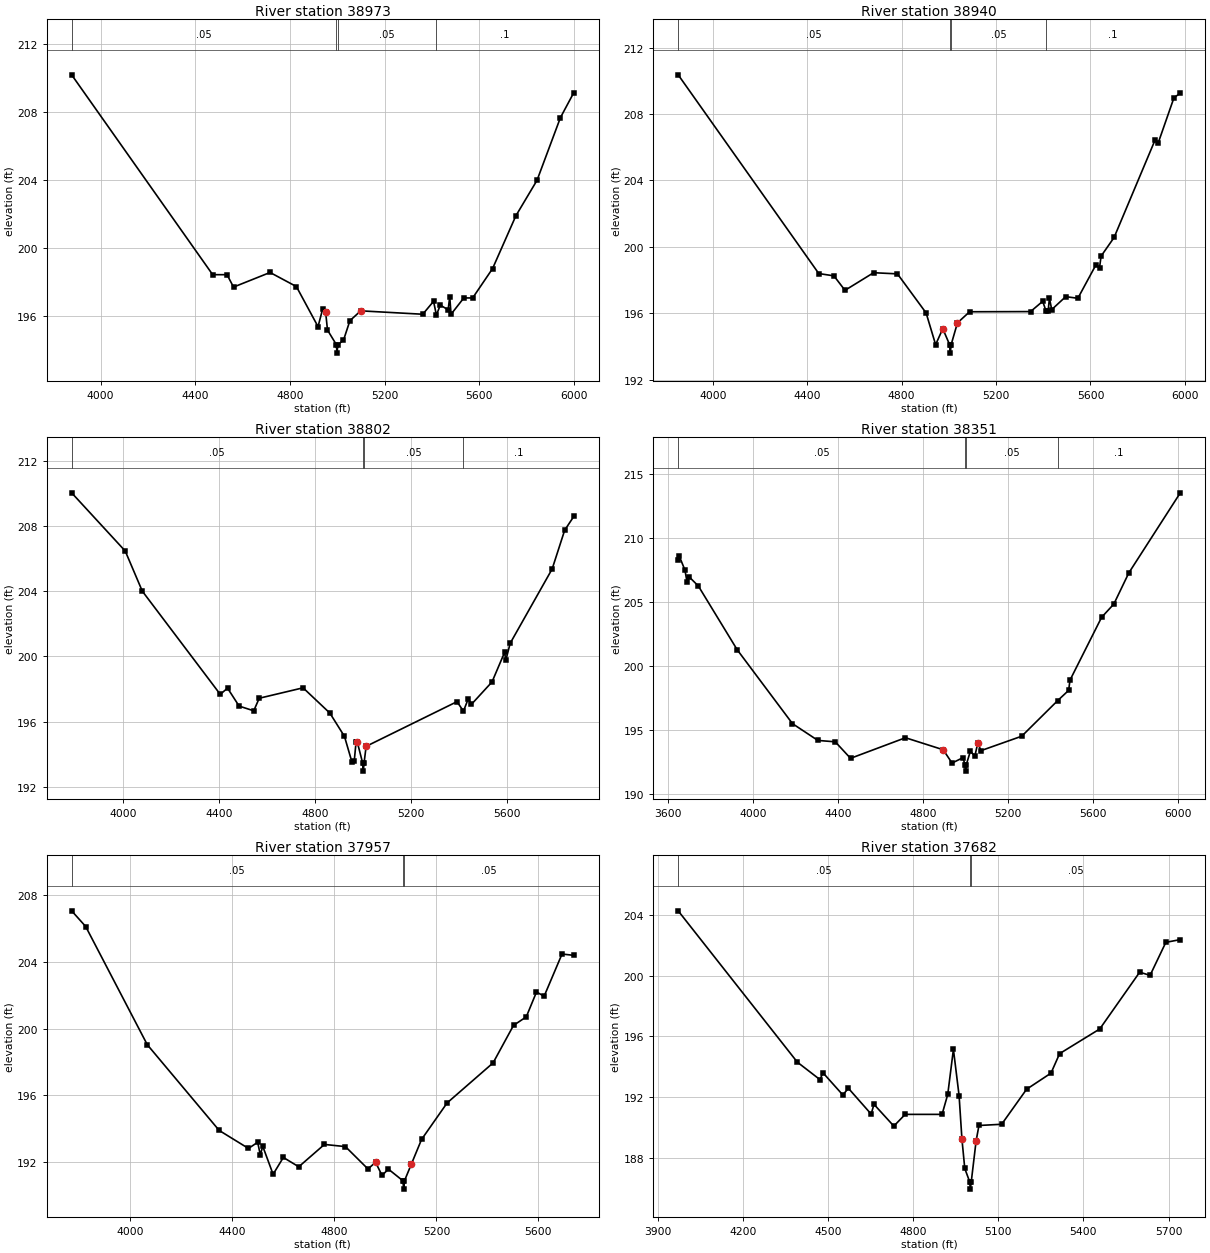
Type RM Length L Ch R = 1 ,38973   ,33,33,33
BEGIN DESCRIPTION:
Mapping XS ac566424
END DESCRIPTION:
XS GIS Cut Line= 5
      2289557.27      13312733.9       2288498.2     13312886.68
      2288432.22     13312876.26      2288400.97     13312917.93
      2287557.22     13313313.77
#Sta/Elev= 30
  3878.1  210.21  4473.8  198.44  4534.4  198.44  4561.9  197.71  4716.2  198.57
  4827.4  197.74  4918.8  195.38  4938.5  196.43  4950.9  196.24  4958.7  195.18
  4996.2  194.32    4999  193.82  5002.2  194.32  5026.3  194.58  5053.4  195.73
    5099  196.31  5361.1  196.11  5406.7  196.87  5418.8  196.06  5435.1  196.65
  5468.2  196.37  5475.1  197.13  5480.7  196.11  5534.5  197.07  5571.9  197.07
    5656   198.8  5754.5  201.91  5843.8     204  5942.6  207.69    5999  209.16
#Mann= 4 ,-1 , 0
  3878.1     .05       0  4996.2    .035       0  5002.2     .05       0
  5418.8      .1       0
Bank Sta=4950.9,5099
XS Rating Curve= 0 ,0
Exp/Cntr=0.3,0.1

Type RM Length L Ch R = 1 ,38940   ,138,138,138
BEGIN DESCRIPTION:
Mapping XS 7276cbdb
END DESCRIPTION:
XS GIS Cut Line= 3
      2289557.23     13312688.76      2288439.17     13312848.49
      2287532.88     13313265.17
#Sta/Elev= 30
  3853.6  210.36  4449.1   198.4  4513.3  198.26  4560.2  197.39  4681.4  198.45
  4782.4  198.38  4903.7  196.03  4944.1  194.12  4974.4  195.08  5003.6  194.11
  5006.4  193.61  5009.6  194.11  5036.5  195.43    5088   196.1  5346.2  196.11
  5397.7  196.73    5411  196.17  5420.7  196.16  5426.2  196.91  5435.9  196.23
  5495.1  197.01  5546.5  196.91    5623  198.92  5638.4  198.76    5645  199.45
    5700  200.57  5873.7  206.44  5887.1  206.27  5953.6  208.98  5980.5  209.26
#Mann= 4 ,-1 , 0
  3853.6     .05       0  5003.6    .035       0  5009.6     .05       0
    5411      .1       0
Bank Sta=4974.4,5036.5
XS Rating Curve= 0 ,0
Exp/Cntr=0.3,0.1

Type RM Length L Ch R = 1 ,38802   ,451,451,451
BEGIN DESCRIPTION:
UNT018 IN NURI 49.0
END DESCRIPTION:
XS GIS Cut Line= 3
      2289537.68     13312546.86      2288337.72     13312746.85
      2287537.74     13313096.85
#Sta/Elev= 30
  3787.4  210.03  4010.4  206.46  4081.4     204  4405.8  197.67  4436.2  198.05
  4484.3  196.95  4545.2  196.66    4568  197.43  4750.5  198.07    4862  196.52
  4922.8  195.09  4953.2  193.55  4963.4  193.57    4971  194.74    4976  194.75
  4998.4  193.46  5001.1  192.96  5004.4  193.46  5012.9  194.48    5391  197.22
    5418  196.64  5437.8  197.39  5451.4  197.06  5536.8  198.43    5589  200.24
  5594.5  199.78  5612.4   200.8  5787.1  205.36  5839.3  207.74  5877.1  208.58
#Mann= 4 ,-1 , 0
  3787.4     .05       0  4998.4    .035       0  5004.4     .05       0
    5418      .1       0
Bank Sta=4976,5012.9
XS Rating Curve= 0 ,0
Exp/Cntr=0.3,0.1

Type RM Length L Ch R = 1 ,38351   ,394,394,394
BEGIN DESCRIPTION:
UNT018 IN NURI 48.0
END DESCRIPTION:
XS GIS Cut Line= 3
      2289388.78     13311941.38      2288363.61     13312177.44
       2287337.7     13312996.87
#Sta/Elev= 30
  3647.4  208.27  3651.6  208.61  3679.3  207.48  3689.2  206.54  3699.8  206.94
  3742.3  206.24  3925.6  201.25  4185.8  195.48  4305.2  194.17  4387.3  194.06
  4459.2  192.77  4717.9  194.38  4895.6  193.44  4937.3   192.4  4988.5  192.82
  4998.3  192.27    5001  191.77  5004.3  192.27  5023.7  193.33  5044.5  192.94
  5058.9  193.98  5073.3  193.37  5265.5   194.5  5434.7  197.28  5486.4  198.08
  5492.8  198.88  5641.7  203.79  5699.4  204.83  5769.8  207.26  6012.4  213.52
#Mann= 4 ,-1 , 0
  3647.4     .05       0  4998.3    .035       0  5004.3     .05       0
  5434.7      .1       0
Bank Sta=4895.6,5058.9
XS Rating Curve= 0 ,0
Exp/Cntr=0.3,0.1

Type RM Length L Ch R = 1 ,37957   ,275,275,275
BEGIN DESCRIPTION:
UNT018 IN NURI 47.0
END DESCRIPTION:
XS GIS Cut Line= 3
      2289332.38     13311863.25      2288269.03     13311984.77
      2287371.65     13312028.12
#Sta/Elev= 30
  3769.9  207.07  3824.9  206.13  4066.5  199.04  4348.3   193.9  4463.1  192.82
  4499.3  193.19  4509.3  192.45  4519.4  192.94  4559.7  191.27  4599.9  192.28
  4660.3  191.72    4761  193.06  4843.3  192.93  4931.6  191.59  4961.6  191.99
  4986.8   191.2  5011.7  191.58  5068.8  190.88  5071.5  190.38  5074.8  190.88
  5101.8  191.88  5141.8  193.36    5242  195.55  5422.2  197.95  5502.3   200.2
  5552.3  200.71  5592.4   202.2  5622.4  201.95  5692.5  204.48  5738.6   204.4
#Mann= 3 ,-1 , 0
  3769.9     .05       0  5068.8    .035       0  5074.8     .05       0
Bank Sta=4961.6,5101.8
XS Rating Curve= 0 ,0
Exp/Cntr=0.3,0.1

Type RM Length L Ch R = 1 ,37682   ,86,86,86
BEGIN DESCRIPTION:
Mapping XS bd20089b
END DESCRIPTION:
XS GIS Cut Line= 3
      2289217.73     13311715.46      2288019.79     13311731.08
      2287483.37     13311928.98
#Sta/Elev= 30
  3971.8  204.25  4391.8  194.31  4471.8  193.16  4481.8  193.62  4551.9  192.16
  4571.9  192.59  4651.9   190.9  4661.9  191.54  4731.9  190.11  4771.9  190.88
  4901.9  190.88  4921.9  192.19  4941.9  195.15  4961.9  192.11  4971.9  189.26
  4981.9  187.33  4998.9  186.47  5001.6  185.97  5004.9  186.47  5021.9  189.14
  5031.9  190.15  5111.9  190.23  5199.8  192.53  5285.8  193.59  5316.2  194.87
  5457.7  196.49  5598.4  200.22    5635  200.01  5690.6  202.18  5741.6  202.36
#Mann= 3 ,-1 , 0
  3971.8     .05       0  4998.9    .035       0  5004.9     .05       0
Bank Sta=4971.9,5021.9
XS Rating Curve= 0 ,0
Exp/Cntr=0.3,0.1

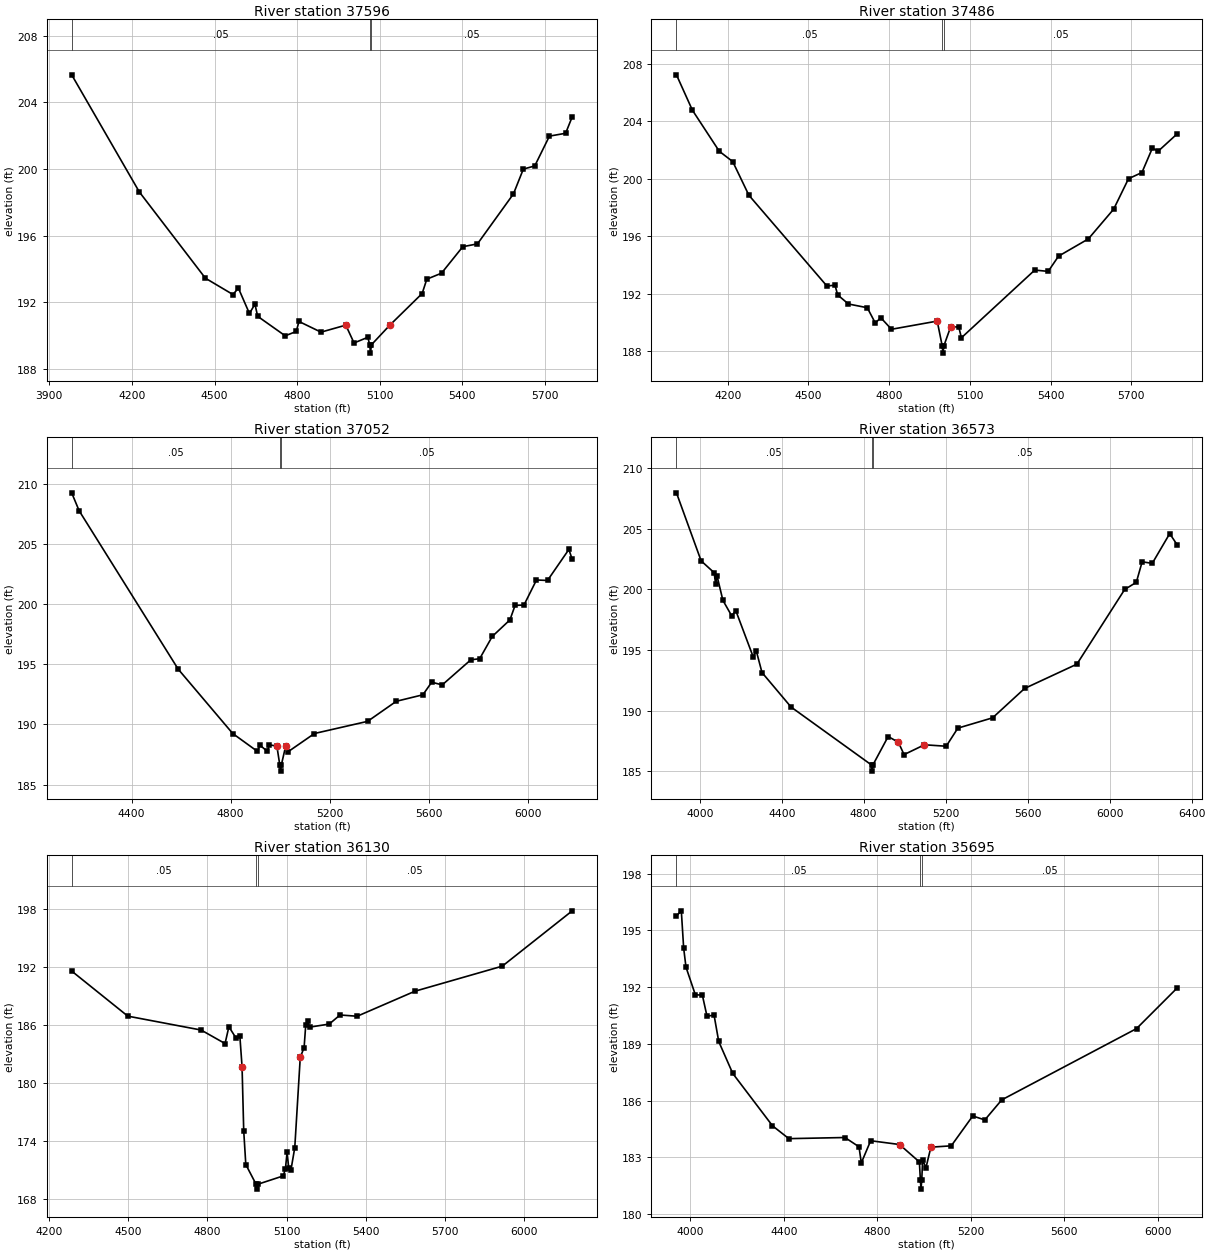
Type RM Length L Ch R = 1 ,37596   ,110,110,110
BEGIN DESCRIPTION:
Mapping XS 991c79c5
END DESCRIPTION:
XS GIS Cut Line= 3
       2289233.3     13311642.54      2288058.85     13311647.75
      2287463.42     13311892.16
#Sta/Elev= 30
  3981.2  205.65  4226.8  198.62  4466.8  193.44  4566.8  192.46  4586.8  192.84
  4626.8  191.32  4646.8  191.88  4656.8  191.15  4756.8  189.98  4796.8  190.24
  4806.8  190.84  4886.8   190.2  4976.8  190.62  5006.8  189.55  5056.8  189.89
  5063.8  189.44  5066.5  188.94  5069.8  189.44  5136.8  190.62  5254.2  192.52
  5271.1  193.38  5324.5  193.74  5401.8  195.33  5455.1   195.5  5585.8   198.5
  5621.7  199.99  5663.2  200.18  5716.5  201.97  5775.3  202.14  5799.3  203.13
#Mann= 3 ,-1 , 0
  3981.2     .05       0  5063.8    .035       0  5069.8     .05       0
Bank Sta=4976.8,5136.8
XS Rating Curve= 0 ,0
Exp/Cntr=0.3,0.1

Type RM Length L Ch R = 1 ,37486   ,434,434,434
BEGIN DESCRIPTION:
UNT018 IN NURI 46.0
END DESCRIPTION:
XS GIS Cut Line= 3
      2289236.88     13311559.42      2288017.29     13311537.72
      2287448.29     13311832.48
#Sta/Elev= 30
  4009.5  207.23  4068.7  204.77  4168.7  201.91  4218.7  201.19  4278.7  198.85
  4568.8  192.53  4598.8  192.59  4608.8  191.91  4648.8  191.28  4718.8  191.02
  4748.8  189.95  4768.8  190.33  4808.8  189.52  4978.8  190.09  4997.4  188.36
  5000.2  187.86  5003.4  188.36  5028.8  189.69  5058.8  189.68  5068.8  188.93
  5341.4  193.64  5391.3  193.55  5429.9  194.61  5540.6  195.81  5634.7  197.88
  5689.9     200  5739.8  200.43  5778.4  202.12  5800.5  201.92  5870.1  203.11
#Mann= 3 ,-1 , 0
  4009.5     .05       0  4997.4    .035       0  5003.4     .05       0
Bank Sta=4978.8,5028.8
XS Rating Curve= 0 ,0
Exp/Cntr=0.3,0.1

Type RM Length L Ch R = 1 ,37052   ,479,479,479
BEGIN DESCRIPTION:
UNT018 IN NURI 45.0
END DESCRIPTION:
XS GIS Cut Line= 3
      2289187.76     13311096.85      2288387.72     13311096.85
      2287387.72     13311796.86
#Sta/Elev= 30
  4158.5  209.27  4188.5  207.78  4588.5   194.6  4808.5  189.25  4908.5  187.76
  4918.5  188.28  4948.5  187.76    4956  188.31  4986.9   188.2  4998.7  186.62
  5001.5  186.12  5004.7  186.62  5022.6  188.22  5031.3  187.72  5138.6  189.25
  5353.1  190.26    5469  191.93  5576.3  192.47    5612  193.52  5654.3  193.29
  5769.8  195.38  5805.6  195.47  5856.2  197.32  5927.7   198.7  5948.6  199.91
  5984.3  199.93  6034.9  202.02  6079.4  201.98  6165.7  204.56  6179.2  203.73
#Mann= 3 ,-1 , 0
  4158.5     .05       0  4998.7    .035       0  5004.7     .05       0
Bank Sta=4986.9,5022.6
XS Rating Curve= 0 ,0
Exp/Cntr=0.3,0.1

Type RM Length L Ch R = 1 ,36573   ,443,443,443
BEGIN DESCRIPTION:
UNT018 IN NURI 44.0
END DESCRIPTION:
XS GIS Cut Line= 3
      2288987.69     13309996.89      2288187.72     13310746.85
      2287287.72     13311746.85
#Sta/Elev= 30
  3886.6  207.95  4006.9  202.35  4070.5  201.37  4077.8  200.43  4084.6  201.11
    4113   199.1  4155.4  197.84  4176.5  198.23  4261.4  194.42  4275.6  194.96
  4303.9  193.15  4445.6  190.31  4838.7  185.53  4841.5  185.03  4844.7  185.53
  4919.4  187.88  4969.2  187.41    4997  186.39  5096.4   187.2  5202.5  187.08
  5259.3  188.57    5429  189.42  5585.2  191.84  5840.1  193.84  6073.3  199.99
  6130.1  200.58  6158.5  202.27  6207.8  202.14    6293  204.59  6328.5  203.69
#Mann= 3 ,-1 , 0
  3886.6     .05       0  4838.7    .035       0  4844.7     .05       0
Bank Sta=4969.2,5096.4
XS Rating Curve= 0 ,0
Exp/Cntr=0.3,0.1

Type RM Length L Ch R = 1 ,36130   ,435,435,435
BEGIN DESCRIPTION:
UNT018 IN NURI 43.0
END DESCRIPTION:
XS GIS Cut Line= 4
      2288604.23     13310188.54      2288044.31     13310327.44
      2287727.47     13310566.15      2287372.16     13311419.77
#Sta/Elev= 30
  4285.3  191.59  4498.1  186.92  4776.2  185.48  4866.9  184.08  4881.4  185.82
  4908.5  184.65  4923.1  184.83  4931.4  181.68  4937.7  175.04  4945.6  171.55
  4984.6   169.5  4987.4     169  4990.6   169.5  5087.6  170.37  5095.8   171.1
  5102.1  172.81  5108.4   171.2  5116.7  170.97  5131.3   173.3  5152.1  182.65
  5166.7  183.67  5172.9  186.01  5181.2  186.37  5187.5  185.78    5262   186.1
    5303  187.04    5368  186.91  5586.8   189.5  5918.4   192.1  6183.5  197.83
#Mann= 3 ,-1 , 0
  4285.3     .05       0  4984.6    .035       0  4990.6     .05       0
Bank Sta=4931.4,5152.1
XS Rating Curve= 0 ,0
Exp/Cntr=0.3,0.1

Type RM Length L Ch R = 1 ,35695   ,346,346,346
BEGIN DESCRIPTION:
UNT018 IN NURI 42.0
END DESCRIPTION:
XS GIS Cut Line= 4
      2288648.56     13310008.45      2287714.45     13310014.94
      2287569.18      13310168.7      2287320.34     13311132.94
#Sta/Elev= 30
  3940.9  195.77  3961.7  196.04  3971.7  194.07  3981.7  193.06  4021.7   191.6
  4051.7  191.58  4071.7  190.46  4101.7  190.53  4121.7  189.13  4181.7  187.44
  4351.8  184.67  4421.8  183.99  4661.8  184.05  4721.8  183.56  4731.8  182.71
  4771.8  183.88  4895.2  183.68  4980.2  182.76  4984.4  181.82  4987.2  181.32
  4990.4  181.82  4994.3  182.85  5008.5  182.46  5029.5  183.54  5116.6  183.61
  5208.6  185.19  5260.2  184.98  5332.5  186.04  5909.3  189.81  6082.4  191.95
#Mann= 3 ,-1 , 0
  3940.9     .05       0  4984.4    .035       0  4990.4     .05       0
Bank Sta=4895.2,5029.5
XS Rating Curve= 0 ,0
Exp/Cntr=0.3,0.1

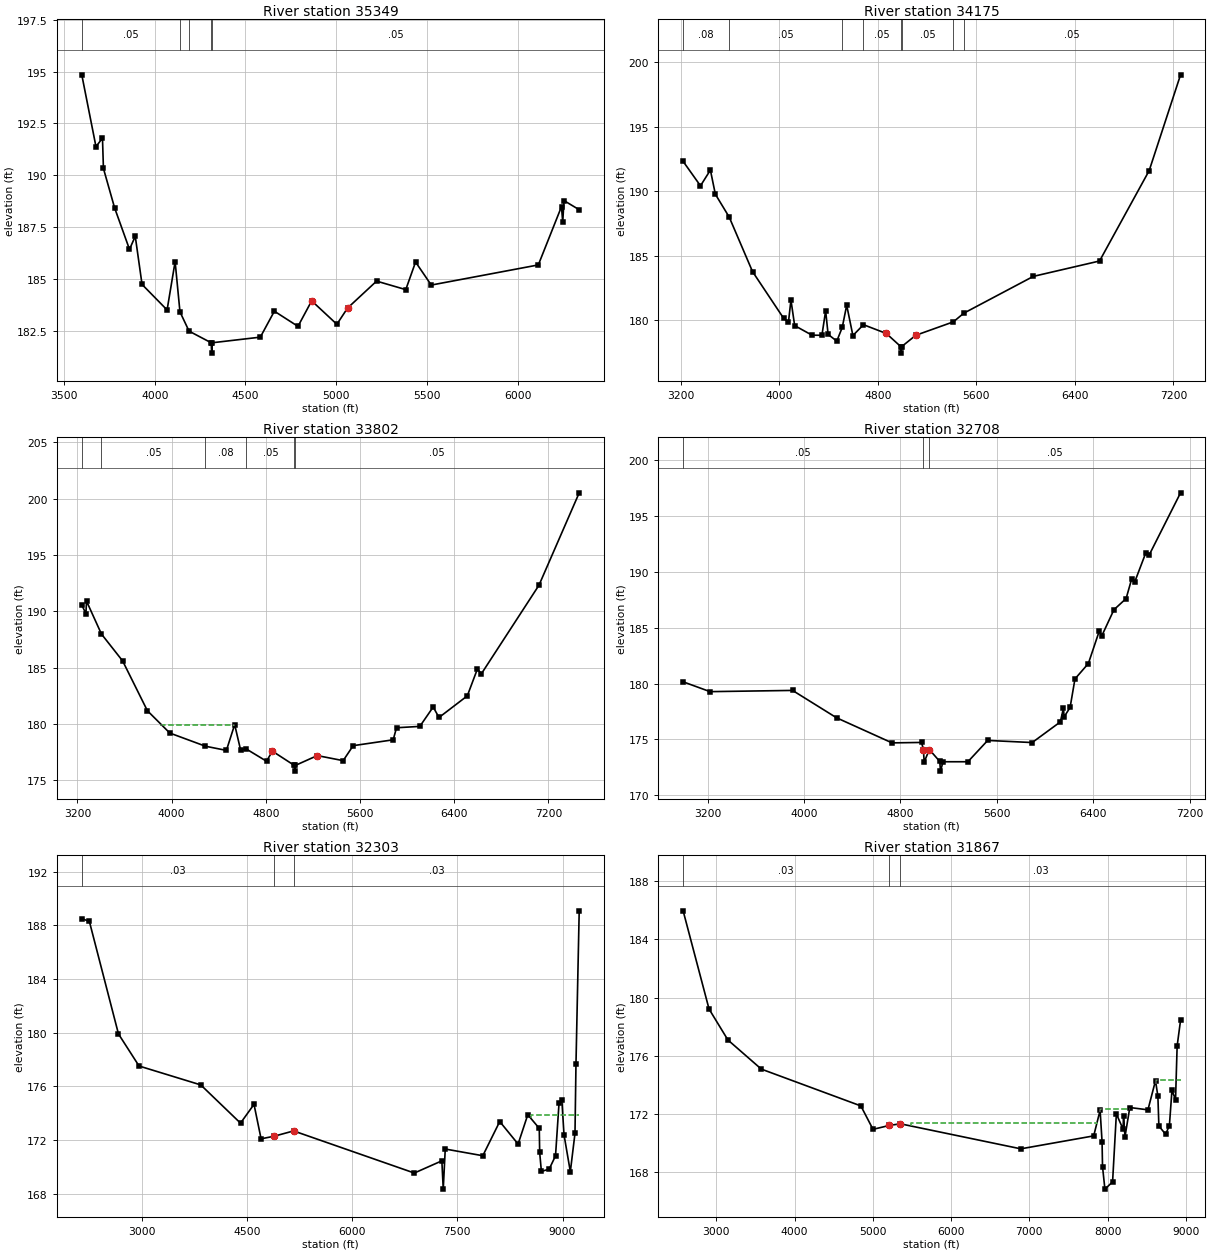
Type RM Length L Ch R = 1 ,35349   ,1174,1174,1174
BEGIN DESCRIPTION:
UNT018 IN NURI 41.0
END DESCRIPTION:
XS GIS Cut Line= 4
       2288683.9     13309647.68       2288217.3     13309539.16
      2286839.26      13310103.4      2286265.51     13310623.02
#Sta/Elev= 30
  3597.5  194.84  3675.7  191.38  3711.6  191.79  3716.8  190.33  3778.4  188.43
  3860.5  186.43  3892.3  187.06  3929.7  184.74  4067.8  183.51    4112  185.84
  4138.7  183.42  4188.8  182.49  4310.8  181.93  4313.6  181.43  4316.8  181.93
  4581.8   182.2  4659.2  183.45  4789.3  182.72  4864.9  183.95  5003.7  182.82
  5062.5   183.6  5222.7   184.9  5383.6  184.49  5437.6  185.82  5524.1  184.71
  6114.3  185.68  6242.1  188.49  6248.8  187.73  6255.8  188.78  6339.7  188.34
#Mann= 5 ,-1 , 0
  3597.5     .05       0  4138.7     .08       0  4188.8     .05       0
  4310.8    .035       0  4316.8     .05       0
Bank Sta=4864.9,5062.5
XS Rating Curve= 0 ,0
Exp/Cntr=0.3,0.1

Type RM Length L Ch R = 1 ,34175   ,373,373,373
BEGIN DESCRIPTION:
UNT018 IN NURI 40.0
END DESCRIPTION:
XS GIS Cut Line= 3
      2289137.74     13308946.85      2287337.72     13309146.85
      2285737.69     13310696.88
#Sta/Elev= 30
  3219.4   192.3  3360.3  190.41  3440.8  191.63    3481  189.76  3593.5  187.99
  3782.9  183.77  4034.4  180.17  4074.6  179.85  4094.8  181.57    4125  179.59
  4265.8  178.85  4346.3  178.84  4376.5  180.73  4396.6  178.91    4467  178.39
  4511.4  179.45  4547.5  181.17  4597.8  178.82  4683.6  179.66  4869.5  178.98
  4987.2  177.96    4990  177.46  4993.2  177.96  5108.3  178.84  5413.4  179.88
  5498.2  180.55  6062.9   183.4  6600.5  184.59  7003.6  191.59  7258.2     199
#Mann= 8 ,-1 , 0
  3219.4     .08       0  3593.5     .05       0  4511.4     .08       0
  4683.6     .05       0  4987.2     .03       0  4993.2     .05       0
  5413.4      .1       0  5498.2     .05       0
Bank Sta=4869.5,5108.3
XS Rating Curve= 0 ,0
Exp/Cntr=0.3,0.1

Type RM Length L Ch R = 1 ,33802   ,1094,1094,1094
BEGIN DESCRIPTION:
Mapping XS a482dabb
END DESCRIPTION:
XS GIS Cut Line= 4
      2288934.08     13308944.03      2287232.69     13308848.54
      2287102.48     13308857.22      2285487.87     13310619.41
#Sta/Elev= 30
  3237.5  190.58  3272.6   189.8  3277.6  190.92  3404.3     188  3584.4  185.61
  3794.7  181.19    3985  179.21  4288.1  178.04  4465.8  177.67  4535.9  179.96
    4586  177.72  4635.6  177.79  4806.3  176.71  4856.4   177.6  5043.8  176.33
  5046.5  175.83  5049.8  176.33  5237.8  177.21  5457.3  176.76  5542.4  178.09
  5882.2  178.61  5910.6  179.68  6108.5   179.8    6222  181.52  6271.3  180.59
  6511.8  182.51  6596.9  184.88    6632  184.48  7120.4  192.33  7462.1  200.53
#Mann= 6 ,-1 , 0
  3237.5     .08       0  3404.3     .05       0  4288.1     .08       0
  4635.6     .05       0  5043.8     .04       0  5049.8     .05       0
#XS Ineff= 1 ,-1
 3898.24 4532.12  179.88
Permanent Ineff=
       F
Bank Sta=4856.4,5237.8
XS Rating Curve= 0 ,0
Exp/Cntr=0.3,0.1

Type RM Length L Ch R = 1 ,32708   ,405,405,405
BEGIN DESCRIPTION:
UNT018 IN NURI 39.0
END DESCRIPTION:
XS GIS Cut Line= 4
      2288129.46     13308815.69      2286185.07     13308593.96
       2285460.2     13309480.87       2285315.5     13310493.74
#Sta/Elev= 30
  2997.3  180.16  3220.5  179.28  3904.9  179.39  4269.5  176.94  4730.2  174.69
  4975.6  174.73    4990  174.05  4996.8  172.98  5039.5  174.09  5125.7  173.03
  5131.9  172.16  5152.9     173    5359     173  5523.4  174.91  5892.4  174.72
    6126  176.57  6151.9  177.81    6157  177.02  6206.8  177.86  6247.2  180.42
  6358.3   181.8  6449.2  184.72  6469.4  184.27  6570.5  186.62  6671.5  187.62
  6717.6  189.38  6742.2  189.09  6833.1  191.67  6864.1  191.55  7122.9  197.09
#Mann= 3 , 0 , 0
  2997.3     .05       0    4990     .03       0  5039.5     .05       0
#XS Ineff= 1 ,-1
 5047.19 5442.42  173.93
Permanent Ineff=
       T
Bank Sta=4990,5039.5
XS Rating Curve= 0 ,0
Exp/Cntr=0.3,0.1

Type RM Length L Ch R = 1 ,32303   ,436,436,436
BEGIN DESCRIPTION:
UNT018 IN NURI 38.0
END DESCRIPTION:
XS GIS Cut Line= 3
      2288854.61      13308827.7      2286209.92     13308410.69
      2281822.08     13307884.82
#Sta/Elev= 30
  2141.2   188.5  2249.4  188.29  2664.5   179.9  2958.1  177.51  3838.8   176.1
  4405.7  173.25  4598.1  174.65  4699.3  172.08  4889.5  172.28  5163.2  172.67
  6885.4  169.53  7278.2  170.44  7298.1  168.33  7326.7  171.32  7862.4  170.82
  8104.1  173.37    8366  171.69  8504.2  173.88  8668.1  172.86  8673.8  171.07
  8698.3  169.65  8809.1  169.82  8899.8  170.81  8950.1  174.75  8990.4  174.97
  9020.6   172.4  9111.3  169.63  9177.7  172.49  9191.8  177.67  9237.8  189.08
#Mann= 3 , 0 , 0
  2141.2     .03       0  4889.5     .03       0  5163.2     .03       0
#XS Ineff= 2 ,-1
 5204.88 8507.74 172.487 8546.12 9240.91 173.858
Permanent Ineff=
       T       F
Bank Sta=4889.5,5163.2
XS Rating Curve= 0 ,0
Exp/Cntr=0.3,0.1

Type RM Length L Ch R = 1 ,31867   ,699,699,699
BEGIN DESCRIPTION:
Mapping XS 793cb319
END DESCRIPTION:
XS GIS Cut Line= 3
      2288616.82     13308766.95      2286455.35     13308126.32
      2282455.34     13307220.07
#Sta/Elev= 30
  2576.5  185.96  2907.6  179.21  3149.2  177.08  3575.7  175.08  4847.5  172.55
  5002.8  170.94  5213.1  171.21  5352.7  171.32  6891.1   169.6  7822.5  170.49
  7904.5  172.25  7929.4   170.1  7935.3  168.38  7965.8  166.83  8063.9  167.33
  8112.2     172  8198.4  170.95  8203.5  171.86  8222.4  170.43  8283.9  172.44
  8515.7  172.28  8612.3  174.29  8642.8  173.22  8655.4  171.17  8741.7   170.6
  8789.9   171.2  8822.4  173.62  8868.3  172.98  8888.8  176.67  8932.3  178.43
#Mann= 3 , 0 , 0
  2576.5     .03       0  5213.1     .03       0  5352.7     .03       0
#XS Ineff= 3 ,-1
 5487.28 7861.72 171.366 7906.25 8284.09  172.32 8618.18 8956.25  174.32
Permanent Ineff=
       T       F       F
Bank Sta=5213.1,5352.7
XS Rating Curve= 0 ,0
Exp/Cntr=0.3,0.1