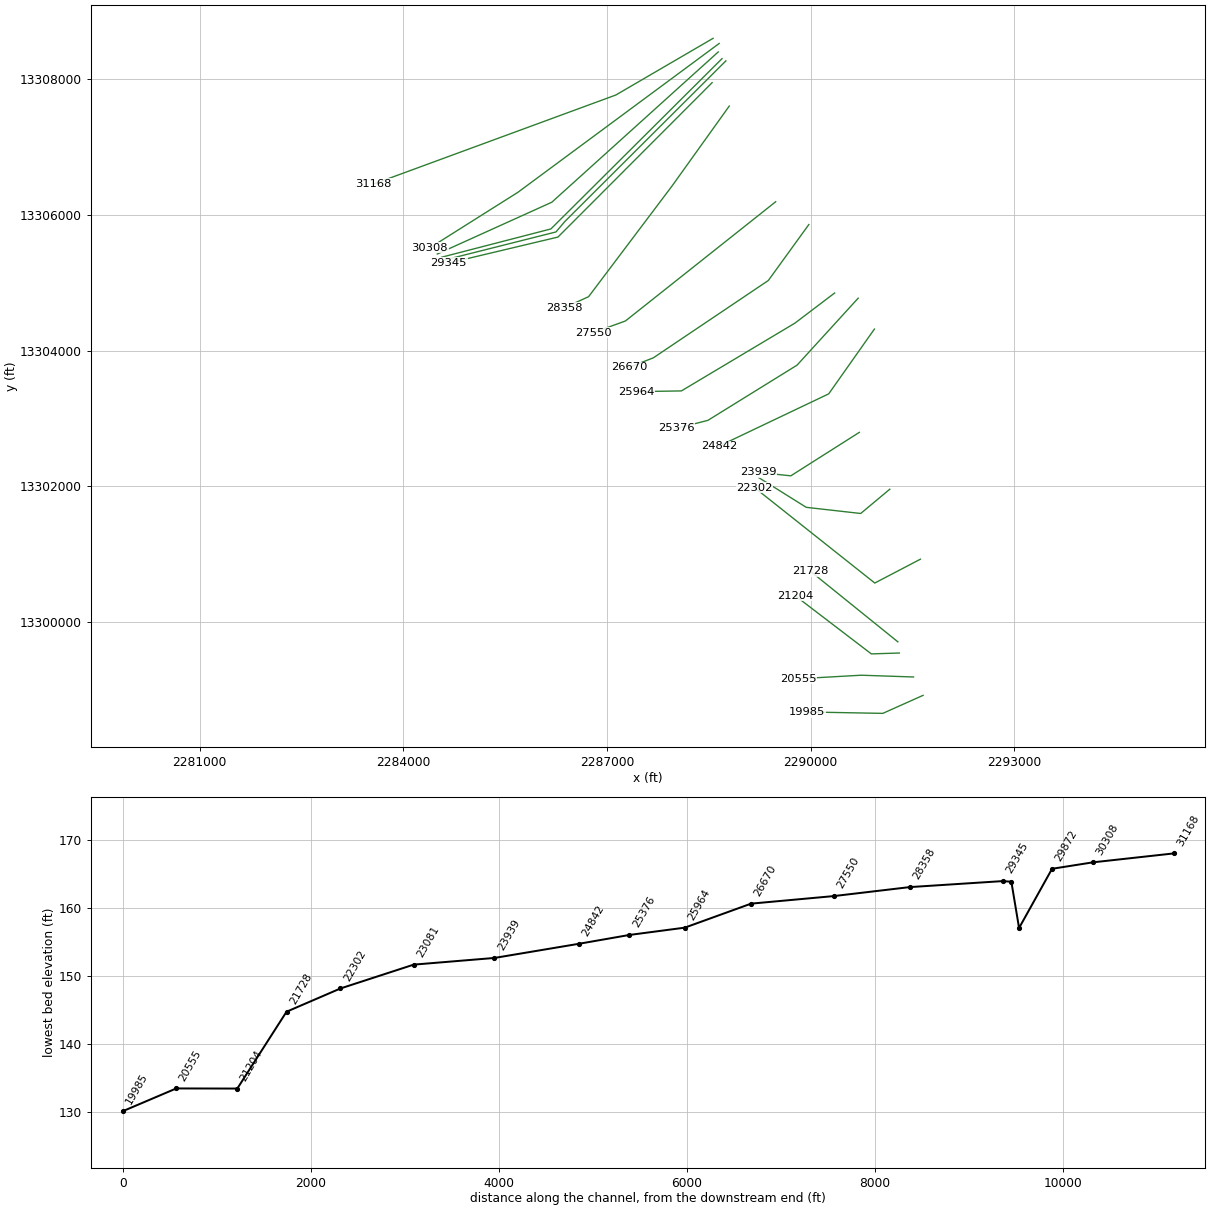
HEC-RAS study UNT018 IN NURI.prj: UNT018 IN NURI Base Level Engineering

--- UNT018 IN NURI.g01 (geometry) --- (continued)

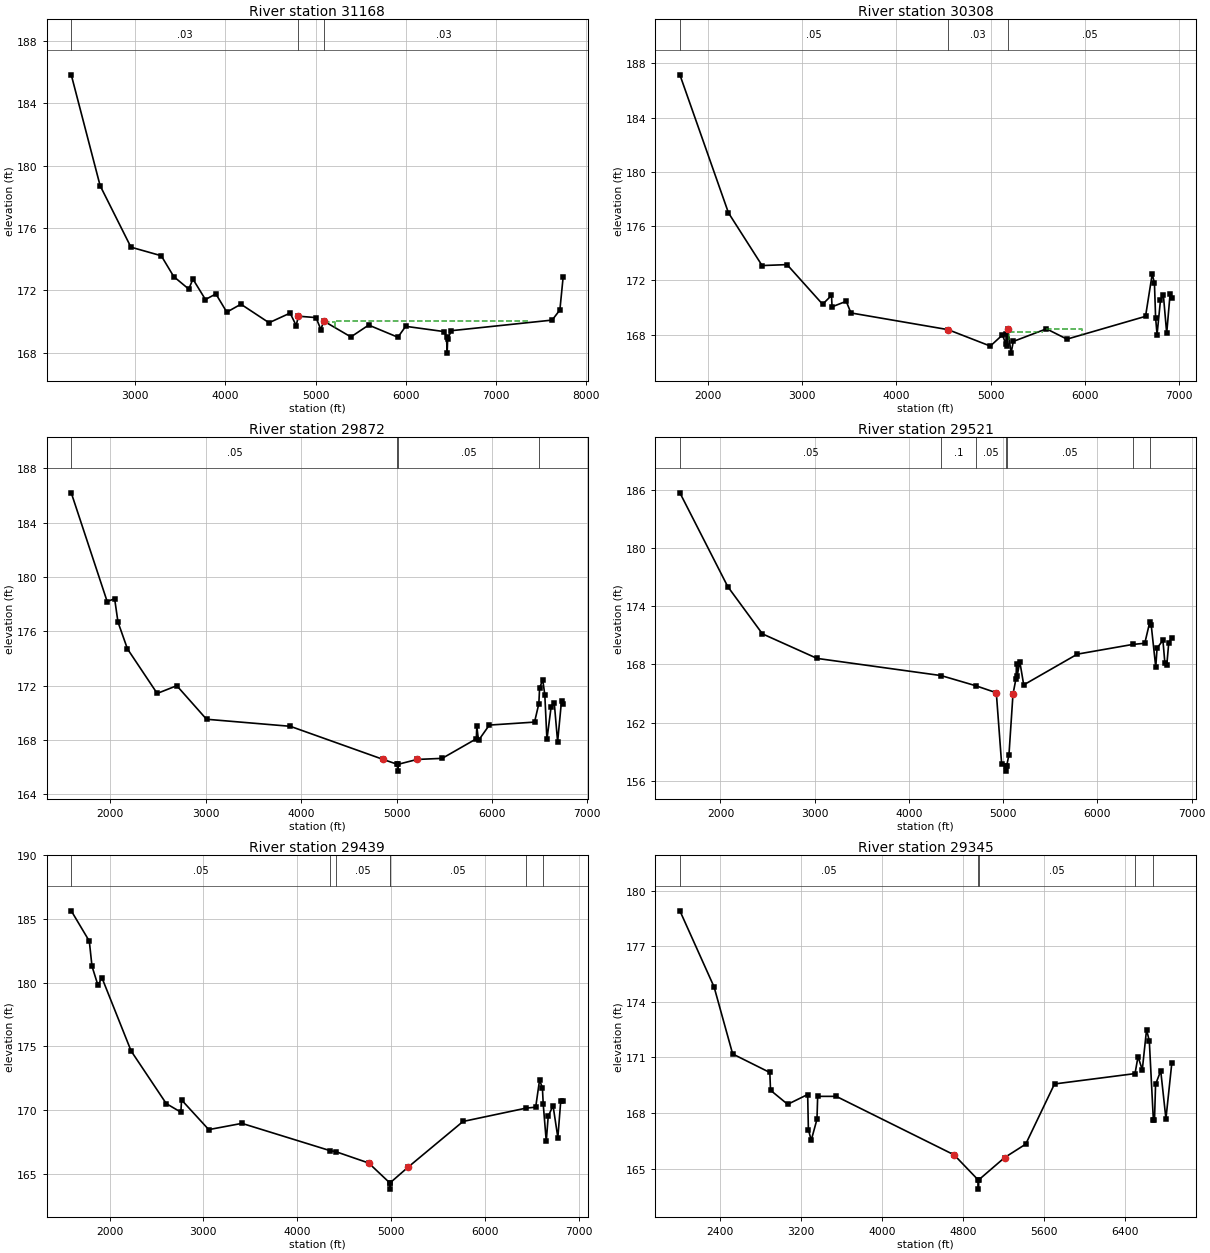
Type RM Length L Ch R = 1 ,31168   ,860,860,860
BEGIN DESCRIPTION:
Mapping XS 18e963c0
END DESCRIPTION:
XS GIS Cut Line= 3
       2288564.5     13308605.99      2287132.23      13307770.5
      2283562.55     13306457.64
#Sta/Elev= 30
    2288  185.82  2608.2  178.71  2950.5  174.76  3287.1  174.21    3426  172.87
  3592.5  172.07  3638.8  172.71  3777.7   171.4  3893.5  171.76  4014.9  170.59
  4171.7   171.1  4483.7  169.91  4718.1  170.53  4784.9  169.73    4810  170.33
  5005.8  170.24  5059.1  169.47    5091  170.02  5392.7     169    5590  169.76
  5914.5  168.98  6000.6  169.68    6431  169.34  6454.8  168.98  6461.2  167.96
  6466.8  168.86  6508.1   169.4  7626.9  170.08  7712.9  170.73  7749.6  172.87
#Mann= 3 , 0 , 0
    2288     .03       0    4810     .03       0    5091     .03       0
#XS Ineff= 2 ,-1
 5093.21  5214.5  169.95 5218.43 7360.76     170
Permanent Ineff=
       T       T
Bank Sta=4810,5091
XS Rating Curve= 0 ,0
Exp/Cntr=0.3,0.1

Type RM Length L Ch R = 1 ,30308   ,436,436,436
BEGIN DESCRIPTION:
Mapping XS dac6354e
END DESCRIPTION:
XS GIS Cut Line= 3
      2288654.85      13308530.6      2285689.54     13306336.14
      2284391.81     13305517.24
#Sta/Elev= 30
  1701.6  187.15  2217.5  176.98  2574.4   173.1  2839.5  173.17  3217.2  170.25
  3311.2   170.9  3317.4  170.06  3467.7  170.47  3517.8  169.61 4549.09  168.38
  4997.7  167.17  5127.1  167.99  5162.6  167.31  5168.9  168.07  5177.2  167.19
  5183.4  168.41  5218.6  166.65  5241.9  167.51  5593.8  168.44  5811.7  167.68
  6646.1  169.36  6717.1  172.48  6740.7   171.8  6753.1  169.24  6768.4  168.02
  6804.9  170.56  6835.3  170.94  6870.8  168.11  6906.3  170.97  6925.1  170.69
#Mann= 3 , 0 , 0
  1701.6     .05       0 4549.09     .03       0  5183.4     .05       0
#XS Ineff= 3 ,-1
 5198.69 5558.84  168.19 5593.98 5969.95  168.43 6737.69 6915.13  170.81
Permanent Ineff=
       F       F       F
Bank Sta=4549.09,5183.4
XS Rating Curve= 0 ,0
Exp/Cntr=0.3,0.1

Type RM Length L Ch R = 1 ,29872   ,351,351,351
BEGIN DESCRIPTION:
Mapping XS c43f0f3c
END DESCRIPTION:
XS GIS Cut Line= 3
      2288640.91     13308405.56      2286189.54      13306190.3
      2284502.38     13305426.57
#Sta/Elev= 30
  1590.6  186.19  1967.3  178.18    2045   178.4  2080.1  176.68  2179.5   174.7
  2491.1  171.42  2696.6  171.99  3008.2  169.52  3886.2     169  4856.2  166.57
    5009   166.2  5011.7   165.7    5015   166.2    5215  166.56  5478.4  166.64
  5835.9  168.08  5841.3  168.99    5859  167.96  5972.4  169.09  6446.3  169.31
  6491.6  170.67  6499.2  171.81  6532.2  172.43  6554.1  171.31  6576.1  168.03
    6620  170.42  6652.9  170.73  6688.3  167.86    6729  170.86  6746.6  170.63
#Mann= 4 ,-1 , 0
  1590.6     .05       0    5009     .03       0    5015     .05       0
  6491.6      .1       0
Bank Sta=4856.2,5215
XS Rating Curve= 0 ,0
Exp/Cntr=0.3,0.1

Type RM Length L Ch R = 1 ,29521   ,82,82,82
BEGIN DESCRIPTION:
Mapping XS 46a1418c
END DESCRIPTION:
XS GIS Cut Line= 3
       2288696.5     13308306.63      2286175.65     13305796.21
      2284566.27     13305379.54
#Sta/Elev= 30
  1569.3  185.69  2077.4  176.02  2445.1  171.15  3024.9  168.62  4341.3  166.85
  4709.9   165.8    4927  165.08  4983.6  157.73  5030.1   157.5  5032.9     157
  5036.1   157.5  5061.4   158.7  5103.8  164.92  5135.2  166.51  5142.3  168.04
  5147.5  166.77  5176.5  168.28  5217.8  165.89  5786.9  169.06  6373.8  170.06
  6502.3  170.18  6554.6  172.33    6571  172.04    6619  167.72    6633  169.68
  6694.9  170.49  6715.6  168.17  6735.7   167.9  6756.9  170.24  6789.4  170.76
#Mann= 7 ,-1 , 0
  1569.3     .05       0  4341.3      .1       0  4709.9     .05       0
  5030.1     .03       0  5036.1     .05       0  6373.8     .08       0
  6554.6      .1       0
Bank Sta=4927,5103.8
XS Rating Curve= 0 ,0
Exp/Cntr=0.3,0.1

Type RM Length L Ch R = 1 ,29439   ,94,94,94
BEGIN DESCRIPTION:
UNT018 IN NURI 37.0
END DESCRIPTION:
XS GIS Cut Line= 4
      2288753.04     13308273.62      2286383.64     13305908.68
      2286250.31     13305751.91      2284612.82     13305339.13
#Sta/Elev= 30
    1592  185.64  1784.4  183.26  1812.7   181.3  1876.3   179.8  1918.7  180.39
  2229.9  174.64  2604.6  170.51  2760.2  169.84  2767.3   170.8  3057.2  168.47
  3410.7  168.96  4349.9  166.82  4410.9  166.74  4761.3  165.85  4984.7   164.3
  4987.5   163.8  4990.7   164.3  5179.1  165.51  5766.9  169.11  6440.6  170.16
  6541.1  170.23  6582.2  172.35  6612.6  171.77  6621.6  170.46  6653.8  167.56
  6674.5   169.5    6726  170.36  6777.3  167.85  6808.5  170.74  6834.2  170.71
#Mann= 7 ,-1 , 0
    1592     .05       0  4349.9      .1       0  4410.9     .05       0
  4984.7     .03       0  4990.7     .05       0  6440.6     .08       0
  6621.6      .1       0
Bank Sta=4761.3,5179.1
XS Rating Curve= 0 ,0
Exp/Cntr=0.3,0.1

Type RM Length L Ch R = 1 ,29345   ,987,987,987
BEGIN DESCRIPTION:
UNT018 IN NURI 36.0
END DESCRIPTION:
XS GIS Cut Line= 3
      2288550.68     13307952.49      2286279.82     13305676.41
      2284671.02     13305293.57
#Sta/Elev= 30
  1999.1  178.92  2337.5  174.81  2521.4  171.19  2889.1  170.19  2896.1  169.23
  3065.8  168.47  3263.8     169  3270.9   167.1  3299.2  166.53  3355.8  167.66
  3362.8   168.9  3546.7   168.9  4713.4  165.74  4950.8  164.39  4953.6  163.89
  4956.8  164.39  5212.2  165.59    5422  166.32  5706.9  169.57  6503.9  170.13
  6533.6  171.05  6575.7  170.33  6617.9   172.5  6645.2   171.9  6685.4  167.62
  6696.6  167.62  6707.3  169.55  6758.3  170.28  6809.7  167.69    6868   170.7
#Mann= 5 ,-1 , 0
  1999.1     .05       0  4950.8     .03       0  4956.8     .05       0
  6503.9     .08       0  6685.4      .1       0
Bank Sta=4713.4,5212.2
XS Rating Curve= 0 ,0
Exp/Cntr=0.3,0.1

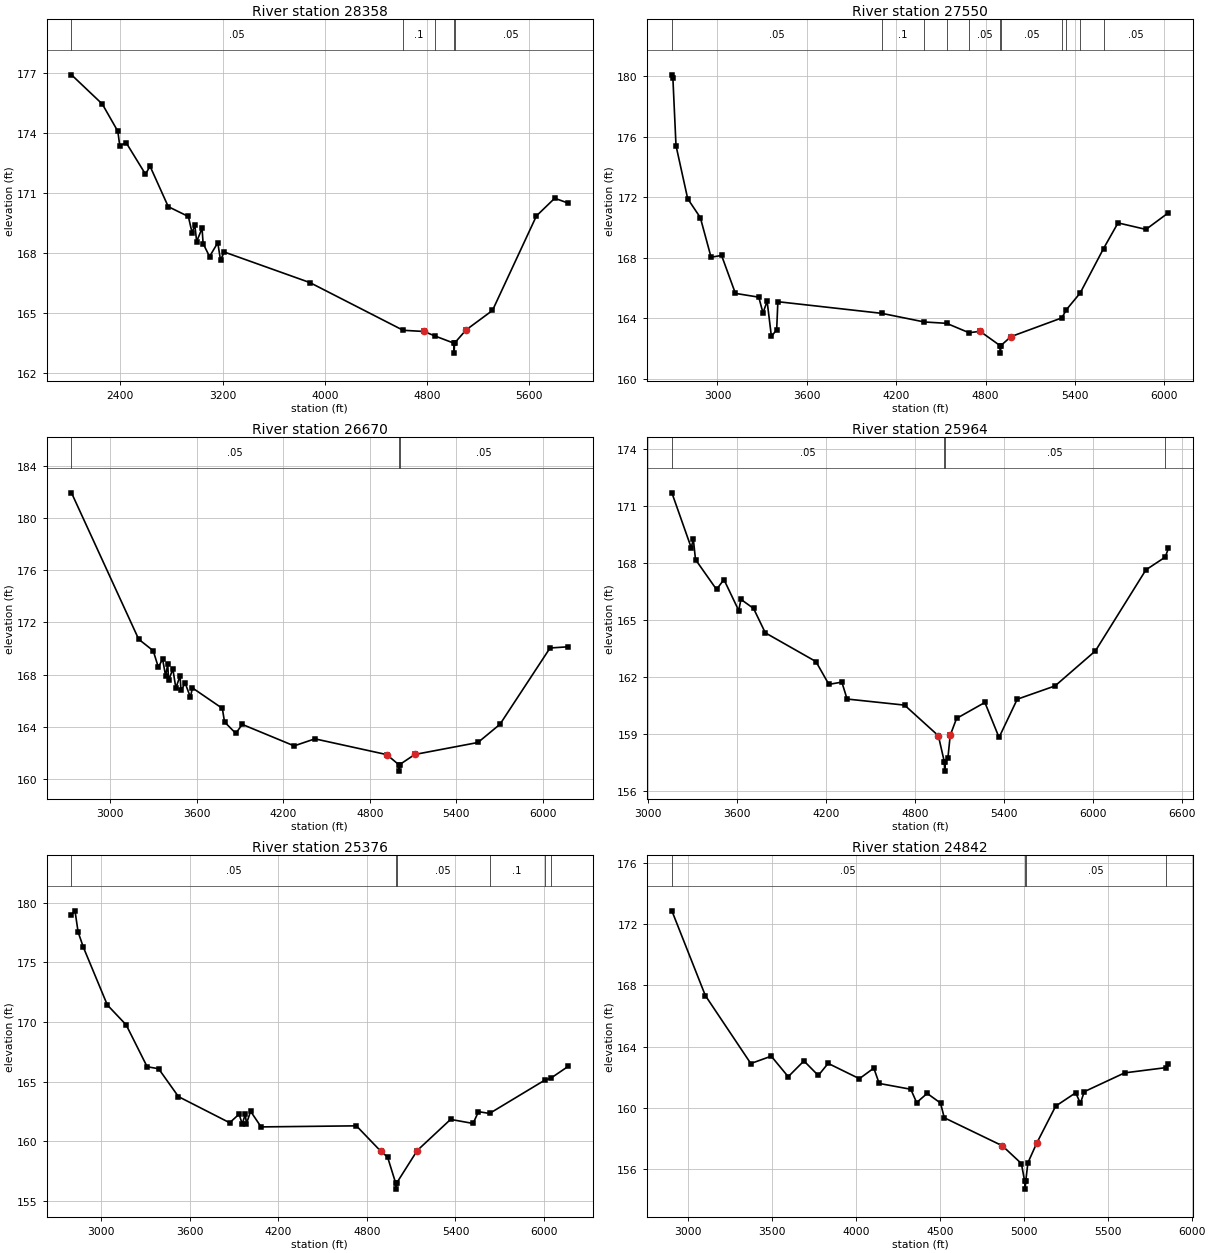
Type RM Length L Ch R = 1 ,28358   ,808,808,808
BEGIN DESCRIPTION:
UNT018 IN NURI 34.0
END DESCRIPTION:
XS GIS Cut Line= 4
      2288803.24     13307607.74      2287956.88     13306425.01
      2286730.75     13304797.41      2286372.73     13304634.67
#Sta/Elev= 30
  2018.2   176.9  2259.4  175.44    2381  174.08  2395.7  173.36  2446.1  173.51
  2597.2  171.94  2632.8  172.34  2775.4  170.32  2932.6  169.83  2962.1  169.01
    2983  169.41  2997.7  168.58  3039.9  169.24  3048.1  168.48  3098.5  167.83
  3162.9  168.52  3184.5  167.64  3212.1  168.06    3884  166.53  4613.2  164.15
  4777.2  164.09  4864.4  163.86  5009.5  163.51  5012.2  163.01  5015.5  163.51
  5106.2  164.17  5312.3  165.14  5656.5  169.86  5799.3  170.74  5903.6   170.5
#Mann= 5 ,-1 , 0
  2018.2     .05       0  4613.2      .1       0  4864.4     .05       0
  5009.5     .03       0  5015.5     .05       0
Bank Sta=4777.2,5106.2
XS Rating Curve= 0 ,0
Exp/Cntr=0.3,0.1

Type RM Length L Ch R = 1 ,27550   ,880,880,880
BEGIN DESCRIPTION:
UNT018 IN NURI 32.0
END DESCRIPTION:
XS GIS Cut Line= 4
      2289486.82     13306197.14       2289117.9     13305904.18
      2287273.29     13304439.34      2286795.86     13304265.73
#Sta/Elev= 30
  2693.6  180.09  2700.5  179.86  2721.3  175.41  2799.8   171.9  2884.7  170.65
  2956.8  168.03  3027.3  168.15  3120.2  165.64  3277.2  165.39  3305.4  164.35
  3333.3  165.12  3362.1  162.79  3397.4  163.24  3405.4  165.09    4103  164.32
  4388.9  163.75  4538.7  163.66  4688.8  163.04  4763.9  163.13  4897.1  162.19
  4899.9  161.69  4903.1  162.19  4970.6  162.78  5312.4  164.02  5342.8  164.56
  5435.3  165.66  5592.3   168.6  5689.7   170.3  5877.3  169.87  6028.2  170.97
#Mann= 11 ,-1 , 0
  2693.6     .05       0    4103      .1       0  4388.9     .05       0
  4538.7      .1       0  4688.8     .05       0  4897.1     .03       0
  4903.1     .05       0  5312.4      .1       0  5342.8     .05       0
  5435.3      .1       0  5592.3     .05       0
Bank Sta=4763.9,4970.6
XS Rating Curve= 0 ,0
Exp/Cntr=0.3,0.1

Type RM Length L Ch R = 1 ,26670   ,706,706,706
BEGIN DESCRIPTION:
UNT018 IN NURI 31.0
END DESCRIPTION:
XS GIS Cut Line= 4
      2289975.08     13305860.74      2289378.32     13305036.13
      2287685.61      13303896.8      2287327.51     13303755.73
#Sta/Elev= 30
  2731.6  181.96  3197.7  170.71  3298.3  169.83  3333.8  168.56  3363.2  169.19
  3384.1  167.91  3398.8  168.78    3405  167.56  3434.4  168.42  3455.3  166.97
  3484.7   167.9  3490.8  166.79  3520.2  167.33  3555.8  166.27  3570.5  166.97
  3777.7   165.4  3792.7  164.36  3870.8  163.48  3915.6  164.17  4275.5  162.52
  4419.5  163.06  4917.3  161.85  5000.9  161.08  5003.6  160.58  5006.9  161.08
  5112.3  161.86  5550.2  162.78    5703  164.18    6050  170.04  6174.8  170.13
#Mann= 3 ,-1 , 0
  2731.6     .05       0  5000.9     .03       0  5006.9     .05       0
Bank Sta=4917.3,5112.3
XS Rating Curve= 0 ,0
Exp/Cntr=0.3,0.1

Type RM Length L Ch R = 1 ,25964   ,588,588,588
BEGIN DESCRIPTION:
UNT018 IN NURI 29.0
END DESCRIPTION:
XS GIS Cut Line= 4
      2290354.88     13304851.66      2289768.95     13304406.79
      2288097.94     13303408.52       2287436.1     13303397.67
#Sta/Elev= 30
  3161.3  171.68  3291.4   168.8    3306  169.23  3320.5  168.17    3462   166.6
  3511.9  167.12  3611.7  165.49  3626.3  166.08  3711.6   165.6  3790.6  164.32
  4131.4  162.81  4218.7  161.61  4306.1  161.73  4341.2  160.84  4728.4  160.52
  4956.1  158.91  4995.9  157.55  4998.6  157.05  5001.9  157.55  5020.3  157.74
  5035.8  158.93  5078.6  159.82  5269.3  160.66  5364.7  158.82  5487.2  160.83
  5742.1  161.53  6013.7  163.37  6353.8  167.63  6483.7   168.3  6505.4  168.76
#Mann= 4 ,-1 , 0
  3161.3     .05       0  4995.9     .03       0  5001.9     .05       0
  6483.7      .1       0
Bank Sta=4956.1,5035.8
XS Rating Curve= 0 ,0
Exp/Cntr=0.3,0.1

Type RM Length L Ch R = 1 ,25376   ,534,534,534
BEGIN DESCRIPTION:
UNT018 IN NURI 28.0
END DESCRIPTION:
XS GIS Cut Line= 4
      2290702.09     13304775.69       2289801.5      13303788.3
      2288488.56     13302974.49      2288022.39     13302855.24
#Sta/Elev= 30
    2800  179.01  2823.7  179.33  2844.7  177.56  2879.8  176.29  3042.7  171.43
  3170.3  169.76  3312.2  166.25  3389.9  166.08  3524.4  163.74    3871  161.55
  3935.1  162.27  3956.1  161.44    3977  162.27  3984.5  161.46  4012.8  162.51
  4083.8   161.2  4729.1  161.29  4894.3  159.16  4940.4  158.67  4995.3  156.48
  4998.1  155.98  5001.3  156.48  5141.2  159.22  5366.9  161.83  5519.3  161.49
  5555.9  162.48  5630.8  162.33  6005.6  165.13  6044.7  165.28  6162.3  166.27
#Mann= 6 ,-1 , 0
    2800     .05       0  4995.3     .03       0  5001.3     .05       0
  5630.8      .1       0  6005.6     .05       0  6044.7      .1       0
Bank Sta=4894.3,5141.2
XS Rating Curve= 0 ,0
Exp/Cntr=0.3,0.1

Type RM Length L Ch R = 1 ,24842   ,903,903,903
BEGIN DESCRIPTION:
Mapping XS 031c6970
END DESCRIPTION:
XS GIS Cut Line= 3
      2290940.85     13304320.02      2290268.08     13303365.12
      2288652.07     13302595.07
#Sta/Elev= 30
  2903.3  172.86  3102.6  167.33  3373.5  162.89  3495.4  163.37  3596.4  162.03
  3690.1  163.06  3775.7  162.11  3834.2   162.9  4020.3   161.9  4106.4  162.59
  4138.3  161.59  4326.6  161.21  4361.6  160.34  4424.2  160.94  4503.8  160.31
  4526.1  159.35  4872.1  157.52  4985.6  156.36  5005.3  155.19  5008.1  154.69
  5011.3  155.19  5024.4  156.41  5076.4  157.68  5189.9  160.11    5309  160.98
  5337.2  160.29  5359.9  161.05  5600.5  162.28  5845.1  162.62  5861.5  162.84
#Mann= 4 ,-1 , 0
  2903.3     .05       0  5005.3     .03       0  5011.3     .05       0
  5845.1      .1       0
Bank Sta=4872.1,5076.4
XS Rating Curve= 0 ,0
Exp/Cntr=0.3,0.1

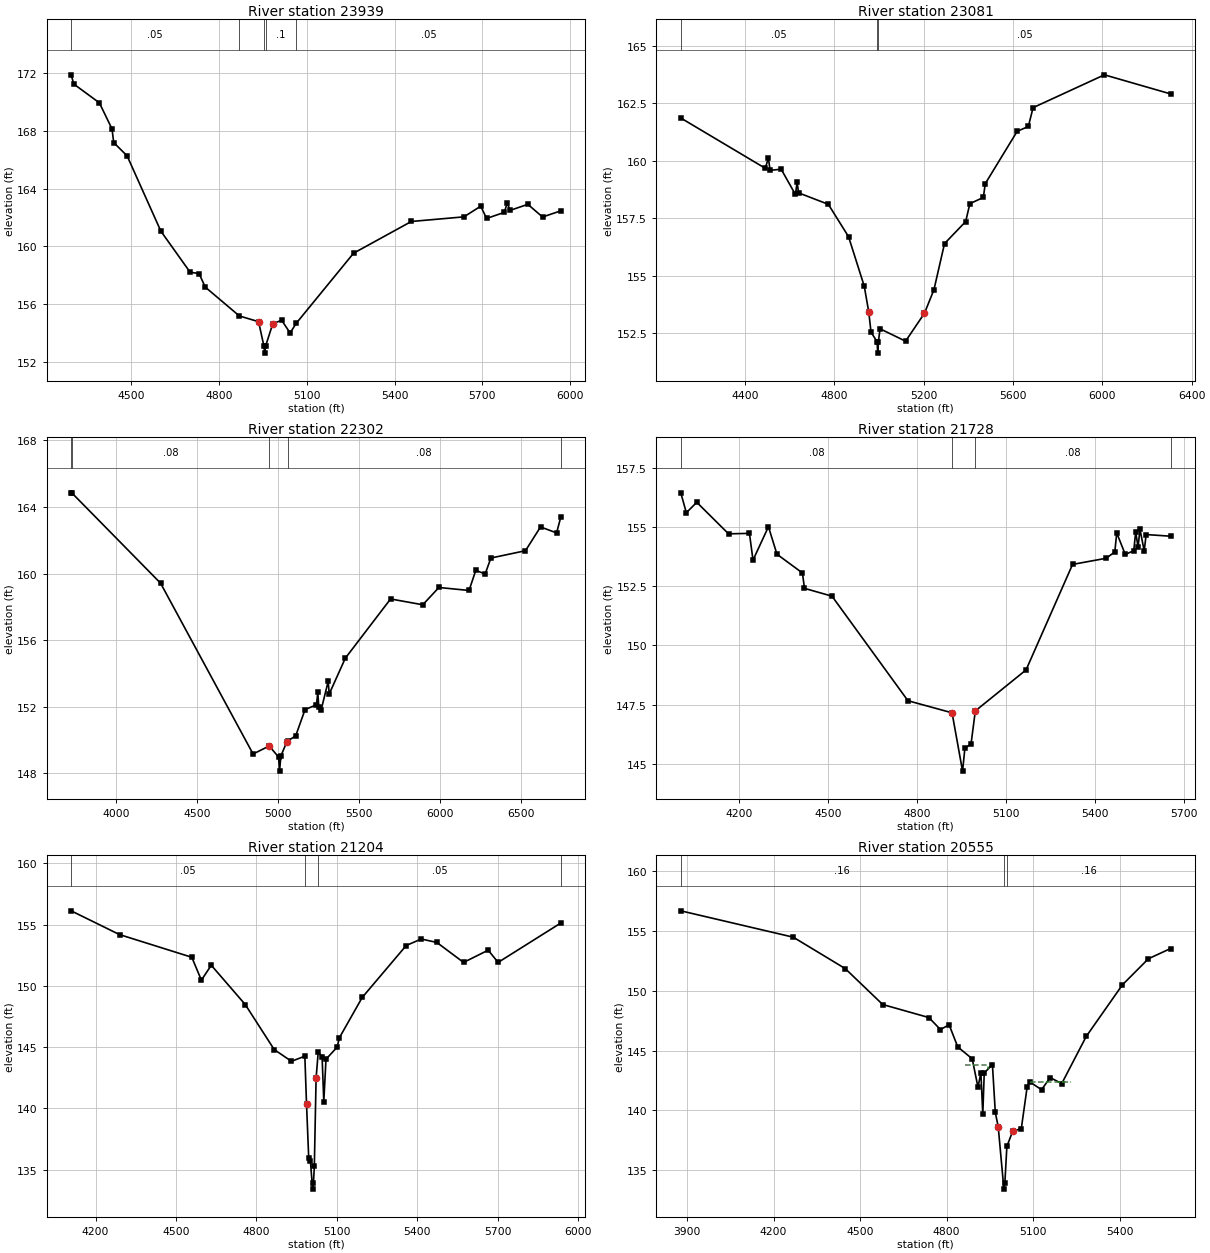
Type RM Length L Ch R = 1 ,23939   ,858,858,858
BEGIN DESCRIPTION:
Mapping XS 193562f0
END DESCRIPTION:
XS GIS Cut Line= 3
      2290719.02     13302797.53      2289709.78     13302156.66
      2289235.48     13302207.12
#Sta/Elev= 30
  4295.7   171.9  4304.7  171.26    4392  169.96  4435.2  168.15  4441.1   167.2
  4486.8  166.28    4602  161.06    4702  158.21  4732.5  158.12  4753.6  157.18
    4870  155.18  4935.8  154.78  4953.9   153.1  4956.7   152.6  4959.9   153.1
  4984.3  154.64  5014.5  154.88  5043.5     154  5064.4  154.67  5260.2  159.53
  5457.5  161.73    5637  162.05  5694.4  162.79  5714.5  161.94  5774.9  162.36
  5784.9     163    5795   162.5  5855.3  162.92  5905.6  162.04  5968.2  162.47
#Mann= 5 ,-1 , 0
  4295.7     .05       0    4870      .1       0  4953.9     .07       0
  4959.9      .1       0  5064.4     .05       0
Bank Sta=4935.8,4984.3
XS Rating Curve= 0 ,0
Exp/Cntr=0.3,0.1

Type RM Length L Ch R = 1 ,23081   ,779,779,779
BEGIN DESCRIPTION:
UNT018 IN NURI 27.0
END DESCRIPTION:
XS GIS Cut Line= 4
      2291168.13     13301959.86      2290739.21     13301601.58
      2289936.86     13301692.41      2289235.47     13302131.41
#Sta/Elev= 30
  4111.5  161.86  4489.9  159.67  4503.9  160.11  4511.7  159.58  4561.2  159.63
  4624.9  158.53  4632.7  159.06  4639.2   158.6  4772.5   158.1  4863.1  156.69
  4933.5  154.53  4953.7   153.4  4963.7  152.53  4990.9  152.12  4993.7  151.62
  4996.9  152.12    5004  152.68  5118.5  152.14  5203.2  153.36  5245.5  154.38
  5292.9  156.39  5387.7  157.35  5406.5  158.13  5466.9   158.4  5475.4     159
  5618.4  161.28  5668.4  161.49  5689.6  162.31  6009.1  163.74  6305.3  162.91
#Mann= 3 ,-1 , 0
  4111.5     .05       0  4990.9     .03       0  4996.9     .05       0
Bank Sta=4953.7,5203.2
XS Rating Curve= 0 ,0
Exp/Cntr=0.3,0.1

Type RM Length L Ch R = 1 ,22302   ,574,574,574
BEGIN DESCRIPTION:
UNT018 IN NURI 26.0
END DESCRIPTION:
XS GIS Cut Line= 3
      2291619.31     13300928.06      2290946.59     13300576.51
      2289176.71     13301981.84
#Sta/Elev= 30
    3724  164.85  3727.7  164.85  4275.1  159.42  4845.5  149.15  4944.8  149.63
  5002.5  148.97  5008.6  148.12  5016.9  149.03  5052.1  149.85  5058.5  149.93
  5108.2  150.24  5165.9  151.82  5236.4  152.11  5244.4  152.86  5250.8  151.96
  5265.2   151.8  5308.5  153.52  5314.9  152.76  5414.2  154.91    5693  158.47
  5891.6  158.12    5991  159.16  6176.8  158.98  6218.4  160.19  6276.1  159.97
  6311.4  160.93  6524.6  161.37  6617.4   162.8  6716.7  162.44    6743  163.42
#Mann= 5 ,-1 , 0
    3724     .05       0  3727.7     .08       0  4944.8     .05       0
  5058.5     .08       0    6743     .08       0
Bank Sta=4944.8,5052.1
XS Rating Curve= 0 ,0
Exp/Cntr=0.3,0.1

Type RM Length L Ch R = 1 ,21728   ,524,524,524
BEGIN DESCRIPTION:
UNT018 IN NURI 24.0
END DESCRIPTION:
XS GIS Cut Line= 2
      2291286.61     13299709.58      2290002.76     13300746.66
#Sta/Elev= 30
  4004.4  156.44  4023.1   155.6  4058.3  156.04  4165.4  154.71  4235.8  154.73
  4247.8   153.6  4299.8  155.01  4328.5  153.85  4414.3  153.06  4421.3  152.41
    4514  152.08  4769.9  147.67  4918.6  147.16    4954   144.7  4961.8  145.66
  4982.6  145.85    4997  147.24    5168  148.97  5324.7  153.42  5438.3  153.68
  5467.1  153.95  5473.5  154.75  5502.3  153.84    5531     154  5537.5   154.8
  5545.4  154.14  5551.8   154.9  5566.2  153.99  5572.6  154.68  5654.8  154.61
#Mann= 4 ,-1 , 0
  4004.4     .08       0  4918.6     .05       0    4997     .08       0
  5654.8     .08       0
Bank Sta=4918.6,4997
XS Rating Curve= 0 ,0
Exp/Cntr=0.3,0.1

Type RM Length L Ch R = 1 ,21204   ,649,649,649
BEGIN DESCRIPTION:
Mapping XS b93053e8
END DESCRIPTION:
XS GIS Cut Line= 3
      2291308.27     13299544.68      2290895.95     13299531.66
      2289772.23     13300390.72
#Sta/Elev= 30
  4108.8  156.12  4289.4  154.18  4558.9  152.33  4594.6  150.46  4631.5  151.68
  4758.4  148.47  4866.3   144.8  4930.7  143.84  4980.6  144.26  4986.9  140.34
  4995.1  135.92  5001.4  135.72  5009.4  133.41  5012.7  133.91    5016  135.27
  5022.6  142.48  5030.5  144.59    5045   144.2  5051.3  140.55  5059.5  144.01
  5101.2     145  5109.4  145.76  5194.6  149.05  5358.8  153.29  5414.9  153.82
    5473  153.54  5572.8  151.91  5664.6  152.91  5701.6  151.91  5935.8  155.13
#Mann= 4 ,-1 , 0
  4108.8     .05       0  4980.6     .03       0  5030.5     .05       0
  5935.8     .05       0
Bank Sta=4986.9,5022.6
XS Rating Curve= 0 ,0
Exp/Cntr=0.3,0.1

Type RM Length L Ch R = 1 ,20555   ,570,570,570
BEGIN DESCRIPTION:
Mapping XS 8dc153fa
END DESCRIPTION:
XS GIS Cut Line= 3
      2291517.52     13299191.38      2290746.65     13299217.43
      2289821.12     13299165.43
#Sta/Elev= 30
  3878.2  156.66  4268.2  154.46  4448.3  151.84  4578.4  148.84  4738.6  147.75
  4778.6  146.75  4808.7  147.15  4838.7   145.3  4888.8  144.31  4908.8  141.94
  4918.9  143.14  4925.5  139.68  4930.5  143.12  4958.9  143.83  4968.9  139.83
    4979  138.63  4998.7  133.43    5002  133.93    5009  136.99    5029  138.25
  5059.1  138.49  5079.1  141.92  5089.1  142.37  5129.2  141.73  5159.2  142.74
  5199.3  142.24  5284.1  146.17  5409.6  150.48  5499.8  152.66  5576.5  153.51
#Mann= 3 ,-1 , 0
  3878.2     .16       0  4998.7     .07       0    5009     .16       0
#XS Ineff= 2 ,-1
 4862.61 4943.41  143.77 5093.75 5232.84  142.37
Permanent Ineff=
       F       F
Bank Sta=4979,5029
XS Rating Curve= 0 ,0
Exp/Cntr=0.3,0.1

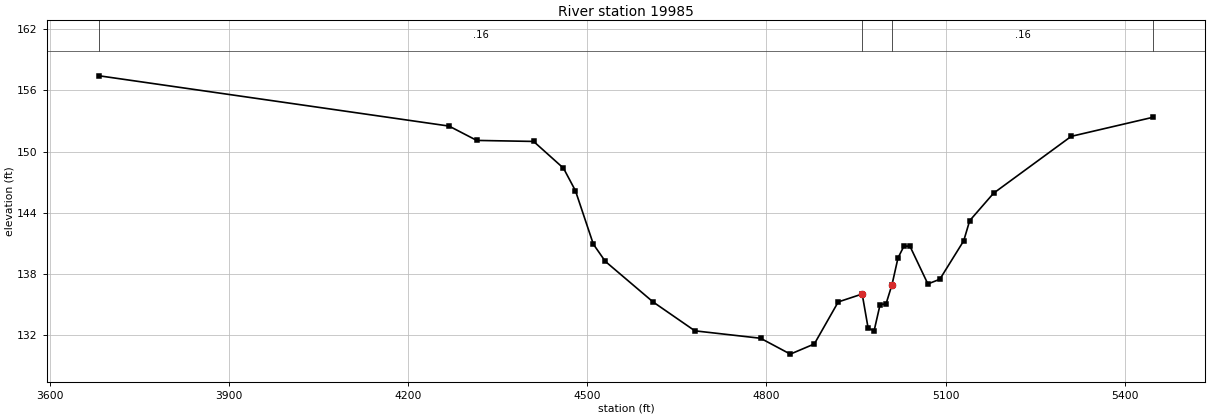
Type RM Length L Ch R = 1 ,19985   ,543,543,543
BEGIN DESCRIPTION:
Mapping XS 1fe39d54
END DESCRIPTION:
XS GIS Cut Line= 3
      2291658.06     13298920.53      2291064.35     13298654.93
      2289951.26     13298675.73
#Sta/Elev= 30
  3683.2  157.44  4268.7   152.5  4315.1  151.09  4410.3  150.99  4460.3  148.36
  4480.3  146.15  4510.3  140.89  4530.3   139.2  4610.3  135.21  4680.3  132.37
  4790.3  131.64  4840.1  130.08  4880.3  131.08  4920.3  135.21  4960.4  135.99
  4970.4  132.63  4980.4  132.38  4990.4  134.95  5000.4  135.03  5010.4  136.92
  5020.4  139.54  5030.4   140.7  5040.4  140.69  5070.4  136.98  5090.4  137.44
  5130.4  141.22  5140.4   143.2  5180.4   145.9  5310.4  151.49  5446.9  153.36
#Mann= 4 ,-1 , 0
  3683.2     .16       0  4960.4     .07       0  5010.4     .16       0
  5446.9     .05       0
Bank Sta=4960.4,5010.4
XS Rating Curve= 0 ,0
Exp/Cntr=0.3,0.1