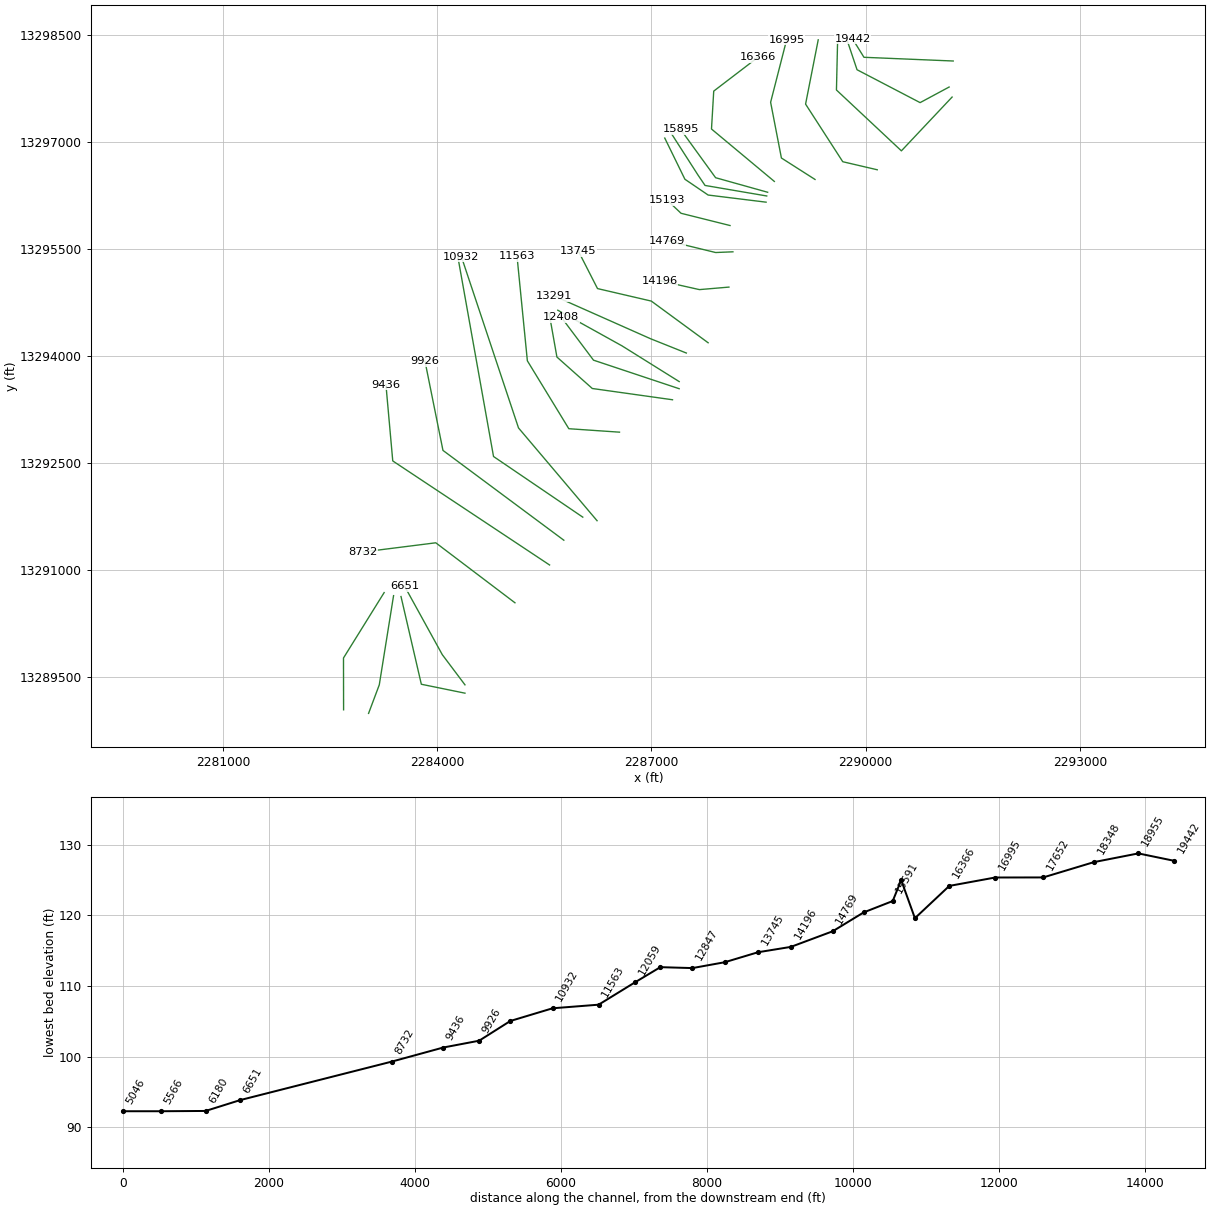
HEC-RAS study UNT018 IN NURI.prj: UNT018 IN NURI Base Level Engineering

--- UNT018 IN NURI.g01 (geometry) --- (continued)

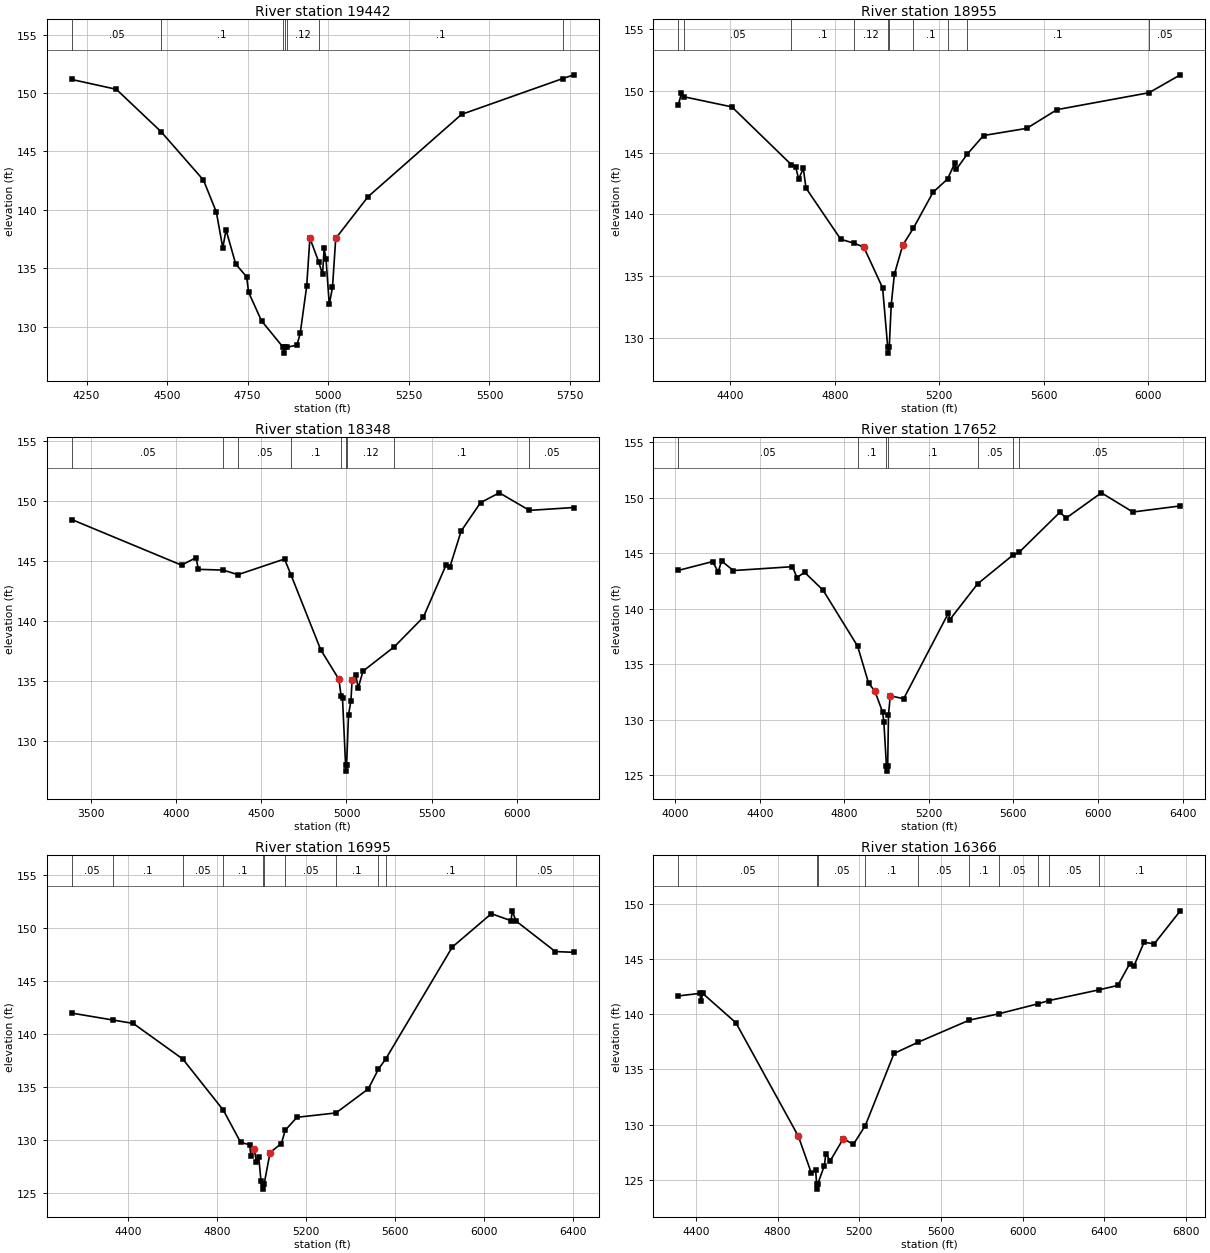
Type RM Length L Ch R = 1 ,19442   ,487,487,487
BEGIN DESCRIPTION:
Mapping XS d96e7ac8
END DESCRIPTION:
XS GIS Cut Line= 3
      2291225.82      13298139.3      2289975.81     13298191.39
      2289814.35     13298451.81
#Sta/Elev= 30
  4204.3  151.17  4342.5  150.33  4481.2   146.7  4612.8  142.55  4652.8  139.81
  4672.8  136.73  4682.8  138.29  4712.8  135.36  4746.9  134.25  4752.9  132.93
  4792.9  130.49    4860  128.22  4862.7  127.72    4866  128.22  4872.6  128.23
    4903  128.41    4913  129.42    4933  133.45    4943  137.57    4971  135.49
  4982.2  134.47  4987.2   136.7  4993.1  135.76  5003.1  131.89  5013.1  133.36
  5023.1  137.55  5123.2  141.12  5413.4  148.18  5727.4  151.25  5761.8  151.57
#Mann= 7 ,-1 , 0
  4204.3     .05       0  4481.2      .1       0    4860     .07       0
    4866      .1       0  4872.6     .12       0    4971      .1       0
  5727.4     .05       0
Bank Sta=4943,5023.1
XS Rating Curve= 0 ,0
Exp/Cntr=0.3,0.1

Type RM Length L Ch R = 1 ,18955   ,607,607,607
BEGIN DESCRIPTION:
UNT018 IN NURI 23.0
END DESCRIPTION:
XS GIS Cut Line= 4
      2291168.54     13297774.73      2290762.27     13297555.97
      2289878.84     13298016.97      2289731.02     13298457.01
#Sta/Elev= 30
  4200.4  148.87  4212.7  149.81  4222.2  149.54  4405.8  148.72  4632.7  144.05
  4649.7  143.86  4661.6  142.88  4679.2  143.73  4689.5  142.14  4822.5  137.99
  4875.1  137.66  4910.9  137.35  4982.8  134.05  5002.3  129.26  5005.1  128.76
  5008.3  129.26  5015.7  132.66  5027.9  135.16  5059.9  137.51  5100.1  138.87
  5175.9   141.8  5231.7  142.88  5258.6  144.14  5264.8  143.65  5306.1  144.87
  5369.1   146.4  5534.5  146.98  5650.6   148.5  6002.9  149.87  6122.5  151.32
#Mann= 10 ,-1 , 0
  4200.4      .1       0  4222.2     .05       0  4632.7      .1       0
  4875.1     .12       0  5002.3     .07       0  5008.3     .12       0
  5100.1      .1       0  5231.7     .16       0  5306.1      .1       0
  6002.9     .05       0
Bank Sta=4910.9,5059.9
XS Rating Curve= 0 ,0
Exp/Cntr=0.3,0.1

Type RM Length L Ch R = 1 ,18348   ,696,696,696
BEGIN DESCRIPTION:
UNT018 IN NURI 22.0
END DESCRIPTION:
XS GIS Cut Line= 4
      2291210.16     13297634.06      2290500.14     13296880.23
       2289590.4     13297733.05      2289605.99     13298393.23
#Sta/Elev= 30
  3389.7  148.44    4033  144.65    4118  145.27  4132.2   144.3  4275.8  144.24
  4364.2  143.86  4636.7  145.16  4676.1  143.79  4849.2  137.61  4955.2  135.17
  4968.4  133.78  4976.6  133.59  4994.7  128.03  4997.4  127.53  5000.7  128.03
  5011.8   132.2    5026  133.38  5032.8  135.11  5054.3  135.53  5068.5  134.44
  5096.8  135.84  5280.5  137.87  5450.5  140.32  5584.8   144.7  5606.3  144.51
  5672.2  147.49  5786.1  149.85  5896.1  150.66  6072.2   149.2  6332.6  149.44
#Mann= 9 ,-1 , 0
  3389.7     .05       0  4275.8      .1       0  4364.2     .05       0
  4676.1      .1       0  4968.4     .12       0  4994.7     .07       0
  5000.7     .12       0  5280.5      .1       0  6072.2     .05       0
Bank Sta=4955.2,5032.8
XS Rating Curve= 0 ,0
Exp/Cntr=0.3,0.1

Type RM Length L Ch R = 1 ,17652   ,657,657,657
BEGIN DESCRIPTION:
Mapping XS 170a7fdf
END DESCRIPTION:
XS GIS Cut Line= 4
      2290161.79     13296615.11      2289678.94     13296727.84
       2289158.1     13297535.14      2289335.18     13298436.14
#Sta/Elev= 30
  4014.6  143.46  4177.1  144.26  4203.6  143.33  4219.6  144.31  4275.5  143.45
  4554.9   143.8    4576  142.82  4612.3  143.29  4699.7  141.68    4863  136.63
  4914.6  133.32  4944.9  132.56  4981.2  130.69  4987.1  129.82  4999.3  125.86
  5002.1  125.36  5005.3  125.86  5009.1  130.43  5017.5  132.15  5080.9  131.89
  5292.7  139.62  5298.6  139.01  5430.6  142.25  5596.1  144.82  5626.2  145.08
  5819.4   148.7    5850  148.19  6015.9  150.46    6165  148.73  6389.4  149.28
#Mann= 7 ,-1 , 0
  4014.6     .05       0    4863      .1       0  4999.3     .07       0
  5005.3      .1       0  5430.6     .05       0  5596.1      .1       0
  5626.2     .05       0
Bank Sta=4944.9,5017.5
XS Rating Curve= 0 ,0
Exp/Cntr=0.3,0.1

Type RM Length L Ch R = 1 ,16995   ,629,629,629
BEGIN DESCRIPTION:
UNT018 IN NURI 21.0
END DESCRIPTION:
XS GIS Cut Line= 4
      2289290.52     13296479.26      2288819.56     13296779.93
      2288668.52     13297561.18      2288892.49     13298436.21
#Sta/Elev= 30
  4146.7  141.94  4331.3  141.29  4422.9  140.97    4646  137.61  4828.3  132.79
    4906  129.76  4946.8  129.53    4952  128.47  4967.1  129.12  4977.3  127.91
  4987.5  128.39  4997.7  126.07  5005.9  125.85  5008.7  125.35  5011.9  125.85
  5038.4   128.8  5089.4  129.65  5106.5   130.9  5159.3  132.12  5334.5  132.53
  5480.3   134.8  5524.8  136.63  5558.2  137.61    5858  148.17  6033.5  151.31
  6122.1  150.65  6127.3  151.58  6144.4  150.62    6321  147.74  6404.4  147.67
#Mann= 11 ,-1 , 0
  4146.7     .05       0  4331.3      .1       0    4646     .05       0
  4828.3      .1       0  5005.9     .07       0  5011.9      .1       0
  5106.5     .05       0  5334.5      .1       0  5524.8     .05       0
  5558.2      .1       0  6144.4     .05       0
Bank Sta=4967.1,5038.4
XS Rating Curve= 0 ,0
Exp/Cntr=0.3,0.1

Type RM Length L Ch R = 1 ,16366   ,471,471,471
BEGIN DESCRIPTION:
Mapping XS 251148e5
END DESCRIPTION:
XS GIS Cut Line= 4
      2288720.62     13296451.79       2287840.4     13297186.18
      2287871.65     13297717.43      2288491.46     13298191.41
#Sta/Elev= 30
    4313  141.66  4418.4  141.89  4424.9  141.22  4432.7  141.89  4595.4  139.23
  4901.3  128.95  4965.1   125.6  4985.9  125.86  4990.7  124.66  4993.5  124.16
  4996.7  124.66  5028.9   126.3  5035.4  127.36  5057.5  126.73  5121.3  128.73
  5170.7  128.21  5229.2  129.92  5369.9  136.45  5489.3  137.48  5738.6  139.47
  5882.3  140.04  6073.3  140.94  6128.2  141.24  6372.8  142.21  6465.5  142.61
  6523.6  144.56  6544.4  144.36  6594.3  146.52  6644.2  146.38  6771.8  149.37
#Mann= 10 ,-1 , 0
    4313     .05       0  4990.7     .03       0  4996.7     .05       0
  5229.2      .1       0  5489.3     .05       0  5738.6      .1       0
  5882.3     .05       0  6073.3      .1       0  6128.2     .05       0
  6372.8      .1       0
Bank Sta=4901.3,5121.3
XS Rating Curve= 0 ,0
Exp/Cntr=0.3,0.1

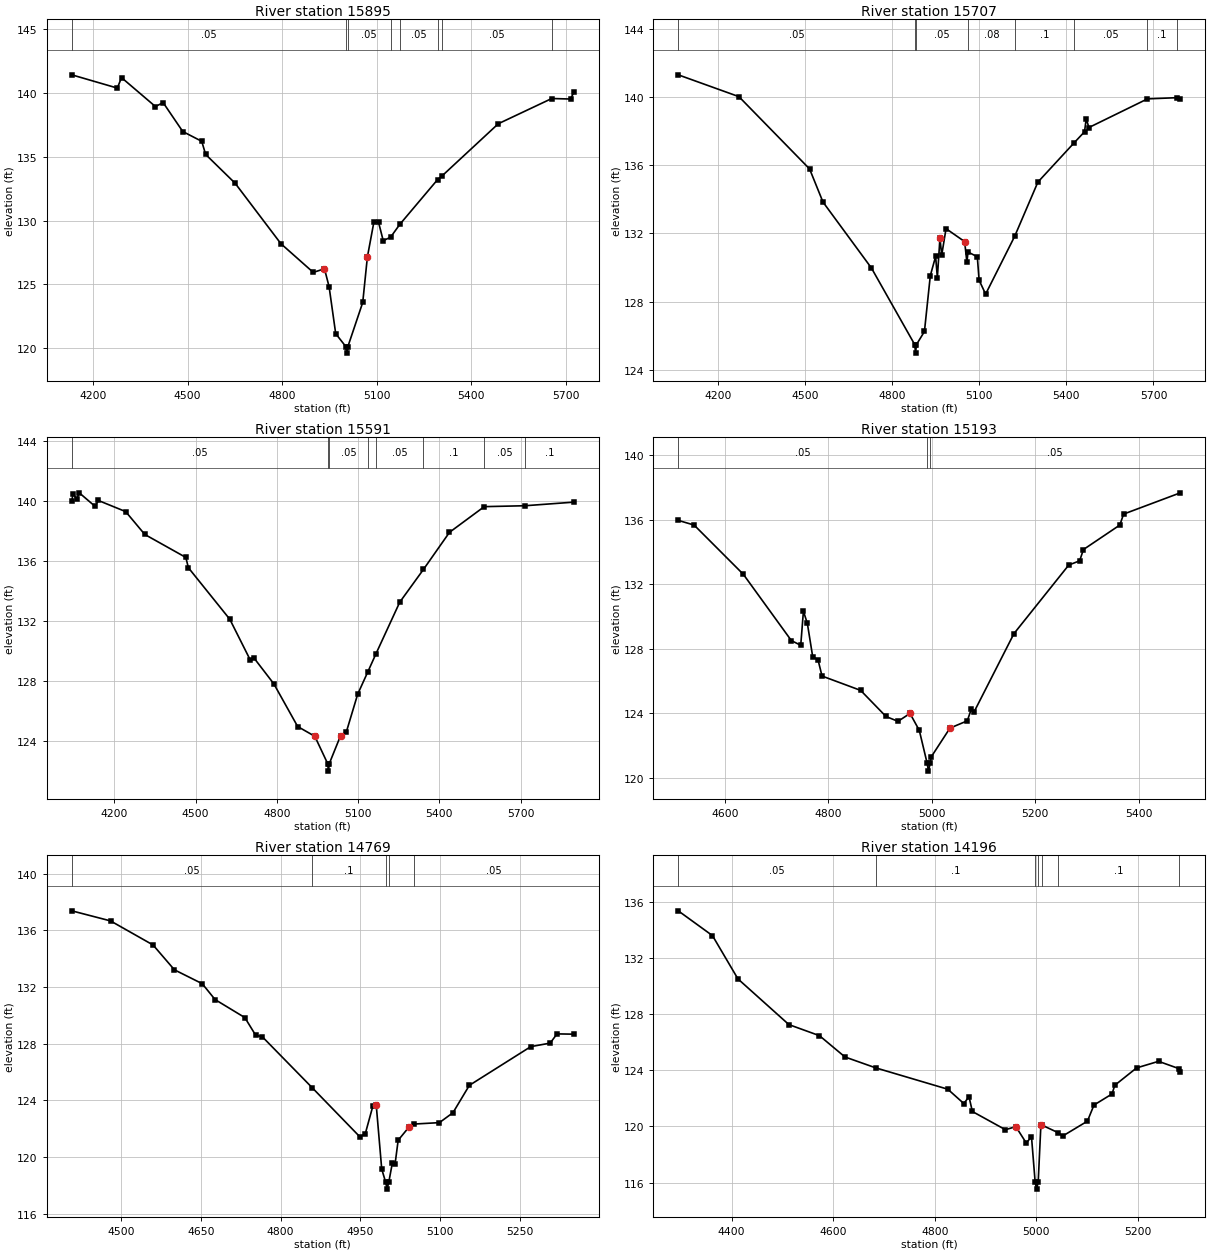
Type RM Length L Ch R = 1 ,15895   ,188,188,188
BEGIN DESCRIPTION:
Mapping XS deff1497
END DESCRIPTION:
XS GIS Cut Line= 3
      2288626.85     13296299.89      2287897.69     13296503.89
      2287407.25     13297180.96
#Sta/Elev= 30
  4132.7  141.44  4277.2   140.4  4290.6  141.22  4398.2  138.95  4422.6  139.26
  4484.9  136.99  4545.1  136.22  4557.5  135.19    4651  132.93  4796.4  128.18
    4899  125.93  4934.6  126.21  4949.3   124.8  4970.2  121.12  5002.7  120.09
  5005.5  119.59  5008.7  120.09    5056  123.57  5070.7  127.13  5091.6  129.91
  5106.3  129.85    5121  128.42  5144.3  128.69    5174  129.71  5293.4  133.21
  5307.1  133.49  5486.2   137.6  5655.8  139.58  5715.6  139.54  5725.9  140.08
#Mann= 8 ,-1 , 0
  4132.7     .05       0  5002.7     .03       0  5008.7     .05       0
  5144.3     .08       0    5174     .05       0  5293.4      .1       0
  5307.1     .05       0  5655.8      .1       0
Bank Sta=4934.6,5070.7
XS Rating Curve= 0 ,0
Exp/Cntr=0.3,0.1

Type RM Length L Ch R = 1 ,15707   ,116,116,116
BEGIN DESCRIPTION:
UNT018 IN NURI 20.0
END DESCRIPTION:
XS GIS Cut Line= 4
      2288613.86      13296247.8      2287750.12     13296395.38
      2287654.39     13296536.56      2287285.68     13297111.56
#Sta/Elev= 30
  4062.5   141.3  4271.6  140.02  4515.1  135.78  4561.2  133.84  4728.2  129.97
  4877.3  125.48  4880.1  124.98  4883.3  125.48  4910.8  126.25    4931  129.52
  4949.3  130.65  4955.3  129.41  4964.2  131.72  4970.3  130.73  4985.2  132.28
  5049.3  131.52  5057.1   130.3  5060.9  130.91    5093  130.63  5099.1  129.26
  5121.6  128.44  5221.7  131.83  5301.7  135.01  5426.9  137.32  5462.3  137.96
  5468.2  138.72  5477.5  138.21  5679.3  139.89  5780.8  139.96  5792.4   139.9
#Mann= 8 ,-1 , 0
  4062.5     .05       0  4877.3     .03       0  4883.3     .05       0
  5060.9     .08       0  5221.7      .1       0  5426.9     .05       0
  5679.3      .1       0  5780.8     .05       0
#XS Ineff= 2 ,-1
  4639.2 4963.41  131.16 5050.34 5218.07  131.28
Permanent Ineff=
       F       F
Bank Sta=4964.2,5049.3
XS Rating Curve= 0 ,0
Exp/Cntr=0.3,0.1

Type RM Length L Ch R = 1 ,15591   ,398,398,398
BEGIN DESCRIPTION:
Mapping XS 68822570
END DESCRIPTION:
XS GIS Cut Line= 4
      2288605.19       13296161.      2287793.52     13296260.83
        2287468.     13296482.18       2287185.9      13297059.4
#Sta/Elev= 30
  4042.9  140.01  4047.7   140.5  4060.5  140.12  4070.6  140.55  4128.9  139.65
  4141.1  140.04  4241.9   139.3  4312.4  137.78    4464  136.25  4473.6  135.56
  4626.5  132.13  4702.8  129.39  4715.4  129.56  4789.1  127.83    4877  124.99
  4940.3  124.34  4987.8  122.52  4990.6  122.02  4993.8  122.52  5035.7  124.39
  5056.6  124.62  5098.6  127.14  5136.3  128.64  5165.3   129.8    5254  133.27
  5341.5  135.45  5437.6  137.92    5566  139.63  5716.3  139.69  5896.8  139.93
#Mann= 8 ,-1 , 0
  4042.9     .05       0  4987.8     .03       0  4993.8     .05       0
  5136.3     .08       0  5165.3     .05       0  5341.5      .1       0
    5566     .05       0  5716.3      .1       0
Bank Sta=4940.3,5035.7
XS Rating Curve= 0 ,0
Exp/Cntr=0.3,0.1

Type RM Length L Ch R = 1 ,15193   ,424,424,424
BEGIN DESCRIPTION:
UNT018 IN NURI 19.0
END DESCRIPTION:
XS GIS Cut Line= 3
        2288100.     13295833.76      2287413.75     13296005.32
      2287222.37     13296186.63
#Sta/Elev= 30
  4509.5  135.97  4540.2  135.68  4635.5  132.62  4728.3  128.51  4746.4  128.22
  4751.6  130.33  4759.2  129.58  4769.5  127.52  4779.9  127.31  4787.6  126.31
  4862.3  125.42  4911.3   123.8  4934.5   123.5  4957.7  123.99  4975.7  122.94
  4990.8  120.91  4993.5  120.41  4996.8  120.91  4998.9   121.3    5035  123.08
  5068.5  123.53  5076.3  124.26  5081.4  124.07  5158.7  128.94  5264.8   133.2
  5285.8  133.46  5293.1  134.16  5363.5  135.68  5370.8  136.36  5480.5  137.68
#Mann= 3 ,-1 , 0
  4509.5     .05       0  4990.8     .03       0  4996.8     .05       0
Bank Sta=4957.7,5035
XS Rating Curve= 0 ,0
Exp/Cntr=0.3,0.1

Type RM Length L Ch R = 1 ,14769   ,573,573,573
BEGIN DESCRIPTION:
UNT018 IN NURI 18.0
END DESCRIPTION:
XS GIS Cut Line= 3
      2288140.41     13295465.38      2287898.19     13295455.29
      2287216.98      13295621.8
#Sta/Elev= 30
  4407.4  137.37  4480.2  136.66  4560.2  134.96  4600.3  133.21  4652.6  132.23
  4676.8  131.11  4732.7  129.84  4753.3  128.58  4765.2   128.5  4859.4  124.89
  4948.9  121.43  4959.1  121.65  4973.4  123.61  4979.7  123.66    4990  119.15
  4997.3  118.24  5000.1  117.74  5003.3  118.24  5009.9  119.57  5015.1  119.52
  5020.9  121.19  5041.5  122.13  5050.7  122.33  5098.4  122.43  5123.9  123.13
  5154.7  125.06  5270.1  127.79  5306.6  128.04  5319.5  128.69  5351.1  128.67
#Mann= 5 ,-1 , 0
  4407.4     .05       0  4859.4      .1       0  4997.3     .07       0
  5003.3      .1       0  5050.7     .05       0
Bank Sta=4979.7,5041.5
XS Rating Curve= 0 ,0
Exp/Cntr=0.3,0.1

Type RM Length L Ch R = 1 ,14196   ,451,451,451
BEGIN DESCRIPTION:
UNT018 IN NURI 17.0
END DESCRIPTION:
XS GIS Cut Line= 3
      2288084.86     13294970.85      2287671.11     13294935.53
      2287111.87     13295061.48
#Sta/Elev= 30
  4294.8  135.39  4362.2  133.62  4412.4  130.53  4512.7  127.27  4572.9  126.48
  4623.1  124.96  4683.9  124.18  4825.5  122.66    4857  121.64  4867.3  122.12
  4873.9  121.07    4939  119.77  4959.5  119.99    4980  118.82  4990.3  119.27
  4997.5  116.03  5000.3  115.53  5003.5  116.03  5008.8  120.11  5010.2  120.11
  5043.2  119.55  5051.8  119.32  5100.4  120.38  5113.3  121.53  5148.8  122.32
  5154.3  122.94  5197.2  124.18  5240.5  124.65  5280.5  124.13  5283.3  123.87
#Mann= 7 ,-1 , 0
  4294.8     .05       0  4683.9      .1       0  4997.5     .07       0
  5003.5      .1       0  5010.2     .16       0  5043.2      .1       0
  5280.5     .05       0
Bank Sta=4959.5,5008.8
XS Rating Curve= 0 ,0
Exp/Cntr=0.3,0.1

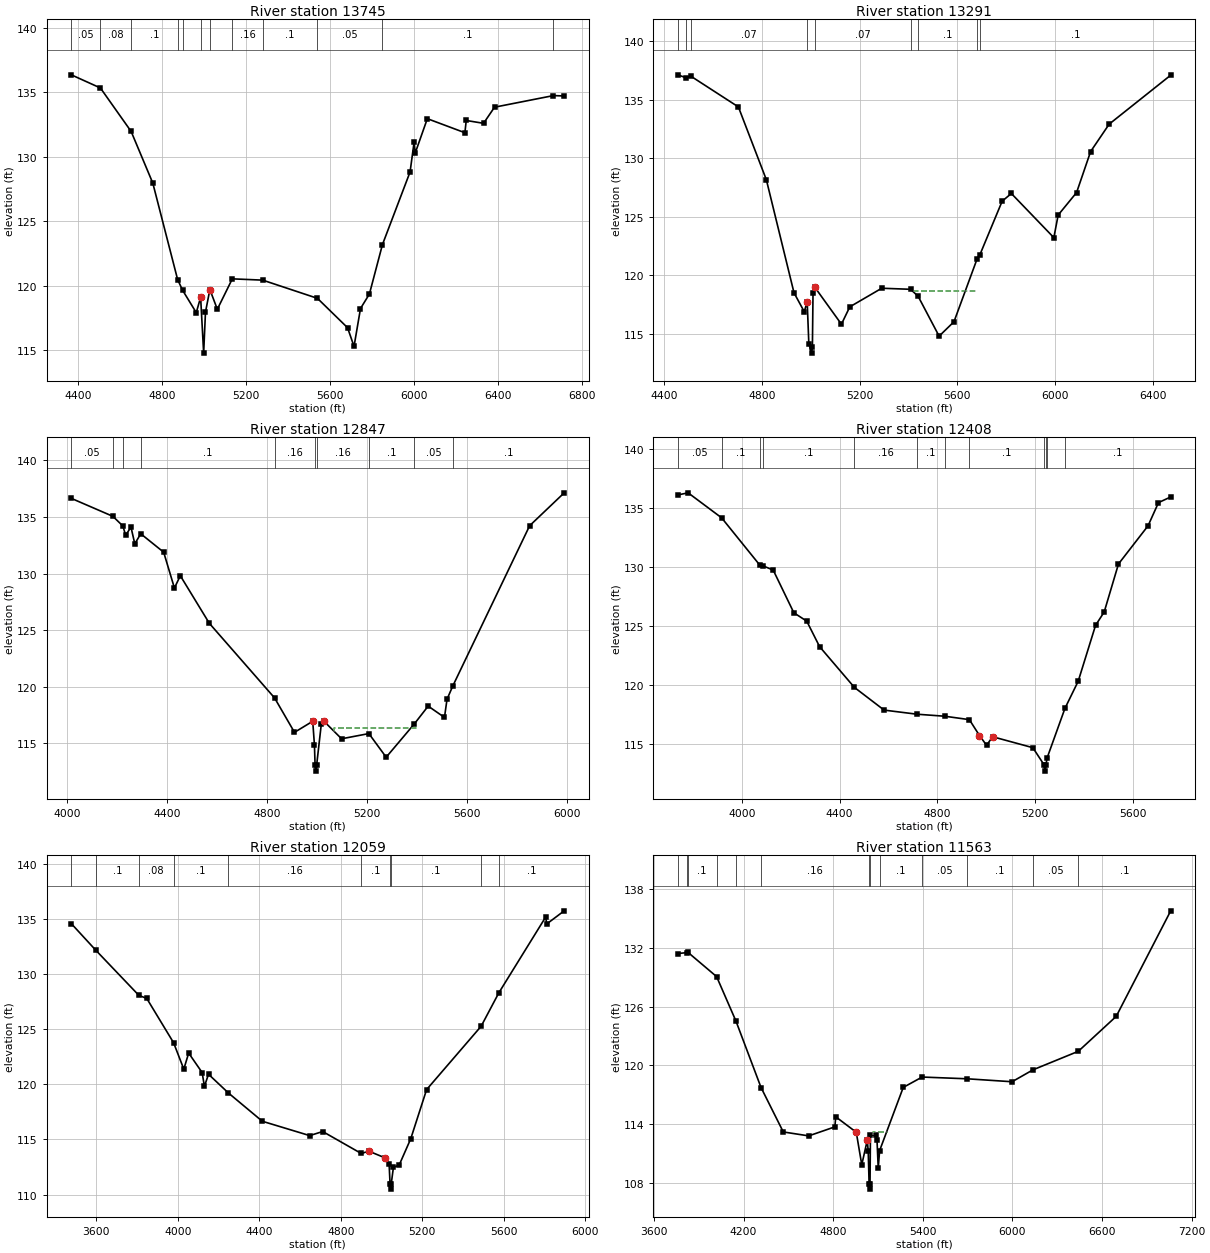
Type RM Length L Ch R = 1 ,13745   ,454,454,454
BEGIN DESCRIPTION:
UNT018 IN NURI 16.0
END DESCRIPTION:
XS GIS Cut Line= 4
       2287793.5     13294190.53      2286997.43     13294774.75
      2286244.04     13294950.07      2285977.16     13295472.37
#Sta/Elev= 30
  4368.9  136.35  4507.5  135.33  4653.8  131.96  4757.1  127.95  4875.3  120.47
  4899.1  119.64    4964  117.91  4984.8   119.1  4999.2  114.77  5007.9  117.95
  5028.8   119.7  5064.3  118.17  5135.7  120.53  5280.4  120.43    5541  119.02
  5684.6  116.74  5715.4  115.29  5746.2  118.23  5788.6  119.35  5850.6  123.18
  5982.3  128.82  6001.6  131.14  6006.7  130.28  6064.5  132.95  6243.4  131.86
  6249.8  132.81  6332.3  132.59  6384.5  133.84  6665.1  134.74  6716.4  134.71
#Mann= 12 ,-1 , 0
  4368.9     .05       0  4507.5     .08       0  4653.8      .1       0
  4875.3     .16       0  4899.1     .07       0  4984.8    .035       0
  5028.8     .07       0  5135.7     .16       0  5280.4      .1       0
    5541     .05       0  5850.6      .1       0  6665.1     .05       0
#XS Ineff= 1 ,-1
  5361.8 5884.46 119.684
Permanent Ineff=
       F
Bank Sta=4984.8,5028.8
XS Rating Curve= 0 ,0
Exp/Cntr=0.3,0.1

Type RM Length L Ch R = 1 ,13291   ,444,444,444
BEGIN DESCRIPTION:
UNT018 IN NURI 15.0
END DESCRIPTION:
XS GIS Cut Line= 3
      2287487.71     13294046.86      2286987.72     13294246.85
      2285637.75     13294846.84
#Sta/Elev= 30
  4456.5  137.12    4491  136.86  4509.4  137.01  4704.2  134.38  4818.6  128.16
  4931.7  118.51  4973.5   116.9  4985.6  117.73  4992.3  114.18  5003.6  113.36
  5006.9  113.86  5009.4  118.46  5016.9  118.98  5125.6  115.83  5159.8  117.31
  5290.5   118.9  5408.2  118.81  5439.1  118.22  5525.1  114.81  5585.9  116.04
  5680.2  121.39  5691.9  121.76  5782.9  126.33  5820.5  126.99  5994.3  123.22
    6012  125.15  6087.3  127.07  6144.7  130.57  6220.6  132.91  6472.3  137.09
#Mann= 9 ,-1 , 0
  4456.5     .05       0    4491     .08       0  4509.4     .07       0
  4985.6    .035       0  5016.9     .07       0  5408.2     .16       0
  5439.1      .1       0  5680.2     .05       0  5691.9      .1       0
#XS Ineff= 1 ,-1
 5421.88 5681.64  118.63
Permanent Ineff=
       F
Bank Sta=4985.6,5016.9
XS Rating Curve= 0 ,0
Exp/Cntr=0.3,0.1

Type RM Length L Ch R = 1 ,12847   ,439,439,439
BEGIN DESCRIPTION:
UNT018 IN NURI 14.0
END DESCRIPTION:
XS GIS Cut Line= 3
      2287387.71     13293646.86      2286587.72     13294146.85
      2285687.76     13294646.83
#Sta/Elev= 30
    4016  136.65  4182.5  135.06  4222.3  134.21  4233.6  133.39  4254.8  134.11
  4270.1  132.63  4293.9  133.52  4385.7  131.89  4428.7  128.72  4452.3  129.81
  4568.5   125.6  4829.7     119  4909.3  115.96  4982.3  116.94  4989.1  114.86
  4991.8  113.03  4994.6  112.53  4997.8  113.03  5016.6  116.68  5026.9  116.95
  5097.8  115.39    5207  115.85  5276.3  113.76  5389.1  116.71  5444.4  118.28
  5509.6  117.28  5519.9  118.89  5543.4  120.08  5850.5  134.23  5988.9  137.14
#Mann= 10 ,-1 , 0
    4016     .05       0  4182.5      .1       0  4222.3     .08       0
  4293.9      .1       0  4829.7     .16       0  4991.8     .07       0
  4997.8     .16       0    5207      .1       0  5389.1     .05       0
  5543.4      .1       0
#XS Ineff= 1 ,-1
 5068.75 5401.56  116.35
Permanent Ineff=
       F
Bank Sta=4982.3,5026.9
XS Rating Curve= 0 ,0
Exp/Cntr=0.3,0.1

Type RM Length L Ch R = 1 ,12408   ,349,349,349
BEGIN DESCRIPTION:
UNT018 IN NURI 13.0
END DESCRIPTION:
XS GIS Cut Line= 3
      2287387.67     13293546.87      2286187.72     13293946.85
       2285737.7     13294546.89
#Sta/Elev= 30
  3738.6   136.1  3780.7  136.28  3917.6  134.16  4074.7  130.12  4086.2  130.09
  4128.6  129.72  4212.9   126.1  4265.6  125.39  4318.3  123.22  4460.2  119.77
  4581.8  117.84  4716.5  117.49  4829.6  117.32  4930.4  117.03  4971.8  115.68
  5000.8  114.85  5025.3  115.58  5189.9  114.65  5236.9  113.16  5239.7  112.66
  5242.9  113.16  5248.6   113.8  5321.2  117.99  5375.3  120.29  5446.2  125.03
  5481.6  126.17  5539.9  130.24  5660.8  133.48  5703.5  135.45  5753.5  135.93
#Mann= 12 ,-1 , 0
  3738.6     .05       0  3917.6      .1       0  4074.7     .08       0
  4086.2      .1       0  4460.2     .16       0  4716.5      .1       0
  4829.6     .16       0  4930.4      .1       0  5236.9     .07       0
  5242.9      .1       0  5248.6     .05       0  5321.2      .1       0
#XS Ineff= 1 ,-1
 5117.19 5314.45  115.04
Permanent Ineff=
       F
Bank Sta=4971.8,5025.3
XS Rating Curve= 0 ,0
Exp/Cntr=0.3,0.1

Type RM Length L Ch R = 1 ,12059   ,496,496,496
BEGIN DESCRIPTION:
UNT018 IN NURI 12.0
END DESCRIPTION:
XS GIS Cut Line= 4
      2287294.43      13293391.9      2286170.96     13293549.78
      2285675.47     13293990.87      2285567.05     13294602.34
#Sta/Elev= 30
  3477.9  134.56    3598  132.15  3809.4  128.06  3848.2  127.78    3980  123.76
    4030  121.37  4053.8  122.83  4120.1  121.06    4131  119.81  4151.2  120.91
  4249.1  119.21  4415.3  116.65  4647.9  115.35  4711.5  115.72  4900.9  113.73
  4938.1  113.94  5016.7  113.34  5037.6  112.74  5042.1     111  5044.8   110.5
  5048.1     111  5058.6  112.47  5086.9  112.68  5143.8  115.07  5221.5  119.52
  5489.1  125.26  5576.3   128.3    5806  135.16    5811  134.53  5896.8  135.72
#Mann= 10 ,-1 , 0
  3477.9     .05       0    3598      .1       0  3809.4     .08       0
    3980      .1       0  4249.1     .16       0  4900.9      .1       0
  5042.1     .07       0  5048.1      .1       0  5489.1     .05       0
  5576.3      .1       0
Bank Sta=4938.1,5016.7
XS Rating Curve= 0 ,0
Exp/Cntr=0.3,0.1

Type RM Length L Ch R = 1 ,11563   ,631,631,631
BEGIN DESCRIPTION:
UNT018 IN NURI 11.0
END DESCRIPTION:
XS GIS Cut Line= 4
      2286551.98     13292937.71      2285842.32     13292986.09
      2285261.69     13293937.67      2285116.71     13295403.57
#Sta/Elev= 30
  3760.3  131.42  3822.6  131.51  3827.2  131.55  4019.9  129.06  4149.6  124.51
  4317.3  117.73  4466.2  113.19  4636.5  112.79  4811.4  113.71  4817.3  114.74
  4954.7  113.16  4991.5  109.84  5028.3  112.34  5034.8  111.21  5040.7  107.85
  5043.5  107.35  5046.7  107.85  5049.6  112.87  5086.4  112.84  5093.4  112.38
  5101.8  109.49  5110.9  111.28  5269.1  117.74  5395.5   118.8  5698.6  118.62
  5997.5  118.32  6137.9  119.54  6440.9  121.43  6694.7     125  7059.4  135.78
#Mann= 13 ,-1 , 0
  3760.3      .1       0  3822.6     .05       0  3827.2      .1       0
  4019.9     .16       0  4149.6      .1       0  4317.3     .16       0
  5040.7     .07       0  5046.7     .16       0  5110.9      .1       0
  5395.5     .05       0  5698.6      .1       0  6137.9     .05       0
  6440.9      .1       0
#XS Ineff= 2 ,-1
 5026.69 5055.28  112.22 5064.81  5164.3  113.22
Permanent Ineff=
       F       F
Bank Sta=4954.7,5028.3
XS Rating Curve= 0 ,0
Exp/Cntr=0.3,0.1

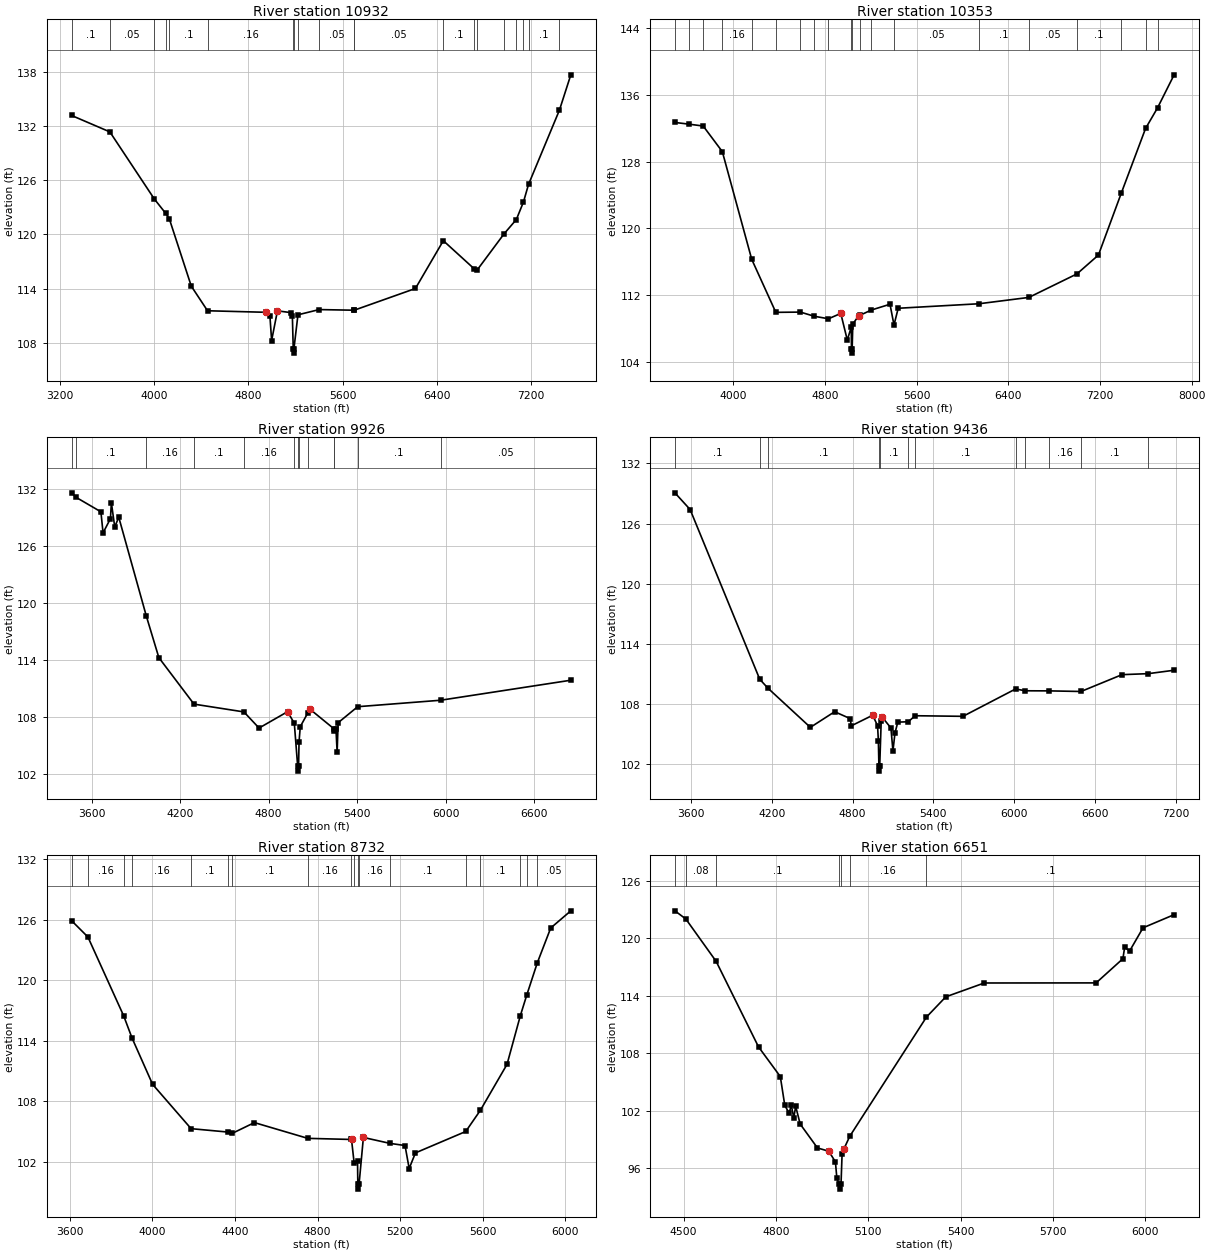
Type RM Length L Ch R = 1 ,10932   ,579,579,579
BEGIN DESCRIPTION:
UNT018 IN NURI 10.0
END DESCRIPTION:
XS GIS Cut Line= 3
       2286237.7     13291696.88      2285137.72     13292996.85
      2284337.73     13295396.83
#Sta/Elev= 30
  3302.3   133.2  3626.5  131.38  4003.9  123.93    4099  122.36  4130.1  121.76
  4316.9  114.27  4454.7  111.54  4948.6  111.37  4983.8  110.93  4998.1  108.24
  5047.4  111.53  5163.3  111.33  5173.9  110.99  5181.4  107.34  5184.2  106.84
  5187.4  107.34  5221.4  111.09    5401  111.67  5697.6   111.6  5698.2   111.6
  6217.4  114.01    6454  119.31  6715.1   116.2  6742.6  116.09  6970.1  120.09
  7073.2  121.66  7133.4   123.6  7176.3  125.55  7438.7   133.8    7535  137.71
#Mann= 20 ,-1 , 0
  3302.3      .1       0  3626.5     .05       0  4003.9      .1       0
    4099     .05       0  4130.1      .1       0  4454.7     .16       0
  5181.4     .07       0  5187.4     .16       0  5221.4      .1       0
    5401     .05       0  5697.6      .1       0  5698.2     .05       0
    6454      .1       0  6715.1     .05       0  6742.6      .1       0
  6970.1     .05       0  7073.2      .1       0  7133.4     .05       0
  7176.3      .1       0  7438.7     .05       0
Bank Sta=4948.6,5047.4
XS Rating Curve= 0 ,0
Exp/Cntr=0.3,0.1

Type RM Length L Ch R = 1 ,10353   ,427,427,427
BEGIN DESCRIPTION:
UNT018 IN NURI 9.0
END DESCRIPTION:
XS GIS Cut Line= 3
      2286037.73     13291746.85      2284787.72     13292596.85
      2284287.72     13295396.83
#Sta/Elev= 30
  3490.9   132.7  3616.5  132.49  3737.7  132.27  3904.6   129.2  4161.1  116.29
  4371.4  109.93    4586  109.96  4707.1  109.46  4830.8  109.16  4938.2   109.8
  4995.1  106.61  5029.5  108.15  5031.5  105.54  5034.3  105.04  5037.5  105.54
  5043.2  108.53    5094  109.52  5103.3  109.56  5203.1   110.2  5367.7   110.9
  5402.6  108.41  5439.3  110.42    6144  110.96  6579.5  111.72  6999.1  114.54
  7186.5   116.8  7386.4  124.24  7597.8  131.98    7702  134.44  7846.8  138.41
#Mann= 20 ,-1 , 0
  3490.9      .1       0  3616.5     .05       0  3737.7      .1       0
  3904.6     .16       0  4161.1      .1       0  4371.4     .16       0
    4586      .1       0  4707.1     .16       0  4830.8      .1       0
  5031.5     .07       0  5037.5     .16       0  5103.3     .05       0
  5203.1     .16       0  5402.6     .05       0    6144      .1       0
  6579.5     .05       0  6999.1      .1       0  7386.4     .05       0
  7597.8      .1       0    7702     .05       0
Bank Sta=4938.2,5094
XS Rating Curve= 0 ,0
Exp/Cntr=0.3,0.1

Type RM Length L Ch R = 1 ,9926    ,490,490,490
BEGIN DESCRIPTION:
UNT018 IN NURI 8.0
END DESCRIPTION:
XS GIS Cut Line= 3
      2285772.27     13291423.58      2284079.55     13292682.27
      2283827.85     13293932.06
#Sta/Elev= 30
    3465  131.58  3494.6  131.11  3663.5  129.58  3678.1  127.36  3728.2  128.86
  3734.4  130.54  3757.3  127.98  3784.5  129.01  3972.2  118.55  4056.4  114.21
  4294.7  109.31  4633.1  108.49  4735.7  106.79  4928.7  108.51  4974.7   107.3
  4997.6  102.75  5000.3  102.25  5003.6  102.75  5006.8  105.34  5015.2  106.94
  5066.5  108.39  5078.2  108.81  5245.2  106.69  5246.1  106.52  5257.1  106.69
  5265.1  104.25  5271.7  107.35  5404.4  109.04  5966.1  109.72  6849.3  111.83
#Mann= 13 ,-1 , 0
    3465     .08       0  3494.6      .1       0  3972.2     .16       0
  4294.7      .1       0  4633.1     .16       0  4974.7      .1       0
  4997.6     .07       0  5003.6      .1       0  5066.5     .16       0
  5245.2      .1       0  5246.1     .16       0  5404.4      .1       0
  5966.1     .05       0
Bank Sta=4928.7,5078.2
XS Rating Curve= 0 ,0
Exp/Cntr=0.3,0.1

Type RM Length L Ch R = 1 ,9436    ,704,704,704
BEGIN DESCRIPTION:
UNT018 IN NURI 7.0
END DESCRIPTION:
XS GIS Cut Line= 3
       2285572.6     13291076.37      2283376.42      13292534.7
      2283280.96     13293602.17
#Sta/Elev= 30
  3480.7  129.07  3593.8   127.4  4110.8  110.46  4172.4  109.56  4486.9  105.66
  4667.3  107.22    4783  106.53  4790.6  105.81    4950  106.87    4986  105.82
    4992  104.32    4996  101.79  4998.8  101.29    5002  101.79  5013.1  106.32
  5022.1  106.65  5085.2   105.6  5100.3  103.31  5115.3  105.09  5136.4  106.18
  5214.4  106.22  5264.9  106.82  5620.5  106.76  6011.1  109.49  6083.8  109.31
  6262.2   109.3  6497.3  109.24  6801.8  110.92  6996.7  111.02  7188.7  111.36
#Mann= 12 ,-1 , 0
  3480.7      .1       0  4110.8     .16       0  4172.4      .1       0
    4996     .07       0    5002      .1       0  5214.4     .16       0
  5264.9      .1       0  6011.1     .16       0  6083.8      .1       0
  6262.2     .16       0  6497.3      .1       0  6996.7     .05       0
Bank Sta=4950,5022.1
XS Rating Curve= 0 ,0
Exp/Cntr=0.3,0.1

Type RM Length L Ch R = 1 ,8732    ,2081,2081,2081
BEGIN DESCRIPTION:
UNT018 IN NURI 6.0
END DESCRIPTION:
XS GIS Cut Line= 3
      2285087.72     13290546.85      2283979.13     13291387.37
      2282961.22     13291258.84
#Sta/Elev= 30
  3608.8  125.89  3687.6  124.28    3861  116.46  3901.3  114.27  4000.9  109.68
  4187.3  105.29  4367.5  104.95    4386  104.82  4493.9  105.89  4752.3  104.33
    4963  104.22  4964.1  104.22  4976.6  101.93  4993.2  102.07  4994.7    99.8
  4997.5    99.3  5000.7    99.8  5021.6  104.42  5150.8  103.83  5223.2  103.62
  5243.3  101.34  5273.6  102.89  5517.2  105.01  5588.1  107.11  5717.1  111.66
  5781.7  116.49  5812.9  118.54  5863.6  121.71  5928.7  125.17    6026  126.87
#Mann= 18 ,-1 , 0
  3608.8      .1       0  3687.6     .16       0    3861      .1       0
  3901.3     .16       0  4187.3      .1       0  4367.5     .16       0
    4386      .1       0  4752.3     .16       0    4963      .1       0
  4976.6     .16       0  4994.7     .07       0  5000.7     .16       0
  5150.8      .1       0  5517.2     .16       0  5588.1      .1       0
  5781.7     .16       0  5812.9      .1       0  5863.6     .05       0
Bank Sta=4964.1,5021.6
XS Rating Curve= 0 ,0
Exp/Cntr=0.3,0.1

Type RM Length L Ch R = 1 ,6651    ,471,471,471
BEGIN DESCRIPTION:
UNT018 IN NURI 5.0
END DESCRIPTION:
XS GIS Cut Line= 3
       2284387.7     13289396.88       2284070.3     13289819.46
      2283542.68     13290777.93
#Sta/Elev= 30
  4471.5  122.84    4507  121.99  4605.6  117.57  4743.3  108.66  4814.1  105.57
  4828.7  102.56  4843.3  101.73  4849.5  102.65  4857.8  101.27  4864.1  102.46
  4878.7  100.62  4934.9   98.13  4971.7   97.79  4993.2   96.68    4998   94.95
  5005.4   94.34  5008.2   93.84  5011.4   94.34  5014.9    97.5  5020.6   98.01
  5039.7   99.34  5289.2  111.77  5352.1  113.88    5477  115.32  5840.6  115.33
  5927.7  117.85  5933.4  119.04  5949.5  118.65  5993.1  121.07  6094.1  122.44
#Mann= 7 ,-1 , 0
  4471.5      .1       0    4507     .08       0  4605.6      .1       0
  5005.4     .07       0  5011.4      .1       0  5039.7     .16       0
  5289.2      .1       0
Bank Sta=4971.7,5020.6
XS Rating Curve= 0 ,0
Exp/Cntr=0.3,0.1

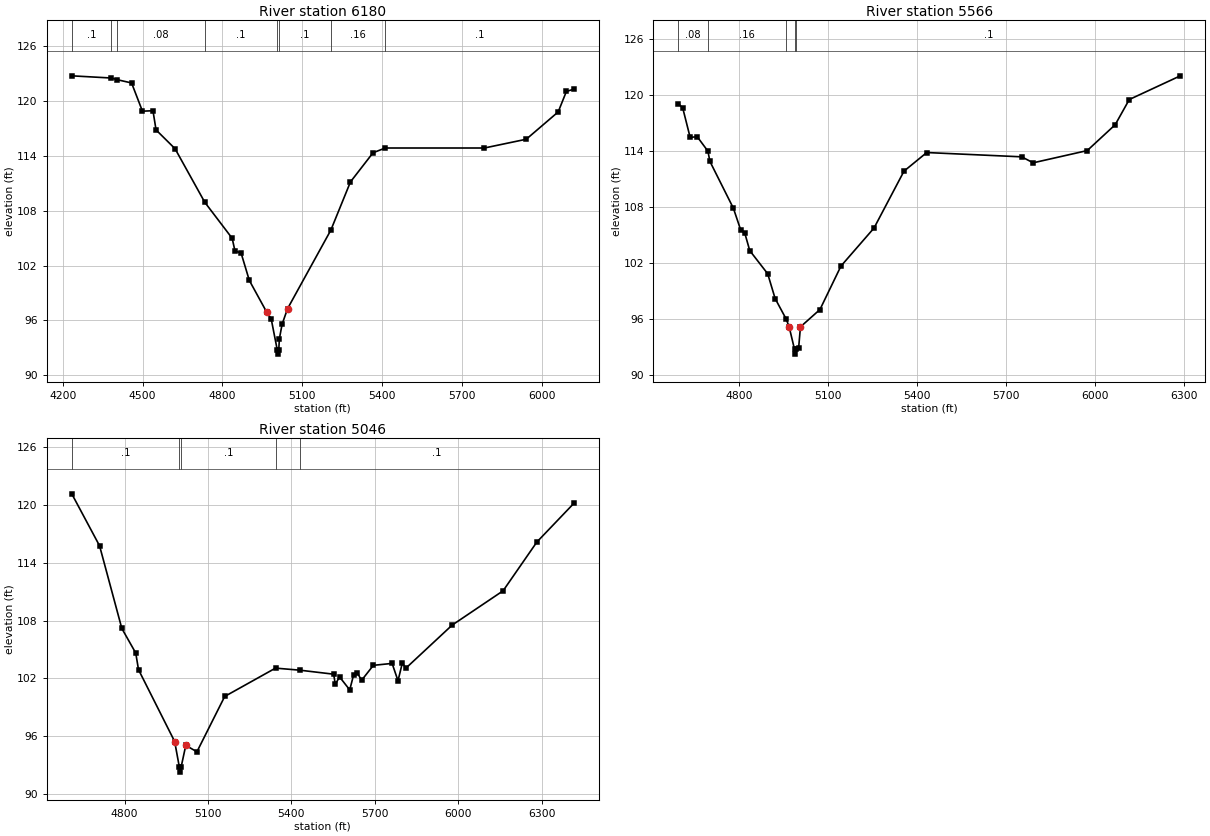
Type RM Length L Ch R = 1 ,6180    ,614,614,614
BEGIN DESCRIPTION:
UNT018 IN NURI 4.0
END DESCRIPTION:
XS GIS Cut Line= 3
      2284387.78       13289280.      2283776.69       13289405.
      2283491.98     13290634.12
#Sta/Elev= 30
  4234.3  122.77  4382.8  122.53  4404.4  122.35  4458.9  121.99  4499.7   118.9
  4539.2  118.95  4550.8  116.85  4622.2  114.79  4733.8  108.93  4836.6  104.99
  4847.1  103.61  4870.2  103.37    4901  100.38    4966   96.92  4983.1   96.18
  5005.7   92.81  5008.4   92.31  5011.7   92.81  5013.9   93.99  5024.2   95.59
  5044.7   97.29  5207.3  105.89  5280.8  111.16  5365.6  114.35  5411.6  114.87
  5783.8  114.87    5941  115.83  6060.9  118.82  6091.7  121.06  6119.7  121.31
#Mann= 8 ,-1 , 0
  4234.3      .1       0  4382.8     .05       0  4404.4     .08       0
  4733.8      .1       0  5005.7     .07       0  5011.7      .1       0
  5207.3     .16       0  5411.6      .1       0
Bank Sta=4966,5044.7
XS Rating Curve= 0 ,0
Exp/Cntr=0.3,0.1

Type RM Length L Ch R = 1 ,5566    ,520,520,520
BEGIN DESCRIPTION:
UNT018 IN NURI 3.0
END DESCRIPTION:
XS GIS Cut Line= 3
      2283037.71     13288996.83      2283187.72     13289396.85
      2283387.72     13290646.83
#Sta/Elev= 30
  4593.7  119.12  4608.9  118.64  4633.8   115.5  4657.8  115.56  4693.8  114.02
  4700.5  112.92  4779.7   107.9  4804.7  105.54    4818  105.25  4834.9  103.36
  4895.4  100.88  4920.4   98.23  4957.3   96.05  4967.5   95.22  4985.9   92.77
  4988.6   92.27  4991.9   92.77  4999.6    92.9  5005.8   95.19  5071.6   97.05
  5142.5  101.71  5253.9  105.78  5355.1  111.88  5431.7  113.87    5752  113.41
  5790.6  112.77  5972.9  114.08  6067.2  116.85  6114.7  119.55  6286.8  122.09
#Mann= 5 ,-1 , 0
  4593.7     .08       0  4693.8     .16       0  4957.3      .1       0
  4985.9     .07       0  4991.9      .1       0
Bank Sta=4967.5,5005.8
XS Rating Curve= 0 ,0
Exp/Cntr=0.3,0.1

Type RM Length L Ch R = 1 ,5046    ,0,0,0
BEGIN DESCRIPTION:
UNT018 IN NURI 1.0
END DESCRIPTION:
XS GIS Cut Line= 3
      2282687.72     13289046.83      2282686.42     13289773.05
      2283255.88     13290689.75
#Sta/Elev= 30
  4610.3  121.17  4710.3  115.77  4790.3  107.19  4840.3  104.64  4850.3  102.91
  4980.3   95.45  4997.3   92.77  5000.1   92.27  5003.3   92.77  5020.3   95.05
  5060.3   94.38  5160.3  100.13  5342.9  103.07  5429.4  102.86    5552  102.44
  5557.9  101.39  5573.2  102.16  5609.8  100.81  5623.5  102.34    5637  102.59
  5652.3   101.8  5694.8  103.36  5762.2  103.56  5783.4  101.76  5798.8  103.58
  5811.9  103.07  5978.2  107.54  6161.3   111.1  6282.9  116.17  6415.7  120.18
#Mann= 5 ,-1 , 0
  4610.3      .1       0  4997.3     .07       0  5003.3      .1       0
  5342.9     .16       0  5429.4      .1       0
Bank Sta=4980.3,5020.3
XS Rating Curve= 0 ,0
Exp/Cntr=0.3,0.1

Chan Stop Cuts=-1
Use User Specified Reach Order=0
Composite Channel Slope=5