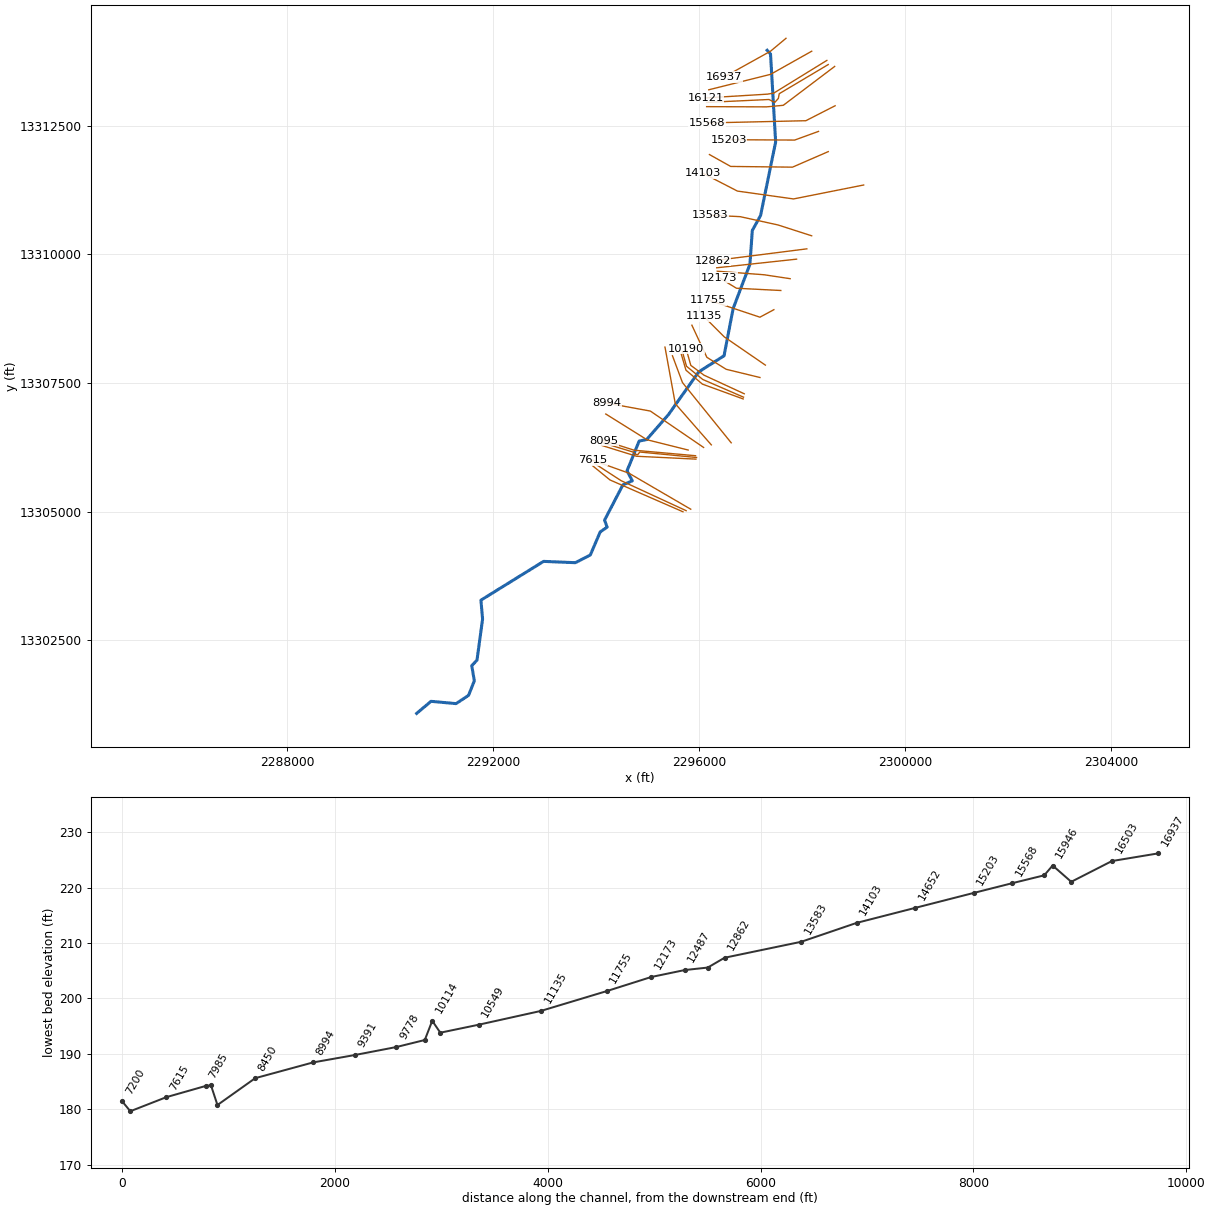
--- UNT019 IN NURI.prj (project) ---

Proj Title=UNT019 IN NURI Base Level Engineering
Current Plan=p01
Default Exp/Contr=0.3,0.1
English Units
Geom File=g01
Flow File=f01
Plan File=p01
Y Axis Title=Elevation
X Axis Title(PF)=Main Channel Distance
X Axis Title(XS)=Station
BEGIN DESCRIPTION:
UNT019 IN NURI
END DESCRIPTION:
DSS Export Rating Curves= 0
DSS Export Rating Curve Sorted= 0
DSS Export Volume Flow Curves= 0
DXF OffsetX= 0
DXF OffsetY= 0
DXF ScaleX= 1
DXF ScaleY= 10

--- UNT019 IN NURI.p01 (plan) ---

Plan Title=Multiple Run
Short Identifier=Multiple
Geom File=g01
Flow File=f01
Subcritical Flow
K Sum by GR= 0
Std Step Tol= 0.01
Critical Tol= 0.01
Num of Std Step Trials= 20
Max Error Tol= 0.3
Flow Tol Ratio= 0.001
Split Flow NTrial= 30
Split Flow Tol= 0.02
Split Flow Ratio= 0.02
Log Output Level= 0
Friction Slope Method= 1
Unsteady Friction Slope Method= 2
Unsteady Bridges Friction Slope Method= 1
Parabolic Critical Depth
Global Vel Dist=  1 , 1 , 1
Global Log Level= 0
CheckData=True
Encroach Param= -1, 0, 0, 0
BEGIN DESCRIPTION:
Multiple Run
END DESCRIPTION:

--- UNT019 IN NURI.f01 (steady flow) ---

Flow Title=Multiple
Number of Profiles=7
Profile Names=10-year,25-year,50-year,1pct_min,100-year,1pct_plu,500-year
River Rch & RM= UNT019 IN NURI,Reach-1,16937
     524     736     912     825    1116    1509    1679
River Rch & RM= UNT019 IN NURI,Reach-1,16503
     743    1062    1332    1218    1647    2228    2532
River Rch & RM= UNT019 IN NURI,Reach-1,12704
    1127    1644    2089    1934    2616    3538    4122
River Rch & RM= UNT019 IN NURI,Reach-1,8095
    1376    2023    2584    2402    3249    4393    5163
Boundary for River Rch & Prof#=UNT019 IN NURI,Reach-1,1
Up Type=0
Dn Type=3
Dn Slope=0.005
Boundary for River Rch & Prof#=UNT019 IN NURI,Reach-1,2
Up Type=0
Dn Type=3
Dn Slope=0.005
Boundary for River Rch & Prof#=UNT019 IN NURI,Reach-1,3
Up Type=0
Dn Type=3
Dn Slope=0.005
Boundary for River Rch & Prof#=UNT019 IN NURI,Reach-1,4
Up Type=0
Dn Type=3
Dn Slope=0.005
Boundary for River Rch & Prof#=UNT019 IN NURI,Reach-1,5
Up Type=0
Dn Type=3
Dn Slope=0.005
Boundary for River Rch & Prof#=UNT019 IN NURI,Reach-1,6
Up Type=0
Dn Type=3
Dn Slope=0.005
Boundary for River Rch & Prof#=UNT019 IN NURI,Reach-1,7
Up Type=0
Dn Type=3
Dn Slope=0.005

--- UNT019 IN NURI.g01 (geometry) ---

Geom Title=Existing Conditions
Program Version=4.10

River Reach=UNT019 IN NURI  ,Reach-1
Reach XY= 30
      2297322.08     13313964.16      2297387.55     13313891.76
      2297486.93     13312182.75      2297194.29     13310754.04
       2297033.7     13310463.24      2296987.04     13309805.69
      2296661.11     13308945.75      2296484.87     13308027.92
      2295993.92      13307716.6      2295403.27      13306882.9
      2294981.71     13306400.75      2294835.88     13306371.11
      2294600.27     13305792.73        2294703.     13305598.51
      2294519.88     13305519.64      2294164.05     13304834.06
      2294214.25     13304698.17      2294079.86     13304606.12
      2293887.29     13304156.81       2293597.2     13304007.72
      2292979.34     13304033.22       2291762.2     13303279.33
       2291794.7     13302912.58      2291685.81     13302112.58
      2291583.74     13302006.48      2291634.63     13301713.27
      2291522.03     13301429.71      2291279.85     13301269.12
       2290793.3     13301313.82      2290514.25     13301079.64

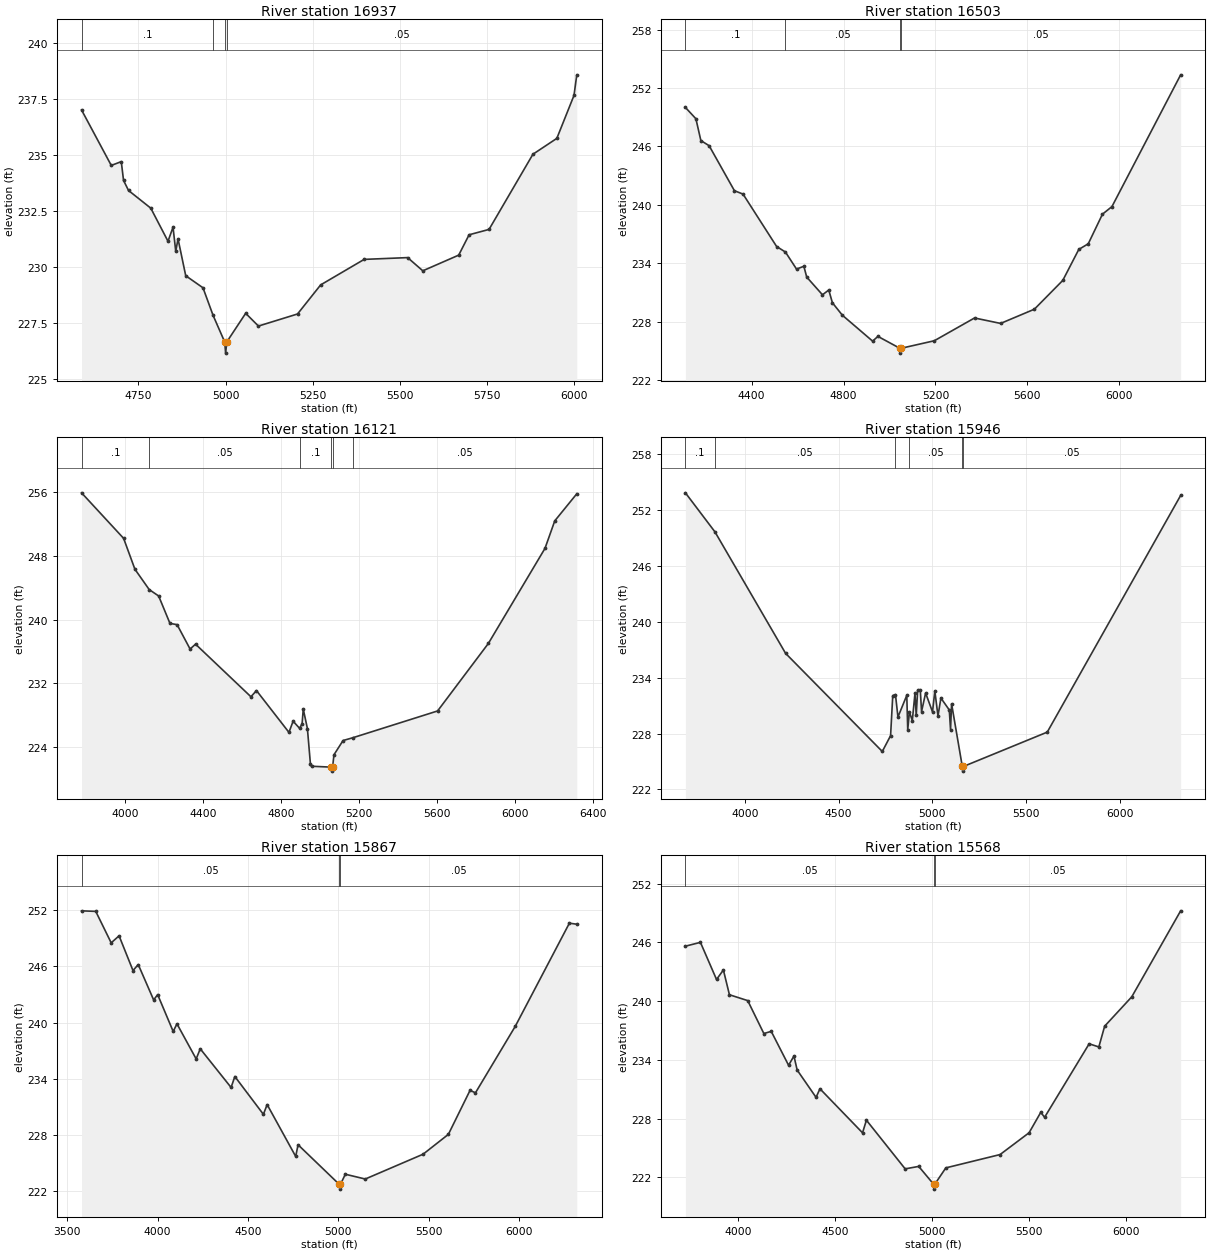
Type RM Length L Ch R = 1 ,16937   ,434,434,434
BEGIN DESCRIPTION:
UNT019 IN NURI 34.0
END DESCRIPTION:
XS GIS Cut Line= 3
       2297687.7     13314196.84      2297387.72     13313946.85
      2296487.76     13313446.88
#Sta/Elev= 30
  4586.9  237.02  4672.1  234.54  4700.8  234.71  4707.3  233.87  4721.6  233.42
  4785.4  232.63  4834.8  231.15  4849.2  231.78    4857   230.7  4863.5  231.26
  4885.6  229.61  4935.1  229.07    4964  227.84  4997.3  226.65    5000  226.15
  5003.3  226.65  5057.5  227.93  5094.1  227.36  5206.2   227.9  5272.5   229.2
  5397.2  230.34  5521.9  230.42  5565.4  229.83  5668.3  230.53  5698.1  231.44
  5755.3  231.68  5881.1  235.04  5949.7  235.75  5998.9  237.67  6006.9  238.59
#Mann= 4 ,-1 , 0
  4586.9      .1       0    4964     .05       0  4997.3     .03       0
  5003.3     .05       0
Bank Sta=4997.3,5003.3
XS Rating Curve= 0 ,0
Exp/Cntr=0.3,0.1

Type RM Length L Ch R = 1 ,16503   ,382,382,382
BEGIN DESCRIPTION:
UNT019 IN NURI 33.0
END DESCRIPTION:
XS GIS Cut Line= 3
       2298187.7     13313946.84      2297387.72     13313496.85
      2296187.71     13313196.85
#Sta/Elev= 30
    4112     250  4157.6  248.84  4179.2   246.6  4215.2  246.07  4325.2  241.45
  4362.8   241.1  4508.8  235.72  4547.2  235.15  4595.5   233.4  4627.3  233.69
  4639.8  232.58  4708.3  230.76  4735.7  231.25  4751.6  229.94    4795  228.66
  4926.6     226  4949.5  226.49  5044.9  225.27  5047.6  224.77  5050.9  225.27
  5194.8  226.04    5370  228.38  5483.4  227.82  5630.3  229.28    5754  232.24
  5823.6  235.42  5864.8     236  5926.6  239.04  5967.9  239.82  6266.8  253.35
#Mann= 4 ,-1 , 0
    4112      .1       0  4547.2     .05       0  5044.9     .03       0
  5050.9     .05       0
Bank Sta=5044.9,5050.9
XS Rating Curve= 0 ,0
Exp/Cntr=0.3,0.1

Type RM Length L Ch R = 1 ,16121   ,175,175,175
BEGIN DESCRIPTION:
Mapping XS 4e071cc6
END DESCRIPTION:
XS GIS Cut Line= 4
      2298481.77      13313767.9      2297453.13     13313134.22
       2297331.6     13313112.52      2296124.96     13313038.73
#Sta/Elev= 30
  3777.2  255.86    3993  250.16  4050.9   246.3  4124.3  243.75  4172.7  242.95
  4230.7  239.52  4267.4  239.36    4334  236.31    4362  236.92    4646  230.34
  4674.6  231.11  4841.1  225.88  4862.5  227.28  4895.5  226.39  4908.6  226.95
  4914.5   228.8  4935.8  226.36  4951.2  221.95    4957  221.64    5059  221.53
  5061.7  221.03    5065  221.53  5072.1  223.08  5118.7  224.86  5167.6   225.2
  5603.6  228.56  5864.1  237.01  6154.6  248.91  6204.7  252.35  6317.7  255.74
#Mann= 6 ,-1 , 0
  3777.2      .1       0  4124.3     .05       0  4895.5      .1       0
    5059     .07       0    5065      .1       0  5167.6     .05       0
Bank Sta=5059,5065
XS Rating Curve= 0 ,0
Exp/Cntr=0.3,0.1

Type RM Length L Ch R = 1 ,15946   ,79,79,79
BEGIN DESCRIPTION:
UNT019 IN NURI 32.0
END DESCRIPTION:
XS GIS Cut Line= 6
      2298508.72      13313687.2       2297557.3      13313121.2
      2297539.93     13313030.05      2297470.49     13312951.93
      2297357.64     13313008.35      2296146.69     13312951.93
#Sta/Elev= 30
  3682.5  253.86  3840.3  249.66  4217.1  236.62  4733.1  226.08  4777.4  227.78
  4788.9  232.08  4803.4  232.19  4816.7  229.78  4863.8  232.11  4868.9  228.42
  4877.9  230.33  4893.3   229.4  4907.5  232.32  4914.2  229.95  4921.7  232.66
  4935.9   232.7  4942.6  230.37  4964.3  232.36  5001.1  230.33  5013.5  232.59
  5030.3  229.89  5045.9  231.82  5090.6  230.54  5097.3  228.44  5102.9   231.2
    5160  224.47  5162.8  223.97    5166  224.47  5613.5  228.16  6325.3  253.58
#Mann= 6 ,-1 , 0
  3682.5      .1       0  3840.3     .05       0  4803.4      .1       0
  4877.9     .05       0    5160     .03       0    5166     .05       0
Bank Sta=5160,5166
XS Rating Curve= 0 ,0
Exp/Cntr=0.3,0.1

Type RM Length L Ch R = 1 ,15867   ,299,299,299
BEGIN DESCRIPTION:
Mapping XS 3c7c5896
END DESCRIPTION:
XS GIS Cut Line= 4
      2298633.71     13313650.73      2297635.42     13312895.51
       2297309.9     13312865.12      2296146.72     13312869.46
#Sta/Elev= 30
  3578.8  251.93  3657.5  251.87  3742.9  248.51  3786.5  249.26  3863.6  245.55
  3892.7  246.19    3978  242.41  4000.1  242.98  4086.2  239.04    4107  239.86
  4213.3  236.11    4236  237.19  4406.7  233.06  4427.5  234.23  4585.6  230.19
  4606.4  231.23  4764.5  225.69  4777.5  226.94  5006.1   222.7  5008.8   222.2
  5012.1   222.7  5039.2  223.79  5149.7  223.28  5469.7  225.93  5609.7  228.05
  5729.7  232.75  5759.7  232.49  5979.7  239.58  6279.7  250.61  6320.7   250.5
#Mann= 3 ,-1 , 0
  3578.8     .05       0  5006.1     .03       0  5012.1     .05       0
Bank Sta=5006.1,5012.1
XS Rating Curve= 0 ,0
Exp/Cntr=0.3,0.1

Type RM Length L Ch R = 1 ,15568   ,365,365,365
BEGIN DESCRIPTION:
UNT019 IN NURI 31.0
END DESCRIPTION:
XS GIS Cut Line= 3
      2298642.33     13312886.81      2298073.79     13312596.03
      2296155.37     13312552.62
#Sta/Elev= 30
  3726.4   245.6  3803.9  245.99  3887.1   242.2  3922.5  243.17  3953.7  240.64
  4048.2  240.04  4131.4  236.68  4169.6   236.9  4259.1  233.44  4286.9  234.38
  4303.5  232.95  4401.1  230.16  4421.1  231.04  4641.1  226.54  4661.1  227.83
  4861.2  222.86  4931.2  223.11  5008.2  221.29    5011  220.79  5014.2  221.29
  5071.2  222.96  5351.3  224.32  5501.3  226.55  5561.4  228.63  5581.4  228.13
  5811.4  235.63  5861.4  235.31  5891.4  237.43  6031.5  240.43  6283.9  249.21
#Mann= 3 ,-1 , 0
  3726.4     .05       0  5008.2     .03       0  5014.2     .05       0
Bank Sta=5008.2,5014.2
XS Rating Curve= 0 ,0
Exp/Cntr=0.3,0.1

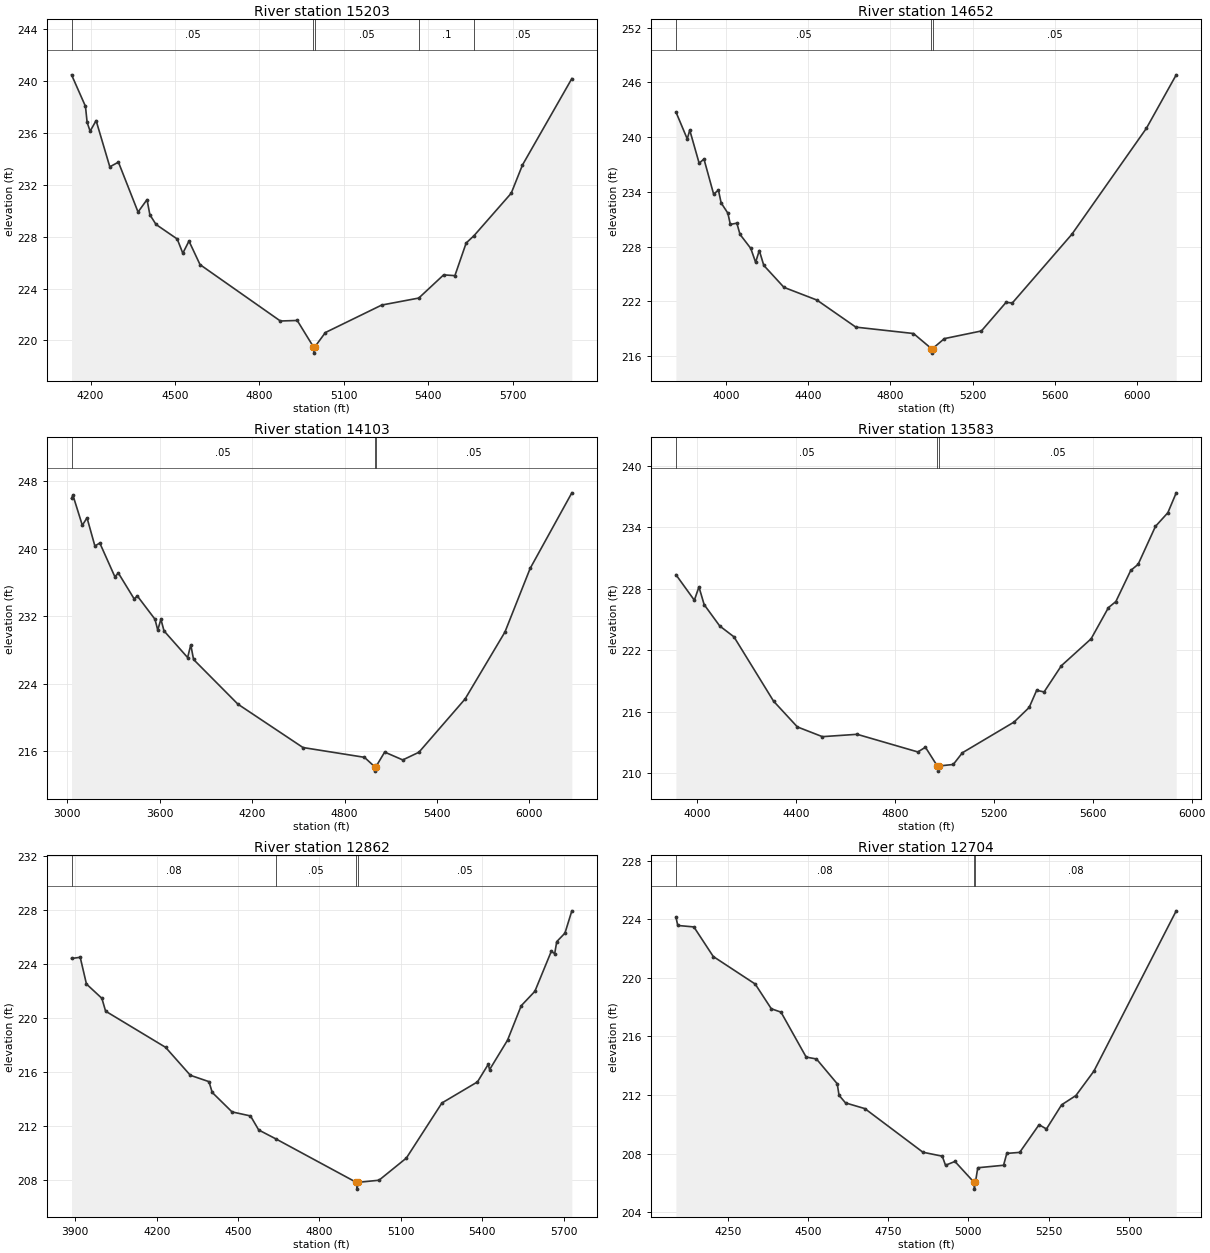
Type RM Length L Ch R = 1 ,15203   ,551,551,551
BEGIN DESCRIPTION:
UNT019 IN NURI 30.0
END DESCRIPTION:
XS GIS Cut Line= 3
      2298319.72     13312388.53      2297856.42     13312220.06
      2296572.31     13312227.08
#Sta/Elev= 30
  4132.4   240.5  4181.8  238.07  4187.7  236.83  4198.4  236.15  4219.6  236.97
  4268.3   233.4  4298.9  233.76  4368.6  229.91  4400.5  230.87  4410.6   229.7
  4432.5  228.95  4507.7  227.83  4527.6  226.73  4549.5  227.67  4588.8  225.85
  4874.1   221.5  4934.1  221.54  4991.1  219.52  4993.8  219.02  4997.1  219.52
  5034.1  220.61  5234.1  222.73  5365.7  223.27  5454.1  225.06  5494.1     225
  5534.1  227.52  5562.2  228.09  5694.1  231.36  5734.1  233.54  5909.5  240.21
#Mann= 5 ,-1 , 0
  4132.4     .05       0  4991.1     .03       0  4997.1     .05       0
  5365.7      .1       0  5562.2     .05       0
Bank Sta=4991.1,4997.1
XS Rating Curve= 0 ,0
Exp/Cntr=0.3,0.1

Type RM Length L Ch R = 1 ,14652   ,549,549,549
BEGIN DESCRIPTION:
UNT019 IN NURI 29.0
END DESCRIPTION:
XS GIS Cut Line= 4
      2298509.25     13311995.43      2297814.31     13311693.59
      2296613.95     13311707.63      2296201.23     13311938.47
#Sta/Elev= 30
  3757.5  242.76  3812.5   239.8  3824.6  240.77  3870.3  237.14  3893.7   237.6
  3940.6  233.76  3964.1  234.18  3977.2  232.79  4009.9  231.66  4021.9  230.43
  4053.5  230.57  4068.8  229.34  4121.2   227.8  4144.6  226.28  4162.6  227.57
  4184.4  225.94  4282.5  223.53  4442.4  222.14  4631.8  219.17  4911.8  218.47
  4998.8  216.82  5001.5  216.32  5004.8  216.82  5061.8  217.91  5241.8  218.75
  5361.8  221.89  5391.8  221.81  5681.8  229.36  6043.6  240.97  6188.5  246.83
#Mann= 3 ,-1 , 0
  3757.5     .05       0  4998.8     .03       0  5004.8     .05       0
Bank Sta=4998.8,5004.8
XS Rating Curve= 0 ,0
Exp/Cntr=0.3,0.1

Type RM Length L Ch R = 1 ,14103   ,520,520,520
BEGIN DESCRIPTION:
UNT019 IN NURI 28.0
END DESCRIPTION:
XS GIS Cut Line= 4
      2299196.21      13311346.9      2297835.07     13311076.06
       2296744.8     13311228.84      2296071.97     13311575.66
#Sta/Elev= 30
  3029.2  245.99  3037.9  246.38    3099   242.8  3129.6  243.68  3180.6  240.34
  3212.5  240.69  3309.7  236.71  3333.5  237.11  3435.5  234.06  3455.9  234.41
  3570.3  231.65  3588.4  230.36  3608.8  231.65  3629.2  230.26  3782.2   227.1
  3802.6  228.61  3820.8  226.87  4108.4  221.57  4530.6  216.42  4929.3  215.26
    4997  214.12  4999.8  213.62    5003  214.12  5060.6  215.88    5178  214.95
  5282.7  215.86  5582.2  222.18  5840.9  230.13  6004.4  237.68  6274.9  246.65
#Mann= 3 ,-1 , 0
  3029.2     .05       0    4997     .03       0    5003     .05       0
Bank Sta=4997,5003
XS Rating Curve= 0 ,0
Exp/Cntr=0.3,0.1

Type RM Length L Ch R = 1 ,13583   ,721,721,721
BEGIN DESCRIPTION:
UNT019 IN NURI 27.0
END DESCRIPTION:
XS GIS Cut Line= 4
      2298186.37     13310359.85      2297533.52     13310570.45
      2296796.46      13310731.9      2296213.85     13310759.98
#Sta/Elev= 30
  3913.8  229.37  3988.3  226.88  4006.9  228.18    4028  226.45    4091  224.37
  4148.6  223.31  4308.8  217.04    4405  214.53  4506.3  213.58  4646.7  213.81
  4892.4  212.09  4923.1  212.55  4971.2  210.72    4974  210.22  4977.2  210.72
  5035.7  210.87  5072.6  212.01  5281.4     215  5342.8  216.43  5373.1   218.1
  5403.1  217.94  5473.2   220.5  5593.3  223.12  5663.4  226.16  5693.4  226.75
  5753.5  229.78  5783.5  230.38  5853.6  234.08  5903.7  235.41  5937.6  237.35
#Mann= 3 ,-1 , 0
  3913.8     .05       0  4971.2     .03       0  4977.2     .05       0
Bank Sta=4971.2,4977.2
XS Rating Curve= 0 ,0
Exp/Cntr=0.3,0.1

Type RM Length L Ch R = 1 ,12862   ,158,158,158
BEGIN DESCRIPTION:
UNT019 IN NURI 26.0
END DESCRIPTION:
XS GIS Cut Line= 2
       2298092.2     13310106.15      2296262.53     13309873.53
#Sta/Elev= 30
  3886.2  224.42  3918.1  224.51  3941.1  222.53    3998  221.47  4011.7  220.52
  4232.9  217.84  4324.2  215.77  4392.8   215.3  4404.8   214.5  4477.8  213.06
  4545.9  212.76  4576.2  211.72  4640.5  211.05  4936.1  207.84  4938.8  207.34
  4942.1  207.84  5019.7     208  5120.5  209.64  5251.6  213.72  5382.6  215.28
  5422.3  216.58  5427.4  216.19  5493.5  218.37  5543.9  220.92  5594.3  221.99
  5654.8  224.95  5667.3  224.78    5675  225.67  5705.2   226.3  5730.6  227.95
#Mann= 4 ,-1 , 0
  3886.2     .08       0  4640.5     .05       0  4936.1     .04       0
  4942.1     .05       0
Bank Sta=4936.1,4942.1
XS Rating Curve= 0 ,0
Exp/Cntr=0.3,0.1

Type RM Length L Ch R = 1 ,12704   ,217,217,217
BEGIN DESCRIPTION:
UNT019 IN NURI 25.0
END DESCRIPTION:
XS GIS Cut Line= 2
      2297893.42     13309905.85      2296342.46     13309738.12
#Sta/Elev= 30
  4088.2  224.16  4093.9  223.58  4144.2  223.48  4204.6  221.46  4335.3  219.58
  4385.6  217.89  4415.8  217.66  4494.3  214.59  4526.4  214.46  4591.1  212.77
  4596.8  211.98    4617  211.46  4677.3  211.07  4858.4  208.09  4918.7  207.82
  4928.8   207.2  4958.2  207.46  5016.3  206.07    5019  205.57  5022.3  206.07
  5029.4  207.03  5109.8   207.2  5119.9  208.01  5160.1  208.08  5220.5  209.97
  5243.5  209.68  5290.9  211.33  5335.3  211.96  5391.5  213.63  5648.2  224.58
#Mann= 3 ,-1 , 0
  4088.2     .08       0  5016.3     .07       0  5022.3     .08       0
Bank Sta=5016.3,5022.3
XS Rating Curve= 0 ,0
Exp/Cntr=0.3,0.1

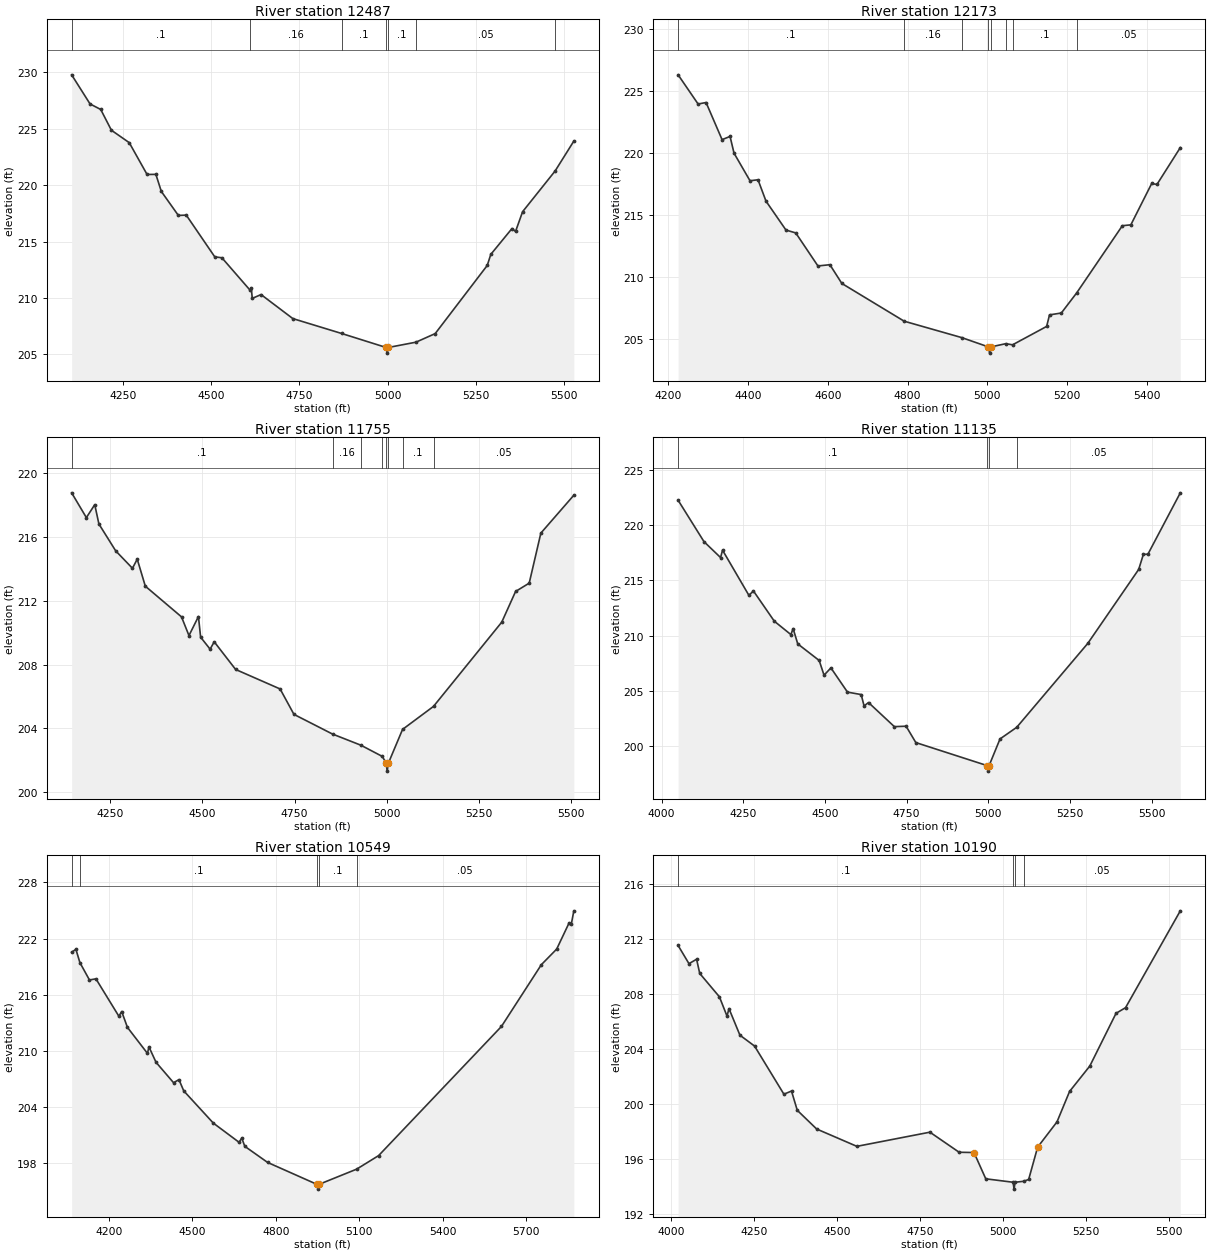
Type RM Length L Ch R = 1 ,12487   ,314,314,314
BEGIN DESCRIPTION:
UNT019 IN NURI 24.0
END DESCRIPTION:
XS GIS Cut Line= 3
      2297769.31      13309526.3      2297262.39     13309602.68
      2296352.76     13309671.86
#Sta/Elev= 30
  4103.8  229.78    4156   227.2  4186.3  226.71  4216.6  224.87  4267.2  223.77
  4317.8  220.95  4342.8  220.96  4358.2  219.45  4406.6  217.32    4429  217.35
  4509.9  213.65  4530.1  213.57  4609.7  210.71  4613.5  210.87  4616.3  209.97
  4641.2  210.31  4731.4  208.18  4869.9  206.86  4996.2  205.62  4998.9  205.12
  5002.2  205.62  5080.7  206.09  5135.3  206.85    5283  212.89  5293.1  213.87
  5353.2  216.16  5363.3   215.9  5383.3  217.65  5475.6  221.26  5528.7  223.91
#Mann= 7 ,-1 , 0
  4103.8      .1       0  4609.7     .16       0  4869.9      .1       0
  4996.2     .07       0  5002.2      .1       0  5080.7     .05       0
  5475.6     .08       0
Bank Sta=4996.2,5002.2
XS Rating Curve= 0 ,0
Exp/Cntr=0.3,0.1

Type RM Length L Ch R = 1 ,12173   ,418,418,418
BEGIN DESCRIPTION:
UNT019 IN NURI 23.0
END DESCRIPTION:
XS GIS Cut Line= 3
      2297587.73     13309296.85      2296725.87     13309340.83
      2296387.68     13309546.88
#Sta/Elev= 30
  4224.8  226.28  4274.9  223.93  4294.9  224.05    4335  221.06    4355  221.32
    4365  219.97    4405  217.75  4425.1  217.83  4445.1  216.11  4495.2  213.78
  4519.7  213.55  4575.3  210.89  4605.3  210.99  4635.3  209.48  4791.6  206.44
  4935.9  205.12  5002.8  204.37  5005.6  203.87  5008.8  204.37  5046.2  204.63
  5063.3  204.54  5148.7  206.02  5155.9  206.95  5185.5   207.1  5223.8  208.71
  5338.5  214.13  5359.8   214.2  5412.1  217.53  5425.2  217.45  5483.8  220.42
#Mann= 8 ,-1 , 0
  4224.8      .1       0  4791.6     .16       0  4935.9      .1       0
  5002.8     .07       0  5008.8      .1       0  5046.2     .05       0
  5063.3      .1       0  5223.8     .05       0
Bank Sta=5002.8,5008.8
XS Rating Curve= 0 ,0
Exp/Cntr=0.3,0.1

Type RM Length L Ch R = 1 ,11755   ,620,620,620
BEGIN DESCRIPTION:
UNT019 IN NURI 22.0
END DESCRIPTION:
XS GIS Cut Line= 3
      2297452.82     13308924.22      2297181.97     13308778.38
      2296182.36     13309111.58
#Sta/Elev= 30
  4145.9  218.74  4185.8  217.19  4208.5     218  4219.8  216.79  4265.3  215.11
  4310.7  214.02  4323.7  214.59  4345.6   212.9  4443.7  210.98  4463.9  209.81
  4489.6     211  4495.5  209.71  4521.2  208.96  4532.4  209.42  4590.4  207.69
    4711  206.47  4748.5  204.88    4853  203.65  4930.1  202.95    4988  202.25
  4998.5  201.83  5001.2  201.33  5004.5  201.83  5042.9  203.94  5126.8  205.38
  5311.8  210.65  5349.3  212.57  5386.2  213.09  5417.8  216.22  5507.2  218.59
#Mann= 8 ,-1 , 0
  4145.9      .1       0    4853     .16       0  4930.1      .1       0
    4988     .16       0  4998.5     .07       0  5004.5     .16       0
  5042.9      .1       0  5126.8     .05       0
Bank Sta=4998.5,5004.5
XS Rating Curve= 0 ,0
Exp/Cntr=0.3,0.1

Type RM Length L Ch R = 1 ,11135   ,586,586,586
BEGIN DESCRIPTION:
UNT019 IN NURI 21.0
END DESCRIPTION:
XS GIS Cut Line= 3
       2297287.7     13307846.87      2296487.72     13308396.85
      2296087.71     13308796.86
#Sta/Elev= 30
  4050.7  222.23  4129.8  218.49  4180.6  217.05  4186.6  217.72  4267.2  213.64
  4281.2  214.03    4345   211.3  4395.7  210.09  4402.6  210.63  4416.7  209.25
  4482.3  207.75  4497.2  206.42  4518.2  207.08  4568.9  204.89  4610.8  204.67
  4619.7  203.64  4633.2  203.95  4712.3  201.77  4748.2  201.81    4778  200.33
  4996.2  198.25  4998.9  197.75  5002.2  198.25  5035.6  200.66  5086.7  201.71
  5304.3   209.3  5459.9  215.98  5474.1  217.33  5488.2  217.36  5587.2   222.9
#Mann= 4 ,-1 , 0
  4050.7      .1       0  4996.2     .07       0  5002.2      .1       0
  5086.7     .05       0
Bank Sta=4996.2,5002.2
XS Rating Curve= 0 ,0
Exp/Cntr=0.3,0.1

Type RM Length L Ch R = 1 ,10549   ,359,359,359
BEGIN DESCRIPTION:
UNT019 IN NURI 20.0
END DESCRIPTION:
XS GIS Cut Line= 4
      2297182.56     13307606.15      2296526.28     13307765.88
      2296151.28     13307998.52      2295860.01     13308622.66
#Sta/Elev= 30
  4066.2  220.55  4081.5  220.86  4095.9  219.44  4130.2  217.59  4153.5  217.71
  4235.9  213.72  4246.1  214.22  4266.7  212.53  4338.8  209.75    4344  210.45
  4369.6   208.8  4432.6  206.62    4452  206.95  4469.2  205.75  4575.5  202.31
  4668.1  200.26  4677.8  200.71  4688.7  199.83  4770.7  198.11  4948.8  195.76
  4951.5  195.26  4954.8  195.76  5090.7  197.39  5169.9  198.84  5611.5  212.63
  5754.9  219.22  5810.1  220.89  5854.3  223.66  5862.5  223.53  5871.7  224.97
#Mann= 5 ,-1 , 0
  4066.2     .05       0  4095.9      .1       0  4948.8     .07       0
  4954.8      .1       0  5090.7     .05       0
Bank Sta=4948.8,4954.8
XS Rating Curve= 0 ,0
Exp/Cntr=0.3,0.1

Type RM Length L Ch R = 1 ,10190   ,76,76,76
BEGIN DESCRIPTION:
UNT019 IN NURI 19.0
END DESCRIPTION:
XS GIS Cut Line= 4
      2296876.94      13307290.2      2296095.72     13307651.29
      2295838.78     13307842.27      2295748.98     13308163.47
#Sta/Elev= 30
  4020.3  211.54    4053  210.22    4076  210.54  4085.5  209.51  4144.8  207.81
  4167.7  206.41  4173.7  206.95  4206.7  205.02  4250.8  204.23  4339.3  200.73
  4362.2  200.96  4379.6  199.56  4438.1   198.2  4559.3  196.94  4779.6  197.97
  4867.7  196.51  4912.5  196.49    4948  194.58  5030.5  194.33  5033.2  193.83
  5036.5  194.33    5062   194.4  5077.3  194.53  5104.4  196.88  5162.8  198.72
  5200.7  200.93  5261.8  202.78  5340.8  206.61  5369.5  207.02  5534.6  214.06
#Mann= 4 ,-1 , 0
  4020.3      .1       0  5030.5     .07       0  5036.5      .1       0
    5062     .05       0
Bank Sta=4912.5,5104.4
XS Rating Curve= 0 ,0
Exp/Cntr=0.3,0.1

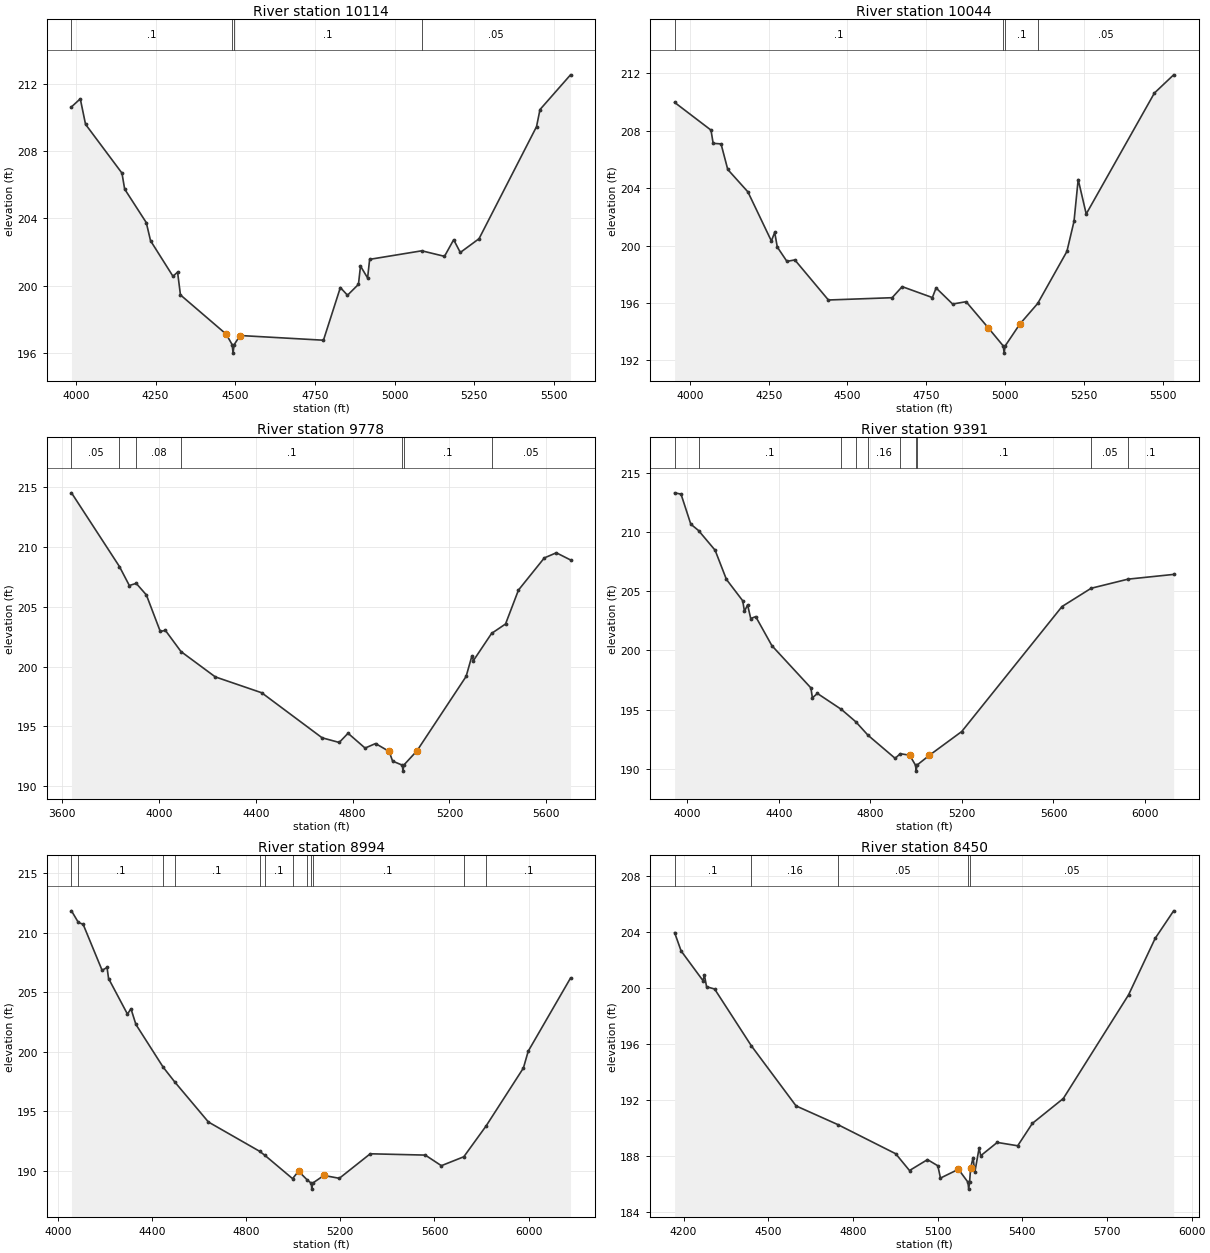
Type RM Length L Ch R = 1 ,10114   ,70,70,70
BEGIN DESCRIPTION:
Mapping XS f5ac7052
END DESCRIPTION:
XS GIS Cut Line= 4
      2296863.04     13307224.23      2296071.42     13307567.96
      2295755.44      13307824.9      2295675.58     13308109.63
#Sta/Elev= 30
  3986.3  210.65  4013.9  211.13  4030.4  209.61  4144.7   206.7  4153.1  205.75
    4221  203.75  4234.4  202.67  4304.8  200.55  4319.2   200.8  4328.2  199.44
  4471.8   197.1  4490.6  196.47  4493.3  195.97  4496.6  196.47  4515.4  197.02
    4777  196.74    4830  199.88  4852.4  199.42  4886.8  200.07  4893.2  201.16
  4915.5  200.45  4921.9  201.56  5085.5  202.07  5156.8  201.74  5185.6  202.73
  5206.4  201.97  5265.2  202.79  5445.6  209.47  5456.5  210.49  5552.3  212.56
#Mann= 4 ,-1 , 0
  3986.3      .1       0  4490.6     .07       0  4496.6      .1       0
  5085.5     .05       0
Bank Sta=4471.8,4515.4
XS Rating Curve= 0 ,0
Exp/Cntr=0.3,0.1

Type RM Length L Ch R = 1 ,10044   ,266,266,266
BEGIN DESCRIPTION:
Mapping XS a5e57ba1
END DESCRIPTION:
XS GIS Cut Line= 4
      2296856.18     13307189.47      2296064.47     13307477.68
      2295745.03     13307748.52      2295654.74     13308057.56
#Sta/Elev= 30
  3951.7  209.97  4067.1  208.04    4074  207.12    4099  207.08  4120.3   205.3
  4184.2  203.74  4258.7  200.32  4269.3  200.92  4277.4   199.9    4308   198.9
  4333.2     199  4439.6  196.21  4641.8  196.37  4673.7  197.14  4769.5  196.38
  4781.3  197.05  4833.7  195.93  4876.6  196.09  4947.3  194.26  4994.4  193.01
  4997.2  192.51  5000.4  193.01  5046.9  194.53  5103.7  195.97  5196.3  199.59
  5218.9  201.69  5232.1   204.6  5257.6   202.2  5473.9  210.62    5535  211.89
#Mann= 4 ,-1 , 0
  3951.7      .1       0  4994.4     .07       0  5000.4      .1       0
  5103.7     .05       0
Bank Sta=4947.3,5046.9
XS Rating Curve= 0 ,0
Exp/Cntr=0.3,0.1

Type RM Length L Ch R = 1 ,9778    ,387,387,387
BEGIN DESCRIPTION:
UNT019 IN NURI 18.0
END DESCRIPTION:
XS GIS Cut Line= 3
       2296623.8     13306337.17      2295677.26      13307507.5
      2295482.83      13308028.3
#Sta/Elev= 30
  3638.8  214.55  3836.8  208.38  3877.7  206.79  3906.2  206.97  3948.1     206
  4005.6  202.94  4026.4  203.04  4091.1  201.26  4232.7  199.14  4424.5  197.81
  4673.9  194.04  4744.5  193.65    4781  194.42  4851.4  193.18  4894.6  193.56
  4950.6   192.9    4965  192.09  5005.1  191.75  5007.9  191.25  5011.1  191.75
  5065.6  192.95  5268.7  199.18  5292.7   200.9    5299  200.51  5373.9  202.78
  5431.5  203.57  5484.9  206.41  5591.6   209.1  5641.3  209.53  5699.9  208.93
#Mann= 7 ,-1 , 0
  3638.8     .05       0  3836.8      .1       0  3906.2     .08       0
  4091.1      .1       0  5005.1     .07       0  5011.1      .1       0
  5373.9     .05       0
Bank Sta=4950.6,5065.6
XS Rating Curve= 0 ,0
Exp/Cntr=0.3,0.1

Type RM Length L Ch R = 1 ,9391    ,397,397,397
BEGIN DESCRIPTION:
UNT019 IN NURI 17.0
END DESCRIPTION:
XS GIS Cut Line= 3
      2296237.73     13306296.85      2295537.72     13307096.85
      2295337.71     13308196.89
#Sta/Elev= 30
  3944.2  213.29  3972.2  213.18  4014.9  210.65  4048.8  210.11  4121.2  208.45
  4170.6  205.99  4241.8  204.19  4249.4   203.3  4263.1  203.84  4276.9  202.69
  4298.7  202.85  4369.4   200.4  4539.8  196.84  4546.4     196  4568.3  196.37
  4673.5  195.02  4736.2  193.98  4789.8  192.84    4908   190.9  4930.5  191.29
  4971.6  191.16  4997.1  190.32  4999.9  189.82  5003.1  190.32    5058  191.16
  5199.1  193.16  5637.4   203.7  5764.6  205.24  5925.8  206.01  6125.3  206.41
#Mann= 10 ,-1 , 0
  3944.2     .08       0  4048.8      .1       0  4673.5     .16       0
  4736.2      .1       0  4789.8     .16       0  4930.5      .1       0
  4997.1     .07       0  5003.1      .1       0  5764.6     .05       0
  5925.8      .1       0
Bank Sta=4971.6,5058
XS Rating Curve= 0 ,0
Exp/Cntr=0.3,0.1

Type RM Length L Ch R = 1 ,8994    ,544,544,544
BEGIN DESCRIPTION:
UNT019 IN NURI 16.0
END DESCRIPTION:
XS GIS Cut Line= 3
      2296087.71     13306246.86      2295053.19     13306954.24
      2294200.88     13307110.15
#Sta/Elev= 30
  4058.1  211.86  4087.3  210.88  4107.5  210.73  4188.1  206.86  4209.1   207.1
  4215.6  206.17  4295.8  203.18  4310.7  203.63  4331.7  202.31  4447.5  198.72
  4496.6  197.48  4639.8  194.11  4857.2  191.65  4880.2   191.3  4997.2  189.35
  5022.4  189.98  5059.6  189.24  5076.3  188.97    5079  188.47  5082.3  188.97
  5130.1  189.62  5195.8  189.38  5327.1  191.44  5560.9  191.33  5629.2  190.44
  5724.5  191.19  5819.2  193.78  5977.7  198.65    5998  200.06  6177.8  206.21
#Mann= 12 ,-1 , 0
  4058.1     .08       0  4087.3      .1       0  4447.5     .16       0
  4496.6      .1       0  4857.2     .16       0  4880.2      .1       0
  4997.2     .16       0  5059.6      .1       0  5076.3     .07       0
  5082.3      .1       0  5724.5     .05       0  5819.2      .1       0
Bank Sta=5022.4,5130.1
XS Rating Curve= 0 ,0
Exp/Cntr=0.3,0.1

Type RM Length L Ch R = 1 ,8450    ,355,355,355
BEGIN DESCRIPTION:
UNT019 IN NURI 15.0
END DESCRIPTION:
XS GIS Cut Line= 3
      2295787.68     13306196.87      2294987.72     13306396.85
       2294187.7     13306896.87
#Sta/Elev= 30
  4168.2  203.97  4191.3  202.66  4268.7  200.54  4273.8  200.93  4281.5   200.1
  4309.9  199.94    4440  195.88  4598.5  191.58  4745.9  190.25  4951.5  188.16
  5000.4  186.96  5064.1  187.74  5100.7   187.3  5110.1  186.42  5173.8  187.05
  5207.3  186.13  5210.1  185.63  5213.3  186.13  5216.8  187.13  5225.7  187.89
  5231.6  186.82  5246.9  188.56  5252.8  188.02  5311.2  188.97  5383.7  188.73
  5435.6  190.33  5545.3  192.11  5776.4  199.52  5870.7  203.56  5936.2  205.53
#Mann= 5 ,-1 , 0
  4168.2      .1       0    4440     .16       0  4745.9     .05       0
  5207.3     .04       0  5213.3     .05       0
Bank Sta=5173.8,5216.8
XS Rating Curve= 0 ,0
Exp/Cntr=0.3,0.1

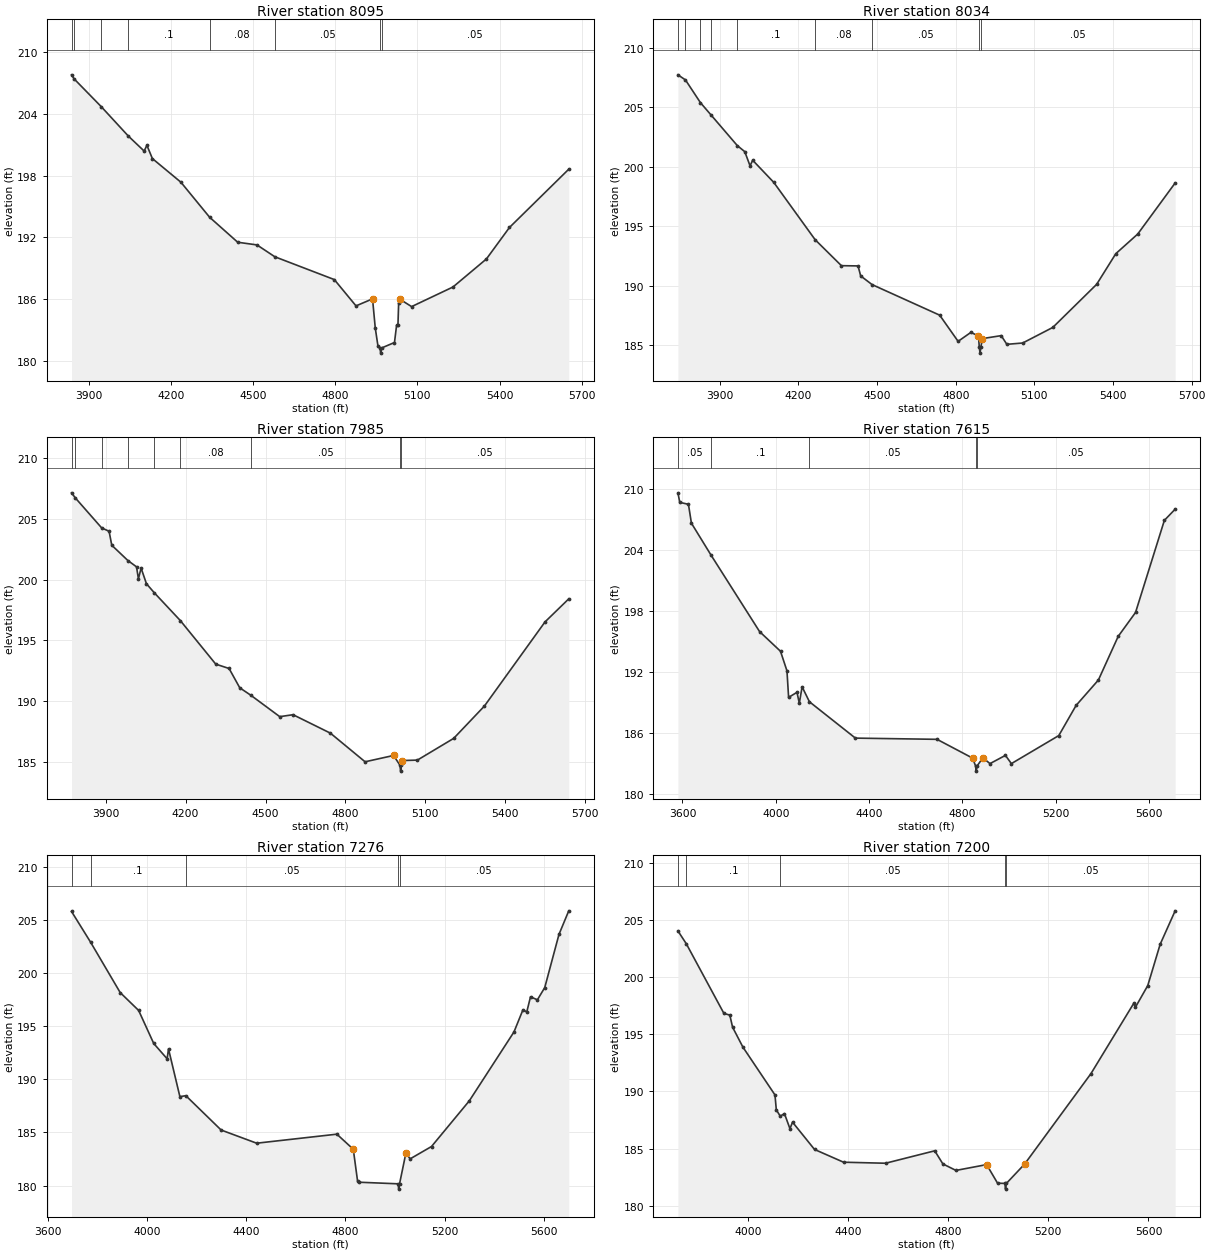
Type RM Length L Ch R = 1 ,8095    ,61,61,61
BEGIN DESCRIPTION:
Mapping XS a36cdacd
END DESCRIPTION:
XS GIS Cut Line= 4
      2295931.66     13306086.19       2294813.6     13306186.88
      2294747.63     13306190.36      2294151.61     13306380.95
#Sta/Elev= 30
  3837.8  207.77  3847.5  207.37  3946.4  204.68  4045.2  201.83  4102.8  200.38
  4112.8  200.94  4132.9  199.65  4236.9  197.36  4341.8  193.96  4444.2  191.54
  4514.5  191.28  4579.8  190.13  4796.7  187.92  4875.9  185.37  4936.2  186.05
  4946.2  183.22  4955.8  181.51  4963.3  181.29    4966  180.79  4969.3  181.29
  5016.3  181.82  5023.9  183.47  5028.9  183.47  5031.5  185.68  5036.8     186
  5078.8   185.3  5229.7   187.2  5351.8  189.92  5435.8  192.97  5652.2  198.62
#Mann= 8 ,-1 , 0
  3837.8     .08       0  3847.5      .1       0  3946.4     .16       0
  4045.2      .1       0  4341.8     .08       0  4579.8     .05       0
  4963.3     .03       0  4969.3     .05       0
Bank Sta=4936.2,5036.8
XS Rating Curve= 0 ,0
Exp/Cntr=0.3,0.1

Type RM Length L Ch R = 1 ,8034    ,49,49,49
BEGIN DESCRIPTION:
UNT019 IN NURI 14.0
END DESCRIPTION:
XS GIS Cut Line= 6
      2295951.59     13306051.75      2294847.53     13306158.35
      2294807.17     13306104.96       2294765.5     13306114.08
      2294719.93     13306157.04      2294131.15     13306335.71
#Sta/Elev= 30
  3740.4  207.74  3769.2  207.31  3826.3   205.4  3868.1  204.33    3967  201.79
  3995.5  201.28  4015.5  200.09  4025.6  200.56    4106   198.7  4263.9  193.88
    4364   191.7  4427.5  191.68  4437.5  190.84    4481  190.11  4738.9  187.54
  4809.2  185.34  4857.7  186.09  4886.8   185.8    4890  184.85  4892.8  184.35
    4896  184.85  4901.3  185.57  4973.6  185.82  4995.1  185.09  5055.5   185.2
  5170.4  186.51  5337.6  190.13  5410.8  192.71  5494.4  194.36  5637.1  198.65
#Mann= 9 ,-1 , 0
  3740.4      .1       0  3769.2     .08       0  3826.3      .1       0
  3868.1     .16       0    3967      .1       0  4263.9     .08       0
    4481     .05       0    4890     .03       0    4896     .05       0
Bank Sta=4886.8,4901.3
XS Rating Curve= 0 ,0
Exp/Cntr=0.3,0.1

Type RM Length L Ch R = 1 ,7985    ,370,370,370
BEGIN DESCRIPTION:
Mapping XS f2eda210
END DESCRIPTION:
XS GIS Cut Line= 3
       2295938.6     13306020.22      2294785.83     13306075.77
      2294105.23     13306287.59
#Sta/Elev= 30
  3771.7  207.17  3786.4  206.74  3884.8  204.28  3912.7     204  3922.8  202.85
  3983.3  201.59  4015.7  201.07  4022.9  200.08  4032.9  200.97  4052.9  199.68
  4081.7  198.95  4180.2  196.64  4313.2  193.05  4363.3  192.69  4403.3   191.1
  4445.2  190.48  4553.5  188.72  4603.5  188.88  4743.7  187.36  4873.9     185
  4980.7  185.52  5004.6  184.73  5007.4  184.23  5010.6  184.73  5013.2   185.1
  5070.4  185.14  5206.6  186.93  5321.8  189.59  5549.5  196.53  5638.6  198.43
#Mann= 9 ,-1 , 0
  3771.7      .1       0  3786.4     .08       0  3884.8     .16       0
  3983.3      .1       0  4081.7     .16       0  4180.2     .08       0
  4445.2     .05       0  5004.6     .03       0  5010.6     .05       0
Bank Sta=4980.7,5013.2
XS Rating Curve= 0 ,0
Exp/Cntr=0.3,0.1

Type RM Length L Ch R = 1 ,7615    ,339,339,339
BEGIN DESCRIPTION:
UNT019 IN NURI 13.0
END DESCRIPTION:
XS GIS Cut Line= 3
      2295837.75     13305046.84      2294637.72     13305746.85
       2293937.7     13305996.86
#Sta/Elev= 30
  3580.4  209.61  3588.3  208.67  3625.5  208.48  3638.3  206.62  3722.6  203.47
  3930.6  195.95  4020.4  194.01  4048.1  192.08  4055.1  189.47  4091.1  189.97
    4101  188.89    4113  190.51  4144.4  189.04  4341.6  185.46  4691.8  185.34
  4844.4  183.49  4857.1  182.71  4859.9  182.21  4863.1  182.71  4888.6  183.52
  4918.8  182.95  4985.1  183.76  5010.6  182.95  5213.9  185.71  5288.2  188.68
  5383.8  191.18  5468.8  195.48  5543.1  197.83  5666.8   206.9    5713     208
#Mann= 5 ,-1 , 0
  3580.4     .05       0  3722.6      .1       0  4144.4     .05       0
  4857.1     .03       0  4863.1     .05       0
Bank Sta=4844.4,4888.6
XS Rating Curve= 0 ,0
Exp/Cntr=0.3,0.1

Type RM Length L Ch R = 1 ,7276    ,76,76,76
BEGIN DESCRIPTION:
Mapping XS 5bb1fd69
END DESCRIPTION:
XS GIS Cut Line= 3
      2295748.46      13305018.6       2294484.6     13305601.92
      2293971.72      13305934.6
#Sta/Elev= 30
  3696.7  205.79  3773.5   202.9  3892.8  198.16  3967.1  196.48  4027.9  193.37
  4081.9  191.93  4087.4  192.86  4133.3  188.37  4157.3  188.46  4299.4  185.23
  4442.6  183.99  4765.8  184.84  4831.9  183.42  4849.2  180.42  4854.7  180.32
  5012.3  180.17    5015  179.67  5018.3  180.17  5043.7  183.04  5061.2  182.52
  5147.1  183.68  5299.5  187.98  5479.4  194.46  5515.6  196.55  5530.8  196.33
  5545.9  197.76  5573.7  197.48  5603.3  198.63  5660.6  203.63    5700  205.85
#Mann= 5 ,-1 , 0
  3696.7     .05       0  3773.5      .1       0  4157.3     .05       0
  5012.3     .03       0  5018.3     .05       0
Bank Sta=4831.9,5043.7
XS Rating Curve= 0 ,0
Exp/Cntr=0.3,0.1

Type RM Length L Ch R = 1 ,7200    ,76,76,76
BEGIN DESCRIPTION:
UNT019 IN NURI 12.0
END DESCRIPTION:
XS GIS Cut Line= 3
      2295687.69     13304996.87      2294269.04     13305615.53
      2293930.13      13305892.7
#Sta/Elev= 30
  3721.1  204.08  3754.6  202.95  3904.9  196.84  3928.3   196.7  3939.3  195.64
  3980.6  193.89  4108.6   189.7    4114  188.39  4129.6  187.84  4146.5  188.06
  4168.4  186.74  4178.8  187.31  4266.5  184.92  4382.5   183.8  4550.2  183.71
  4746.6   184.8  4779.1  183.65  4831.3  183.08  4953.8  183.59  4997.5  181.96
  5026.6  181.94  5029.3  181.44  5032.6  181.94  5105.3  183.63  5370.5  191.57
  5541.3  197.73  5547.8  197.38  5597.3  199.29  5646.8  202.91  5706.6  205.84
#Mann= 5 ,-1 , 0
  3721.1     .05       0  3754.6      .1       0  4129.6     .05       0
  5026.6     .03       0  5032.6     .05       0
Bank Sta=4953.8,5105.3
XS Rating Curve= 0 ,0
Exp/Cntr=0.3,0.1