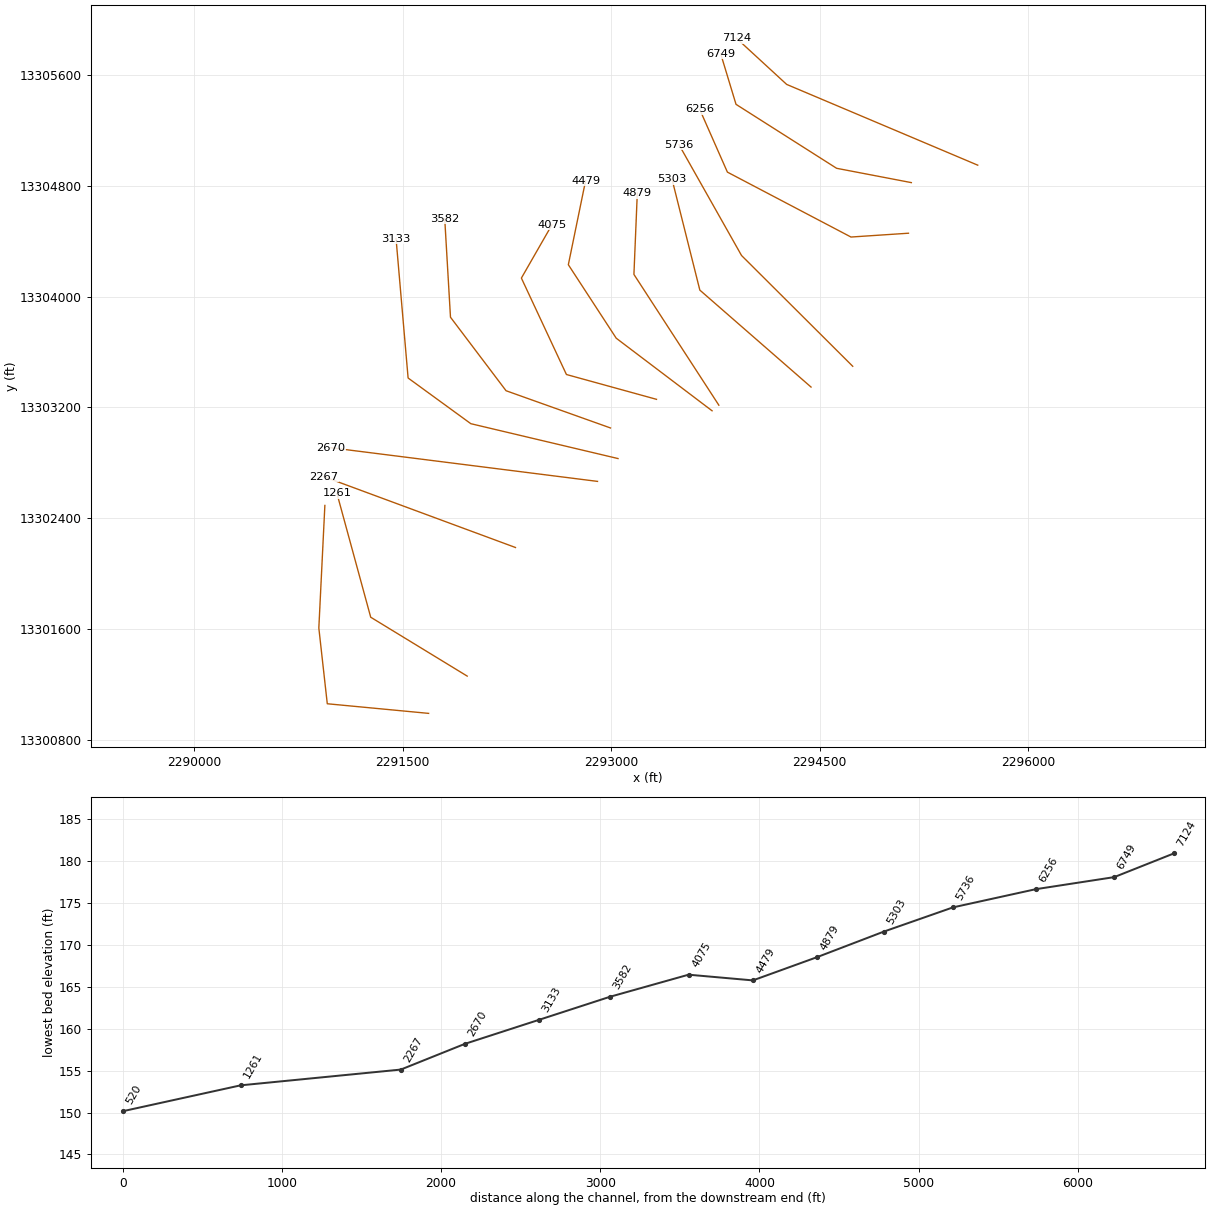
HEC-RAS study UNT019 IN NURI.prj: UNT019 IN NURI Base Level Engineering

--- UNT019 IN NURI.g01 (geometry) --- (continued)

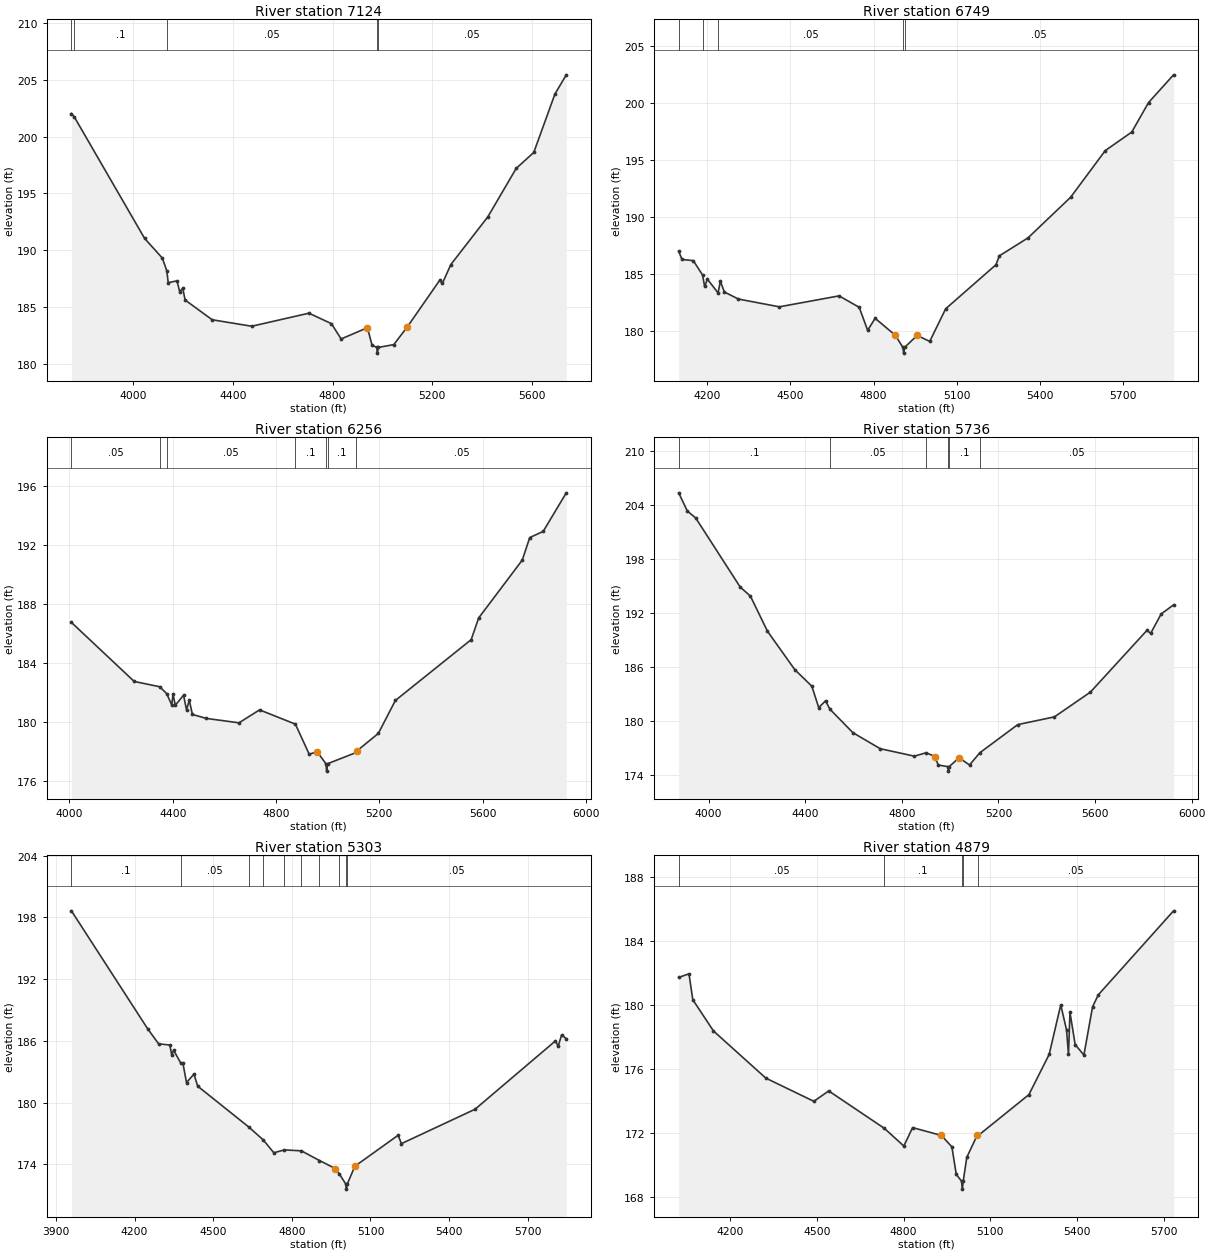
Type RM Length L Ch R = 1 ,7124    ,375,375,375
BEGIN DESCRIPTION:
Mapping XS b686b07a
END DESCRIPTION:
XS GIS Cut Line= 3
      2295637.37     13304949.15      2294262.37     13305532.48
      2293901.97     13305865.16
#Sta/Elev= 30
  3753.1  202.04  3764.7  201.74  4046.6  191.03  4117.6   189.3  4135.8  188.16
  4141.2  187.13  4176.4  187.29  4187.2  186.34  4199.4  186.64    4209   185.6
  4317.6  183.86    4476  183.29  4705.3  184.44  4795.5  183.52  4834.5  182.17
    4940  183.16  4958.3  181.63  4977.2  181.42    4980  180.92  4983.2  181.42
  5045.5  181.67  5099.7  183.23    5230  187.35  5240.3  187.06  5274.4  188.73
  5422.9  192.94  5536.3   197.2  5606.9  198.61  5691.7  203.76  5737.2  205.45
#Mann= 5 ,-1 , 0
  3753.1     .05       0  3764.7      .1       0  4135.8     .05       0
  4977.2     .03       0  4983.2     .05       0
Bank Sta=4940,5099.7
XS Rating Curve= 0 ,0
Exp/Cntr=0.3,0.1

Type RM Length L Ch R = 1 ,6749    ,493,493,493
BEGIN DESCRIPTION:
UNT019 IN NURI 11.0
END DESCRIPTION:
XS GIS Cut Line= 4
      2295159.61     13304823.18      2294621.88     13304926.59
      2293897.98     13305388.51      2293787.99     13305752.86
#Sta/Elev= 30
  4096.4  187.02  4108.5   186.3  4149.2   186.2  4182.6  184.94    4190  183.94
  4200.3  184.57  4238.5  183.37  4247.1  184.39  4261.3  183.45  4312.2  182.83
  4459.9  182.15  4675.5  183.11  4748.2  182.11  4778.7  180.09  4805.8  181.14
  4878.5  179.66    4906  178.59  4908.7  178.09    4912  178.59  4957.3  179.64
  5002.9  179.12  5060.5  181.98    5242  185.84  5254.2  186.62  5357.5  188.19
  5511.4  191.75  5636.8  195.85  5732.3  197.47    5793  200.06  5883.3  202.49
#Mann= 5 ,-1 , 0
  4096.4     .05       0  4182.6      .1       0  4238.5     .05       0
    4906     .03       0    4912     .05       0
Bank Sta=4878.5,4957.3
XS Rating Curve= 0 ,0
Exp/Cntr=0.3,0.1

Type RM Length L Ch R = 1 ,6256    ,520,520,520
BEGIN DESCRIPTION:
UNT019 IN NURI 10.0
END DESCRIPTION:
XS GIS Cut Line= 4
      2295138.96     13304457.78      2294725.29      13304430.2
      2293835.93     13304899.02      2293636.46     13305352.98
#Sta/Elev= 30
  4007.9  186.75    4251  182.74  4349.9  182.38  4376.9  181.91  4396.3  181.14
  4401.3   181.9    4410  181.12  4442.1  181.81  4453.6   180.8  4464.1  181.48
  4476.3   180.5  4530.2  180.23  4656.7  179.93  4736.3  180.81  4875.1  179.84
  4928.4   177.8  4959.4  177.96  4993.3  177.15    4996  176.65  4999.3  177.15
  5111.1  177.92  5113.6  178.03  5196.1  179.21  5262.1  181.45  5555.6  185.58
  5584.4  187.05  5753.2  190.98  5782.2  192.51  5834.3  192.93  5923.7  195.55
#Mann= 7 ,-1 , 0
  4007.9     .05       0  4349.9      .1       0  4376.9     .05       0
  4875.1      .1       0  4993.3     .07       0  4999.3      .1       0
  5111.1     .05       0
Bank Sta=4959.4,5113.6
XS Rating Curve= 0 ,0
Exp/Cntr=0.3,0.1

Type RM Length L Ch R = 1 ,5736    ,433,433,433
BEGIN DESCRIPTION:
UNT019 IN NURI 9.0
END DESCRIPTION:
XS GIS Cut Line= 3
      2294737.72     13303496.86      2293937.72     13304296.85
      2293487.74     13305096.81
#Sta/Elev= 30
  3875.9  205.36  3911.3  203.36  3946.6  202.56  4130.5  194.91  4172.9   193.9
  4243.6     190  4356.7  185.74  4427.4   183.9  4455.7  181.53    4484  182.28
  4502.3  181.35  4597.1  178.75  4710.3  176.97  4851.7  176.14  4900.9  176.52
  4936.6   176.1  4950.7  175.16  4990.1  174.98  4992.9  174.48  4996.1  174.98
  5036.9  175.97  5080.3  175.16    5123  176.52  5279.8  179.64  5431.8   180.5
  5580.9  183.25  5814.6  190.09  5830.5  189.78  5873.8  191.92  5925.1  192.93
#Mann= 6 ,-1 , 0
  3875.9      .1       0  4502.3     .05       0  4900.9      .1       0
  4990.1     .07       0  4996.1      .1       0    5123     .05       0
Bank Sta=4936.6,5036.9
XS Rating Curve= 0 ,0
Exp/Cntr=0.3,0.1

Type RM Length L Ch R = 1 ,5303    ,424,424,424
BEGIN DESCRIPTION:
UNT019 IN NURI 8.0
END DESCRIPTION:
XS GIS Cut Line= 3
      2294437.72     13303346.85      2293637.72     13304046.85
      2293437.73     13304846.82
#Sta/Elev= 30
  3959.3  198.63  4250.2  187.17    4292  185.71  4334.7   185.6  4342.3  184.59
  4348.9  185.11  4376.2  183.85  4384.5  183.85  4398.3  181.95  4426.7  182.77
    4441   181.6  4637.4   177.6  4691.4  176.37  4731.4  175.13  4771.4  175.41
  4836.5  175.32  4905.3  174.38  4965.8   173.6  4981.5  173.07  5005.6   172.1
  5008.3   171.6  5011.6   172.1  5040.4  173.82  5205.3  176.83  5218.2  176.02
    5499  179.36  5805.7     186    5816  185.47  5828.9  186.57  5846.9  186.22
#Mann= 10 ,-1 , 0
  3959.3      .1       0  4376.2     .05       0  4637.4      .1       0
  4691.4     .05       0  4771.4      .1       0  4836.5     .05       0
  4905.3      .1       0  4981.5     .05       0  5005.6     .04       0
  5011.6     .05       0
Bank Sta=4965.8,5040.4
XS Rating Curve= 0 ,0
Exp/Cntr=0.3,0.1

Type RM Length L Ch R = 1 ,4879    ,400,400,400
BEGIN DESCRIPTION:
UNT019 IN NURI 7.0
END DESCRIPTION:
XS GIS Cut Line= 3
      2293774.51     13303215.79      2293163.37     13304160.28
      2293187.72     13304746.81
#Sta/Elev= 30
  4022.1  181.73  4057.7  181.96    4071  180.34  4142.5  178.39  4323.5  175.45
  4489.7     174  4541.1  174.65  4733.9  172.31    4801  171.21  4831.3  172.36
    4931  171.87  4967.2  171.16  4982.4  169.44  5000.5  169.02  5003.3  168.52
  5006.5  169.02  5018.7   170.5  5054.9  171.89  5058.6  171.87  5233.7  174.42
  5303.8  176.93  5343.8  180.02  5363.8  178.46  5370.6  176.93  5375.7  179.55
  5393.8  177.54  5423.9  176.89  5453.9   179.9  5473.9  180.65  5734.1  185.89
#Mann= 5 ,-1 , 0
  4022.1     .05       0  4733.9      .1       0  5000.5     .07       0
  5006.5      .1       0  5058.6     .05       0
Bank Sta=4931,5054.9
XS Rating Curve= 0 ,0
Exp/Cntr=0.3,0.1

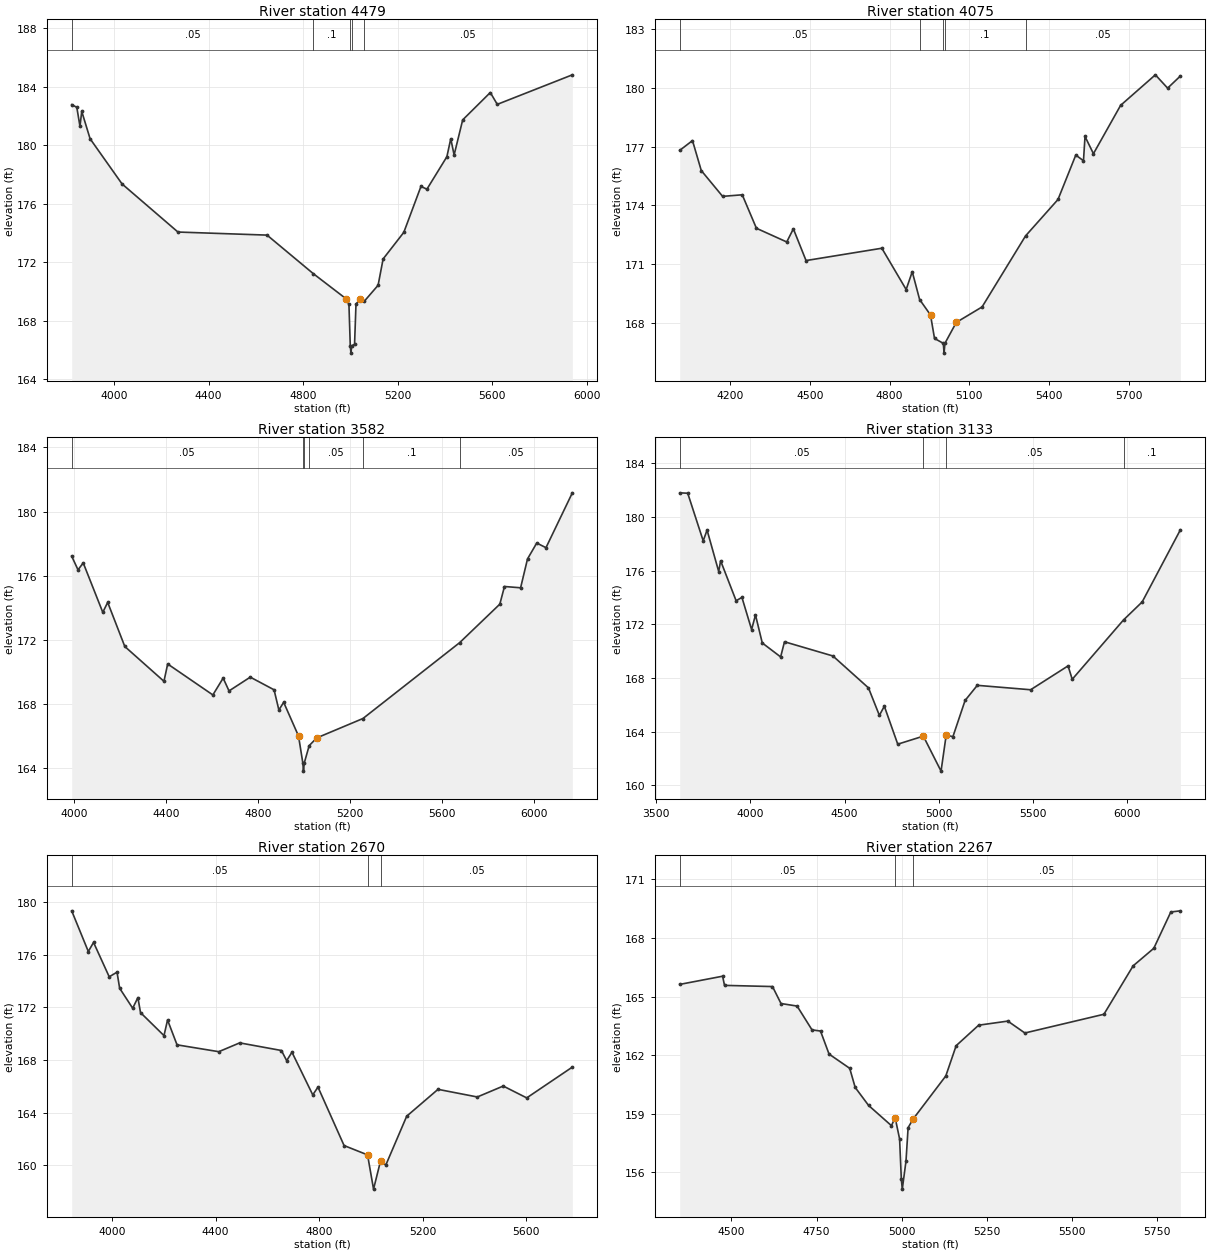
Type RM Length L Ch R = 1 ,4479    ,404,404,404
BEGIN DESCRIPTION:
UNT019 IN NURI 6.0
END DESCRIPTION:
XS GIS Cut Line= 4
       2293725.6     13303175.45      2293036.19     13303699.41
      2292691.48     13304230.27      2292815.56     13304836.92
#Sta/Elev= 30
    3821  182.76  3842.6  182.58    3856  181.28  3863.5   182.3  3898.8  180.43
    4034  177.34  4270.5  174.05  4647.5  173.84  4842.7  171.21  4981.5  169.49
  4993.9  169.11  4999.6  166.27  5002.4  165.77  5005.6  166.27  5017.7  166.37
  5023.7   169.1  5038.9  169.45  5058.5  169.31  5117.3  170.41  5138.5  172.21
  5226.1  174.03  5298.6  177.17  5323.8  176.98  5408.3   179.2  5424.7  180.43
  5438.9  179.32  5475.2  181.72    5592  183.59  5621.5  182.78  5939.1   184.8
#Mann= 5 ,-1 , 0
    3821     .05       0  4842.7      .1       0  4999.6     .07       0
  5005.6      .1       0  5058.5     .05       0
Bank Sta=4981.5,5038.9
XS Rating Curve= 0 ,0
Exp/Cntr=0.3,0.1

Type RM Length L Ch R = 1 ,4075    ,493,493,493
BEGIN DESCRIPTION:
UNT019 IN NURI 5.0
END DESCRIPTION:
XS GIS Cut Line= 4
      2293325.77     13303258.17      2292677.69     13303437.42
      2292353.65     13304133.75      2292573.52     13304518.51
#Sta/Elev= 30
  4010.3  176.81  4058.3  177.31  4091.3  175.78  4171.6  174.46  4245.5  174.54
  4298.8  172.83  4412.9  172.13  4437.8   172.8  4485.5  171.18  4770.7  171.81
  4862.2   169.7  4885.1  170.61  4912.8  169.19  4953.8   168.4  4968.9   167.2
    5002  166.95  5004.8  166.45    5008  166.95  5050.8  168.02  5147.8  168.81
  5311.4  172.44  5433.4   174.3  5500.4  176.57  5529.3  176.28  5535.1  177.52
  5566.8  176.64    5669  179.11  5799.8  180.67  5845.9  179.99  5893.9  180.61
#Mann= 5 ,-1 , 0
  4010.3     .05       0  4912.8      .1       0    5002     .07       0
    5008      .1       0  5311.4     .05       0
Bank Sta=4953.8,5050.8
XS Rating Curve= 0 ,0
Exp/Cntr=0.3,0.1

Type RM Length L Ch R = 1 ,3582    ,449,449,449
BEGIN DESCRIPTION:
UNT019 IN NURI 4.0
END DESCRIPTION:
XS GIS Cut Line= 4
      2292994.87     13303051.33      2292243.35     13303320.22
      2291843.48     13303851.08      2291802.11     13304561.19
#Sta/Elev= 30
  3990.7  177.22  4018.1  176.37  4040.8   176.8  4125.7  173.72    4147  174.34
  4221.3  171.59  4391.3  169.42  4407.5   170.5  4603.7  168.57  4648.4  169.62
  4673.9  168.82  4766.2  169.68  4869.5  168.89  4890.4  167.63  4911.2  168.11
  4975.7  166.01  4994.5  164.32  4997.2  163.82  5000.5  164.32    5022  165.41
  5054.8  165.89  5255.5   167.1  5675.5  171.83  5849.9  174.23    5870  175.33
  5940.1  175.25  5970.1  177.05  6010.2  178.04  6050.3  177.75  6164.8  181.17
#Mann= 6 ,-1 , 0
  3990.7     .05       0  4994.5     .07       0  5000.5     .05       0
    5022     .05       0  5255.5      .1       0  5675.5     .05       0
Bank Sta=4975.7,5054.8
XS Rating Curve= 0 ,0
Exp/Cntr=0.3,0.1

Type RM Length L Ch R = 1 ,3133    ,463,463,463
BEGIN DESCRIPTION:
UNT019 IN NURI 3.0
END DESCRIPTION:
XS GIS Cut Line= 4
      2293048.97     13302830.44      2291989.95     13303082.17
      2291538.56     13303412.04      2291451.75       13304419.
#Sta/Elev= 30
  3624.6  181.81    3667  181.78  3749.2  178.23  3769.8  179.03  3831.5  175.94
  3841.7  176.74    3924  173.76  3954.8  174.01  4006.2  171.61  4026.8   172.7
  4062.9  170.61  4160.4  169.57  4180.9   170.7  4437.9  169.64  4626.7  167.26
  4684.6  165.21    4711  165.89  4782.2  163.06  4918.1  163.66  5012.1  161.05
  5039.4  163.74  5075.1  163.62  5139.7  166.32  5204.6  167.45  5487.8  167.12
  5686.5   168.9  5708.6   167.9  5981.1  172.33    6080  173.67  6282.9  179.05
#Mann= 4 ,-1 , 0
  3624.6     .05       0  4918.1     .03       0  5039.4     .05       0
  5981.1      .1       0
Bank Sta=4918.1,5039.4
XS Rating Curve= 0 ,0
Exp/Cntr=0.3,0.1

Type RM Length L Ch R = 1 ,2670    ,403,403,403
BEGIN DESCRIPTION:
UNT019 IN NURI 2.0
END DESCRIPTION:
XS GIS Cut Line= 2
      2292901.43      13302665.5      2290982.97     13302908.57
#Sta/Elev= 30
  3844.3  179.34  3908.5  176.25  3928.7  176.94  3989.2  174.33  4019.4  174.68
  4029.5  173.46  4079.9  171.94    4100  172.75  4110.1  171.61  4200.8  169.86
  4214.5  171.05  4251.2  169.16  4412.5  168.64  4493.2  169.31  4654.4  168.73
  4674.6  167.96  4695.1   168.6  4775.4  165.36  4795.6  165.95  4896.4  161.51
  4987.1   160.8  5010.2   158.2  5037.5  160.36  5057.6  160.03  5138.3  163.74
  5259.2  165.78    5411   165.2  5511.2  166.03  5601.9  165.13  5778.1  167.47
#Mann= 3 , 0 , 0
  3844.3     .05       0  4987.1     .03       0  5037.5     .05       0
Bank Sta=4987.1,5037.5
XS Rating Curve= 0 ,0
Exp/Cntr=0.3,0.1

Type RM Length L Ch R = 1 ,2267    ,1006,1006,1006
BEGIN DESCRIPTION:
Mapping XS f2ce0bdd
END DESCRIPTION:
XS GIS Cut Line= 2
       2292311.1     13302188.09      2290931.79     13302699.91
#Sta/Elev= 30
    4348  165.62    4474  166.04  4479.6  165.57  4620.6  165.51  4645.6  164.64
  4692.9  164.51  4736.7  163.29  4761.7  163.23  4786.8  162.05  4847.5  161.32
  4863.6  160.34  4902.9  159.42  4970.2  158.38  4980.9   158.8  4994.1   157.7
  4999.2  155.63    5002  155.13  5012.9  156.57  5019.1  158.28  5034.2  158.73
  5129.9  160.93  5160.3  162.48  5226.4  163.53  5312.1  163.74  5362.2  163.13
  5594.5  164.09  5680.3  166.57  5741.1  167.47  5791.1  169.33  5819.2  169.39
#Mann= 3 , 0 , 0
    4348     .05       0  4980.9     .03       0  5034.2     .05       0
Bank Sta=4980.9,5034.2
XS Rating Curve= 0 ,0
Exp/Cntr=0.3,0.1

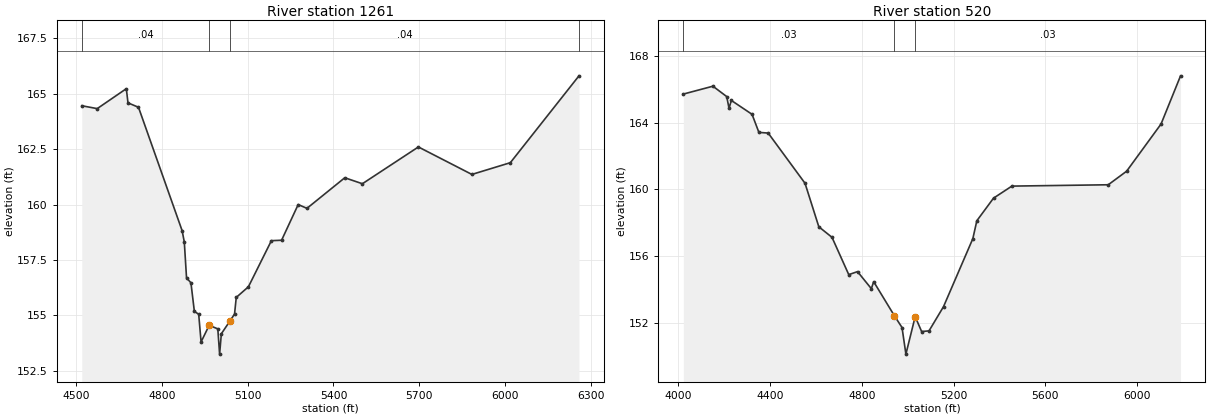
Type RM Length L Ch R = 1 ,1261    ,741,741,741
BEGIN DESCRIPTION:
Mapping XS 4330f8b1
END DESCRIPTION:
XS GIS Cut Line= 3
      2291963.88     13301259.27      2291269.46      13301684.6
       2291026.4     13302578.73
#Sta/Elev= 30
  4518.7  164.46  4572.8  164.33  4674.7  165.23  4680.5  164.59  4717.3  164.39
  4870.1  158.82  4877.7  158.31  4885.5  156.69  4900.9  156.47  4912.9  155.18
  4928.1  155.05  4936.4   153.8  4964.8  154.55    4995  154.39  5001.3  153.25
  5007.4  154.17  5038.3  154.76  5053.6  155.06  5059.6  155.81  5102.2  156.29
  5182.6  158.37  5218.3  158.39  5276.4     160  5307.2  159.83  5439.6  161.21
  5501.2  160.94  5697.3   162.6  5884.6  161.36  6019.3  161.89  6259.6  165.81
#Mann= 4 ,-1 , 0
  4518.7     .04       0  4964.8     .03       0  5038.3     .04       0
  6259.6     .05       0
Bank Sta=4964.8,5038.3
XS Rating Curve= 0 ,0
Exp/Cntr=0.3,0.1

Type RM Length L Ch R = 1 ,520     ,0,0,0
BEGIN DESCRIPTION:
UNT019 IN NURI 1.0
END DESCRIPTION:
XS GIS Cut Line= 4
      2291686.11     13300990.16      2290956.96      13301059.6
       2290896.2     13301606.48       2290939.6     13302491.83
#Sta/Elev= 30
  4021.3   165.7  4150.3  166.17  4210.5  165.55  4220.6  164.85  4230.6  165.32
    4321  164.49  4350.9  163.41  4391.4  163.37  4552.1  160.37  4612.3  157.77
  4669.8  157.14  4742.9  154.91  4781.2  155.09  4841.5  154.07  4851.6  154.49
  4942.1  152.45  4975.3  151.75  4992.2  150.16  5032.7   152.4  5060.8  151.51
  5093.1  151.55  5156.4     153  5284.2  157.06  5301.7  158.13  5374.4  159.48
  5454.5   160.2    5875  160.28  5955.1  161.09  6105.3  163.91  6190.4  166.79
#Mann= 3 , 0 , 0
  4021.3     .03       0  4942.1    .025       0  5032.7     .03       0
Bank Sta=4942.1,5032.7
XS Rating Curve= 0 ,0
Exp/Cntr=0.3,0.1

Chan Stop Cuts=-1
Use User Specified Reach Order=0
Composite Channel Slope=5