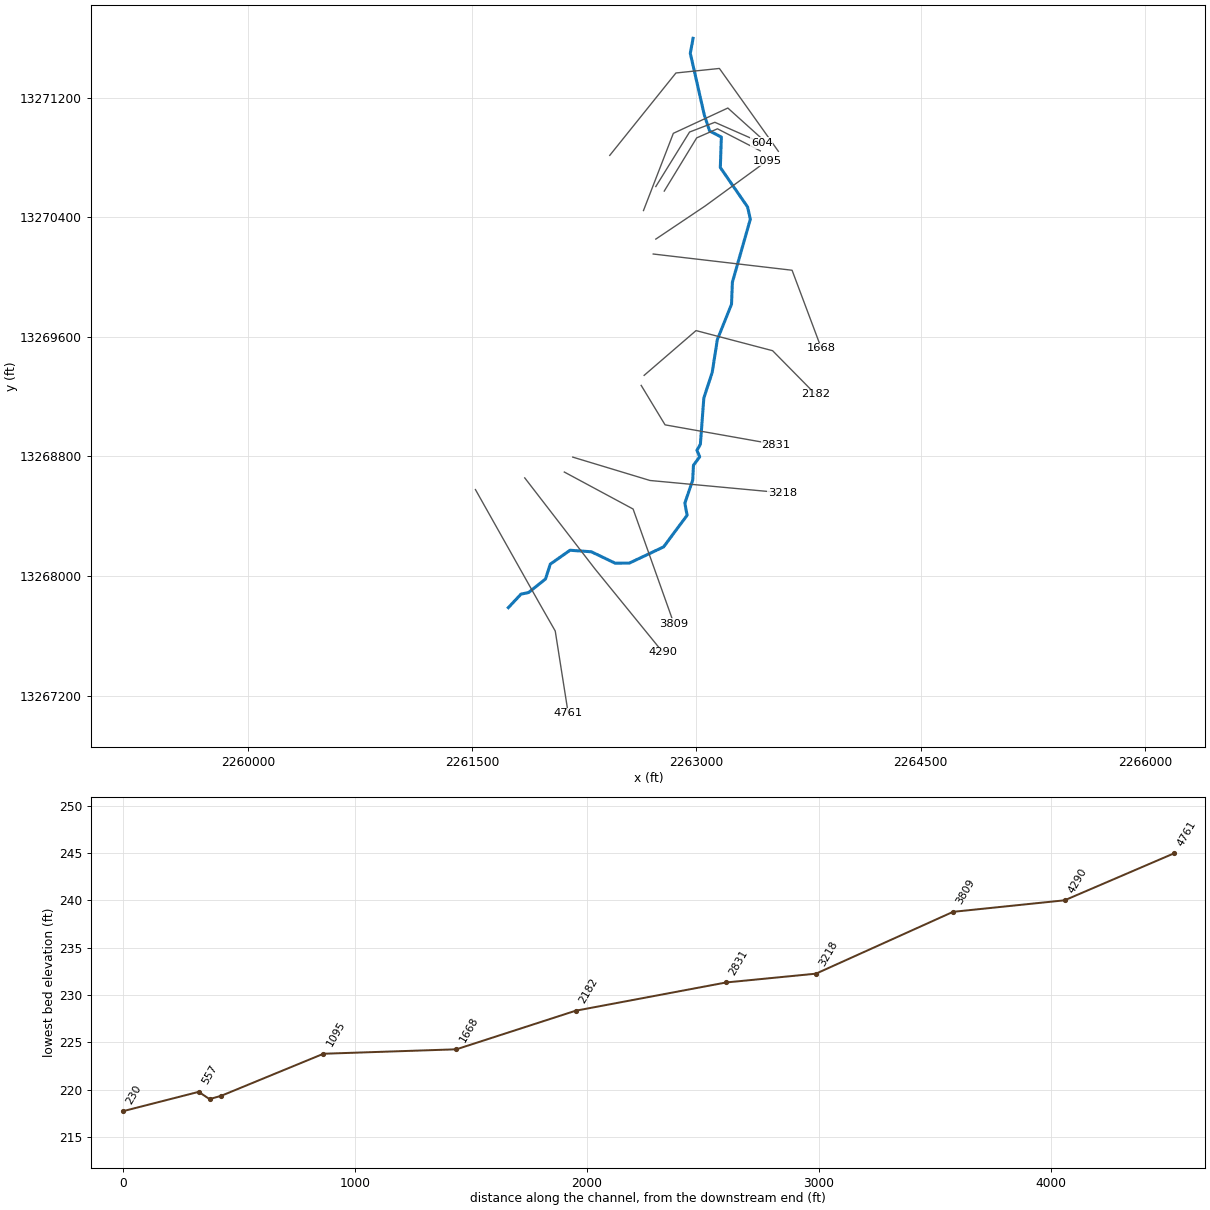
--- UNT021 IN NURI.prj (project) ---

Proj Title=UNT021 IN NURI Base Level Engineering
Current Plan=p01
Default Exp/Contr=0.3,0.1
English Units
Geom File=g01
Flow File=f01
Plan File=p01
Y Axis Title=Elevation
X Axis Title(PF)=Main Channel Distance
X Axis Title(XS)=Station
BEGIN DESCRIPTION:
UNT021 IN NURI
END DESCRIPTION:
DSS Export Rating Curves= 0
DSS Export Rating Curve Sorted= 0
DSS Export Volume Flow Curves= 0
DXF OffsetX= 0
DXF OffsetY= 0
DXF ScaleX= 1
DXF ScaleY= 10

--- UNT021 IN NURI.p01 (plan) ---

Plan Title=Multiple Run
Short Identifier=Multiple
Geom File=g01
Flow File=f01
Subcritical Flow
K Sum by GR= 0
Std Step Tol= 0.01
Critical Tol= 0.01
Num of Std Step Trials= 20
Max Error Tol= 0.3
Flow Tol Ratio= 0.001
Split Flow NTrial= 30
Split Flow Tol= 0.02
Split Flow Ratio= 0.02
Log Output Level= 0
Friction Slope Method= 1
Unsteady Friction Slope Method= 2
Unsteady Bridges Friction Slope Method= 1
Parabolic Critical Depth
Global Vel Dist=  1 , 1 , 1
Global Log Level= 0
CheckData=True
Encroach Param= -1, 0, 0, 0
BEGIN DESCRIPTION:
Multiple Run
END DESCRIPTION:

--- UNT021 IN NURI.f01 (steady flow) ---

Flow Title=Multiple
Number of Profiles=7
Profile Names=10-year,25-year,50-year,1pct_min,100-year,1pct_plu,500-year
River Rch & RM= UNT021 IN NURI,Reach-1,4761
     245     343     427     391     529     715     824
River Rch & RM= UNT021 IN NURI,Reach-1,3809
     276     388     483     443     599     810     934
Boundary for River Rch & Prof#=UNT021 IN NURI,Reach-1,1
Up Type=0
Dn Type=3
Dn Slope=0.005
Boundary for River Rch & Prof#=UNT021 IN NURI,Reach-1,2
Up Type=0
Dn Type=3
Dn Slope=0.005
Boundary for River Rch & Prof#=UNT021 IN NURI,Reach-1,3
Up Type=0
Dn Type=3
Dn Slope=0.005
Boundary for River Rch & Prof#=UNT021 IN NURI,Reach-1,4
Up Type=0
Dn Type=3
Dn Slope=0.005
Boundary for River Rch & Prof#=UNT021 IN NURI,Reach-1,5
Up Type=0
Dn Type=3
Dn Slope=0.005
Boundary for River Rch & Prof#=UNT021 IN NURI,Reach-1,6
Up Type=0
Dn Type=3
Dn Slope=0.005
Boundary for River Rch & Prof#=UNT021 IN NURI,Reach-1,7
Up Type=0
Dn Type=3
Dn Slope=0.005

--- UNT021 IN NURI.g01 (geometry) ---

Geom Title=Existing Conditions
Program Version=4.10

River Reach=UNT021 IN NURI  ,Reach-1
Reach XY= 30
      2261742.03     13267788.83      2261826.78     13267879.32
      2261876.47     13267889.49      2261990.61      13267980.6
      2262022.47     13268079.72      2262154.83     13268172.64
      2262297.16     13268162.53      2262456.46     13268086.15
       2262551.6     13268086.84      2262780.71      13268195.2
      2262937.72     13268406.86      2262922.64     13268487.13
      2262975.26     13268642.66      2262980.19     13268741.15
      2263022.21     13268797.98      2263003.34     13268841.29
      2263026.45     13268880.95      2263049.63     13269191.03
      2263105.57     13269362.19      2263139.85     13269580.97
      2263234.75     13269818.12      2263240.63     13269965.59
      2263360.68     13270387.14      2263341.97     13270469.36
      2263159.91     13270732.61      2263166.75     13270936.41
      2263088.44     13270976.98      2263052.89     13271083.63
      2262958.91     13271496.87      2262977.72     13271596.85

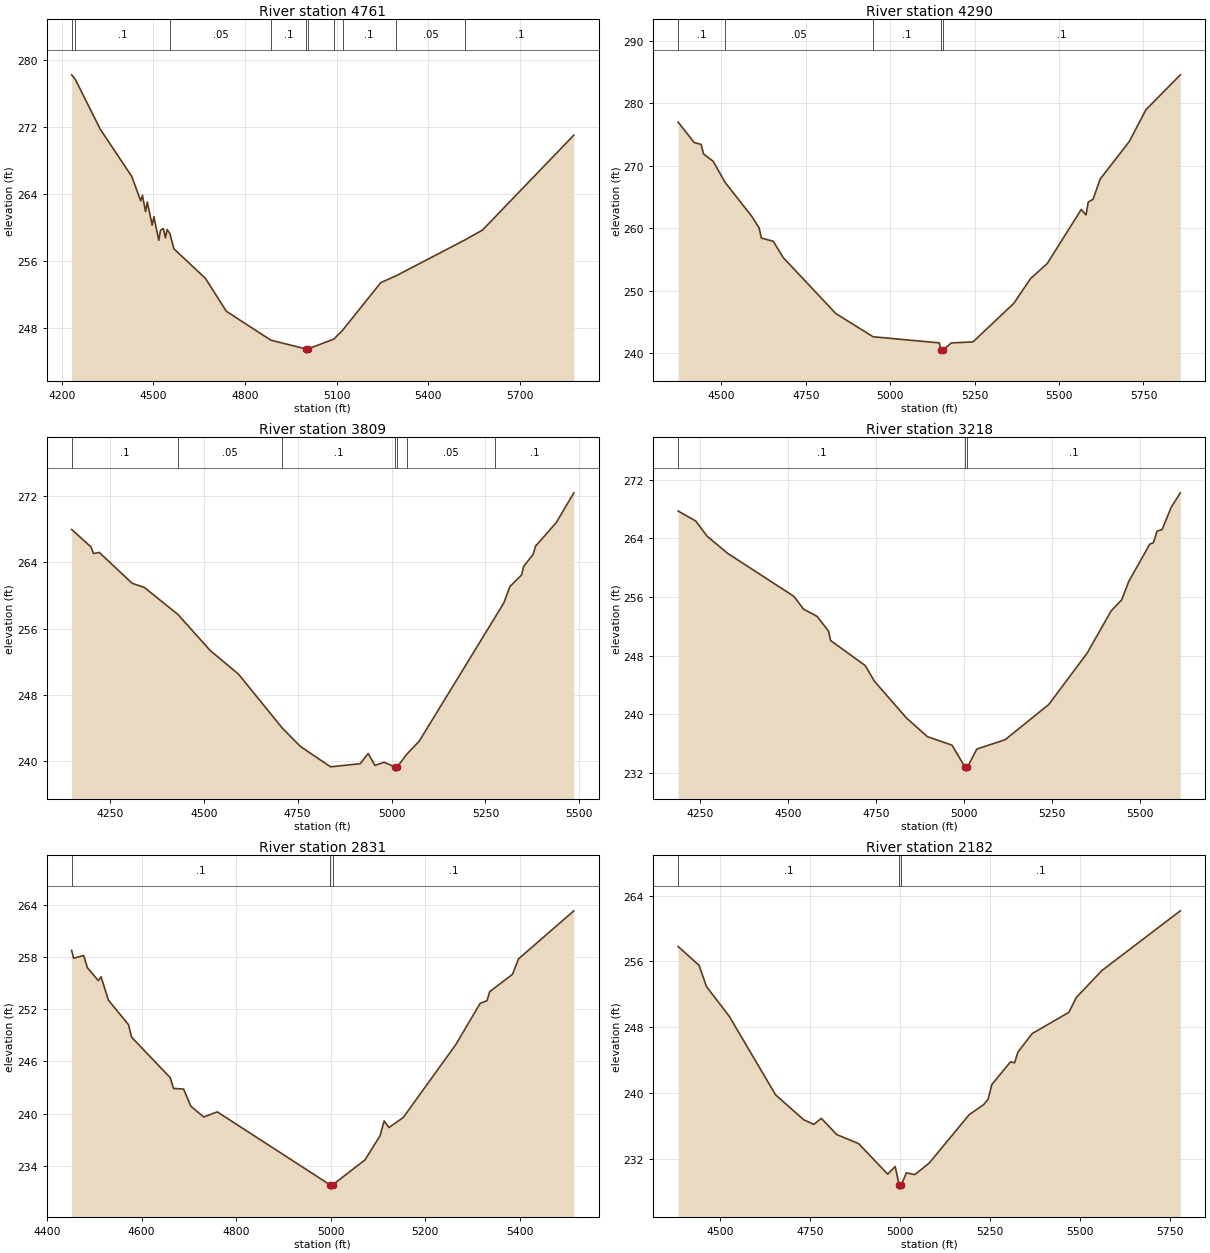
Type RM Length L Ch R = 1 ,4761    ,471,471,471
BEGIN DESCRIPTION:
UNT021 IN NURI 10.0
END DESCRIPTION:
XS GIS Cut Line= 4
      2261521.81     13268578.63      2261951.51     13267814.72
      2262055.68     13267632.43      2262142.43     13267081.54
#Sta/Elev= 30
  4232.3  278.22  4244.3  277.67  4326.1  271.72  4429.4  266.07  4458.3  263.16
    4464  263.84  4474.2  261.88    4480  263.03  4495.9  260.27  4501.6  261.27
  4517.6  258.45  4523.3  259.65  4532.6  259.87  4539.3  258.75    4545  259.74
  4553.8  259.27  4567.1  257.44  4670.3  253.91  4738.8  249.98  4884.8  246.52
  5000.1  245.48  5002.8  244.98  5006.1  245.48  5090.8  246.66  5119.1   247.7
  5244.5  253.41  5293.1  254.19  5520.9  258.52  5577.4  259.68  5876.4  271.02
#Mann= 10 ,-1 , 0
  4232.3     .05       0  4244.3      .1       0  4553.8     .05       0
  4884.8      .1       0  5000.1     .07       0  5006.1      .1       0
  5090.8     .05       0  5119.1      .1       0  5293.1     .05       0
  5520.9      .1       0
Bank Sta=5000.1,5006.1
XS Rating Curve= 0 ,0
Exp/Cntr=0.3,0.1

Type RM Length L Ch R = 1 ,4290    ,481,481,481
BEGIN DESCRIPTION:
UNT021 IN NURI 9.0
END DESCRIPTION:
XS GIS Cut Line= 3
      2261851.69     13268656.73      2262320.43      13268049.1
      2262775.06     13267490.56
#Sta/Elev= 30
  4371.6  277.02    4419  273.75  4439.8  273.43  4447.2   271.9  4475.2  270.75
  4511.2  267.33  4589.3  261.96  4611.4  260.09  4618.3  258.44  4653.6  257.93
  4682.6  255.34  4838.7  246.36  4949.3  242.64  5145.5  241.66  5150.4  240.52
  5153.2  240.02  5156.4  240.52  5180.7  241.65  5245.1  241.82    5366  247.99
  5415.5  251.95  5465.1  254.37  5565.7  263.02    5580  262.15  5586.5  264.21
  5600.8  264.67  5621.7  267.88  5707.9  273.89  5757.4  278.99  5859.2  284.58
#Mann= 5 ,-1 , 0
  4371.6      .1       0  4511.2     .05       0  4949.3      .1       0
  5150.4     .07       0  5156.4      .1       0
Bank Sta=5150.4,5156.4
XS Rating Curve= 0 ,0
Exp/Cntr=0.3,0.1

Type RM Length L Ch R = 1 ,3809    ,591,591,591
BEGIN DESCRIPTION:
UNT021 IN NURI 8.0
END DESCRIPTION:
XS GIS Cut Line= 3
      2262116.42     13268695.81      2262576.51      13268448.4
      2262849.63     13267681.05
#Sta/Elev= 30
  4148.3  267.97  4199.9  265.85  4206.5  265.06  4221.8   265.2  4309.4  261.47
  4341.9  260.97  4431.4   257.7  4517.2  253.36  4592.6   250.5  4709.4  243.98
  4757.3  241.78  4837.6  239.32  4916.5   239.7  4937.7  240.93  4955.6  239.49
  4980.2  239.87    5009   239.3  5011.7   238.8    5015   239.3  5040.2  240.83
  5073.6  242.42  5275.4  257.36  5298.6  259.08    5315  261.08  5345.8  262.46
  5351.7  263.52  5376.7  264.96  5383.5  265.97  5438.3  268.79  5485.2  272.39
#Mann= 7 ,-1 , 0
  4148.3      .1       0  4431.4     .05       0  4709.4      .1       0
    5009     .07       0    5015      .1       0  5040.2     .05       0
  5275.4      .1       0
Bank Sta=5009,5015
XS Rating Curve= 0 ,0
Exp/Cntr=0.3,0.1

Type RM Length L Ch R = 1 ,3218    ,387,387,387
BEGIN DESCRIPTION:
UNT021 IN NURI 7.0
END DESCRIPTION:
XS GIS Cut Line= 3
      2262172.85     13268795.63      2262689.36     13268639.37
      2263573.71     13268557.01
#Sta/Elev= 30
  4187.1  267.71  4236.9  266.36  4269.9  264.26    4328  261.94  4516.1  256.09
  4543.8  254.34    4582  253.36  4614.9  251.34  4620.5  250.07    4719  246.65
  4745.2  244.52  4835.6  239.54  4895.8  236.96  4966.1  235.79  5003.3  232.76
    5006  232.26  5009.3  232.76  5036.4  235.27  5116.8  236.54  5240.7  241.33
  5349.9  248.33  5418.1  254.09  5448.2   255.6  5468.3  258.11  5528.5  263.22
  5538.6  263.39  5548.6  264.96  5563.2  265.19  5588.8   268.2  5614.9  270.19
#Mann= 3 ,-1 , 0
  4187.1      .1       0  5003.3     .07       0  5009.3      .1       0
Bank Sta=5003.3,5009.3
XS Rating Curve= 0 ,0
Exp/Cntr=0.3,0.1

Type RM Length L Ch R = 1 ,2831    ,649,649,649
BEGIN DESCRIPTION:
UNT021 IN NURI 6.0
END DESCRIPTION:
XS GIS Cut Line= 3
      2262630.57     13269275.37      2262790.27     13269011.51
      2263533.03     13268879.62
#Sta/Elev= 30
  4451.8  258.73  4455.9  257.84  4477.3  258.15  4485.1  256.75  4508.3  255.27
  4514.1   255.7  4529.6  253.03  4572.3   250.2  4578.6  248.78  4660.5  244.12
  4667.4  242.89  4688.7  242.82  4704.2  240.84  4731.4  239.61    4760   240.2
  4998.4  231.83  5001.1  231.33  5004.4  231.83  5072.5  234.68  5104.7  237.48
  5113.1  239.16  5123.3   238.4  5153.7  239.56  5265.5  247.98  5316.2  252.65
  5330.9  252.97  5336.5     254  5384.8  255.99  5397.5  257.76  5514.6  263.28
#Mann= 3 ,-1 , 0
  4451.8      .1       0  4998.4     .07       0  5004.4      .1       0
Bank Sta=4998.4,5004.4
XS Rating Curve= 0 ,0
Exp/Cntr=0.3,0.1

Type RM Length L Ch R = 1 ,2182    ,514,514,514
BEGIN DESCRIPTION:
UNT021 IN NURI 5.0
END DESCRIPTION:
XS GIS Cut Line= 4
      2262650.32     13269342.52      2262997.52     13269641.98
      2263509.67     13269507.43      2263796.11     13269216.65
#Sta/Elev= 30
  4383.5  257.81  4441.6  255.54  4462.5  252.94  4526.1  249.31  4654.4   239.8
  4732.3  236.78  4760.8   236.2  4781.7  236.94  4824.5  234.97  4885.3  233.87
  4966.3  230.16    4987  231.09  4998.2  228.84  5000.9  228.34  5004.2  228.84
    5018  230.32  5041.5   230.1  5081.9  231.52  5192.6  237.38    5233  238.61
  5245.4  239.28  5255.8  241.05  5307.5   243.8  5318.9  243.69  5328.2  244.98
  5367.9  247.24  5469.6  249.81  5490.8  251.63  5561.5  254.89  5779.7  262.15
#Mann= 3 ,-1 , 0
  4383.5      .1       0  4998.2     .07       0  5004.2      .1       0
Bank Sta=4998.2,5004.2
XS Rating Curve= 0 ,0
Exp/Cntr=0.3,0.1

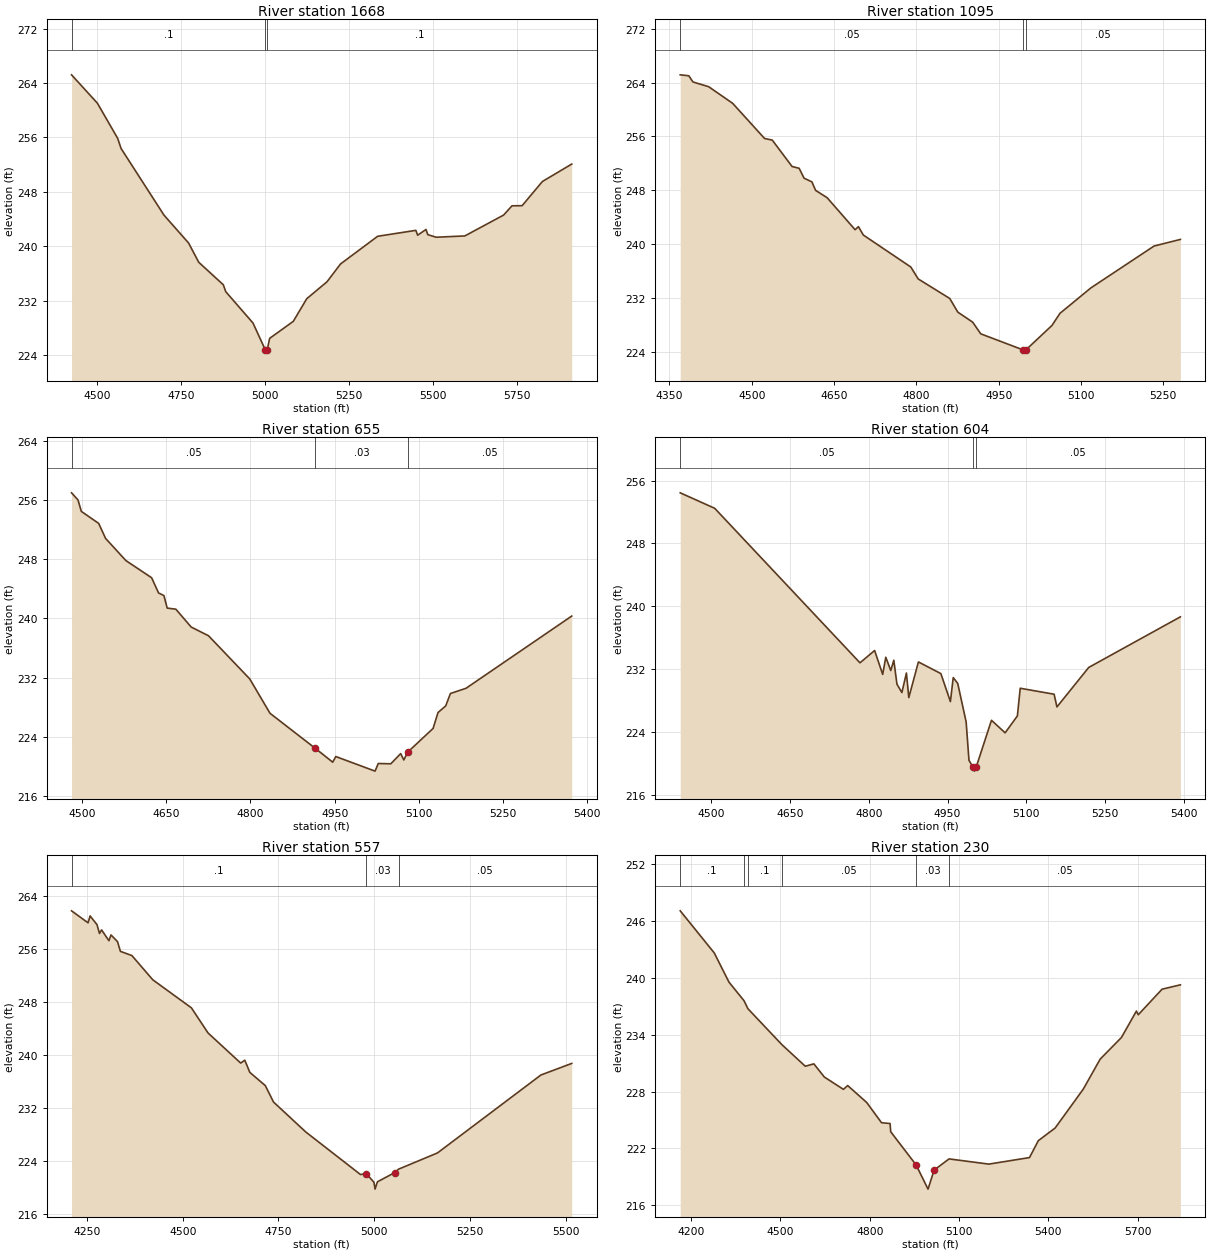
Type RM Length L Ch R = 1 ,1668    ,573,573,573
BEGIN DESCRIPTION:
Mapping XS 37edb133
END DESCRIPTION:
XS GIS Cut Line= 3
      2262711.08     13270154.13      2263639.88     13270045.62
       2263835.2     13269524.76
#Sta/Elev= 30
  4422.7   265.2  4499.9  261.02  4560.3  255.85  4570.3  254.37  4698.5  244.55
  4771.7  240.46  4801.9  237.63  4875.3  234.31  4882.5   233.3  4963.7  228.69
  5000.3  224.76    5003  224.26  5006.3  224.76  5013.3  226.43  5083.8  228.93
  5124.1  232.27  5184.5  234.76  5224.8  237.38  5335.5  241.45  5449.3  242.32
  5454.7  241.61  5479.6  242.45  5484.9  241.69  5509.8  241.31  5595.3   241.5
    5711  244.57  5735.9  245.93  5766.2  245.95  5826.7  249.51  5914.1  252.07
#Mann= 3 ,-1 , 0
  4422.7      .1       0  5000.3     .07       0  5006.3      .1       0
Bank Sta=5000.3,5006.3
XS Rating Curve= 0 ,0
Exp/Cntr=0.3,0.1

Type RM Length L Ch R = 1 ,1095    ,440,440,440
BEGIN DESCRIPTION:
Mapping XS 894747fb
END DESCRIPTION:
XS GIS Cut Line= 3
      2262728.46     13270253.99      2263058.28     13270475.31
      2263473.84     13270778.32
#Sta/Elev= 30
  4369.7  265.15  4385.3  265.01  4392.9  264.09  4421.4  263.39  4465.2  260.92
  4523.4  255.69  4537.4  255.45  4573.5  251.53  4586.4  251.26  4595.4  249.79
  4609.7  249.24  4616.4  247.98  4637.4  246.89  4688.4  242.13  4694.4  242.59
  4703.4  241.34  4789.9  236.59  4803.3  234.82  4860.9  231.91  4875.6  229.88
  4902.7  228.39  4917.3  226.66  4993.9  224.29  4996.7  223.79  4999.9  224.29
  5047.1   227.9  5061.8  229.71  5118.2  233.49  5233.3  239.71  5281.2  240.69
#Mann= 3 , 0 , 0
  4369.7     .05       0  4993.9     .03       0  4999.9     .05       0
Bank Sta=4993.9,4999.9
XS Rating Curve= 0 ,0
Exp/Cntr=0.3,0.1

Type RM Length L Ch R = 1 ,655     ,51,51,51
BEGIN DESCRIPTION:
UNT021 IN NURI 3.0
END DESCRIPTION:
XS GIS Cut Line= 4
      2262784.84     13270575.13      2263001.86     13270931.04
      2263140.75      13270991.8      2263427.21     13270844.23
#Sta/Elev= 30
  4481.4  256.97  4492.9  256.01  4498.8  254.46  4529.7  252.84    4542  250.81
  4578.2  247.81    4624  245.49  4636.3  243.44  4645.9  243.08  4651.7  241.39
  4667.2  241.24  4694.4  238.83  4725.3  237.65  4798.8  231.81  4834.8  227.17
  4915.6  222.42  4946.5  220.56    4952  221.32  5021.9  219.35  5027.6  220.38
  5049.9  220.34  5067.5  221.72  5073.1  220.86  5080.2  221.93  5125.2  225.12
    5134  227.27  5147.7  228.17  5156.1  229.84  5183.9  230.55  5372.1  240.31
#Mann= 3 , 0 , 0
  4481.4     .05       0  4915.6     .03       0  5080.2     .05       0
Bank Sta=4915.6,5080.2
XS Rating Curve= 0 ,0
Exp/Cntr=0.3,0.1

Type RM Length L Ch R = 1 ,604     ,47,47,47
BEGIN DESCRIPTION:
UNT021 IN NURI 2.0
END DESCRIPTION:
XS GIS Cut Line= 4
      2262728.41     13270605.51      2262954.11      13270970.1
      2263123.39     13271035.21      2263437.73     13270896.85
#Sta/Elev= 30
  4440.4  254.45  4506.1  252.48  4783.1  232.79    4811  234.36  4826.4  231.31
  4832.3   233.5  4841.8  231.81  4847.6  233.12  4853.6  230.07    4863     229
  4871.6  231.49  4876.2  228.36  4894.5   232.9  4937.3  231.42  4955.5  227.85
  4960.9  230.91  4969.5  230.16  4985.5  225.26  4990.9  220.37  4998.6  219.49
  5001.4  218.99  5004.6  219.49  5033.8  225.47  5059.8  223.87  5083.2  226.02
  5088.6  229.55  5153.2  228.79  5158.6  227.17  5219.2   232.2    5394  238.65
#Mann= 3 , 0 , 0
  4440.4     .05       0  4998.6     .03       0  5004.6     .05       0
Bank Sta=4998.6,5004.6
XS Rating Curve= 0 ,0
Exp/Cntr=0.3,0.1

Type RM Length L Ch R = 1 ,557     ,327,327,327
BEGIN DESCRIPTION:
UNT021 IN NURI 4.0
END DESCRIPTION:
XS GIS Cut Line= 4
      2262645.94      13270444.9      2262845.61     13270961.42
      2263210.19     13271130.69      2263470.62     13270896.31
#Sta/Elev= 30
  4209.7  261.78  4252.8  259.97  4258.1  261.01  4276.1   259.7  4282.7  258.36
  4288.1   258.9  4307.3  257.27  4312.7  258.14  4329.7  257.13  4337.3  255.66
  4367.2  255.03  4421.8  251.37  4522.7  247.13  4566.1  243.34  4651.4  238.79
  4662.1  239.23  4675.2  237.39  4715.7  235.39  4737.1  232.91  4820.9  228.41
  4964.3  221.96  4979.5   222.1  4999.4  220.79  5002.2  219.76  5008.4  220.86
  5053.7  222.26  5063.5  222.77  5165.4  225.23  5435.3  236.99  5515.8  238.74
#Mann= 3 ,-1 , 0
  4209.7      .1       0  4979.5     .03       0  5063.5     .05       0
Bank Sta=4979.5,5053.7
XS Rating Curve= 0 ,0
Exp/Cntr=0.3,0.1

Type RM Length L Ch R = 1 ,230     ,0,0,0
BEGIN DESCRIPTION:
UNT021 IN NURI 1.0
END DESCRIPTION:
XS GIS Cut Line= 4
      2262420.29     13270813.89      2262862.97     13271365.07
      2263153.77     13271395.45       2263548.1     13270841.24
#Sta/Elev= 30
  4163.8  247.08    4278  242.64  4327.6  239.55  4377.9   237.6  4391.1  236.75
  4505.4  232.95  4583.7  230.68  4612.5  230.93  4647.7  229.54  4711.7  228.24
  4726.1  228.64  4790.1  226.85  4839.7  224.72  4868.5  224.63  4870.5  223.77
  4955.9  220.26  4995.9  217.71  5016.3  219.72  5066.5   220.9  5200.1  220.35
  5336.6  221.04  5366.1  222.82  5422.7  224.16  5517.3  228.27  5573.9  231.43
  5645.2  233.71  5695.6   236.5  5701.8  236.11  5781.7  238.81  5843.3  239.27
#Mann= 6 ,-1 , 0
  4163.8      .1       0  4377.9     .05       0  4391.1      .1       0
  4505.4     .05       0  4955.9     .03       0  5066.5     .05       0
Bank Sta=4955.9,5016.3
XS Rating Curve= 0 ,0
Exp/Cntr=0.3,0.1

Chan Stop Cuts=-1
Use User Specified Reach Order=0
Composite Channel Slope=5