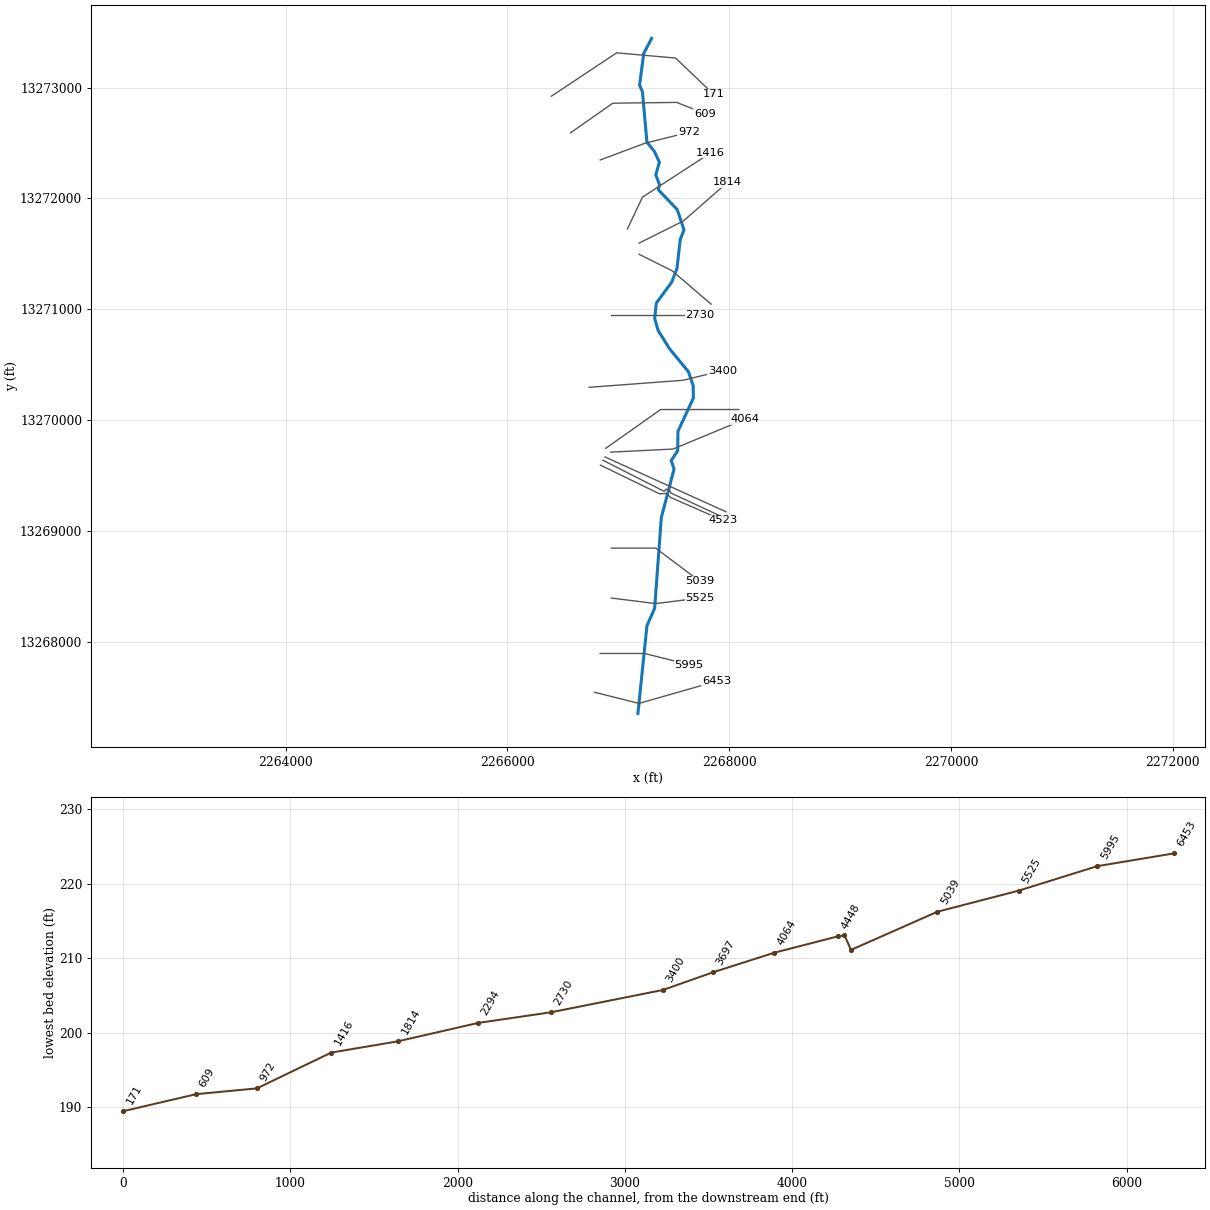
--- UNT022 IN NURI.prj (project) ---

Proj Title=UNT022 IN NURI Base Level Engineering
Current Plan=p01
Default Exp/Contr=0.3,0.1
English Units
Geom File=g01
Flow File=f01
Plan File=p01
BEGIN DESCRIPTION:
UNT022 IN NURI
END DESCRIPTION:

--- UNT022 IN NURI.p01 (plan) ---

Plan Title=Multiple Run
Short Identifier=Multiple
Geom File=g01
Flow File=f01
Subcritical Flow
K Sum by GR= 0
Std Step Tol= 0.01
Critical Tol= 0.01
Num of Std Step Trials= 20
Max Error Tol= 0.3
Flow Tol Ratio= 0.001
Split Flow NTrial= 30
Split Flow Tol= 0.02
Split Flow Ratio= 0.02
Log Output Level= 0
Friction Slope Method= 1
Unsteady Friction Slope Method= 2
Unsteady Bridges Friction Slope Method= 1
Parabolic Critical Depth
Global Vel Dist=  1 , 1 , 1
Global Log Level= 0
CheckData=True
Encroach Param= -1, 0, 0, 0
BEGIN DESCRIPTION:
Multiple Run
END DESCRIPTION:

--- UNT022 IN NURI.f01 (steady flow) ---

Flow Title=Multiple
Number of Profiles=7
Profile Names=10-year,25-year,50-year,1pct_min,100-year,1pct_plu,500-year
River Rch & RM= UNT022 IN NURI,Reach-1,6453
     255     357     443     404     547     739     846
River Rch & RM= UNT022 IN NURI,Reach-1,5995
     355     504     631     581     785    1062    1235
Boundary for River Rch & Prof#=UNT022 IN NURI,Reach-1,1
Up Type=0
Dn Type=3
Dn Slope=0.005
Boundary for River Rch & Prof#=UNT022 IN NURI,Reach-1,2
Up Type=0
Dn Type=3
Dn Slope=0.005
Boundary for River Rch & Prof#=UNT022 IN NURI,Reach-1,3
Up Type=0
Dn Type=3
Dn Slope=0.005
Boundary for River Rch & Prof#=UNT022 IN NURI,Reach-1,4
Up Type=0
Dn Type=3
Dn Slope=0.005
Boundary for River Rch & Prof#=UNT022 IN NURI,Reach-1,5
Up Type=0
Dn Type=3
Dn Slope=0.005
Boundary for River Rch & Prof#=UNT022 IN NURI,Reach-1,6
Up Type=0
Dn Type=3
Dn Slope=0.005
Boundary for River Rch & Prof#=UNT022 IN NURI,Reach-1,7
Up Type=0
Dn Type=3
Dn Slope=0.005

--- UNT022 IN NURI.g01 (geometry) ---

Geom Title=Existing Conditions

River Reach=UNT022 IN NURI,Reach-1
Reach XY= 30
      2267177.72     13267356.85      2267258.96     13268146.09
      2267328.54     13268305.31      2267388.59     13269121.30
      2267503.56     13269560.50      2267477.72     13269636.85
      2267536.37     13269726.12      2267539.05     13269901.09
      2267677.84     13270200.26      2267675.91     13270310.99
      2267634.43     13270435.50      2267460.39     13270647.95
      2267360.96     13270808.20      2267328.74     13270917.39
      2267343.51     13271056.27      2267481.90     13271244.54
      2267530.09     13271369.57      2267559.54     13271631.18
      2267593.31     13271716.53      2267532.19     13271899.26
      2267361.94     13272078.22      2267371.81     13272125.79
      2267338.84     13272211.77      2267371.26     13272326.58
      2267325.08     13272425.59      2267259.03     13272507.35
      2267218.28     13272962.62      2267192.63     13273021.02
      2267229.82     13273306.98      2267301.44     13273443.70

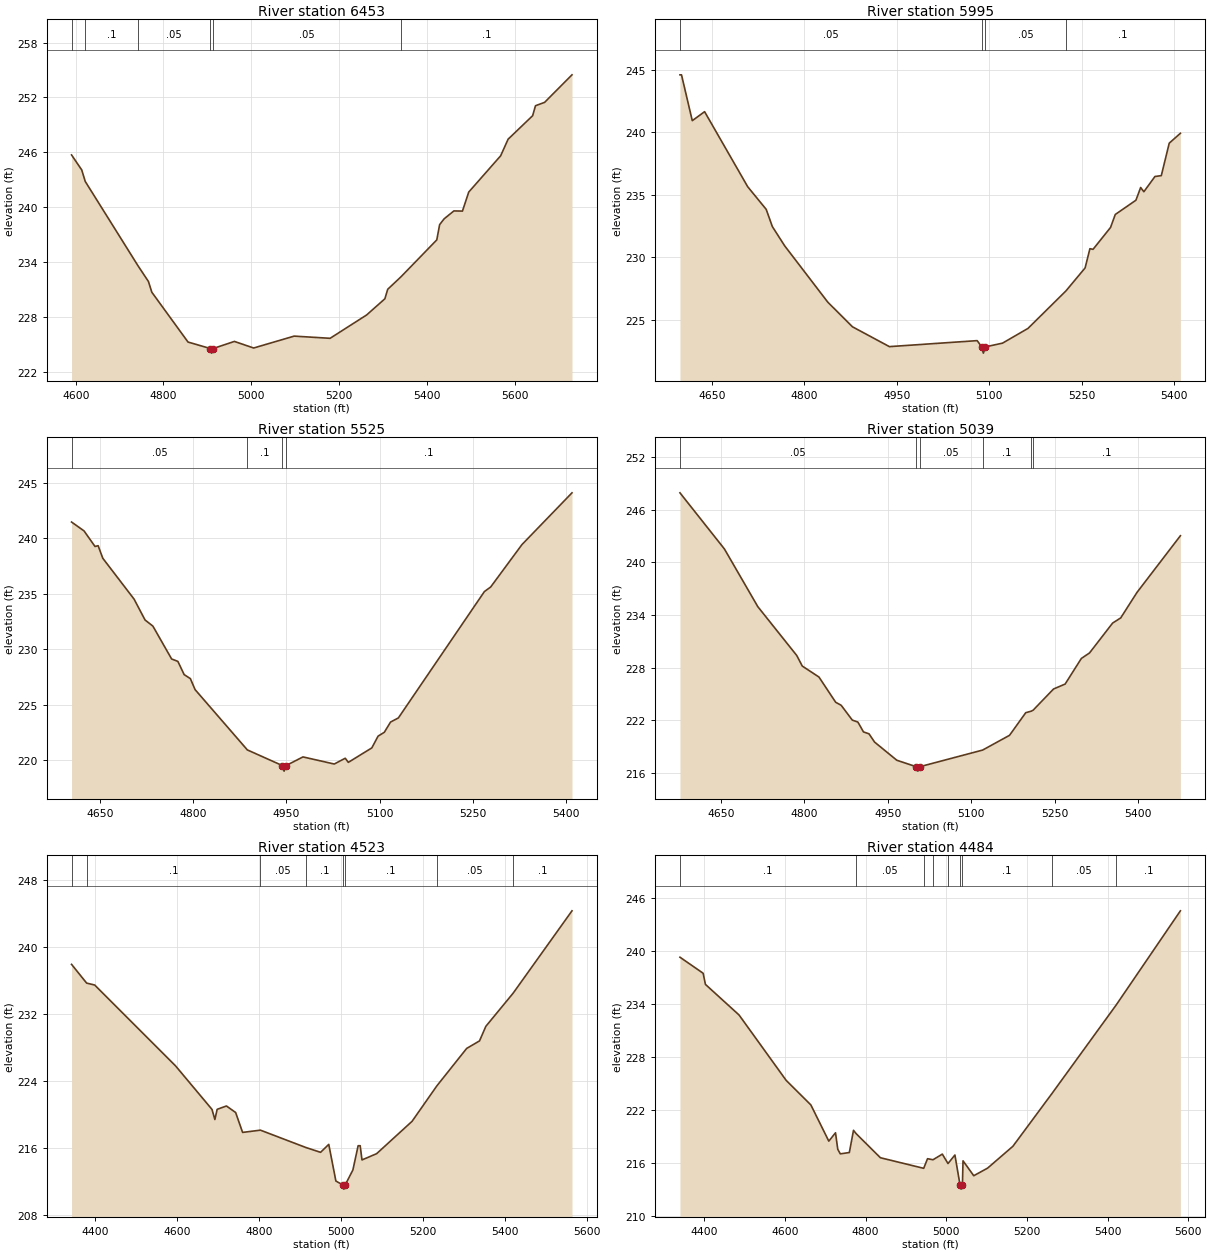
Type RM Length L Ch R = 1,6453,458,458,458
BEGIN DESCRIPTION:
UNT022 IN NURI 14.0
END DESCRIPTION:
XS GIS Cut Line= 3
      2266787.76     13267546.85      2267187.72     13267446.85
      2267887.74     13267646.86
#Sta/Elev= 30
  4590.6  245.71  4613.8  244.07  4621.8  242.81  4742.3  233.57  4765.8  231.87
  4773.5  230.70  4856.0  225.25  4907.1  224.54  4909.9  224.04  4913.1  224.54
  4961.6  225.32  5005.5  224.60  5097.8  225.90  5179.7  225.66  5262.9  228.21
  5304.5  229.98  5311.0  231.02  5341.3  232.39  5422.8  236.42  5429.3  238.09
  5439.7  238.73  5461.8  239.59  5481.3  239.57  5495.6  241.65  5568.4  245.62
  5585.3  247.43  5641.2  250.00  5647.7  251.09  5668.5  251.46  5730.9  254.47
#Mann=6,-1,0
  4590.6    0.05       0  4621.8     0.1       0  4742.3    0.05       0
  4907.1    0.03       0  4913.1    0.05       0  5341.3     0.1       0
Bank Sta=4907.1,4913.1
Exp/Cntr=0.3,0.1

Type RM Length L Ch R = 1,5995,470,470,470
BEGIN DESCRIPTION:
UNT022 IN NURI 13.0
END DESCRIPTION:
XS GIS Cut Line= 3
      2266837.67     13267896.85      2267237.72     13267896.85
      2267637.76     13267796.84
#Sta/Elev= 30
  4598.0  244.61  4600.5  244.61  4618.0  240.94  4638.0  241.66  4708.0  235.65
  4738.0  233.84  4748.0  232.46  4768.0  230.92  4838.0  226.41  4878.0  224.44
  4938.0  222.85  5080.5  223.33  5087.8  222.83  5090.6  222.33  5093.8  222.83
  5121.7  223.13  5163.0  224.31  5224.4  227.30  5255.7  229.15  5263.5  230.69
  5268.6  230.64  5297.0  232.39  5304.7  233.43  5338.2  234.57  5345.9  235.59
  5351.1  235.25  5369.1  236.47  5379.4  236.54  5392.3  239.14  5410.4  239.93
#Mann=4,-1,0
  4598.0    0.05       0  5087.8    0.03       0  5093.8    0.05       0
  5224.4     0.1       0
Bank Sta=5087.8,5093.8
Exp/Cntr=0.3,0.1

Type RM Length L Ch R = 1,5525,486,486,486
BEGIN DESCRIPTION:
UNT022 IN NURI 12.0
END DESCRIPTION:
XS GIS Cut Line= 3
      2266937.76     13268396.85      2267337.72     13268346.85
      2267737.74     13268396.86
#Sta/Elev= 30
  4603.9  241.47  4624.0  240.67  4641.7  239.27  4646.7  239.34  4654.2  238.21
  4704.6  234.53  4722.3  232.65  4734.9  232.10  4765.1  229.14  4775.2  228.92
  4785.3  227.73  4795.3  227.37  4802.9  226.38  4887.1  220.95  4943.5  219.54
  4946.3  219.04  4949.5  219.54  4976.7  220.32  5027.1  219.68  5044.8  220.20
  5049.8  219.83  5087.6  221.13  5097.7  222.19  5107.8  222.54  5117.8  223.46
  5130.4  223.83  5269.0  235.21  5279.1  235.62  5329.5  239.44  5410.1  244.10
#Mann=4,-1,0
  4603.9    0.05       0  4887.1     0.1       0  4943.5    0.07       0
  4949.5     0.1       0
Bank Sta=4943.5,4949.5
Exp/Cntr=0.3,0.1

Type RM Length L Ch R = 1,5039,516,516,516
BEGIN DESCRIPTION:
UNT022 IN NURI 11.0
END DESCRIPTION:
XS GIS Cut Line= 3
      2266937.72     13268846.85      2267337.72     13268846.85
      2267737.72     13268546.85
#Sta/Elev= 30
  4576.3  247.92  4656.3  241.52  4716.3  234.95  4786.3  229.39  4796.3  228.18
  4826.3  226.93  4856.3  224.06  4866.3  223.71  4886.3  222.02  4896.3  221.80
  4906.3  220.68  4916.3  220.46  4926.3  219.52  4966.3  217.45  5001.4  216.71
  5004.2  216.21  5007.4  216.71  5120.7  218.61  5169.0  220.29  5198.2  222.87
  5208.0  223.04  5211.4  223.15  5248.2  225.57  5269.0  226.13  5298.2  229.05
  5312.8  229.67  5354.4  233.08  5369.0  233.67  5398.2  236.57  5476.3  243.03
#Mann=6,-1,0
  4576.3    0.05       0  5001.4    0.03       0  5007.4    0.05       0
  5120.7     0.1       0  5208.0    0.05       0  5211.4     0.1       0
Bank Sta=5001.4,5007.4
Exp/Cntr=0.3,0.1

Type RM Length L Ch R = 1,4523,39,39,39
BEGIN DESCRIPTION:
Mapping XS bacd21b9
END DESCRIPTION:
XS GIS Cut Line= 6
      2266839.38     13269595.35      2267371.04     13269337.12
      2267427.47     13269339.29      2267444.83     13269332.78
      2267470.87     13269304.57      2267944.41     13269096.99
#Sta/Elev= 30
  4341.6  237.96  4378.4  235.72  4398.1  235.49  4595.5  225.82  4684.4  220.62
  4691.4  219.41  4697.0  220.63  4719.6  221.03  4742.1  220.25  4759.1  217.87
  4802.6  218.14  4913.3  216.07  4949.4  215.49  4969.4  216.44  4986.8  212.06
  5003.5  211.59  5006.3  211.09  5009.5  211.59  5028.3  213.38  5041.1  216.28
  5046.1  216.28  5050.5  214.58  5086.3  215.33  5172.8  219.20  5233.2  223.43
  5306.0  227.91  5337.4  228.81  5352.8  230.55  5419.2  234.50  5563.1  244.36
#Mann=8,-1,0
  4341.6    0.05       0  4378.4     0.1       0  4802.6    0.05       0
  4913.3     0.1       0  5003.5    0.07       0  5009.5     0.1       0
  5233.2    0.05       0  5419.2     0.1       0
Bank Sta=5003.5,5009.5
Exp/Cntr=0.3,0.1

Type RM Length L Ch R = 1,4484,36,36,36
BEGIN DESCRIPTION:
UNT022 IN NURI 10.0
END DESCRIPTION:
XS GIS Cut Line= 6
      2266863.22     13269638.77      2267414.44     13269358.82
      2267431.81     13269378.35      2267464.36     13269367.50
      2267475.21     13269343.63      2267961.36     13269117.92
#Sta/Elev= 30
  4339.8  239.34  4397.3  237.52  4402.9  236.26  4486.3  232.79  4603.2  225.37
  4664.4  222.59  4708.9  218.48  4725.5  219.43  4731.1  217.56  4737.4  217.04
  4759.8  217.19  4770.1  219.71  4776.5  219.34  4836.8  216.60  4944.2  215.40
  4953.7  216.49  4967.2  216.37  4990.4  217.01  5004.4  215.94  5021.6  216.91
  5034.2  213.54  5036.9  213.04  5040.2  213.54  5041.7  216.25  5068.3  214.56
  5102.6  215.42  5165.4  217.90  5262.5  223.90  5421.3  233.91  5580.7  244.60
#Mann=9,-1,0
  4339.8     0.1       0  4776.5    0.05       0  4944.2     0.1       0
  4967.2    0.05       0  5004.4     0.1       0  5034.2    0.03       0
  5040.2     0.1       0  5262.5    0.05       0  5421.3     0.1       0
Bank Sta=5034.2,5040.2
Exp/Cntr=0.3,0.1

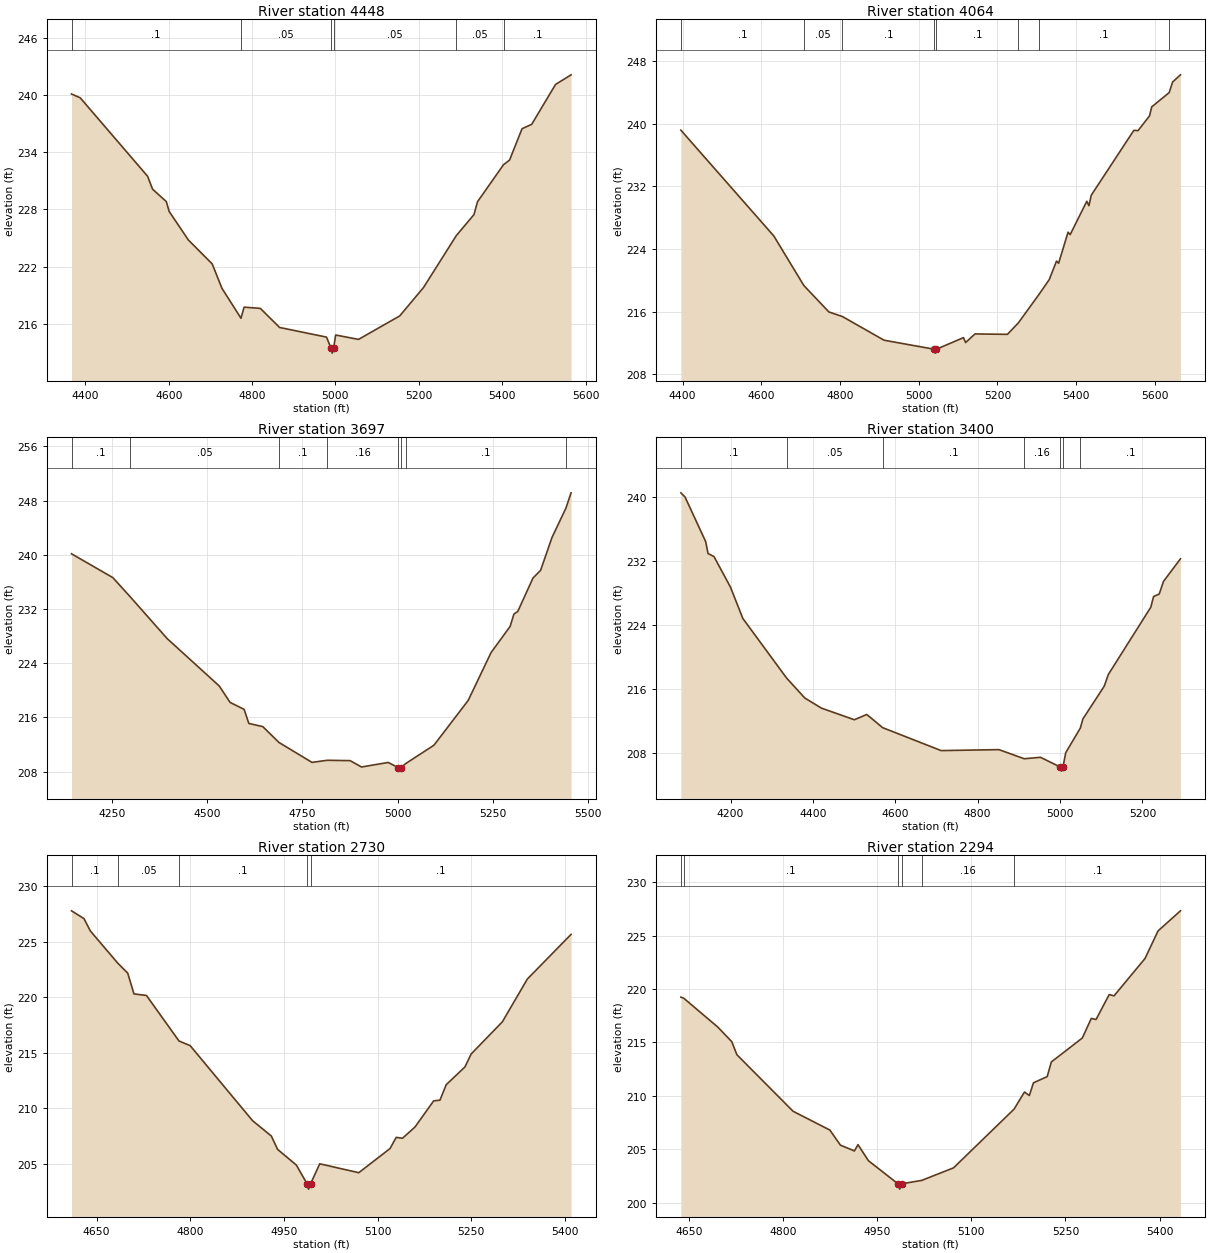
Type RM Length L Ch R = 1,4448,384,384,384
BEGIN DESCRIPTION:
Mapping XS 6011e3da
END DESCRIPTION:
XS GIS Cut Line= 2
      2266880.62     13269669.13      2267972.13     13269174.38
#Sta/Elev= 30
  4366.9  240.10  4387.8  239.70  4549.5  231.47  4561.3  230.12  4594.3  228.82
  4601.1  227.79  4647.3  224.79  4704.5  222.28  4727.6  219.74  4773.4  216.59
  4780.9  217.75  4819.9  217.62  4866.1  215.62  4978.6  214.61  4989.6  213.43
  4992.3  212.93  4995.6  213.43  5000.5  214.83  5055.4  214.37  5154.2  216.83
  5211.3  219.81  5290.1  225.26  5332.3  227.45  5340.9  228.81  5403.3  232.69
  5417.7  233.17  5447.7  236.46  5470.8  236.92  5528.0  241.10  5565.3  242.11
#Mann=6,-1,0
  4366.9     0.1       0  4773.4    0.05       0  4989.6    0.07       0
  4995.6    0.05       0  5290.1    0.05       0  5403.3     0.1       0
Bank Sta=4989.6,4995.6
Exp/Cntr=0.3,0.1

Type RM Length L Ch R = 1,4064,367,367,367
BEGIN DESCRIPTION:
UNT022 IN NURI 9.0
END DESCRIPTION:
XS GIS Cut Line= 3
      2266931.83     13269712.55      2267494.31     13269740.33
      2268147.09     13270011.17
#Sta/Elev= 30
  4395.4  239.19  4631.6  225.68  4708.1  219.34  4771.7  215.97  4806.2  215.38
  4911.9  212.36  5039.1  211.21  5041.9  210.71  5045.1  211.21  5113.8  212.69
  5119.2  212.06  5143.0  213.16  5225.5  213.11  5253.1  214.56  5305.2  218.17
  5331.8  220.10  5350.3  222.47  5355.7  222.19  5379.6  226.16  5385.0  225.85
  5427.3  230.11  5432.7  229.54  5438.6  230.88  5546.9  239.17  5557.5  239.13
  5586.8  241.02  5592.2  242.16  5636.7  243.99  5645.4  245.34  5665.3  246.26
#Mann=8,-1,0
  4395.4     0.1       0  4708.1    0.05       0  4806.2     0.1       0
  5039.1    0.07       0  5045.1     0.1       0  5253.1    0.05       0
  5305.2     0.1       0  5636.7    0.05       0
Bank Sta=5039.1,5045.1
Exp/Cntr=0.3,0.1

Type RM Length L Ch R = 1,3697,297,297,297
BEGIN DESCRIPTION:
UNT022 IN NURI 8.0
END DESCRIPTION:
XS GIS Cut Line= 3
      2266887.76     13269746.88      2267382.44     13270096.53
      2268087.76     13270096.85
#Sta/Elev= 30
  4144.3  240.16  4252.6  236.65  4297.8  233.85  4395.4  227.64  4532.0  220.65
  4560.6  218.22  4597.3  217.20  4609.6  215.12  4646.3  214.65  4688.8  212.31
  4775.4  209.37  4815.2  209.68  4875.4  209.63  4905.4  208.69  4975.4  209.36
  5002.4  208.58  5005.1  208.08  5008.4  208.58  5021.5  209.20  5095.4  211.90
  5185.4  218.52  5245.4  225.58  5295.4  229.44  5305.4  231.27  5315.4  231.64
  5355.4  236.58  5375.4  237.72  5405.4  242.58  5441.7  246.88  5455.4  249.16
#Mann=8,-1,0
  4144.3     0.1       0  4297.8    0.05       0  4688.8     0.1       0
  4815.2    0.16       0  5002.4    0.07       0  5008.4    0.16       0
  5021.5     0.1       0  5441.7    0.05       0
Bank Sta=5002.4,5008.4
Exp/Cntr=0.3,0.1

Type RM Length L Ch R = 1,3400,670,670,670
BEGIN DESCRIPTION:
UNT022 IN NURI 7.0
END DESCRIPTION:
XS GIS Cut Line= 3
      2266737.69     13270296.85      2267583.83     13270360.42
      2267937.71     13270446.85
#Sta/Elev= 30
  4079.5  240.55  4089.6  240.03  4139.7  234.45  4145.5  232.95  4159.8  232.58
  4199.9  228.75  4229.9  224.83  4336.3  217.36  4380.4  214.87  4420.5  213.61
  4500.7  212.15  4530.8  212.81  4569.4  211.16  4711.3  208.29  4851.7  208.41
  4913.1  207.27  4952.6  207.45  5001.1  206.22  5003.8  205.72  5007.1  206.22
  5013.8  208.02  5049.3  211.11  5055.5  212.25  5107.4  216.36  5117.3  217.82
  5220.3  226.23  5227.2  227.58  5240.8  227.88  5251.1  229.46  5292.3  232.29
#Mann=7,-1,0
  4079.5     0.1       0  4336.3    0.05       0  4569.4     0.1       0
  4913.1    0.16       0  5001.1    0.07       0  5007.1    0.16       0
  5049.3     0.1       0
Bank Sta=5001.1,5007.1
Exp/Cntr=0.3,0.1

Type RM Length L Ch R = 1,2730,436,436,436
BEGIN DESCRIPTION:
UNT022 IN NURI 6.0
END DESCRIPTION:
XS GIS Cut Line= 3
      2266937.76     13270946.85      2267337.72     13270946.85
      2267737.76     13270946.85
#Sta/Elev= 30
  4609.9  227.78  4629.9  227.08  4639.9  225.98  4683.8  223.08  4699.9  222.17
  4709.9  220.30  4729.9  220.16  4782.0  216.06  4799.9  215.64  4899.9  208.88
  4929.9  207.50  4939.9  206.30  4969.9  204.89  4986.9  203.22  4989.6  202.72
  4992.9  203.22  5007.4  205.00  5069.9  204.20  5119.9  206.37  5129.9  207.38
  5139.9  207.30  5159.9  208.31  5189.9  210.67  5199.9  210.73  5209.9  212.12
  5239.9  213.72  5249.9  214.89  5299.9  217.79  5339.9  221.64  5409.9  225.66
#Mann=5,-1,0
  4609.9     0.1       0  4683.8    0.05       0  4782.0     0.1       0
  4986.9    0.07       0  4992.9     0.1       0
Bank Sta=4986.9,4992.9
Exp/Cntr=0.3,0.1

Type RM Length L Ch R = 1,2294,480,480,480
BEGIN DESCRIPTION:
UNT022 IN NURI 5.0
END DESCRIPTION:
XS GIS Cut Line= 3
      2267187.71     13271496.86      2267487.72     13271346.85
      2267837.73     13271046.85
#Sta/Elev= 30
  4636.9  219.24  4641.5  219.14  4695.6  216.45  4718.0  215.08  4726.3  213.85
  4815.8  208.57  4874.5  206.81  4891.3  205.40  4913.6  204.86  4919.2  205.45
  4936.0  203.94  4983.0  201.79  4985.8  201.29  4989.0  201.79  5021.1  202.11
  5071.6  203.28  5168.1  208.77  5184.7  210.37  5192.4  210.04  5199.0  211.23
  5220.9  211.81  5227.5  213.18  5276.9  215.42  5291.2  217.25  5298.8  217.15
  5319.7  219.48  5327.4  219.36  5376.8  222.85  5397.6  225.43  5433.3  227.31
#Mann=6,-1,0
  4636.9    0.05       0  4641.5     0.1       0  4983.0    0.07       0
  4989.0     0.1       0  5021.1    0.16       0  5168.1     0.1       0
Bank Sta=4983,4989
Exp/Cntr=0.3,0.1

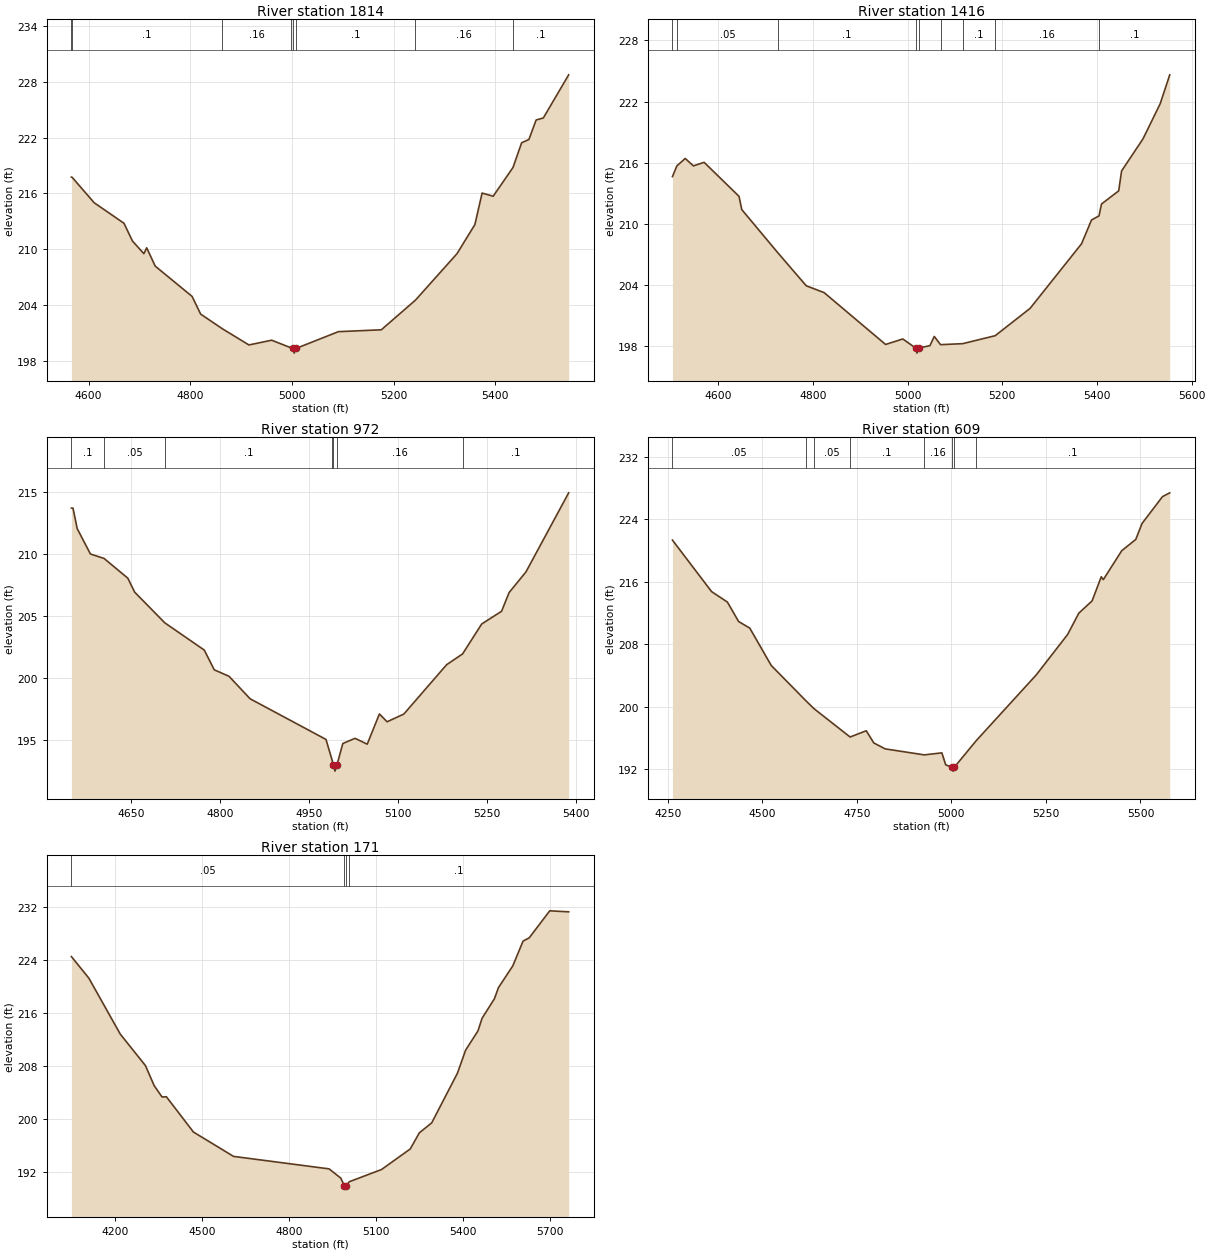
Type RM Length L Ch R = 1,1814,398,398,398
BEGIN DESCRIPTION:
UNT022 IN NURI 4.0
END DESCRIPTION:
XS GIS Cut Line= 3
      2267187.68     13271596.83      2267587.72     13271796.85
      2267987.74     13272146.87
#Sta/Elev= 30
  4566.0  217.75  4567.2  217.75  4610.8  215.00  4669.5  212.79  4686.2  210.88
  4708.6  209.52  4714.2  210.15  4731.0  208.18  4803.6  204.92  4820.4  203.02
  4863.2  201.44  4915.4  199.70  4960.2  200.21  4998.3  199.39  5001.9  199.32
  5004.6  198.82  5007.9  199.32  5091.6  201.13  5176.0  201.33  5243.2  204.52
  5325.0  209.52  5360.2  212.65  5374.4  216.04  5396.2  215.70  5435.2  218.79
  5452.2  221.45  5466.5  221.80  5480.7  223.90  5494.9  224.12  5544.8  228.76
#Mann=8,-1,0
  4566.0    0.05       0  4567.2     0.1       0  4863.2    0.16       0
  4998.3     0.1       0  5001.9    0.07       0  5007.9     0.1       0
  5243.2    0.16       0  5435.2     0.1       0
Bank Sta=5001.9,5007.9
Exp/Cntr=0.3,0.1

Type RM Length L Ch R = 1,1416,444,444,444
BEGIN DESCRIPTION:
UNT022 IN NURI 3.0
END DESCRIPTION:
XS GIS Cut Line= 3
      2267082.55     13271724.58      2267218.70     13272011.60
      2267832.96     13272410.70
#Sta/Elev= 30
  4503.5  214.64  4512.8  215.69  4530.5  216.42  4547.7  215.69  4570.4  216.04
  4644.1  212.70  4649.9  211.40  4726.8  207.12  4786.1  203.92  4823.8  203.25
  4953.6  198.16  4989.9  198.70  5017.2  197.81  5019.9  197.31  5023.2  197.81
  5047.2  198.04  5056.4  198.95  5069.7  198.14  5116.4  198.24  5185.1  199.02
  5258.7  201.70  5367.4  208.04  5388.5  210.38  5404.3  210.78  5409.6  211.95
  5445.9  213.24  5452.0  215.19  5497.3  218.35  5533.5  221.79  5553.7  224.63
#Mann=9,-1,0
  4503.5     0.1       0  4512.8    0.05       0  4726.8     0.1       0
  5017.2    0.07       0  5023.2     0.1       0  5069.7    0.16       0
  5116.4     0.1       0  5185.1    0.16       0  5404.3     0.1       0
Bank Sta=5017.2,5023.2
Exp/Cntr=0.3,0.1

Type RM Length L Ch R = 1,972,363,363,363
BEGIN DESCRIPTION:
UNT022 IN NURI 2.0
END DESCRIPTION:
XS GIS Cut Line= 3
      2266837.69     13272346.84      2267237.72     13272496.85
      2267637.68     13272596.85
#Sta/Elev= 30
  4548.6  213.67  4551.3  213.67  4558.4  212.02  4580.7  209.98  4603.8  209.62
  4643.9  208.03  4655.4  206.91  4706.3  204.44  4772.9  202.25  4789.8  200.66
  4814.7  200.14  4850.3  198.33  4978.4  195.06  4988.2  193.48  4990.9  193.01
  4993.6  192.51  4996.9  193.01  5006.8  194.73  5027.4  195.15  5048.0  194.68
  5068.6  197.11  5081.5  196.48  5109.8  197.10  5182.0  201.07  5209.0  201.94
  5241.3  204.35  5274.8  205.37  5287.6  206.88  5316.0  208.54  5388.1  214.90
#Mann=7,-1,0
  4548.6     0.1       0  4603.8    0.05       0  4706.3     0.1       0
  4988.2    0.16       0  4990.9    0.07       0  4996.9    0.16       0
  5209.0     0.1       0
Bank Sta=4990.9,4996.9
Exp/Cntr=0.3,0.1

Type RM Length L Ch R = 1,609,438,438,438
BEGIN DESCRIPTION:
Mapping XS 0b8ef0ed
END DESCRIPTION:
XS GIS Cut Line= 4
      2266569.42     13272591.48      2266951.34     13272858.82
      2267527.73     13272865.76      2267781.23     13272765.05
#Sta/Elev= 30
  4262.1  221.31  4365.6  214.72  4407.4  213.38  4437.1  210.89  4466.7  210.04
  4523.4  205.26  4615.3  200.73  4636.5  199.73  4732.0  196.10  4774.7  196.90
  4794.7  195.34  4824.7  194.58  4928.3  193.81  4974.7  194.07  4985.0  192.53
  5001.7  192.23  5004.4  191.73  5007.7  192.23  5065.4  195.62  5224.7  204.07
  5307.4  209.23  5337.0  211.96  5372.1  213.53  5396.4  216.62  5401.8  216.25
  5450.4  219.95  5487.6  221.40  5504.3  223.45  5558.3  226.88  5577.5  227.37
#Mann=8,-1,0
  4262.1    0.05       0  4615.3     0.1       0  4636.5    0.05       0
  4732.0     0.1       0  4928.3    0.16       0  5001.7    0.07       0
  5007.7    0.16       0  5065.4     0.1       0
Bank Sta=5001.7,5007.7
Exp/Cntr=0.3,0.1

Type RM Length L Ch R = 1,171,0,0,0
BEGIN DESCRIPTION:
UNT022 IN NURI 1.0
END DESCRIPTION:
XS GIS Cut Line= 4
      2266397.53     13272922.20      2266986.06     13273312.81
      2267517.31     13273265.94      2267861.07     13272937.80
#Sta/Elev= 30
  4050.2  224.46  4110.4  221.21  4218.5  212.80  4305.6  208.04  4335.7  205.02
  4362.7  203.32  4377.8  203.35  4471.0  198.04  4609.3  194.37  4938.9  192.49
  4979.1  191.10  4991.6  189.94  4994.3  189.44  4997.6  189.94  5008.3  190.55
  5119.6  192.39  5218.8  195.49  5250.1  197.92  5292.8  199.42  5381.5  206.90
  5409.8  210.38  5452.3  213.27  5466.4  215.17  5508.9  218.10  5523.0  219.79
  5572.4  223.06  5607.9  226.80  5629.0  227.28  5699.8  231.35  5765.1  231.20
#Mann=4,-1,0
  4050.2    0.05       0  4991.6    0.04       0  4997.6    0.05       0
  5008.3     0.1       0
Bank Sta=4991.6,4997.6
Exp/Cntr=0.3,0.1

Chan Stop Cuts=-1