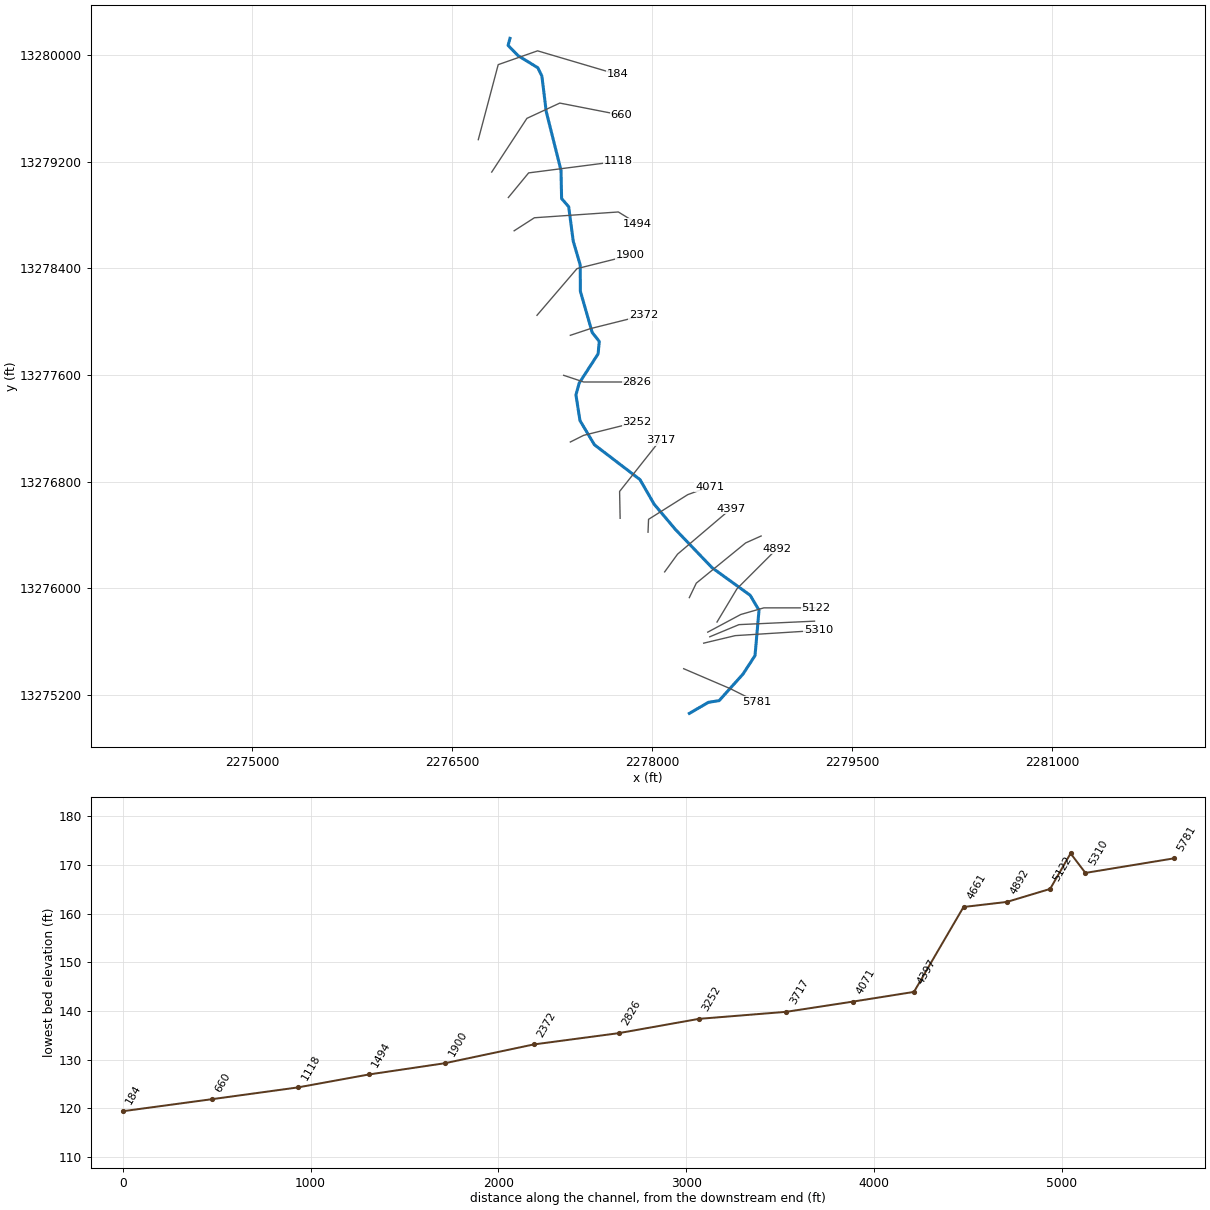
--- UNT023 IN NURI.prj (project) ---

Proj Title=UNT023 IN NURI Base Level Engineering
Current Plan=p01
Default Exp/Contr=0.3,0.1
English Units
Geom File=g01
Flow File=f01
Plan File=p01
BEGIN DESCRIPTION:
UNT023 IN NURI
END DESCRIPTION:

--- UNT023 IN NURI.p01 (plan) ---

Plan Title=Multiple Run
Short Identifier=Multiple
Geom File=g01
Flow File=f01
Subcritical Flow
K Sum by GR= 0
Std Step Tol= 0.01
Critical Tol= 0.01
Num of Std Step Trials= 20
Max Error Tol= 0.3
Flow Tol Ratio= 0.001
Split Flow NTrial= 30
Split Flow Tol= 0.02
Split Flow Ratio= 0.02
Log Output Level= 0
Friction Slope Method= 1
Unsteady Friction Slope Method= 2
Unsteady Bridges Friction Slope Method= 1
Parabolic Critical Depth
Global Vel Dist=  1 , 1 , 1
Global Log Level= 0
CheckData=True
Encroach Param= -1, 0, 0, 0
BEGIN DESCRIPTION:
Multiple Run
END DESCRIPTION:

--- UNT023 IN NURI.f01 (steady flow) ---

Flow Title=Multiple
Number of Profiles=7
Profile Names=10-year,25-year,50-year,1pct_min,100-year,1pct_plu,500-year
River Rch & RM= UNT023 IN NURI,Reach-1,5781
     260     365     454     416     563     761     878
River Rch & RM= UNT023 IN NURI,Reach-1,5310
     336     477     598     552     746    1009    1178
Boundary for River Rch & Prof#=UNT023 IN NURI,Reach-1,1
Up Type=0
Dn Type=3
Dn Slope=0.005
Boundary for River Rch & Prof#=UNT023 IN NURI,Reach-1,2
Up Type=0
Dn Type=3
Dn Slope=0.005
Boundary for River Rch & Prof#=UNT023 IN NURI,Reach-1,3
Up Type=0
Dn Type=3
Dn Slope=0.005
Boundary for River Rch & Prof#=UNT023 IN NURI,Reach-1,4
Up Type=0
Dn Type=3
Dn Slope=0.005
Boundary for River Rch & Prof#=UNT023 IN NURI,Reach-1,5
Up Type=0
Dn Type=3
Dn Slope=0.005
Boundary for River Rch & Prof#=UNT023 IN NURI,Reach-1,6
Up Type=0
Dn Type=3
Dn Slope=0.005
Boundary for River Rch & Prof#=UNT023 IN NURI,Reach-1,7
Up Type=0
Dn Type=3
Dn Slope=0.005

--- UNT023 IN NURI.g01 (geometry) ---

Geom Title=Existing Conditions

River Reach=UNT023 IN NURI,Reach-1
Reach XY= 30
      2278280.37     13275061.84      2278423.73     13275144.94
      2278503.28     13275157.12      2278682.38     13275356.31
      2278772.66     13275495.20      2278802.52     13275835.48
      2278736.55     13275947.29      2278450.44     13276154.23
      2278175.61     13276441.07      2278016.10     13276630.57
      2277910.14     13276814.87      2277568.36     13277076.23
      2277459.92     13277257.57      2277429.85     13277449.81
      2277454.26     13277538.58      2277595.95     13277757.50
      2277604.73     13277850.74      2277551.62     13277918.38
      2277463.10     13278226.58      2277461.87     13278424.58
      2277409.59     13278602.63      2277375.35     13278861.00
      2277322.28     13278922.35      2277317.74     13279133.16
      2277206.89     13279575.93      2277174.34     13279840.69
      2277143.95     13279903.19      2276996.39     13279993.47
      2276920.86     13280070.72      2276935.21     13280123.79

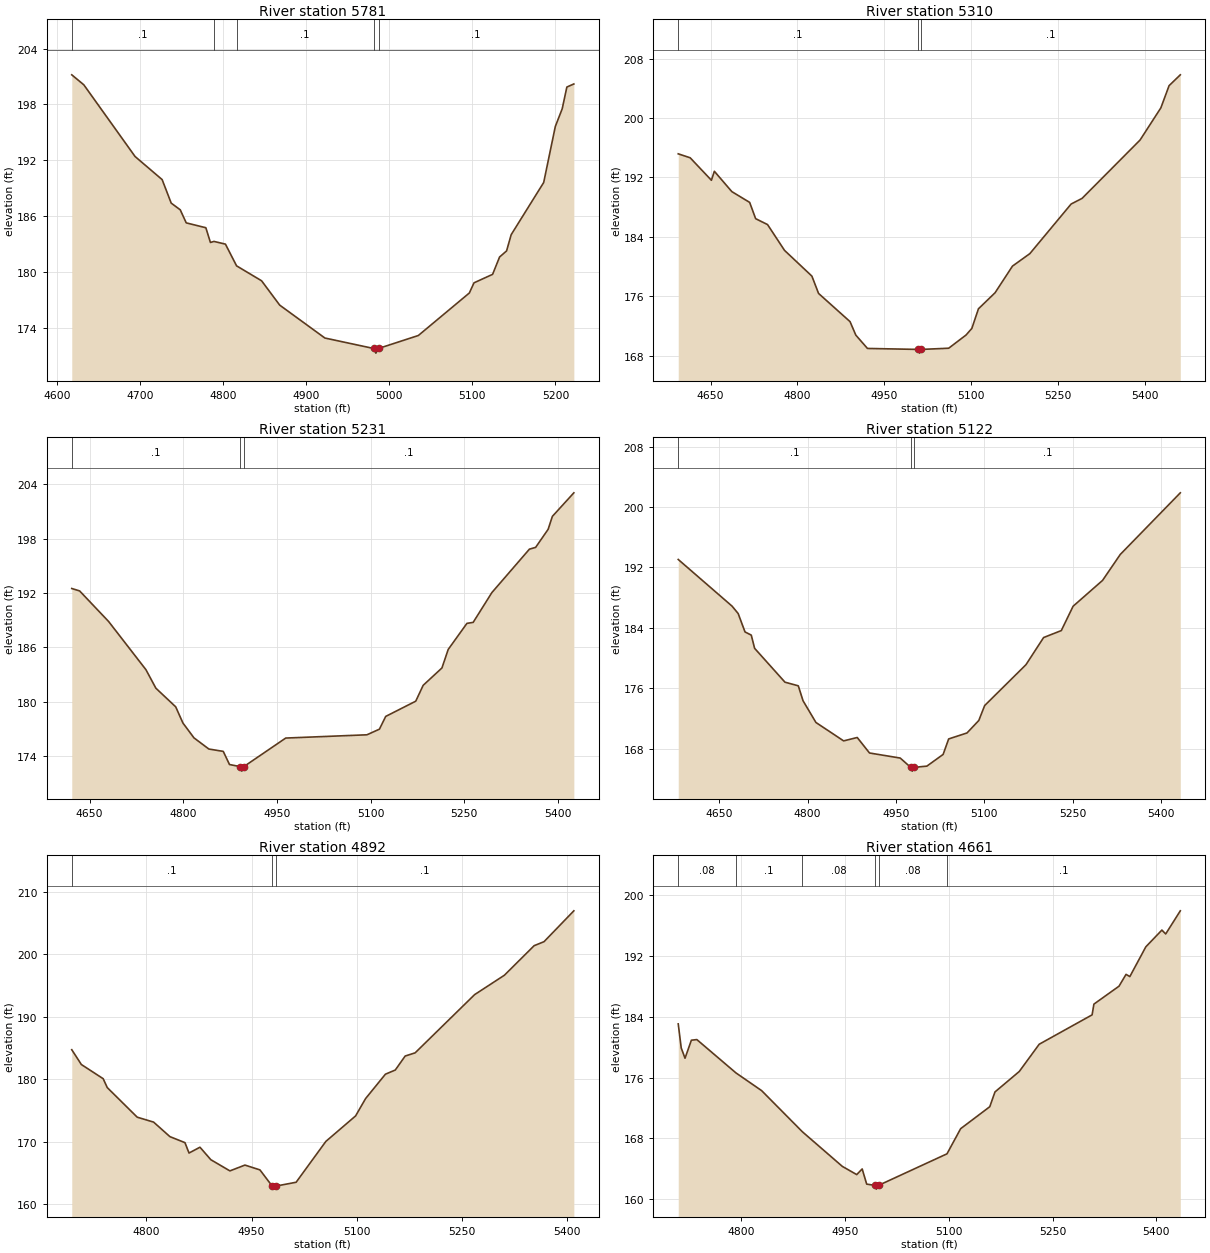
Type RM Length L Ch R = 1,5781,471,471,471
BEGIN DESCRIPTION:
UNT023 IN NURI 13.0
END DESCRIPTION:
XS GIS Cut Line= 3
      2278237.69     13275396.87      2278587.72     13275246.85
      2278787.70     13275146.87
#Sta/Elev= 30
  4617.7  201.18  4632.2  200.11  4693.9  192.42  4726.5  189.94  4737.4  187.42
  4748.3  186.70  4755.5  185.30  4779.1  184.78  4784.6  183.20  4788.9  183.31
  4802.7  183.02  4816.1  180.69  4846.2  179.09  4868.0  176.48  4922.4  172.95
  4981.0  171.83  4983.8  171.33  4987.0  171.83  5034.9  173.22  5096.3  177.78
  5101.9  178.87  5124.3  179.78  5132.7  181.64  5141.1  182.29  5146.7  184.04
  5185.8  189.63  5199.8  195.64  5208.1  197.54  5213.7  199.87  5222.1  200.20
#Mann=5,-1,0
  4617.7     0.1       0  4788.9    0.08       0  4816.1     0.1       0
  4981.0    0.07       0  4987.0     0.1       0
Bank Sta=4981,4987
Exp/Cntr=0.3,0.1

Type RM Length L Ch R = 1,5310,79,79,79
BEGIN DESCRIPTION:
Mapping XS 03f57c73
END DESCRIPTION:
XS GIS Cut Line= 3
      2278387.64     13275588.41      2278624.22     13275644.84
      2279247.08     13275683.91
#Sta/Elev= 30
  4594.0  195.18  4614.6  194.65  4651.3  191.62  4656.4  192.83  4686.6  190.09
  4717.4  188.64  4727.7  186.45  4748.3  185.65  4777.6  182.18  4824.9  178.71
  4836.4  176.38  4890.8  172.58  4900.8  170.76  4920.9  168.97  5008.1  168.84
  5010.8  168.34  5014.1  168.84  5061.2  169.00  5091.2  170.78  5101.2  171.67
  5112.6  174.31  5141.3  176.47  5171.4  180.06  5201.4  181.74  5272.7  188.42
  5291.6  189.18  5391.8  197.04  5427.7  201.37  5441.9  204.36  5461.3  205.82
#Mann=3,-1,0
  4594.0     0.1       0  5008.1    0.07       0  5014.1     0.1       0
Bank Sta=5008.1,5014.1
Exp/Cntr=0.3,0.1

Type RM Length L Ch R = 1,5231,109,109,109
BEGIN DESCRIPTION:
UNT023 IN NURI 12.0
END DESCRIPTION:
XS GIS Cut Line= 3
      2278433.24     13275636.16      2278652.44     13275727.31
      2279218.85     13275753.35
#Sta/Elev= 30
  4621.3  192.51  4633.9  192.24  4680.3  188.87  4740.1  183.55  4756.1  181.50
  4787.8  179.45  4799.4  177.66  4817.1  176.02  4840.9  174.79  4864.0  174.53
  4874.0  173.08  4891.0  172.85  4893.8  172.35  4897.0  172.85  4964.1  176.00
  5094.2  176.36  5114.2  176.98  5124.3  178.39  5172.4  180.07  5184.3  181.82
  5214.4  183.74  5224.4  185.78  5254.4  188.66  5264.4  188.77  5294.4  192.06
  5354.5  196.85  5364.5  197.05  5384.5  199.04  5391.3  200.47  5425.7  203.07
#Mann=3,-1,0
  4621.3     0.1       0  4891.0    0.07       0  4897.0     0.1       0
Bank Sta=4891,4897
Exp/Cntr=0.3,0.1

Type RM Length L Ch R = 1,5122,230,230,230
BEGIN DESCRIPTION:
Mapping XS 4a9e616a
END DESCRIPTION:
XS GIS Cut Line= 4
      2278418.09     13275670.90      2278665.46     13275803.26
      2278839.07     13275853.18      2279229.67     13275853.18
#Sta/Elev= 30
  4580.6  193.06  4672.0  186.88  4682.3  185.90  4693.9  183.47  4704.5  183.05
  4710.2  181.30  4761.7  176.82  4784.3  176.34  4792.3  174.37  4814.2  171.49
  4861.2  169.05  4884.3  169.50  4905.1  167.45  4957.2  166.78  4975.0  165.55
  4977.7  165.05  4981.0  165.55  5002.4  165.71  5030.0  167.26  5039.4  169.31
  5070.5  170.10  5090.5  171.75  5100.5  173.73  5170.5  179.13  5200.5  182.73
  5230.5  183.65  5250.5  186.87  5300.5  190.29  5330.5  193.72  5432.4  201.88
#Mann=3,-1,0
  4580.6     0.1       0  4975.0    0.07       0  4981.0     0.1       0
Bank Sta=4975,4981
Exp/Cntr=0.3,0.1

Type RM Length L Ch R = 1,4892,231,231,231
BEGIN DESCRIPTION:
UNT023 IN NURI 11.0
END DESCRIPTION:
XS GIS Cut Line= 3
      2278487.70     13275746.81      2278637.72     13275996.85
      2278937.75     13276296.88
#Sta/Elev= 30
  4693.6  184.70  4707.3  182.33  4738.4  180.06  4744.2  178.64  4786.9  173.90
  4810.3  173.11  4833.6  170.78  4855.0  169.82  4860.8  168.16  4876.4  169.09
  4891.9  167.09  4919.1  165.30  4940.5  166.23  4961.9  165.46  4979.3  162.88
  4982.0  162.38  4985.3  162.88  5013.5  163.48  5055.9  170.02  5098.3  174.10
  5112.5  176.87  5140.8  180.78  5154.9  181.45  5169.0  183.69  5183.2  184.20
  5268.0  193.52  5310.5  196.63  5352.9  201.36  5367.0  202.00  5409.5  206.94
#Mann=3,-1,0
  4693.6     0.1       0  4979.3    0.07       0  4985.3     0.1       0
Bank Sta=4979.3,4985.3
Exp/Cntr=0.3,0.1

Type RM Length L Ch R = 1,4661,264,264,264
BEGIN DESCRIPTION:
Mapping XS d7e27fab
END DESCRIPTION:
XS GIS Cut Line= 4
      2278280.01     13275929.78      2278332.27     13276038.33
      2278702.27     13276339.96      2278818.49     13276392.05
#Sta/Elev= 30
  4709.4  183.05  4713.7  179.90  4719.2  178.54  4728.4  180.91  4736.3  180.99
  4792.8  176.61  4829.9  174.28  4888.8  168.87  4946.4  164.33  4967.2  163.25
  4975.1  163.99  4981.6  162.00  4992.9  161.84  4995.7  161.34  4998.9  161.84
  5097.6  165.98  5117.3  169.28  5159.4  172.17  5166.9  174.11  5202.0  176.80
  5230.8  180.38  5307.2  184.24  5309.8  185.65  5346.1  188.01  5356.2  189.56
  5361.7  189.27  5384.8  193.18  5408.0  195.38  5413.5  194.87  5434.6  197.91
#Mann=6,-1,0
  4709.4    0.08       0  4792.8     0.1       0  4888.8    0.08       0
  4992.9    0.07       0  4998.9    0.08       0  5097.6     0.1       0
Bank Sta=4992.9,4998.9
Exp/Cntr=0.3,0.1

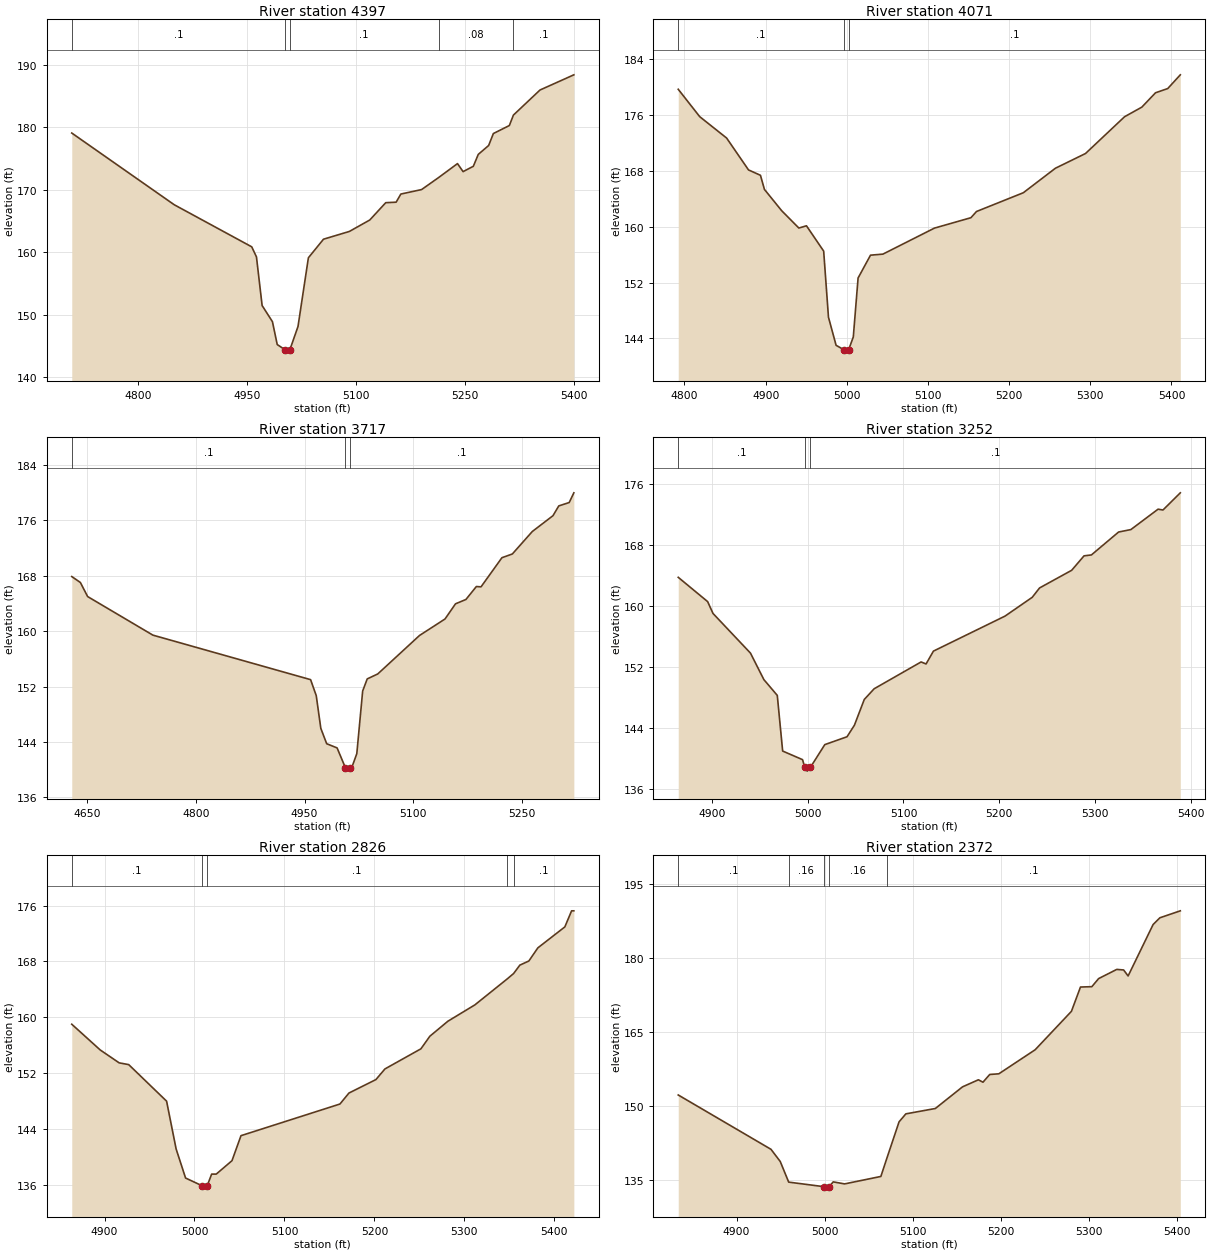
Type RM Length L Ch R = 1,4397,326,326,326
BEGIN DESCRIPTION:
UNT023 IN NURI 10.0
END DESCRIPTION:
XS GIS Cut Line= 3
      2278094.99     13276122.78      2278191.51     13276255.50
      2278593.21     13276596.94
#Sta/Elev= 30
  4708.2  179.09  4849.3  167.62  4956.0  160.89  4962.5  159.28  4970.3  151.50
  4984.5  148.92  4991.1  145.26  5002.4  144.39  5005.1  143.89  5008.4  144.39
  5019.7  148.15  5034.0  159.14  5054.8  162.11  5090.4  163.35  5118.5  165.18
  5140.5  167.95  5154.8  168.03  5161.3  169.33  5189.9  170.05  5213.3  171.97
  5239.3  174.20  5247.0  172.92  5261.1  173.77  5267.9  175.67  5282.2  177.10
  5288.7  179.01  5310.7  180.29  5316.3  181.96  5352.9  185.97  5399.5  188.40
#Mann=5,-1,0
  4708.2     0.1       0  5002.4    0.07       0  5008.4     0.1       0
  5213.3    0.08       0  5316.3     0.1       0
Bank Sta=5002.4,5008.4
Exp/Cntr=0.3,0.1

Type RM Length L Ch R = 1,4071,354,354,354
BEGIN DESCRIPTION:
UNT023 IN NURI 9.0
END DESCRIPTION:
XS GIS Cut Line= 4
      2277970.32     13276420.38      2277974.34     13276516.91
      2278267.93     13276701.91      2278432.25     13276762.03
#Sta/Elev= 30
  4792.3  179.71  4818.8  175.78  4851.9  172.72  4878.9  168.15  4893.6  167.38
  4898.5  165.36  4919.7  162.31  4940.9  159.82  4950.3  160.14  4971.5  156.51
  4977.4  147.04  4986.8  143.01  4996.3  142.39  4999.0  141.89  5002.3  142.39
  5008.0  144.21  5013.9  152.66  5029.2  155.93  5044.5  156.08  5108.0  159.81
  5152.9  161.30  5159.8  162.19  5217.5  164.88  5257.0  168.39  5294.1  170.50
  5342.2  175.77  5363.5  177.15  5380.4  179.21  5395.4  179.81  5410.9  181.78
#Mann=3,-1,0
  4792.3     0.1       0  4996.3    0.07       0  5002.3     0.1       0
Bank Sta=4996.3,5002.3
Exp/Cntr=0.3,0.1

Type RM Length L Ch R = 1,3717,465,465,465
BEGIN DESCRIPTION:
UNT023 IN NURI 8.0
END DESCRIPTION:
XS GIS Cut Line= 3
      2277761.20     13276524.91      2277757.17     13276726.04
      2278062.64     13277111.89
#Sta/Elev= 30
  4628.6  167.90  4640.5  167.04  4650.5  165.01  4740.6  159.44  4958.4  153.01
  4966.2  150.70  4972.5  145.98  4980.6  143.76  4995.0  143.15  5006.4  140.30
  5009.1  139.80  5012.4  140.30  5015.8  140.48  5022.2  142.32  5030.3  151.37
  5036.6  153.12  5051.1  153.83  5108.8  159.39  5144.0  161.77  5158.5  163.96
  5172.9  164.59  5187.3  166.46  5193.7  166.41  5222.6  170.62  5237.0  171.16
  5264.5  174.40  5293.1  176.69  5301.1  178.10  5315.5  178.59  5321.9  179.99
#Mann=3,-1,0
  4628.6     0.1       0  5006.4    0.07       0  5012.4     0.1       0
Bank Sta=5006.4,5012.4
Exp/Cntr=0.3,0.1

Type RM Length L Ch R = 1,3252,426,426,426
BEGIN DESCRIPTION:
UNT023 IN NURI 7.0
END DESCRIPTION:
XS GIS Cut Line= 3
      2277387.75     13277096.87      2277487.72     13277146.85
      2277887.74     13277246.86
#Sta/Elev= 30
  4864.9  163.72  4895.6  160.54  4901.2  158.99  4940.3  153.80  4954.3  150.33
  4968.3  148.26  4973.9  140.98  4994.7  139.85  4996.9  138.85  4999.6  138.35
  5002.9  138.85  5017.9  141.82  5041.1  142.85  5048.8  144.36  5059.1  147.73
  5069.4  149.13  5118.4  152.64  5123.6  152.38  5131.3  154.06  5206.0  158.64
  5234.4  161.10  5242.1  162.33  5275.6  164.64  5288.5  166.53  5296.2  166.65
  5324.6  169.65  5337.4  169.97  5365.8  172.64  5370.9  172.53  5389.0  174.78
#Mann=3,-1,0
  4864.9     0.1       0  4996.9    0.07       0  5002.9     0.1       0
Bank Sta=4996.9,5002.9
Exp/Cntr=0.3,0.1

Type RM Length L Ch R = 1,2826,454,454,454
BEGIN DESCRIPTION:
UNT023 IN NURI 6.0
END DESCRIPTION:
XS GIS Cut Line= 3
      2277337.69     13277596.86      2277487.72     13277546.85
      2277887.68     13277546.85
#Sta/Elev= 30
  4863.6  159.02  4895.3  155.33  4916.3  153.49  4926.9  153.24  4969.0  148.01
  4979.6  141.17  4990.1  137.01  5008.2  135.92  5011.0  135.42  5014.2  135.92
  5019.1  137.57  5024.2  137.57  5041.7  139.49  5051.7  143.07  5161.7  147.60
  5171.7  149.17  5201.7  151.10  5211.7  152.62  5251.7  155.50  5261.7  157.31
  5281.7  159.45  5311.7  161.79  5347.6  165.50  5354.7  166.27  5361.7  167.48
  5371.7  168.07  5381.7  169.95  5411.7  172.95  5419.2  175.25  5421.7  175.25
#Mann=5,-1,0
  4863.6     0.1       0  5008.2    0.07       0  5014.2     0.1       0
  5347.6    0.08       0  5354.7     0.1       0
Bank Sta=5008.2,5014.2
Exp/Cntr=0.3,0.1

Type RM Length L Ch R = 1,2372,472,472,472
BEGIN DESCRIPTION:
UNT023 IN NURI 5.0
END DESCRIPTION:
XS GIS Cut Line= 3
      2277387.75     13277896.86      2277537.72     13277946.85
      2277937.73     13278046.86
#Sta/Elev= 30
  4833.8  152.18  4939.2  141.16  4949.7  138.69  4959.3  134.51  4999.2  133.59
  5001.9  133.09  5005.2  133.59  5009.9  134.56  5022.8  134.15  5064.0  135.66
  5070.8  139.34  5084.7  146.74  5092.4  148.35  5125.9  149.44  5156.8  153.83
  5174.8  155.26  5180.0  154.77  5187.7  156.34  5198.0  156.47  5239.3  161.35
  5280.5  169.14  5290.8  174.07  5303.7  174.14  5311.4  175.78  5332.0  177.64
  5339.8  177.53  5344.9  176.31  5373.3  186.74  5381.0  188.11  5404.2  189.52
#Mann=5,-1,0
  4833.8     0.1       0  4959.3    0.16       0  4999.2    0.07       0
  5005.2    0.16       0  5070.8     0.1       0
Bank Sta=4999.2,5005.2
Exp/Cntr=0.3,0.1

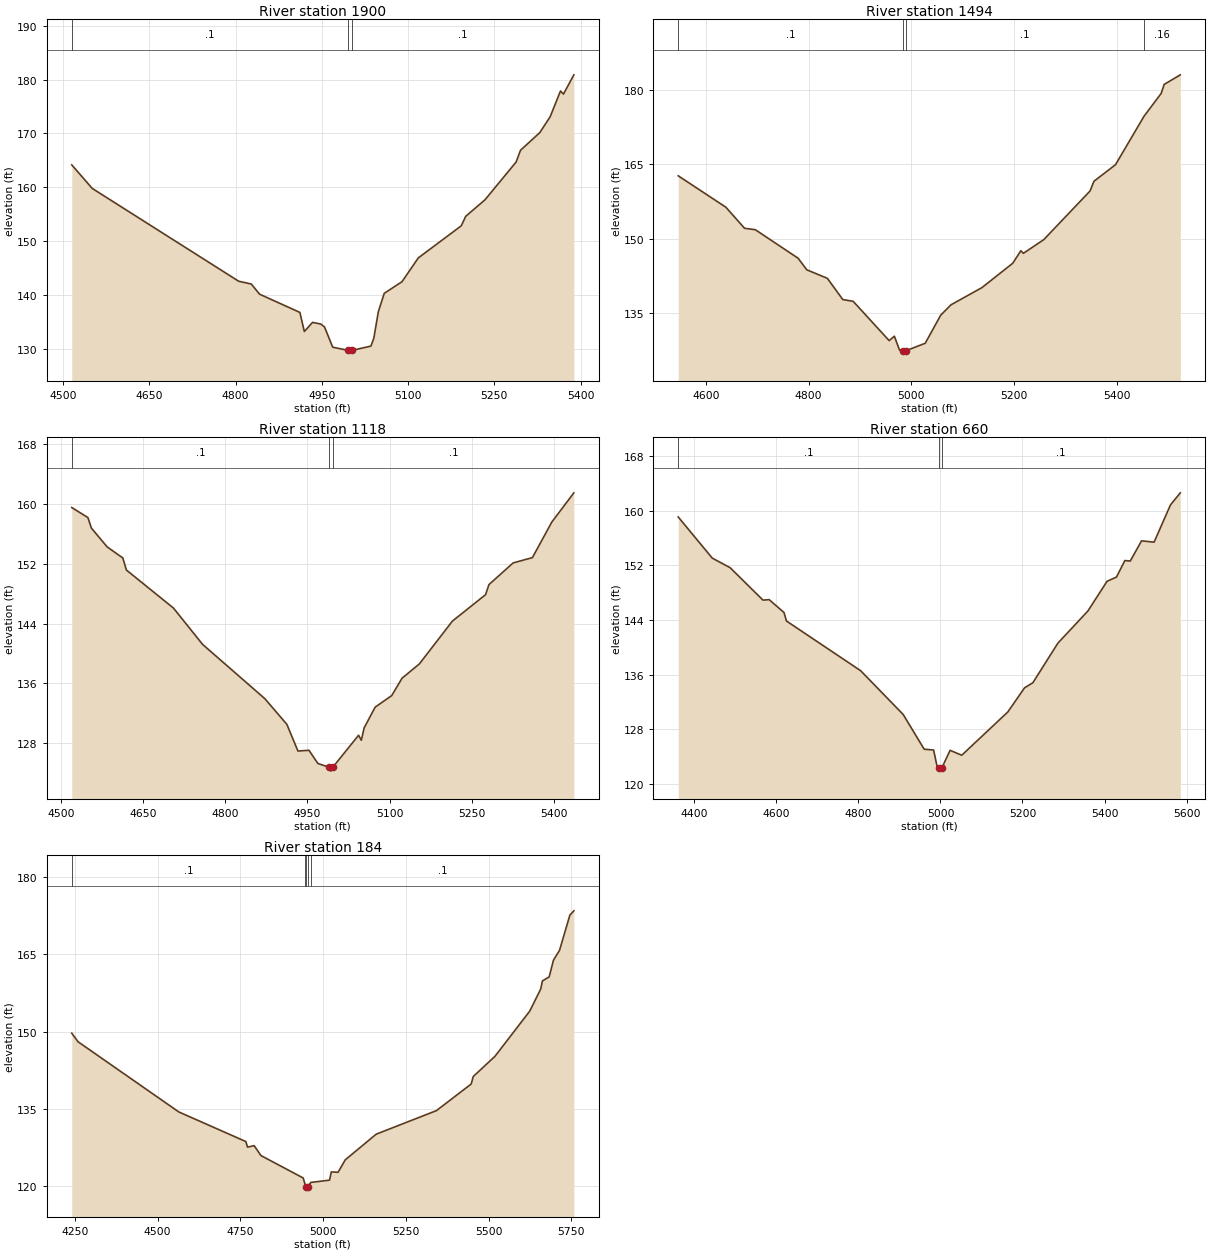
Type RM Length L Ch R = 1,1900,406,406,406
BEGIN DESCRIPTION:
UNT023 IN NURI 4.0
END DESCRIPTION:
XS GIS Cut Line= 3
      2277137.69     13278046.82      2277437.72     13278396.85
      2277837.69     13278496.85
#Sta/Elev= 30
  4515.1  164.16  4550.8  159.79  4805.4  142.58  4827.4  142.06  4841.7  140.18
  4911.9  136.79  4919.6  133.25  4933.9  134.94  4948.1  134.64  4954.7  134.10
  4969.0  130.34  4996.3  129.74  4999.1  129.24  5002.3  129.74  5035.4  130.54
  5040.5  132.00  5048.3  136.90  5058.6  140.33  5089.5  142.49  5117.9  146.91
  5192.6  152.86  5200.3  154.62  5233.8  157.68  5287.9  164.68  5295.7  166.88
  5329.2  170.15  5347.2  173.09  5365.2  177.88  5370.4  177.29  5388.4  180.87
#Mann=3,-1,0
  4515.1     0.1       0  4996.3    0.07       0  5002.3     0.1       0
Bank Sta=4996.3,5002.3
Exp/Cntr=0.3,0.1

Type RM Length L Ch R = 1,1494,376,376,376
BEGIN DESCRIPTION:
UNT023 IN NURI 3.0
END DESCRIPTION:
XS GIS Cut Line= 4
      2276966.42     13278680.69      2277118.36     13278778.37
      2277747.70     13278821.77      2277888.76     13278734.97
#Sta/Elev= 30
  4546.3  162.63  4639.0  156.31  4675.3  152.07  4696.4  151.77  4779.5  146.04
  4796.5  143.70  4836.6  141.98  4866.6  137.70  4886.7  137.36  4956.8  129.44
  4966.9  130.33  4976.9  127.55  4983.9  127.42  4986.7  126.92  4989.9  127.42
  5027.0  128.91  5057.1  134.56  5077.1  136.65  5137.3  140.11  5197.4  145.03
  5213.0  147.54  5218.0  147.02  5257.6  149.77  5347.8  159.58  5355.3  161.53
  5397.3  164.87  5453.0  174.66  5486.1  179.21  5492.0  181.04  5523.4  182.97
#Mann=4,-1,0
  4546.3     0.1       0  4983.9    0.07       0  4989.9     0.1       0
  5453.0    0.16       0
Bank Sta=4983.9,4989.9
Exp/Cntr=0.3,0.1

Type RM Length L Ch R = 1,1118,458,458,458
BEGIN DESCRIPTION:
UNT023 IN NURI 2.0
END DESCRIPTION:
XS GIS Cut Line= 3
      2276923.04     13278930.27      2277074.96     13279114.74
      2277747.71     13279201.55
#Sta/Elev= 30
  4519.5  159.54  4549.0  158.20  4555.4  156.79  4584.1  154.28  4612.8  152.79
  4619.3  151.18  4705.3  146.09  4758.5  141.23  4872.2  133.97  4912.5  130.53
  4932.7  126.96  4952.8  127.06  4969.1  125.30  4990.2  124.77  4992.9  124.27
  4996.2  124.77  5043.5  129.07  5048.5  128.40  5053.7  130.06  5073.8  132.83
  5104.1  134.38  5122.9  136.70  5154.5  138.61  5215.0  144.35  5275.5  147.88
  5281.7  149.23  5325.9  152.13  5361.1  152.84  5396.5  157.59  5436.8  161.51
#Mann=3,-1,0
  4519.5     0.1       0  4990.2    0.07       0  4996.2     0.1       0
Bank Sta=4990.2,4996.2
Exp/Cntr=0.3,0.1

Type RM Length L Ch R = 1,660,476,476,476
BEGIN DESCRIPTION:
Mapping XS e255944c
END DESCRIPTION:
XS GIS Cut Line= 4
      2276798.26     13279120.96      2277062.16     13279523.75
      2277308.69     13279638.33      2277770.45     13279548.06
#Sta/Elev= 30
  4360.8  159.11  4443.7  153.08  4487.4  151.67  4567.4  146.92  4582.5  146.99
  4618.7  145.10  4624.6  143.86  4805.5  136.57  4909.1  130.16  4960.4  125.06
  4983.3  124.95  4991.8  122.55  4997.6  122.35  5000.4  121.85  5003.6  122.35
  5023.5  124.90  5051.9  124.18  5164.2  130.52  5205.0  134.06  5225.3  134.81
  5286.4  140.62  5359.6  145.34  5406.1  149.68  5429.1  150.30  5449.5  152.72
  5462.7  152.65  5490.2  155.61  5520.8  155.42  5560.7  160.88  5584.7  162.65
#Mann=3,-1,0
  4360.8     0.1       0  4997.6    0.07       0  5003.6     0.1       0
Bank Sta=4997.6,5003.6
Exp/Cntr=0.3,0.1

Type RM Length L Ch R = 1,184,0,0,0
BEGIN DESCRIPTION:
UNT023 IN NURI 1.0
END DESCRIPTION:
XS GIS Cut Line= 4
      2276697.59     13279364.07      2276846.88     13279926.53
      2277142.14     13280030.04      2277739.21     13279853.62
#Sta/Elev= 30
  4240.5  149.68  4259.7  148.01  4564.1  134.37  4766.6  128.62  4771.7  127.54
  4791.7  127.82  4812.4  125.89  4939.9  121.54  4945.0  120.42  4947.5  119.87
  4950.2  119.37  4953.5  119.87  4963.2  120.67  5019.6  121.12  5024.9  122.72
  5045.3  122.64  5067.0  125.06  5160.5  130.05  5342.6  134.63  5447.6  139.80
  5454.0  141.27  5519.4  145.18  5624.5  153.96  5657.8  158.27  5663.0  159.85
  5683.4  160.63  5696.3  163.88  5714.6  165.78  5745.9  172.64  5757.9  173.47
#Mann=5,-1,0
  4240.5     0.1       0  4945.0    0.16       0  4947.5    0.07       0
  4953.5    0.16       0  4963.2     0.1       0
Bank Sta=4947.5,4953.5
Exp/Cntr=0.3,0.1

Chan Stop Cuts=-1