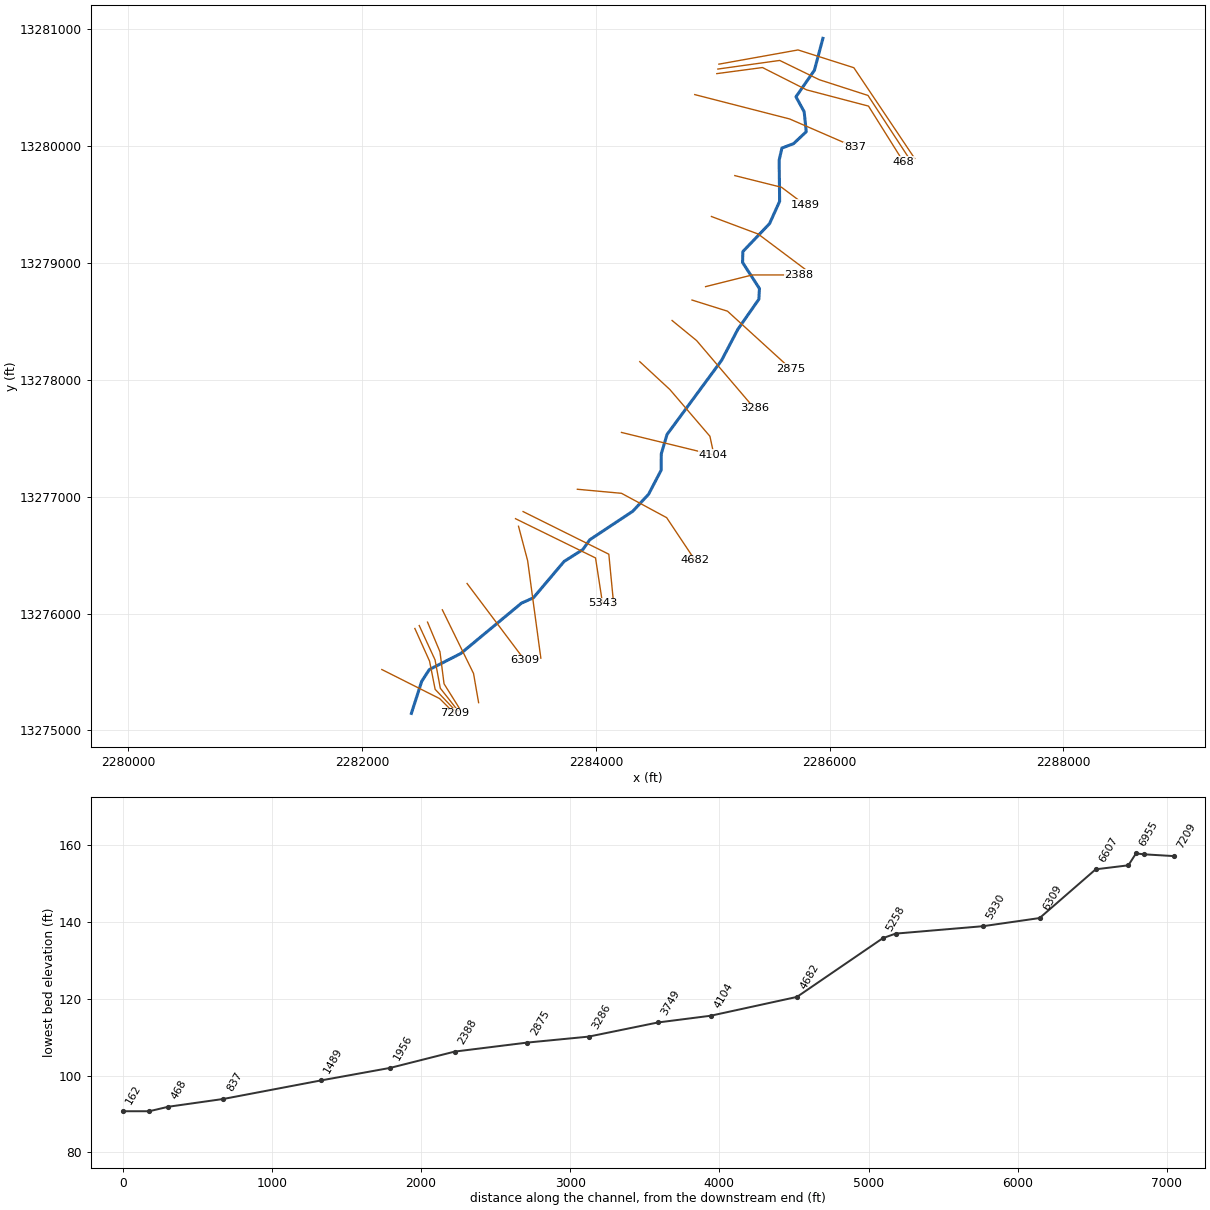
--- UNT024 IN NURI.prj (project) ---

Proj Title=UNT024 IN NURI Base Level Engineering
Current Plan=p01
Default Exp/Contr=0.3,0.1
English Units
Geom File=g01
Flow File=f01
Plan File=p01
Y Axis Title=Elevation
X Axis Title(PF)=Main Channel Distance
X Axis Title(XS)=Station
BEGIN DESCRIPTION:
UNT024 IN NURI
END DESCRIPTION:
DSS Export Rating Curves= 0
DSS Export Rating Curve Sorted= 0
DSS Export Volume Flow Curves= 0
DXF OffsetX= 0
DXF OffsetY= 0
DXF ScaleX= 1
DXF ScaleY= 10

--- UNT024 IN NURI.p01 (plan) ---

Plan Title=Multiple Run
Short Identifier=Multiple
Geom File=g01
Flow File=f01
Subcritical Flow
K Sum by GR= 0
Std Step Tol= 0.01
Critical Tol= 0.01
Num of Std Step Trials= 20
Max Error Tol= 0.3
Flow Tol Ratio= 0.001
Split Flow NTrial= 30
Split Flow Tol= 0.02
Split Flow Ratio= 0.02
Log Output Level= 0
Friction Slope Method= 1
Unsteady Friction Slope Method= 2
Unsteady Bridges Friction Slope Method= 1
Parabolic Critical Depth
Global Vel Dist=  1 , 1 , 1
Global Log Level= 0
CheckData=True
Encroach Param= -1, 0, 0, 0
BEGIN DESCRIPTION:
Multiple Run
END DESCRIPTION:

--- UNT024 IN NURI.f01 (steady flow) ---

Flow Title=Multiple
Number of Profiles=7
Profile Names=10-year,25-year,50-year,1pct_min,100-year,1pct_plu,500-year
River Rch & RM= UNT024 IN NURI,Reach-1,7209
     279     393     490     450     608     823     952
River Rch & RM= UNT024 IN NURI,Reach-1,5258
     388     556     700     649     878    1187    1400
Boundary for River Rch & Prof#=UNT024 IN NURI,Reach-1,1
Up Type=0
Dn Type=3
Dn Slope=0.005
Boundary for River Rch & Prof#=UNT024 IN NURI,Reach-1,2
Up Type=0
Dn Type=3
Dn Slope=0.005
Boundary for River Rch & Prof#=UNT024 IN NURI,Reach-1,3
Up Type=0
Dn Type=3
Dn Slope=0.005
Boundary for River Rch & Prof#=UNT024 IN NURI,Reach-1,4
Up Type=0
Dn Type=3
Dn Slope=0.005
Boundary for River Rch & Prof#=UNT024 IN NURI,Reach-1,5
Up Type=0
Dn Type=3
Dn Slope=0.005
Boundary for River Rch & Prof#=UNT024 IN NURI,Reach-1,6
Up Type=0
Dn Type=3
Dn Slope=0.005
Boundary for River Rch & Prof#=UNT024 IN NURI,Reach-1,7
Up Type=0
Dn Type=3
Dn Slope=0.005

--- UNT024 IN NURI.g01 (geometry) ---

Geom Title=Existing Conditions
Program Version=4.10

River Reach=UNT024 IN NURI  ,Reach-1
Reach XY= 30
      2282420.56     13275145.67      2282508.75     13275419.65
      2282573.85     13275520.34      2282843.24     13275657.94
      2283362.11     13276088.52      2283464.12      13276134.3
      2283727.59     13276445.97      2283887.68     13276547.37
      2283946.38      13276630.8      2284314.38     13276874.77
       2284450.1     13277020.52      2284557.72     13277226.85
      2284558.73     13277366.33      2284607.83     13277531.81
      2285075.19     13278166.81      2285213.15     13278430.56
      2285393.62      13278689.3       2285398.4     13278780.88
      2285254.39     13279003.19      2285256.21     13279096.42
      2285484.85     13279335.48      2285571.31     13279526.89
      2285567.15     13279878.45      2285590.84     13279982.09
       2285691.1     13280020.64      2285798.92     13280122.46
      2285781.21     13280293.29      2285711.07     13280420.97
      2285868.53     13280647.34      2285941.57     13280921.23

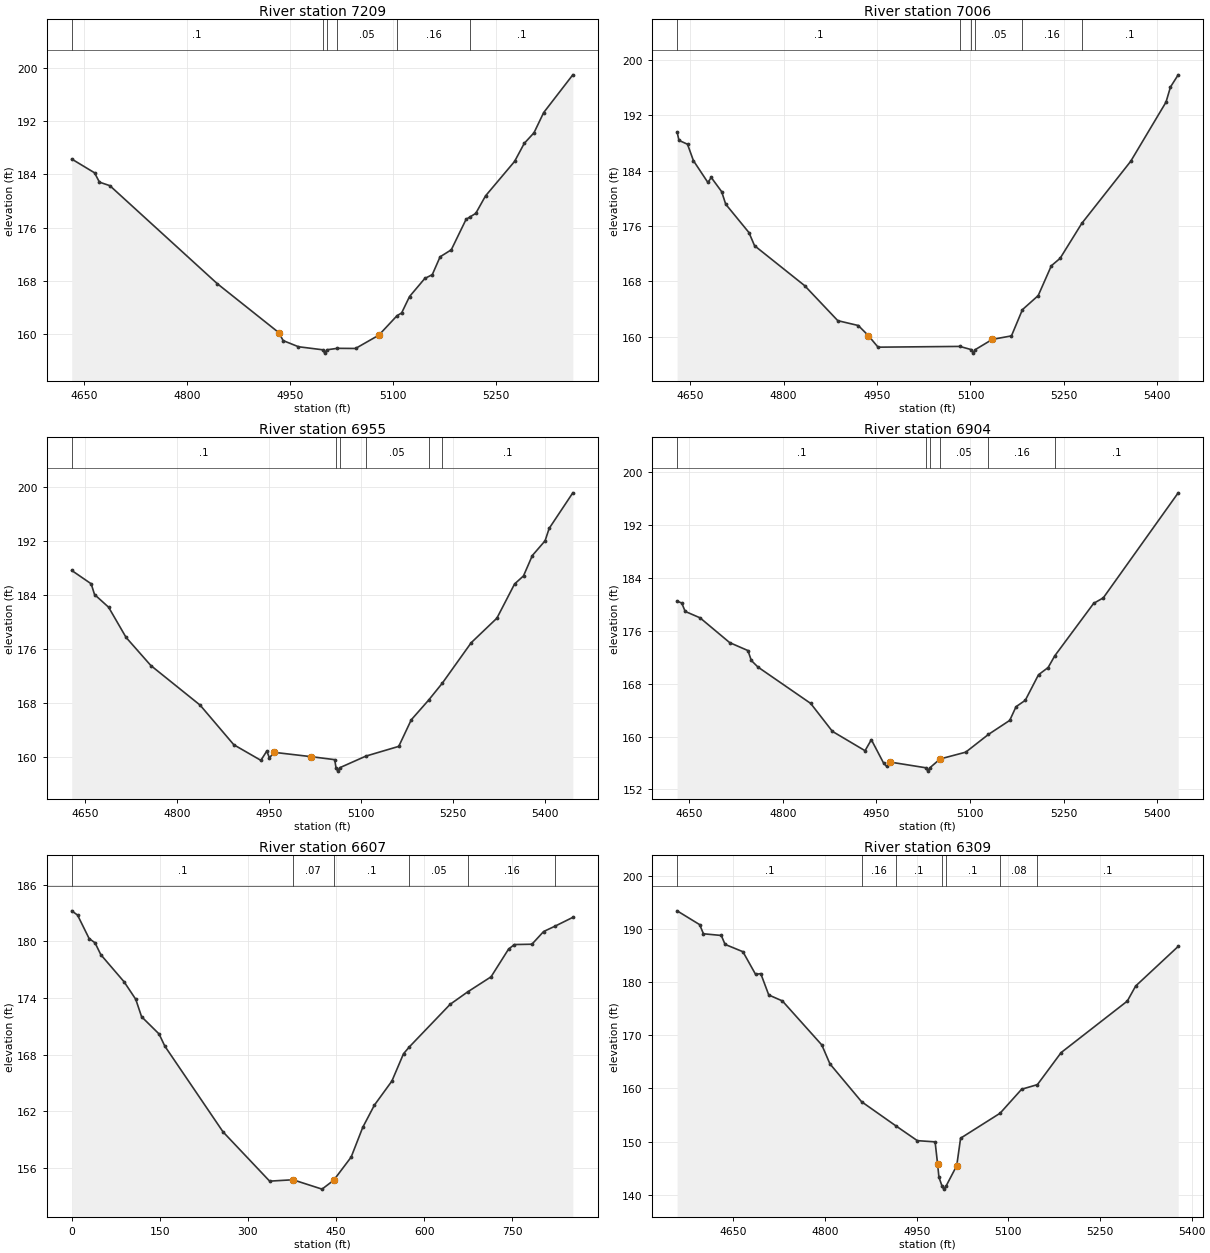
Type RM Length L Ch R = 1 ,7209    ,203,203,203
BEGIN DESCRIPTION:
UNT024 IN NURI 16.0
END DESCRIPTION:
XS GIS Cut Line= 3
      2282168.01     13275520.67      2282662.49     13275272.08
      2282787.76     13275146.82
#Sta/Elev= 30
  4631.8  186.32  4665.1  184.25  4672.2  182.85  4687.4  182.32  4844.1   167.6
  4933.7  160.26  4940.1  159.06  4962.4  158.14  4997.8  157.68  5000.6  157.18
  5003.8  157.68  5019.2   157.9  5045.6  157.88  5079.6  159.88  5106.2  162.81
  5112.8  163.21  5124.3  165.67  5146.6  168.39  5157.5  168.96  5168.9  171.64
  5185.2  172.69  5206.8  177.27  5212.4  177.62  5220.9  178.16  5235.1  180.78
  5277.5  185.96  5291.6  188.67  5305.8  190.26  5319.9  193.29  5362.4  198.96
#Mann= 6 ,-1 , 0
  4631.8      .1       0  4997.8     .07       0  5003.8      .1       0
  5019.2     .05       0  5106.2     .16       0  5212.4      .1       0
Bank Sta=4933.7,5079.6
XS Rating Curve= 0 ,0
Exp/Cntr=0.3,0.1

Type RM Length L Ch R = 1 ,7006    ,51,51,51
BEGIN DESCRIPTION:
Mapping XS 85be9509
END DESCRIPTION:
XS GIS Cut Line= 4
      2282450.32     13275872.06      2282576.19     13275592.12
      2282623.93     13275351.23      2282797.51     13275168.97
#Sta/Elev= 30
  4629.2   189.6  4632.2  188.39  4645.9  187.83  4655.4  185.46  4678.6  182.31
    4684  183.03  4700.7  180.98  4707.2  179.17  4744.5  175.07  4753.5  173.17
  4833.9   167.4  4887.1  162.34    4920  161.64  4936.1  160.19  4951.7  158.51
  5082.9  158.62  5101.6  158.15  5104.4  157.65  5107.6  158.15  5135.2  159.64
  5165.8  160.14  5183.4  163.93  5208.7  165.96  5229.8  170.27  5243.9  171.35
  5278.7   176.4  5357.2  185.37  5413.8  193.91    5421   196.1  5433.4  197.86
#Mann= 6 ,-1 , 0
  4629.2      .1       0  5082.9     .05       0  5101.6     .07       0
  5107.6     .05       0  5183.4     .16       0  5278.7      .1       0
Bank Sta=4936.1,5135.2
XS Rating Curve= 0 ,0
Exp/Cntr=0.3,0.1

Type RM Length L Ch R = 1 ,6955    ,51,51,51
BEGIN DESCRIPTION:
UNT024 IN NURI 15.0
END DESCRIPTION:
XS GIS Cut Line= 4
      2282487.72     13275896.86      2282622.88       13275604.
      2282668.02     13275360.95      2282820.77     13275166.54
#Sta/Elev= 30
  4628.8  187.64  4660.5  185.66    4666  184.07  4688.9  182.19  4717.4  177.71
  4757.8  173.54  4838.1  167.67  4893.1  161.79  4937.2  159.48  4946.8  160.85
  4951.2  159.84  4958.6  160.67  5019.6  160.02  5057.6  159.58  5059.7  158.38
  5062.5  157.88  5065.7  158.38  5108.5  160.11    5162  161.55  5182.4  165.49
  5210.6   168.4    5233  170.92  5280.1  176.92    5322  180.56  5350.9  185.64
  5365.4  186.83  5379.8  189.85  5400.6  192.04  5407.2  193.87  5445.8  199.15
#Mann= 6 ,-1 , 0
  4628.8      .1       0  5059.7     .07       0  5065.7      .1       0
  5108.5     .05       0  5210.6     .16       0    5233      .1       0
Bank Sta=4958.6,5019.6
XS Rating Curve= 0 ,0
Exp/Cntr=0.3,0.1

Type RM Length L Ch R = 1 ,6904    ,219,219,219
BEGIN DESCRIPTION:
Mapping XS de5e984b
END DESCRIPTION:
XS GIS Cut Line= 4
      2282558.81     13275926.35      2282665.16     13275672.41
      2282699.88     13275398.97      2282833.56     13275185.52
#Sta/Elev= 30
  4630.6  180.52  4638.1  180.22  4643.5  178.96  4667.3  177.99  4714.9  174.23
  4744.1  173.03  4749.5  171.53  4760.2  170.53  4844.6  165.03  4879.4   160.8
  4931.7  157.87  4941.8  159.54  4961.4     156  4966.4  155.49    4972  156.15
  5029.5  155.28  5032.2  154.78  5035.5  155.28  5051.9  156.62    5093  157.65
  5129.3  160.33  5163.5  162.46  5173.6  164.53  5188.4   165.5  5209.6  169.37
    5225  170.46  5235.7  172.24    5298  180.18  5313.4  181.01  5433.4  196.91
#Mann= 6 ,-1 , 0
  4630.6      .1       0  5029.5     .07       0  5035.5      .1       0
  5051.9     .05       0  5129.3     .16       0  5235.7      .1       0
Bank Sta=4972,5051.9
XS Rating Curve= 0 ,0
Exp/Cntr=0.3,0.1

Type RM Length L Ch R = 1 ,6607    ,376,376,376
XS GIS Cut Line= 3
     2282685.371    13276031.794     2282952.298    13275487.089
       2282995.7    13275237.523
#Sta/Elev= 30
       0183.25059.909178182.799829.72753180.298939.63671179.865149.54589178.5982
 89.1826175.7218 109.001173.8681118.9101172.0217148.6377170.1943158.5468168.8974
257.6386159.8049 336.912154.5843376.5488154.7321426.0946153.7383 445.913154.6769
475.6405157.1325495.4589 160.295515.2772162.6497545.0048165.1968564.8231168.0974
574.7323168.8217644.2253173.3378674.0494174.6563713.8149176.2525 743.639 179.193
753.5804179.6753783.4045179.7093803.2872181.0563  823.17181.6372852.9941182.5566
#Mann= 6 ,-1 , 0
       0      .1       0376.5488     .07       0 445.913      .1       0
574.7323     .05       0674.0494     .16       0  823.17      .1       0
Bank Sta=376.5488,445.913
XS Rating Curve= 0 ,0
Exp/Cntr=0.3,0.1

Type RM Length L Ch R = 1 ,6309    ,379,379,379
BEGIN DESCRIPTION:
UNT024 IN NURI 14.0
END DESCRIPTION:
XS GIS Cut Line= 2
      2282897.16     13276256.81      2283389.72     13275601.23
#Sta/Elev= 30
    4558  193.45  4594.9  190.85  4601.1  189.13  4630.3  188.81  4636.5  187.13
  4665.7  185.75  4686.5  181.47  4694.9  181.63    4708   177.6  4730.3  176.48
  4794.8  168.19  4808.1  164.63  4859.9   157.5  4915.7  152.98  4951.1  150.17
  4980.2  149.94 4984.21  145.84  4986.5  143.26  4991.8  141.54  4994.5  141.04
  4997.8  141.54  5015.6  145.46  5021.9  150.63  5086.5  155.33  5121.8  159.85
  5147.6  160.72  5186.4  166.75  5294.7  176.45  5308.4  179.29    5378  186.75
#Mann= 7 ,-1 , 0
    4558      .1       0  4859.9     .16       0  4915.7      .1       0
  4991.8     .07       0  4997.8      .1       0  5086.5     .08       0
  5147.6      .1       0
Bank Sta=4984.21,5015.6
XS Rating Curve= 0 ,0
Exp/Cntr=0.3,0.1

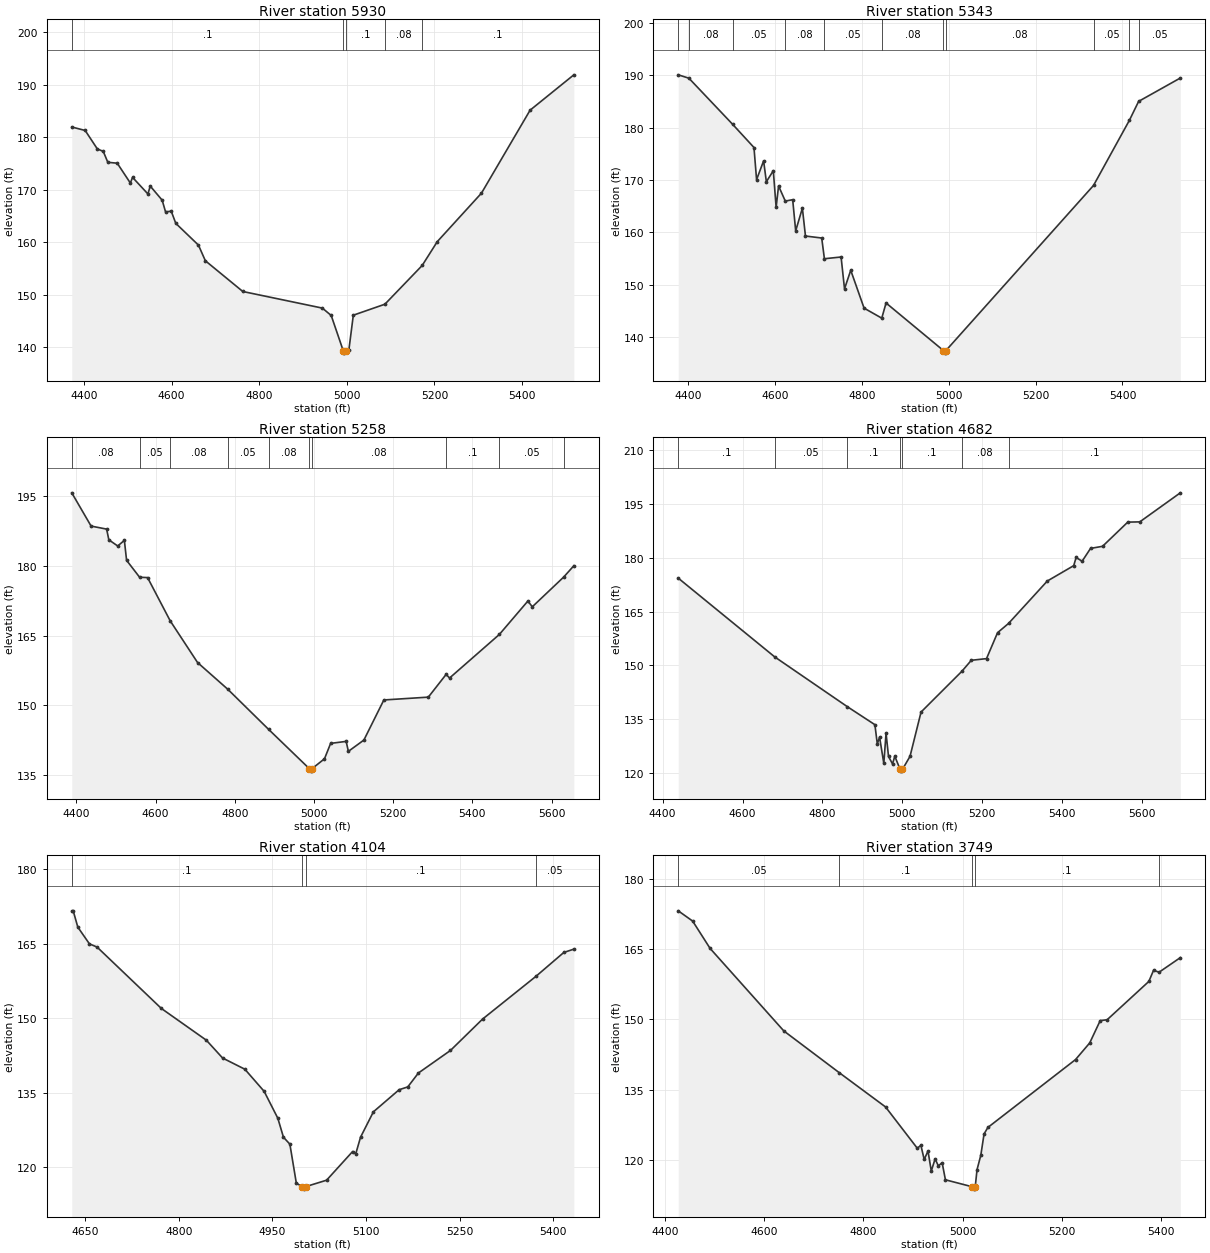
Type RM Length L Ch R = 1 ,5930    ,587,587,587
BEGIN DESCRIPTION:
UNT024 IN NURI 13.0
END DESCRIPTION:
XS GIS Cut Line= 3
      2283337.28      13276746.4      2283415.41     13276451.22
      2283528.26     13275617.88
#Sta/Elev= 30
  4371.9  181.96  4402.5   181.3  4430.3  177.78  4443.8  177.32  4454.2  175.24
  4475.7  175.07  4505.6   171.3  4510.7  172.37  4545.8  169.21    4551  170.72
  4578.3  168.03    4586  165.81    4599  165.93  4609.4  163.62  4661.1  159.48
  4676.9   156.5  4762.4  150.65    4944  147.49  4964.2  146.09  4991.5  139.42
  4994.2  138.92  4997.5  139.42  5004.6  139.55  5014.7  146.14  5086.8  148.23
  5171.9   155.6  5206.4  160.14  5307.3  169.37  5418.3  185.16  5518.2  191.89
#Mann= 5 ,-1 , 0
  4371.9      .1       0  4991.5     .07       0  4997.5      .1       0
  5086.8     .08       0  5171.9      .1       0
Bank Sta=4991.5,4997.5
XS Rating Curve= 0 ,0
Exp/Cntr=0.3,0.1

Type RM Length L Ch R = 1 ,5343    ,85,85,85
BEGIN DESCRIPTION:
UNT024 IN NURI 12.0
END DESCRIPTION:
XS GIS Cut Line= 3
      2283311.26     13276811.46      2283996.14     13276475.53
      2284056.05     13276087.46
#Sta/Elev= 30
  4377.6  190.05  4402.1  189.41  4502.6  180.63  4551.9  176.19  4557.9  170.06
  4574.1  173.65  4580.4  169.66  4596.4  171.77  4602.9  164.78  4608.5  168.86
    4624  165.97    4641  166.24  4647.9   160.3  4663.3  164.62  4670.4  159.31
  4707.8  158.93    4714  154.98  4752.4  155.31  4760.3  149.24  4774.6  152.78
  4805.3  145.56    4846  143.65  4855.9  146.54  4987.8  137.48  4990.6  136.98
  4993.8  137.48  5333.4  168.96    5416  181.39  5437.2  184.99  5533.1  189.44
#Mann= 11 ,-1 , 0
  4377.6     .05       0  4402.1     .08       0  4502.6     .05       0
    4624     .08       0    4714     .05       0    4846     .08       0
  4987.8     .07       0  4993.8     .08       0  5333.4     .05       0
    5416      .1       0  5437.2     .05       0
Bank Sta=4987.8,4993.8
XS Rating Curve= 0 ,0
Exp/Cntr=0.3,0.1

Type RM Length L Ch R = 1 ,5258    ,576,576,576
BEGIN DESCRIPTION:
UNT024 IN NURI 11.0
END DESCRIPTION:
XS GIS Cut Line= 3
      2283376.33     13276872.24      2284109.86     13276507.65
       2284153.2     13276061.19
#Sta/Elev= 30
  4388.5  195.79  4437.3  188.62  4476.5  187.97  4482.1  185.66  4504.5  184.33
  4521.3  185.54  4526.9  181.24  4559.8  177.59  4579.9  177.52    4637   168.2
  4706.1  159.21  4782.4  153.45  4885.5   144.8  4988.7   136.3  4991.5   135.8
  4994.7   136.3  5026.6  138.46  5042.1  141.78  5081.3  142.21  5086.9  140.06
  5126.1   142.5  5176.5  151.14  5288.8  151.75  5333.7  156.65  5342.4  155.87
  5468.2  165.27    5540  172.45  5551.4  171.23  5630.5  177.63  5656.2  180.07
#Mann= 10 ,-1 , 0
  4388.5     .08       0  4559.8     .05       0    4637     .08       0
  4782.4     .05       0  4885.5     .08       0  4988.7     .07       0
  4994.7     .08       0  5333.7      .1       0  5468.2     .05       0
  5630.5      .1       0
Bank Sta=4988.7,4994.7
XS Rating Curve= 0 ,0
Exp/Cntr=0.3,0.1

Type RM Length L Ch R = 1 ,4682    ,578,578,578
BEGIN DESCRIPTION:
UNT024 IN NURI 10.0
END DESCRIPTION:
XS GIS Cut Line= 4
      2283840.75      13277063.2      2284218.36     13277028.48
      2284604.65     13276820.15      2284847.72     13276455.54
#Sta/Elev= 30
  4439.2  174.32  4680.6  152.35  4862.4  138.46  4931.3  133.44  4937.3  128.06
    4943  129.99  4953.6  122.65  4959.2  131.05  4965.4  124.57  4975.4   122.5
  4981.1  124.65  4994.3  120.99  4997.1  120.49  5000.3  120.99  5019.2  124.62
  5046.8  136.97    5149  148.34  5172.5   151.4  5210.6  151.87  5238.2   159.1
  5265.6  161.67  5362.7  173.51  5428.8   177.8  5434.8  180.08  5449.8  179.03
  5470.9  182.61  5500.9  183.19    5564  189.94  5594.1  190.01  5695.5  198.11
#Mann= 7 ,-1 , 0
  4439.2      .1       0  4680.6     .05       0  4862.4      .1       0
  4994.3     .07       0  5000.3      .1       0    5149     .08       0
  5265.6      .1       0
Bank Sta=4994.3,5000.3
XS Rating Curve= 0 ,0
Exp/Cntr=0.3,0.1

Type RM Length L Ch R = 1 ,4104    ,355,355,355
BEGIN DESCRIPTION:
UNT024 IN NURI 9.0
END DESCRIPTION:
XS GIS Cut Line= 2
      2284218.33     13277549.32      2284999.63     13277358.34
#Sta/Elev= 30
  4628.7  171.67    4631  171.67  4638.4  168.38    4657  165.01  4669.2  164.37
  4772.2     152  4844.3   145.6  4870.3  142.01    4906  139.75  4936.9  135.29
  4958.8  129.87  4967.8  126.05  4978.1  124.65  4988.4  116.82  4997.4  116.09
  5000.2  115.59  5003.4  116.09  5036.9  117.39  5078.6  123.17  5083.7  122.74
  5091.3  126.05  5111.9  131.17  5153.1  135.62    5167  136.19    5184  138.99
  5235.4  143.54  5286.8  149.86  5372.2  158.46  5416.9  163.28    5433  163.95
#Mann= 4 ,-1 , 0
  4628.7      .1       0  4997.4     .07       0  5003.4      .1       0
  5372.2     .05       0
Bank Sta=4997.4,5003.4
XS Rating Curve= 0 ,0
Exp/Cntr=0.3,0.1

Type RM Length L Ch R = 1 ,3749    ,463,463,463
BEGIN DESCRIPTION:
UNT024 IN NURI 8.0
END DESCRIPTION:
XS GIS Cut Line= 4
      2284374.73     13278154.71      2284631.96     13277916.53
      2284974.92     13277516.41      2285003.12     13277384.85
#Sta/Elev= 30
  4426.8  173.16  4455.9  170.97    4491  165.15  4639.6  147.56  4751.2  138.67
  4844.7  131.35  4908.6  122.56    4916  123.16  4922.6  120.15  4930.3  121.96
  4936.9  117.68  4944.6  120.28  4951.1  118.79  4958.8  119.46  4965.4  115.82
  5019.5  114.33  5022.2  113.83  5025.5  114.33  5029.1  117.96  5036.8  121.08
  5043.3   125.6    5051  126.98  5227.7  141.45  5256.3     145  5277.4  149.75
  5291.4  149.94  5375.5  158.11  5384.9  160.47  5396.2  160.08  5438.9  163.18
#Mann= 5 ,-1 , 0
  4426.8     .05       0  4751.2      .1       0  5019.5     .07       0
  5025.5      .1       0  5396.2     .05       0
Bank Sta=5019.5,5025.5
XS Rating Curve= 0 ,0
Exp/Cntr=0.3,0.1

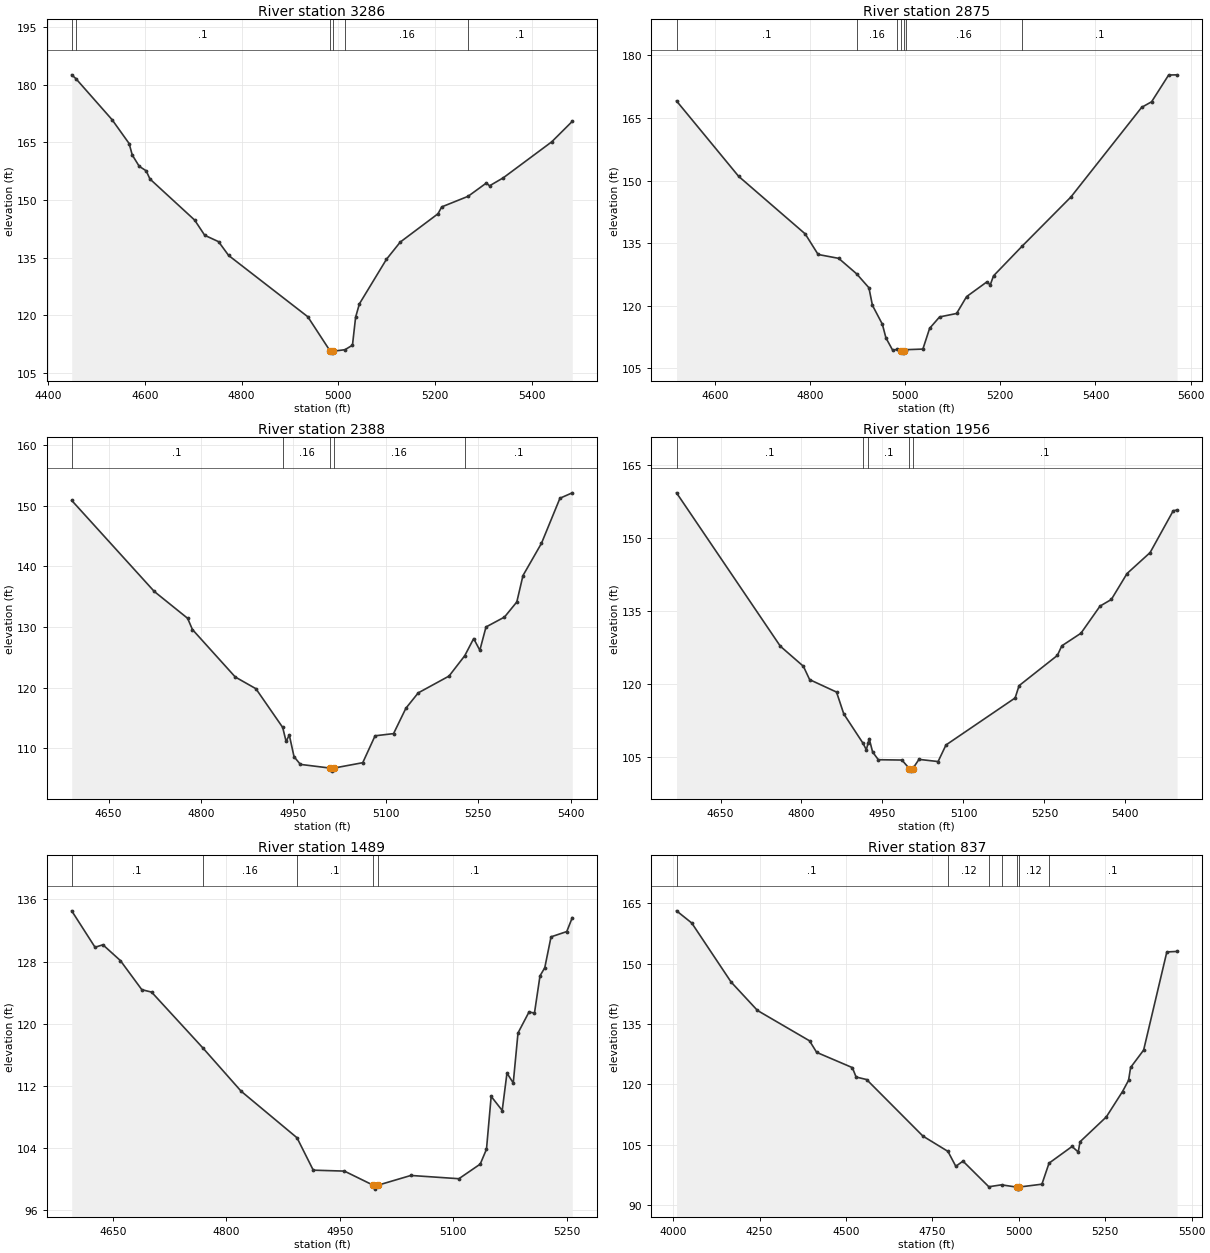
Type RM Length L Ch R = 1 ,3286    ,411,411,411
BEGIN DESCRIPTION:
UNT024 IN NURI 7.0
END DESCRIPTION:
XS GIS Cut Line= 3
      2284651.05     13278507.16       2284860.6     13278335.71
      2285356.01     13277754.56
#Sta/Elev= 30
  4448.9  182.61  4457.4  181.64  4532.4  170.92  4567.6  164.72    4574  161.75
  4588.4   158.8  4602.8  157.62  4610.6  155.49    4703  144.79  4723.8  140.83
  4752.4  139.17  4773.2  135.58  4936.8  119.62  4983.2  110.65    4986  110.15
  4989.2  110.65  5013.6  111.04  5029.1  112.22  5035.6  119.51  5043.4  122.98
  5099.3  134.58  5127.9  139.07  5205.8  146.43  5213.5  148.22    5268  150.98
  5305.8  154.44  5312.3  153.71  5340.9  155.81  5440.8  165.16  5483.3  170.49
#Mann= 6 ,-1 , 0
  4448.9     .16       0  4457.4      .1       0  4983.2     .07       0
  4989.2      .1       0  5013.6     .16       0    5268      .1       0
Bank Sta=4983.2,4989.2
XS Rating Curve= 0 ,0
Exp/Cntr=0.3,0.1

Type RM Length L Ch R = 1 ,2875    ,487,487,487
BEGIN DESCRIPTION:
UNT024 IN NURI 6.0
END DESCRIPTION:
XS GIS Cut Line= 3
      2284821.71     13278682.11      2285125.48     13278586.64
      2285668.02     13278091.85
#Sta/Elev= 30
    4519  169.09  4649.6  151.01  4789.6   137.2  4816.8  132.26  4860.1  131.33
  4897.7  127.63  4923.6  124.28    4931  120.07  4951.9  115.53  4959.4  112.25
  4973.6  109.29  4982.1  109.49  4991.5   109.1  4994.3   108.6  4997.5   109.1
  5002.6  109.43  5037.1  109.57  5051.3  114.55  5072.2  117.28    5108  118.11
    5129  122.15  5171.5  125.67  5178.8  124.98  5185.7  127.14  5245.7  134.24
  5348.5  146.06  5497.2  167.55  5518.1  168.89  5553.9   175.3  5571.7  175.35
#Mann= 7 ,-1 , 0
    4519      .1       0  4897.7     .16       0  4982.1      .1       0
  4991.5     .07       0  4997.5      .1       0  5002.6     .16       0
  5245.7      .1       0
Bank Sta=4991.5,4997.5
XS Rating Curve= 0 ,0
Exp/Cntr=0.3,0.1

Type RM Length L Ch R = 1 ,2388    ,432,432,432
BEGIN DESCRIPTION:
UNT024 IN NURI 5.0
END DESCRIPTION:
XS GIS Cut Line= 3
       2284937.7     13278796.85      2285337.72     13278896.85
      2285737.69     13278896.85
#Sta/Elev= 30
  4590.1  150.85  4724.1  135.85  4778.2  131.43    4786  129.58  4855.5  121.76
    4889  119.83  4932.5  113.45    4938  111.14  4943.2   112.2  4950.9  108.63
  4961.2  107.36  5009.4  106.75  5012.2  106.25  5015.4  106.75  5062.4  107.64
  5082.4  112.07  5112.4  112.43  5132.4  116.61  5152.4  119.14  5202.4  121.91
  5227.9  125.26  5242.4  128.09  5252.4  126.16  5262.4     130  5292.4  131.63
  5312.4  134.12  5322.4  138.47  5352.4  143.78  5382.4  151.21  5402.4   152.1
#Mann= 5 ,-1 , 0
  4590.1      .1       0  4932.5     .16       0  5009.4     .07       0
  5015.4     .16       0  5227.9      .1       0
Bank Sta=5009.4,5015.4
XS Rating Curve= 0 ,0
Exp/Cntr=0.3,0.1

Type RM Length L Ch R = 1 ,1956    ,467,467,467
BEGIN DESCRIPTION:
UNT024 IN NURI 4.0
END DESCRIPTION:
XS GIS Cut Line= 3
      2284987.68     13279396.87      2285387.72     13279246.85
      2285787.68     13278946.88
#Sta/Elev= 30
  4568.5  159.29  4760.8  127.72  4803.5  123.59  4815.1  120.84  4864.9  118.28
  4878.3  113.79    4914  107.74  4920.1   106.4  4923.5  107.88  4925.4   108.7
  4931.7  105.96  4942.3  104.36    4986  104.29    5000  102.51  5002.8  102.01
    5006  102.51  5017.6  104.43    5053  103.98  5067.6  107.39  5195.7  117.07
    5203   119.6  5273.9  125.82  5282.2   127.8  5317.6  130.39    5353  135.98
  5373.9  137.34    5403  142.68  5445.7  146.99  5488.5  155.59  5495.7  155.76
#Mann= 5 ,-1 , 0
  4568.5      .1       0    4914     .16       0  4923.5      .1       0
    5000     .07       0    5006      .1       0
Bank Sta=5000,5006
XS Rating Curve= 0 ,0
Exp/Cntr=0.3,0.1

Type RM Length L Ch R = 1 ,1489    ,652,652,652
BEGIN DESCRIPTION:
UNT024 IN NURI 3.0
END DESCRIPTION:
XS GIS Cut Line= 3
       2285187.7     13279746.86      2285587.72     13279646.85
       2285787.7     13279496.87
#Sta/Elev= 30
  4595.2  134.54  4626.1  129.85  4636.5  130.17  4659.6  128.14    4688  124.39
  4700.9  124.08  4768.5  116.92  4819.4  111.32  4893.3  105.33  4914.8  101.16
    4956  101.04  4994.2   99.22    4997   98.72  5000.2   99.22    5044  100.48
  5107.5  100.06  5135.7  101.94    5144  103.86  5150.2  110.66  5164.8  108.84
  5171.1  113.66  5179.4  112.38  5185.7  118.82  5200.2  121.51  5207.5  121.39
  5214.8  126.17  5221.1  127.21  5229.4  131.19  5250.2  131.87  5257.5  133.66
#Mann= 5 ,-1 , 0
  4595.2      .1       0  4768.5     .16       0  4893.3      .1       0
  4994.2     .07       0  5000.2      .1       0
Bank Sta=4994.2,5000.2
XS Rating Curve= 0 ,0
Exp/Cntr=0.3,0.1

Type RM Length L Ch R = 1 ,837     ,369,369,369
BEGIN DESCRIPTION:
UNT024 IN NURI 2.0
END DESCRIPTION:
XS GIS Cut Line= 3
      2284844.99     13280439.88      2285656.63     13280231.55
       2286216.5      13279988.5
#Sta/Elev= 30
  4009.6  163.14  4053.7  160.11  4167.5  145.43  4243.9  138.35  4394.4  130.81
  4415.1  127.93  4518.3  124.14  4529.2   121.8  4559.6  121.17  4722.6   107.1
  4794.9   103.3  4817.7   99.58  4838.4  100.88  4913.2    94.5  4949.9   94.98
  4993.7   94.41  4996.4   93.91  4999.7   94.41  5066.8   95.14  5087.4  100.37
    5154  104.52  5171.8  103.15  5177.2   105.7  5253.1  111.87    5300  118.19
  5317.5  120.98  5323.4  124.17  5361.1   128.5  5428.2  152.91  5457.9  153.04
#Mann= 7 ,-1 , 0
  4009.6      .1       0  4794.9     .12       0  4913.2      .1       0
  4949.9     .12       0  4993.7     .07       0  4999.7     .12       0
  5087.4      .1       0
Bank Sta=4993.7,4999.7
XS Rating Curve= 0 ,0
Exp/Cntr=0.3,0.1

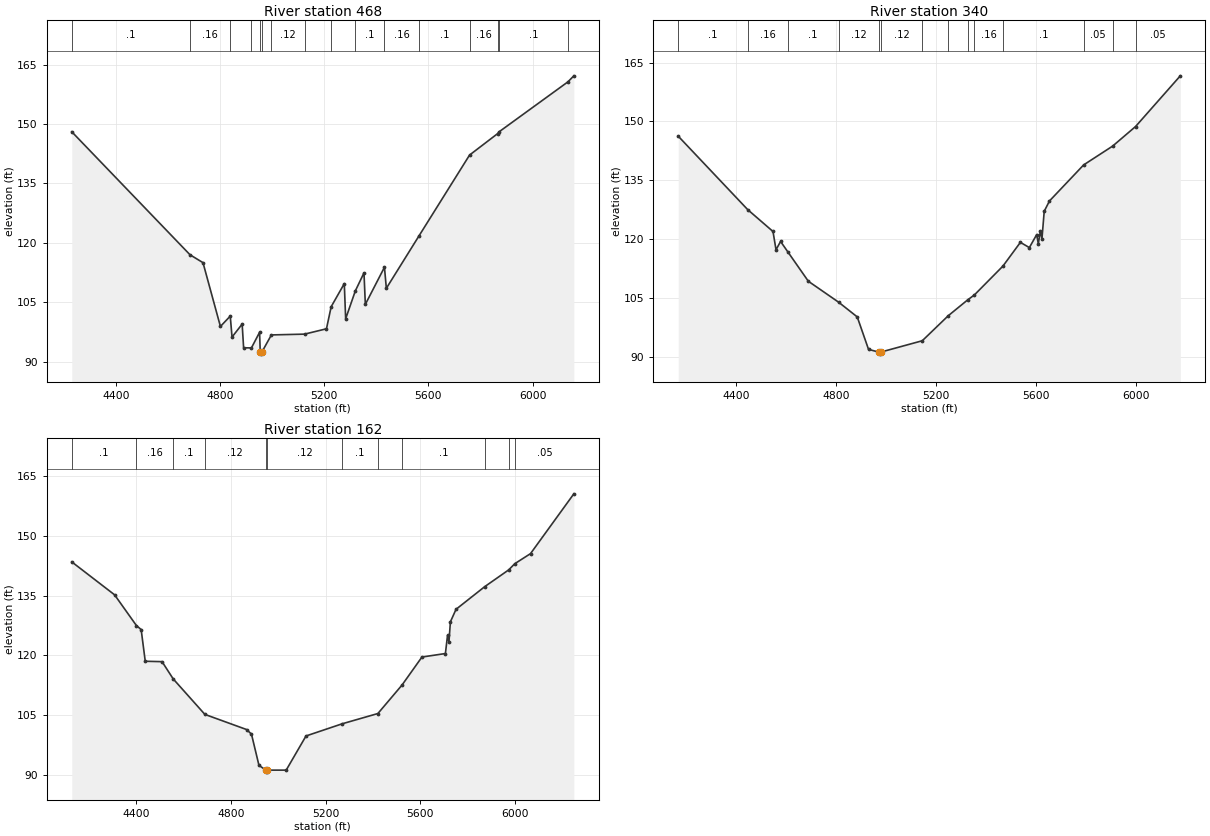
Type RM Length L Ch R = 1 ,468     ,128,128,128
BEGIN DESCRIPTION:
Mapping XS 8ed3d427
END DESCRIPTION:
XS GIS Cut Line= 5
      2285033.76     13280619.27      2285424.42     13280671.36
      2285802.03     13280480.39      2286331.54      13280341.5
      2286631.03     13279864.05
#Sta/Elev= 30
  4230.4  148.04  4684.6  116.97  4734.4  114.98  4801.3   98.87  4839.1  101.48
  4845.9   96.19  4884.8   99.47  4890.4   93.48  4920.4   93.45  4951.7   97.39
  4954.3   92.38    4957   91.88  4960.3   92.38  4997.1   96.73  5124.4   96.93
  5208.6   98.28  5226.7  103.86  5277.1  109.69  5282.3  100.81  5319.6  107.87
  5352.7  112.41  5357.9  104.45  5431.3  113.82  5438.6  108.51  5564.3  121.78
  5758.2  142.16  5866.3  147.59  5872.6  148.08    6136  160.65  6158.7  162.17
#Mann= 16 ,-1 , 0
  4230.4      .1       0  4684.6     .16       0  4839.1     .12       0
  4920.4     .16       0  4954.3     .07       0  4960.3     .16       0
  4997.1     .12       0  5124.4      .1       0  5226.7     .12       0
  5319.6      .1       0  5431.3     .16       0  5564.3      .1       0
  5758.2     .16       0  5866.3     .05       0  5872.6      .1       0
    6136     .05       0
Bank Sta=4954.3,4960.3
XS Rating Curve= 0 ,0
Exp/Cntr=0.3,0.1

Type RM Length L Ch R = 1 ,340     ,178,178,178
BEGIN DESCRIPTION:
Mapping XS b425b6ee
END DESCRIPTION:
XS GIS Cut Line= 5
      2285042.46     13280658.34      2285571.99     13280732.13
      2285910.53      13280567.2       2286327.2     13280432.65
      2286687.29     13279881.66
#Sta/Elev= 30
  4168.1  146.25  4445.9  127.53    4547  121.96    4559  117.31  4577.3  119.42
  4605.7  116.82  4688.3  109.28  4809.4  103.94  4883.8  100.19  4928.9   91.92
  4970.9   91.21  4973.7   90.71  4976.9   91.21  5143.8   94.12  5247.9  100.51
  5325.6  104.55  5352.1  105.79  5466.3  113.15    5536  119.19  5571.9  117.86
  5601.1  121.16  5607.7  118.86  5616.2  122.14  5622.2  120.07  5631.3  127.12
  5652.4  129.75    5789  138.93  5904.8  143.72  5996.5  148.71  6175.4  161.63
#Mann= 14 ,-1 , 0
  4168.1      .1       0  4445.9     .16       0  4605.7      .1       0
  4809.4     .12       0  4970.9     .07       0  4976.9     .12       0
  5143.8      .1       0  5247.9     .16       0  5325.6      .1       0
  5352.1     .16       0  5466.3      .1       0    5789     .05       0
  5904.8      .1       0  5996.5     .05       0
Bank Sta=4970.9,4976.9
XS Rating Curve= 0 ,0
Exp/Cntr=0.3,0.1

Type RM Length L Ch R = 1 ,162     ,0,0,0
BEGIN DESCRIPTION:
UNT024 IN NURI 1.0
END DESCRIPTION:
XS GIS Cut Line= 4
      2285051.69     13280700.35      2285728.78     13280821.88
      2286206.21     13280669.97      2286727.06     13279893.04
#Sta/Elev= 30
  4126.3  143.45  4307.4  135.19  4399.7  127.49  4419.9  126.47  4437.2  118.52
  4508.3  118.42  4555.5  114.09  4689.5  105.19  4865.6   101.4  4886.6  100.25
  4918.3   92.41  4947.5   91.21  4950.3   90.71  4953.5   91.21  5033.5   91.21
  5117.4   99.78  5271.2  102.85  5421.5  105.41  5523.7  112.56  5607.9  119.58
  5707.2  120.46  5716.1     125  5722.2  123.39  5728.3  128.41  5752.1  131.55
  5873.4  137.23  5974.9  141.44  6000.9     143  6067.3  145.52  6250.6  160.52
#Mann= 12 ,-1 , 0
  4126.3      .1       0  4399.7     .16       0  4555.5      .1       0
  4689.5     .12       0  4947.5     .07       0  4953.5     .12       0
  5271.2      .1       0  5421.5     .16       0  5523.7      .1       0
  5873.4     .05       0  5974.9      .1       0  6000.9     .05       0
Bank Sta=4947.5,4953.5
XS Rating Curve= 0 ,0
Exp/Cntr=0.3,0.1

Chan Stop Cuts=-1
Use User Specified Reach Order=0
Composite Channel Slope=5