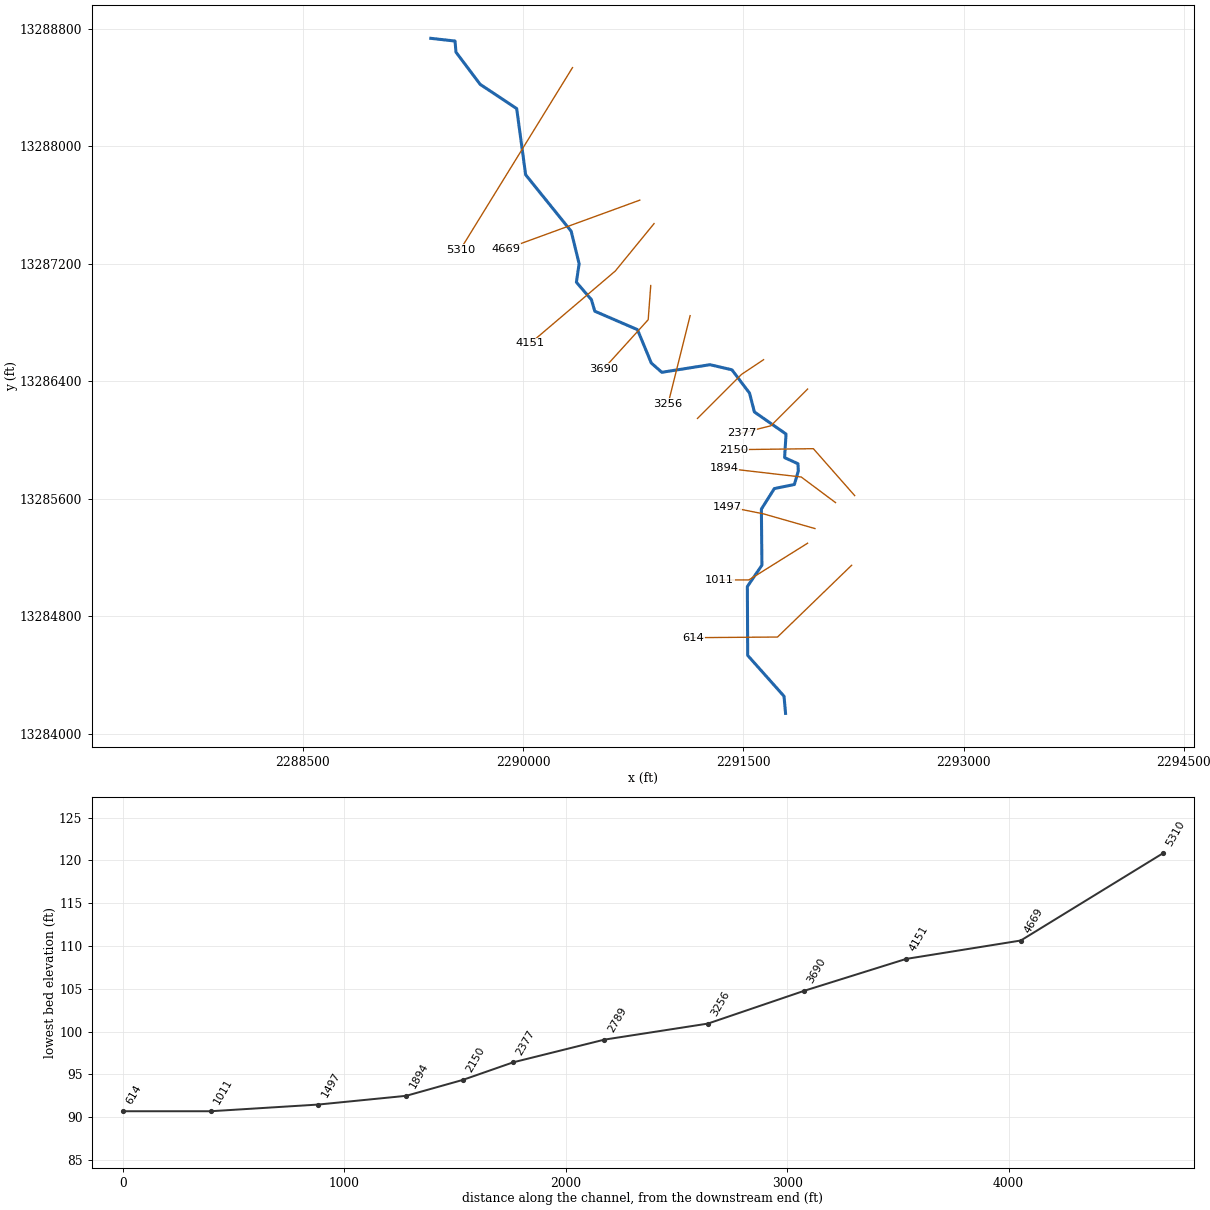
--- UNT025 IN NURI.prj (project) ---

Proj Title=UNT025 IN NURI Base Level Engineering
Current Plan=p01
Default Exp/Contr=0.3,0.1
English Units
Geom File=g01
Flow File=f01
Plan File=p01
Y Axis Title=Elevation
X Axis Title(PF)=Main Channel Distance
X Axis Title(XS)=Station
BEGIN DESCRIPTION:
UNT025 IN NURI
END DESCRIPTION:
DSS Export Rating Curves= 0
DSS Export Rating Curve Sorted= 0
DSS Export Volume Flow Curves= 0
DXF OffsetX= 0
DXF OffsetY= 0
DXF ScaleX= 1
DXF ScaleY= 10

--- UNT025 IN NURI.p01 (plan) ---

Plan Title=Multiple Run
Short Identifier=Multiple
Geom File=g01
Flow File=f01
Subcritical Flow
K Sum by GR= 0
Std Step Tol= 0.01
Critical Tol= 0.01
Num of Std Step Trials= 20
Max Error Tol= 0.3
Flow Tol Ratio= 0.001
Split Flow NTrial= 30
Split Flow Tol= 0.02
Split Flow Ratio= 0.02
Log Output Level= 0
Friction Slope Method= 1
Unsteady Friction Slope Method= 2
Unsteady Bridges Friction Slope Method= 1
Parabolic Critical Depth
Global Vel Dist=  1 , 1 , 1
Global Log Level= 0
CheckData=True
Encroach Param= -1, 0, 0, 0
BEGIN DESCRIPTION:
Multiple Run
END DESCRIPTION:

--- UNT025 IN NURI.f01 (steady flow) ---

Flow Title=Multiple
Program Version=4.10
Number of Profiles= 7
Profile Names=10-year,25-year,50-year,1pct_min,100-year,1pct_plu,500-year
River Rch & RM=UNT025 IN NURI,Reach-1         ,5310
     442     609     746     667     902    1221    1333
River Rch & RM=UNT025 IN NURI,Reach-1         ,2150
     992    1420    1781    1626    2199    2974    3380
River Rch & RM=UNT025 IN NURI,Reach-1         ,1894
     992    1420    1781    1626    2199    2974    3380
Boundary for River Rch & Prof#=UNT025 IN NURI,Reach-1         , 1
Up Type= 0
Dn Type= 3
Dn Slope=0.005
Boundary for River Rch & Prof#=UNT025 IN NURI,Reach-1         , 2
Up Type= 0
Dn Type= 3
Dn Slope=0.005
Boundary for River Rch & Prof#=UNT025 IN NURI,Reach-1         , 3
Up Type= 0
Dn Type= 3
Dn Slope=0.005
Boundary for River Rch & Prof#=UNT025 IN NURI,Reach-1         , 4
Up Type= 0
Dn Type= 3
Dn Slope=0.005
Boundary for River Rch & Prof#=UNT025 IN NURI,Reach-1         , 5
Up Type= 0
Dn Type= 3
Dn Slope=0.005
Boundary for River Rch & Prof#=UNT025 IN NURI,Reach-1         , 6
Up Type= 0
Dn Type= 3
Dn Slope=0.005
Boundary for River Rch & Prof#=UNT025 IN NURI,Reach-1         , 7
Up Type= 0
Dn Type= 3
Dn Slope=0.005
DSS Import GetInterval= 0
DSS Import GetPeak= 0
DSS Import FillOption= 0

--- UNT025 IN NURI.g01 (geometry) ---

Geom Title=Existing Conditions
Program Version=4.10

River Reach=UNT025 IN NURI  ,Reach-1
Reach XY= 30
      2289371.47     13288735.68       2289536.4     13288717.24
      2289542.91     13288641.28      2289707.84      13288422.1
      2289956.32     13288257.17      2290017.44      13287806.4
      2290327.57      13287421.8      2290381.59     13287200.62
      2290363.13     13287074.19      2290465.25     13286955.96
       2290488.4     13286877.06      2290778.97     13286751.64
      2290873.21     13286524.03      2290944.76     13286461.11
      2291272.81     13286512.83      2291422.19     13286478.11
      2291542.31     13286319.33      2291575.41     13286190.93
      2291790.94     13286040.48      2291781.17     13285879.89
      2291872.16     13285838.29      2291874.56     13285788.78
      2291847.72     13285696.85      2291711.26     13285669.12
      2291622.99     13285529.39      2291626.61     13285147.01
      2291527.48     13285001.95      2291529.78     13284532.71
      2291777.19     13284254.84       2291787.6     13284137.98

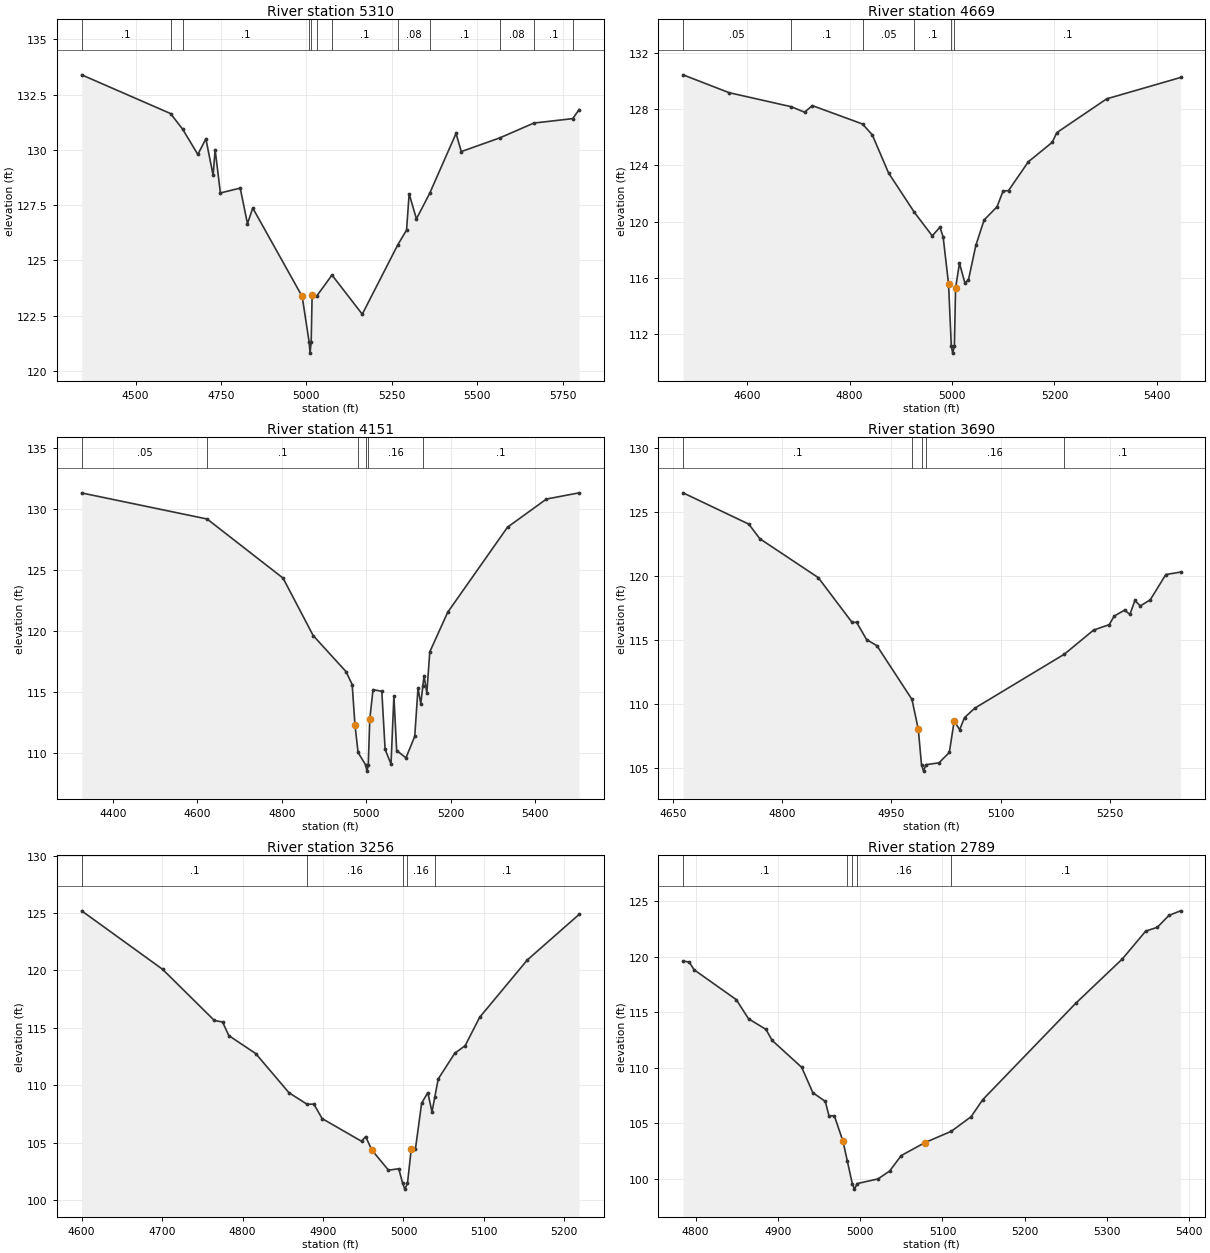
Type RM Length L Ch R = 1 ,5310    ,641,641,641
BEGIN DESCRIPTION:
UNT025 IN NURI 11.0
END DESCRIPTION:
XS GIS Cut Line= 2
      2290336.46     13288536.33      2289572.65     13287296.88
#Sta/Elev= 30
  4342.2  133.39  4602.2  131.64  4637.5  130.94  4682.2  129.79  4705.7   130.5
  4726.9  128.85  4732.8  130.01  4748.2  128.05  4806.2  128.27  4827.5  126.66
  4842.9  127.37  4987.6  123.37  5007.9  121.31  5010.6  120.81  5013.9  121.31
  5016.7  123.45  5030.1  123.39  5074.8  124.34  5163.4  122.57  5267.5  125.71
    5293  126.37  5300.6  128.01  5321.9  126.88  5360.6  128.03  5437.8  130.74
  5453.2  129.92  5565.9  130.54  5665.6  131.21  5779.2  131.41  5798.1  131.82
#Mann= 12 ,-1 , 0
  4342.2      .1       0  4602.2     .05       0  4637.5      .1       0
  5007.9     .07       0  5013.9      .1       0  5030.1     .08       0
  5074.8      .1       0  5267.5     .08       0  5360.6      .1       0
  5565.9     .08       0  5665.6      .1       0  5779.2     .08       0
Bank Sta=4987.6,5016.7
XS Rating Curve= 0 ,0
Exp/Cntr=0.3,0.1

Type RM Length L Ch R = 1 ,4669    ,518,518,518
BEGIN DESCRIPTION:
UNT025 IN NURI 10.0
END DESCRIPTION:
XS GIS Cut Line= 2
      2290794.82     13287633.55      2289882.13      13287300.4
#Sta/Elev= 30
  4474.8  130.45  4564.7  129.18  4686.1  128.18  4712.1  127.79  4727.2  128.26
  4825.3  126.95  4844.3  126.18  4876.2  123.46  4926.6  120.66  4961.4  118.99
  4976.5   119.6  4982.7  118.92  4993.3  115.57  4998.7  111.14  5001.4  110.64
  5004.7  111.14    5007  115.26  5014.6  117.04  5025.3  115.63  5032.2  115.86
  5046.6  118.31  5062.8  120.12    5088  121.06  5099.8  122.18  5110.4  122.21
  5149.1  124.26  5195.6  125.64  5204.9  126.34  5302.1  128.74  5446.4  130.26
#Mann= 6 ,-1 , 0
  4474.8     .05       0  4686.1      .1       0  4825.3     .05       0
  4926.6      .1       0  4998.7     .07       0  5004.7      .1       0
Bank Sta=4993.3,5007
XS Rating Curve= 0 ,0
Exp/Cntr=0.3,0.1

Type RM Length L Ch R = 1 ,4151    ,461,461,461
BEGIN DESCRIPTION:
UNT025 IN NURI 9.0
END DESCRIPTION:
XS GIS Cut Line= 3
      2290891.99     13287473.79      2290628.11      13287150.9
      2290048.29     13286657.87
#Sta/Elev= 30
  4325.8  131.33  4622.9  129.19  4802.7  124.34  4874.1  119.62  4952.1  116.65
  4966.4   115.6    4973  112.31  4980.4  110.02  4998.5  108.99  5001.3  108.49
  5004.5  108.99  5008.1  112.76  5015.8  115.18  5036.6  115.04  5044.4  110.28
  5058.4  109.07  5065.2  114.66  5071.8  110.18  5093.8  109.58  5114.6  111.35
  5122.3  115.31  5128.9  114.02  5133.9  115.52  5136.6  116.33  5143.2  114.91
  5150.2  118.28  5192.6  121.53  5334.3  128.52  5426.5  130.83  5503.9  131.34
#Mann= 6 ,-1 , 0
  4325.8     .05       0  4622.9      .1       0  4980.4     .16       0
  4998.5     .07       0  5004.5     .16       0  5133.9      .1       0
Bank Sta=4973,5008.1
XS Rating Curve= 0 ,0
Exp/Cntr=0.3,0.1

Type RM Length L Ch R = 1 ,3690    ,434,434,434
BEGIN DESCRIPTION:
UNT025 IN NURI 8.0
END DESCRIPTION:
XS GIS Cut Line= 3
      2290869.43     13287051.95      2290852.07      13286819.3
      2290550.02       13286486.
#Sta/Elev= 30
    4664  126.53  4754.3  124.08  4769.4  122.94  4849.6   119.9    4896   116.4
  4902.3   116.4    4916  115.05  4930.2  114.57  4978.3  110.37    4987  108.04
  4991.4  105.26  4994.2  104.76  4997.4  105.26  5015.4  105.41  5029.6  106.22
  5036.3  108.68  5043.8     108  5050.5  108.95  5064.7  109.69  5187.6  113.91
  5227.6  115.79  5249.2  116.22    5256  116.89  5270.2  117.35  5277.6  117.02
  5284.4  118.11  5291.8  117.68  5305.5  118.16  5326.9  120.14  5347.1  120.33
#Mann= 5 ,-1 , 0
    4664      .1       0  4978.3     .16       0  4991.4     .07       0
  4997.4     .16       0  5187.6      .1       0
Bank Sta=4987,5036.3
XS Rating Curve= 0 ,0
Exp/Cntr=0.3,0.1

Type RM Length L Ch R = 1 ,3256    ,467,467,467
BEGIN DESCRIPTION:
UNT025 IN NURI 7.0
END DESCRIPTION:
XS GIS Cut Line= 3
      2291137.71     13286846.83      2291037.72     13286446.85
      2290987.73     13286246.89
#Sta/Elev= 30
    4600  125.19  4700.5   120.1  4764.9  115.64  4775.2   115.5  4782.9  114.32
  4816.4  112.75  4857.7  109.34  4880.3  108.33  4888.6  108.35  4898.9  107.09
  4947.9  105.11    4953  105.52  4960.7  104.35  4981.4  102.59  4994.2  102.72
    4999  101.44  5001.7  100.94    5005  101.44  5009.7  104.44  5014.9  104.44
  5022.6  108.43  5030.3  109.35  5035.5  107.66  5039.1  109.01  5043.2  110.54
  5063.8  112.78  5076.7  113.44  5094.7  115.91    5154  120.91  5218.4  124.88
#Mann= 5 ,-1 , 0
    4600      .1       0  4880.3     .16       0    4999     .07       0
    5005     .16       0  5039.1      .1       0
Bank Sta=4960.7,5009.7
XS Rating Curve= 0 ,0
Exp/Cntr=0.3,0.1

Type RM Length L Ch R = 1 ,2789    ,412,412,412
BEGIN DESCRIPTION:
UNT025 IN NURI 6.0
END DESCRIPTION:
XS GIS Cut Line= 3
      2291637.72     13286546.86      2291487.72     13286446.85
      2291187.75     13286146.89
#Sta/Elev= 30
  4784.8  119.61  4792.3   119.5  4798.3  118.81  4849.4  116.13  4864.4   114.4
  4885.5  113.45    4893  112.46    4929  110.03  4942.5  107.75  4957.6  106.97
  4962.1  105.67  4968.6  105.67  4979.2  103.36  4984.4   101.6  4990.4   99.57
  4993.1   99.07  4996.4   99.57  5021.7   99.99  5035.8   100.7  5049.9  102.09
  5078.2  103.24  5110.8  104.28  5134.8  105.59  5148.9  107.12  5262.1  115.81
  5318.6  119.79  5346.9  122.29  5361.1  122.64  5375.2  123.71  5389.3  124.12
#Mann= 5 ,-1 , 0
  4784.8      .1       0  4984.4     .16       0  4990.4     .07       0
  4996.4     .16       0  5110.8      .1       0
Bank Sta=4979.2,5078.2
XS Rating Curve= 0 ,0
Exp/Cntr=0.3,0.1

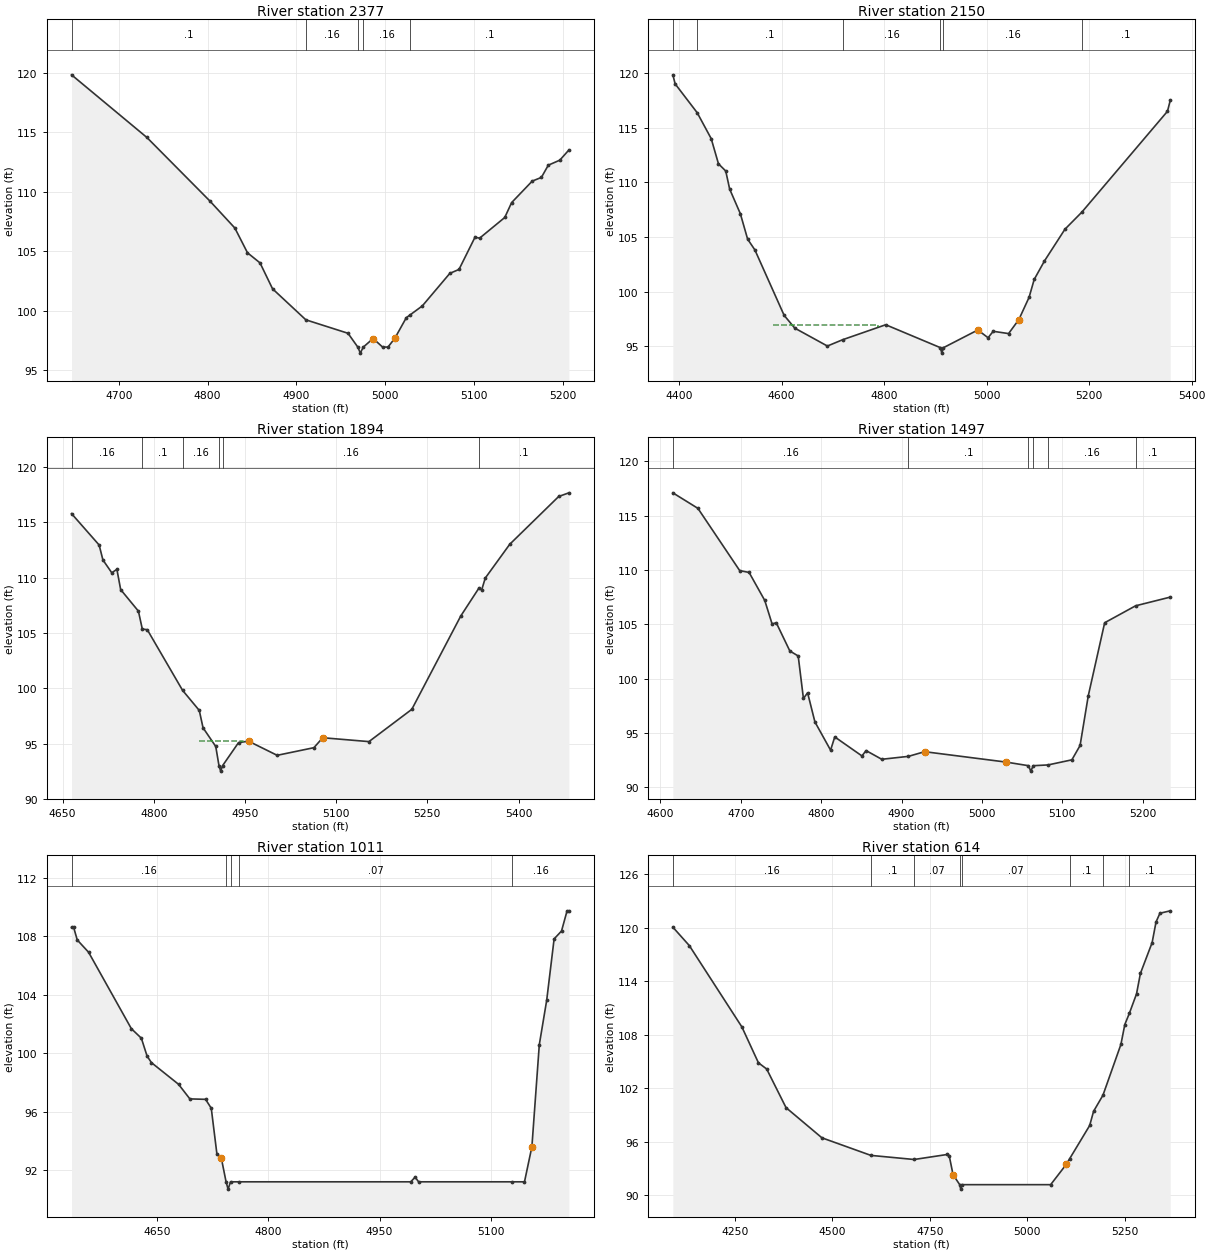
Type RM Length L Ch R = 1 ,2377    ,227,227,227
BEGIN DESCRIPTION:
UNT025 IN NURI 5.0
END DESCRIPTION:
XS GIS Cut Line= 3
       2291937.7     13286346.83      2291687.72     13286096.85
      2291487.69     13286046.85
#Sta/Elev= 30
  4646.9  119.83  4731.7  114.56  4802.4  109.23  4830.7  106.94  4844.9  104.86
    4859  104.01  4873.1  101.83  4910.6   99.22    4958   98.09  4969.1   96.92
  4971.9   96.42  4975.1   96.92  4986.3   97.65  4996.9   96.93    5003   96.93
  5010.7   97.67  5023.6    99.4  5027.6   99.62  5041.6  100.39  5072.6  103.13
  5082.9  103.46  5100.9  106.17  5106.1  106.09  5134.4  107.83  5142.1  109.08
  5165.3  110.89  5175.6   111.2  5183.4  112.23  5196.3  112.65  5206.6  113.51
#Mann= 5 ,-1 , 0
  4646.9      .1       0  4910.6     .16       0  4969.1     .07       0
  4975.1     .16       0  5027.6      .1       0
Bank Sta=4986.3,5010.7
XS Rating Curve= 0 ,0
Exp/Cntr=0.3,0.1

Type RM Length L Ch R = 1 ,2150    ,256,256,256
BEGIN DESCRIPTION:
Mapping XS 828327ee
END DESCRIPTION:
XS GIS Cut Line= 3
      2292258.31     13285621.39      2291977.07     13285940.83
      2291432.31     13285933.89
#Sta/Elev= 30
  4387.8  119.86  4392.3  119.03  4435.3  116.39  4462.6  114.02  4476.8  111.71
    4491  111.05  4498.6   109.4  4519.5  107.14  4533.7  104.81  4547.9  103.82
  4604.9   97.83  4625.7   96.66  4689.3   95.02  4719.2    95.6  4803.1   96.97
  4909.8   94.87  4912.5   94.37  4915.8   94.87  4982.8   96.49  5002.8   95.78
  5012.8   96.37  5042.8   96.16  5062.8   97.44  5082.8   99.48  5092.8  101.12
  5112.8  102.81  5152.8  105.72  5185.7  107.28  5352.8  116.52  5358.2  117.51
#Mann= 6 ,-1 , 0
  4387.8     .16       0  4435.3      .1       0  4719.2     .16       0
  4909.8     .07       0  4915.8     .16       0  5185.7      .1       0
#XS Ineff= 1 ,-1
 4583.44 4788.75   96.98
Permanent Ineff=
       F
Bank Sta=4982.8,5062.8
XS Rating Curve= 0 ,0
Exp/Cntr=0.3,0.1

Type RM Length L Ch R = 1 ,1894    ,397,397,397
BEGIN DESCRIPTION:
UNT025 IN NURI 3.1
END DESCRIPTION:
XS GIS Cut Line= 3
      2292127.82     13285573.73      2291894.53     13285747.89
      2291371.05     13285808.45
#Sta/Elev= 30
  4664.8   115.8  4710.2  112.96  4716.4  111.61    4731  110.45  4739.4  110.76
  4745.6  108.93  4774.8  106.98  4781.2  105.36  4789.4   105.3  4847.4   99.82
  4874.9      98  4881.1   96.43    4902   94.74  4907.3   93.01  4910.1   92.51
  4913.3   93.01  4939.5   95.09  4955.9   95.22    5003   93.94  5063.4   94.63
    5078   95.53    5154   95.18  5224.5    98.1    5305  106.54  5334.7  109.05
  5339.4   108.9  5345.3  109.97  5385.6  113.03  5466.1  117.35  5482.9  117.68
#Mann= 6 ,-1 , 0
  4664.8     .16       0  4781.2      .1       0  4847.4     .16       0
  4907.3     .07       0  4913.3     .16       0  5334.7      .1       0
#XS Ineff= 1 ,-1
    4875 4946.09   95.28
Permanent Ineff=
       F
Bank Sta=4955.9,5078
XS Rating Curve= 0 ,0
Exp/Cntr=0.3,0.1

Type RM Length L Ch R = 1 ,1497    ,486,486,486
BEGIN DESCRIPTION:
UNT025 IN NURI 3.0
END DESCRIPTION:
XS GIS Cut Line= 3
      2291987.73     13285396.85      2291637.72     13285496.85
      2291387.69     13285546.86
#Sta/Elev= 30
  4615.4  117.11  4646.6  115.68  4698.6  109.95  4710.3  109.78  4729.8   107.2
  4738.9  105.04  4744.1  105.15    4761  102.55  4771.4  102.09  4777.9   98.18
  4783.1    98.7  4792.2   96.02  4811.7   93.42  4816.9   94.64  4850.7   92.89
  4855.9   93.38  4875.4   92.58  4908.6   92.85  4928.7   93.28  5030.4   92.32
    5058   91.99  5060.8   91.49    5064   91.99  5082.3   92.06    5112   92.53
  5122.2   93.85  5132.4   98.43  5152.8  105.15  5191.3  106.71  5234.4  107.51
#Mann= 6 ,-1 , 0
  4615.4     .16       0  4908.6      .1       0    5058     .07       0
    5064      .1       0  5082.3     .16       0  5191.3      .1       0
Bank Sta=4928.7,5030.4
XS Rating Curve= 0 ,0
Exp/Cntr=0.3,0.1

Type RM Length L Ch R = 1 ,1011    ,397,397,397
BEGIN DESCRIPTION:
UNT025 IN NURI 2.0
END DESCRIPTION:
XS GIS Cut Line= 3
      2291937.72     13285296.85      2291537.72     13285046.85
      2291337.72     13285046.85
#Sta/Elev= 30
  4534.1   108.6    4537   108.6  4541.8  107.75  4557.1  106.91  4614.9  101.68
  4628.4  101.03  4636.1   99.81    4642   99.36  4678.6   97.88  4693.9   96.88
  4715.1   96.85  4722.8   96.24  4730.4   93.12  4736.3   92.85  4742.8   91.21
  4745.5   90.71  4748.8   91.21  4760.6   91.21  4992.2   91.21  4998.1   91.53
  5002.8   91.21    5129   91.21  5145.8   91.21  5155.8   93.61  5165.8  100.59
  5175.8  103.63  5185.8  107.82  5195.8  108.36  5203.3  109.74  5205.8  109.74
#Mann= 5 ,-1 , 0
  4534.1     .16       0  4742.8     .07       0  4748.8     .16       0
  4760.6     .07       0    5129     .16       0
Bank Sta=4736.3,5155.8
XS Rating Curve= 0 ,0
Exp/Cntr=0.3,0.1

Type RM Length L Ch R = 1 ,614     ,0,0,0
BEGIN DESCRIPTION:
UNT025 IN NURI 1.0
END DESCRIPTION:
XS GIS Cut Line= 3
      2292237.73     13285146.87      2291732.86     13284657.93
      2291161.29      13284653.6
#Sta/Elev= 30
  4091.6  120.06  4133.9  117.99  4268.5  108.88  4310.9  104.86    4332  104.17
  4381.6   99.84  4473.5   96.46    4599   94.49  4709.8   94.03  4794.4   94.59
  4799.6   94.47  4809.6   92.32  4826.6   91.21  4829.3   90.71  4832.6   91.21
  5059.6   91.21  5099.6   93.48  5108.6   94.14  5159.6   97.84  5169.6   99.43
  5193.6  101.23  5239.6  106.92  5249.6  109.15  5261.3  110.41  5279.6  112.58
  5289.6  114.88  5319.6  118.33  5329.6  120.64  5339.6  121.62    5366  121.89
#Mann= 8 ,-1 , 0
  4091.6     .16       0    4599      .1       0  4709.8     .07       0
  4826.6     .07       0  4832.6     .07       0  5108.6      .1       0
  5193.6     .16       0  5261.3      .1       0
Bank Sta=4809.6,5099.6
XS Rating Curve= 0 ,0
Exp/Cntr=0.3,0.1

Chan Stop Cuts=-1
Use User Specified Reach Order=0
Composite Channel Slope=5