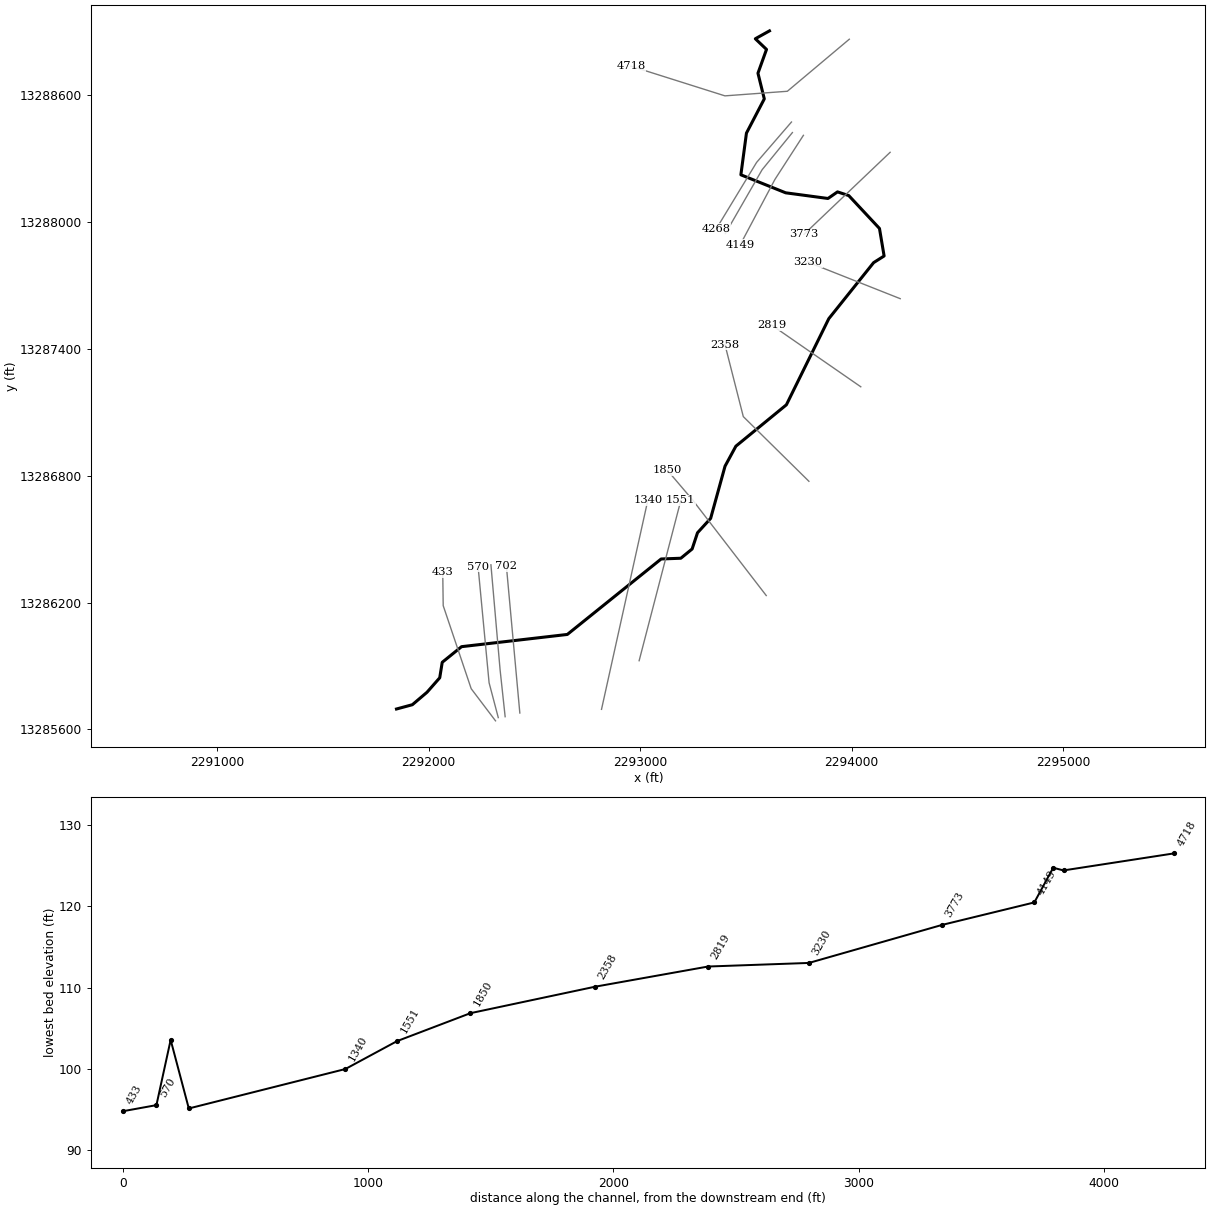
--- UNT026 IN NURI.prj (project) ---

Proj Title=UNT026 IN NURI Base Level Engineering
Current Plan=p01
Default Exp/Contr=0.3,0.1
English Units
Geom File=g01
Flow File=f01
Plan File=p01
BEGIN DESCRIPTION:
UNT026 IN NURI
END DESCRIPTION:

--- UNT026 IN NURI.p01 (plan) ---

Plan Title=Multiple Run
Short Identifier=Multiple
Geom File=g01
Flow File=f01
Subcritical Flow
K Sum by GR= 0
Std Step Tol= 0.01
Critical Tol= 0.01
Num of Std Step Trials= 20
Max Error Tol= 0.3
Flow Tol Ratio= 0.001
Split Flow NTrial= 30
Split Flow Tol= 0.02
Split Flow Ratio= 0.02
Log Output Level= 0
Friction Slope Method= 1
Unsteady Friction Slope Method= 2
Unsteady Bridges Friction Slope Method= 1
Parabolic Critical Depth
Global Vel Dist=  1 , 1 , 1
Global Log Level= 0
CheckData=True
Encroach Param= -1, 0, 0, 0
BEGIN DESCRIPTION:
Multiple Run
END DESCRIPTION:

--- UNT026 IN NURI.f01 (steady flow) ---

Flow Title=Multiple
Number of Profiles=7
Profile Names=10-year,25-year,50-year,1pct_min,100-year,1pct_plu,500-year
River Rch & RM= UNT026 IN NURI,Reach-1,4718
     807    1146    1429    1299    1756    2375    2666
Boundary for River Rch & Prof#=UNT026 IN NURI,Reach-1,1
Up Type=0
Dn Type=3
Dn Slope=0.005
Boundary for River Rch & Prof#=UNT026 IN NURI,Reach-1,2
Up Type=0
Dn Type=3
Dn Slope=0.005
Boundary for River Rch & Prof#=UNT026 IN NURI,Reach-1,3
Up Type=0
Dn Type=3
Dn Slope=0.005
Boundary for River Rch & Prof#=UNT026 IN NURI,Reach-1,4
Up Type=0
Dn Type=3
Dn Slope=0.005
Boundary for River Rch & Prof#=UNT026 IN NURI,Reach-1,5
Up Type=0
Dn Type=3
Dn Slope=0.005
Boundary for River Rch & Prof#=UNT026 IN NURI,Reach-1,6
Up Type=0
Dn Type=3
Dn Slope=0.005
Boundary for River Rch & Prof#=UNT026 IN NURI,Reach-1,7
Up Type=0
Dn Type=3
Dn Slope=0.005

--- UNT026 IN NURI.g01 (geometry) ---

Geom Title=Existing Conditions

River Reach=UNT026 IN NURI,Reach-1
Reach XY= 30
      2293611.71     13288903.95      2293544.84     13288866.71
      2293597.72     13288816.24      2293557.26     13288703.79
      2293587.24     13288582.30      2293502.82     13288420.41
      2293476.49     13288223.26      2293688.21     13288138.14
      2293888.48     13288111.29      2293933.46     13288142.48
      2293986.84     13288124.94      2294131.95     13287969.49
      2294153.89     13287839.35      2294104.30     13287807.90
      2293892.30     13287542.88      2293691.72     13287135.48
      2293452.83     13286939.81      2293401.57     13286845.26
      2293333.48     13286598.30      2293271.35     13286530.30
      2293245.94     13286453.59      2293192.47     13286409.84
      2293099.41     13286406.37      2292655.66     13286049.43
      2292155.40     13285991.62      2292064.02     13285917.67
      2292052.22     13285844.45      2291991.97     13285775.92
      2291922.77     13285717.10      2291847.72     13285696.85

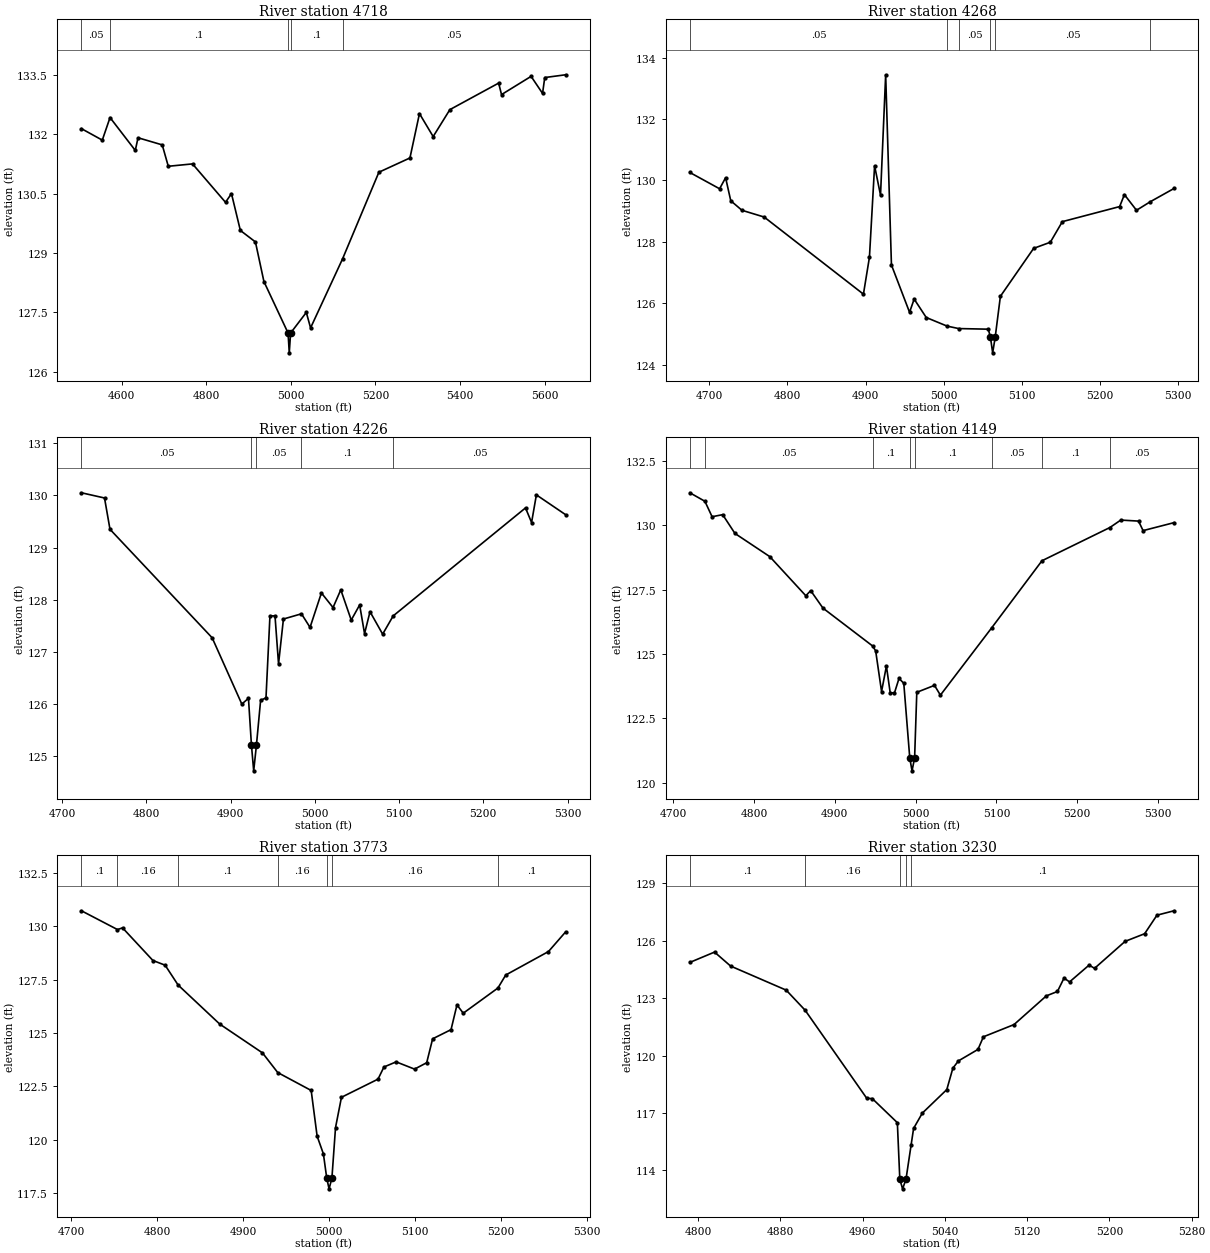
Type RM Length L Ch R = 1,4718,450,450,450
BEGIN DESCRIPTION:
UNT026 IN NURI 9.0
END DESCRIPTION:
XS GIS Cut Line= 4
      2293989.25     13288864.53      2293696.26     13288618.34
      2293401.12     13288596.64      2292956.81     13288737.06
#Sta/Elev= 30
  4505.2  132.14  4554.5  131.85  4572.8  132.42  4632.5  131.59  4639.0  131.91
  4696.2  131.73  4710.5  131.19  4767.8  131.25  4845.8  130.28  4859.9  130.50
  4880.9  129.57  4916.5  129.28  4936.6  128.28  4993.7  126.98  4996.5  126.48
  4999.7  126.98  5036.8  127.50  5046.9  127.11  5122.4  128.85  5208.4  131.04
  5281.8  131.40  5304.3  132.52  5336.7  131.94  5376.2  132.62  5491.5  133.29
  5498.3  133.00  5568.2  133.46  5595.3  133.03  5600.5  133.43  5649.8  133.50
#Mann=5,-1,0
  4505.2    0.05       0  4572.8     0.1       0  4993.7    0.07       0
  4999.7     0.1       0  5122.4    0.05       0
Bank Sta=4993.7,4999.7
Exp/Cntr=0.3,0.1

Type RM Length L Ch R = 1,4268,42,42,42
BEGIN DESCRIPTION:
Mapping XS daa7d5ac
END DESCRIPTION:
XS GIS Cut Line= 3
      2293715.76     13288472.92      2293550.86     13288281.97
      2293359.88     13287967.29
#Sta/Elev= 30
  4674.9  130.26  4713.0  129.73  4720.7  130.09  4727.3  129.34  4741.6  129.03
  4770.1  128.81  4897.3  126.30  4905.0  127.50  4911.6  130.48  4919.2  129.52
  4925.8  133.44  4933.2  127.25  4956.4  125.71  4962.3  126.14  4977.8  125.54
  5004.5  125.26  5019.4  125.18  5057.3  125.16  5060.1  124.89  5062.9  124.39
  5066.1  124.89  5072.8  126.23  5115.4  127.79  5136.8  127.99  5152.2  128.66
  5225.6  129.15  5231.7  129.54  5247.2  129.03  5265.0  129.31  5295.3  129.74
#Mann=6,-1,0
  4674.9    0.05       0  5004.5     0.1       0  5019.4    0.05       0
  5060.1   0.035       0  5066.1    0.05       0  5265.0     0.1       0
Bank Sta=5060.1,5066.1
Exp/Cntr=0.3,0.1

Type RM Length L Ch R = 1,4226,77,77,77
BEGIN DESCRIPTION:
UNT026 IN NURI 8.0
END DESCRIPTION:
XS GIS Cut Line= 3
      2293720.12     13288423.02      2293576.90     13288247.25
      2293403.27     13287945.57
#Sta/Elev= 30
  4722.9  130.05  4750.3  129.95  4756.8  129.35  4878.1  127.27  4913.3  126.00
  4921.2  126.11  4924.7  125.22  4927.4  124.72  4930.7  125.22  4935.6  126.07
  4942.0  126.12  4946.7  127.69  4952.7  127.69  4956.9  126.77  4962.7  127.63
  4984.1  127.73  4994.3  127.47  5007.8  128.13  5021.6  127.85  5030.8  128.19
  5043.2  127.61  5053.2  127.90  5059.0  127.35  5065.5  127.77  5080.5  127.34
  5093.0  127.69  5250.1  129.76  5257.3  129.48  5263.0  130.01  5297.7  129.63
#Mann=5,-1,0
  4722.9    0.05       0  4924.7    0.07       0  4930.7    0.05       0
  4984.1     0.1       0  5093.0    0.05       0
Bank Sta=4924.7,4930.7
Exp/Cntr=0.3,0.1

Type RM Length L Ch R = 1,4149,376,376,376
BEGIN DESCRIPTION:
Mapping XS 94c7c78b
END DESCRIPTION:
XS GIS Cut Line= 3
      2293772.19     13288409.97      2293637.66     13288201.68
      2293472.87     13287891.61
#Sta/Elev= 30
  4720.6  131.26  4739.2  130.93  4748.1  130.33  4761.2  130.41  4776.4  129.68
  4819.5  128.78  4864.1  127.26  4870.1  127.46  4885.3  126.78  4946.7  125.31
  4950.5  125.12  4957.8  123.54  4963.8  124.53  4968.5  123.49  4973.8  123.49
  4979.4  124.05  4985.3  123.86  4992.7  120.96  4995.5  120.46  4998.7  120.96
  5001.4  123.51  5023.3  123.78  5030.6  123.40  5094.2  126.02  5156.3  128.62
  5240.3  129.91  5253.8  130.20  5275.8  130.16  5281.4  129.79  5319.7  130.10
#Mann=8,-1,0
  4720.6     0.1       0  4739.2    0.05       0  4946.7     0.1       0
  4992.7    0.07       0  4998.7     0.1       0  5094.2    0.05       0
  5156.3     0.1       0  5240.3    0.05       0
Bank Sta=4992.7,4998.7
Exp/Cntr=0.3,0.1

Type RM Length L Ch R = 1,3773,543,543,543
BEGIN DESCRIPTION:
Mapping XS 2cb3dd0b
END DESCRIPTION:
XS GIS Cut Line= 2
      2294182.36     13288329.70      2293774.69     13287941.55
#Sta/Elev= 30
  4711.9  130.73  4753.8  129.85  4759.7  129.93  4795.0  128.40  4809.2  128.18
  4824.3  127.25  4872.7  125.42  4922.4  124.07  4940.1  123.15  4979.0  122.31
  4985.9  120.17  4993.2  119.34  4997.1  118.20  4999.8  117.70  5003.1  118.20
  5007.3  120.57  5014.2  121.99  5056.7  122.84  5063.6  123.41  5077.8  123.65
  5099.2  123.31  5113.3  123.61  5120.2  124.73  5141.6  125.16  5148.5  126.32
  5155.8  125.93  5196.1  127.11  5205.2  127.72  5254.9  128.82  5274.8  129.74
#Mann=7,-1,0
  4711.9     0.1       0  4753.8    0.16       0  4824.3     0.1       0
  4940.1    0.16       0  4997.1    0.07       0  5003.1    0.16       0
  5196.1     0.1       0
Bank Sta=4997.1,5003.1
Exp/Cntr=0.3,0.1

Type RM Length L Ch R = 1,3230,411,411,411
BEGIN DESCRIPTION:
UNT026 IN NURI 7.0
END DESCRIPTION:
XS GIS Cut Line= 2
      2294230.07     13287637.46      2293792.26     13287810.85
#Sta/Elev= 30
  4791.9  124.87  4815.9  125.41  4831.5  124.68  4885.6  123.42  4904.0  122.37
  4964.0  117.76  4969.3  117.75  4993.7  116.49  4996.1  113.53  4998.8  113.03
  5002.1  113.53  5007.1  115.33  5009.5  116.19  5018.0  116.99  5041.8  118.22
  5047.7  119.34  5053.1  119.72  5072.1  120.32  5077.4  120.98  5107.2  121.62
  5138.6  123.12  5149.4  123.35  5155.8  124.05  5161.2  123.85  5180.2  124.73
  5185.5  124.56  5215.2  125.97  5234.2  126.37  5246.2  127.34  5262.8  127.57
#Mann=5,-1,0
  4791.9     0.1       0  4904.0    0.16       0  4996.1    0.07       0
  5002.1    0.16       0  5007.1     0.1       0
Bank Sta=4996.1,5002.1
Exp/Cntr=0.3,0.1

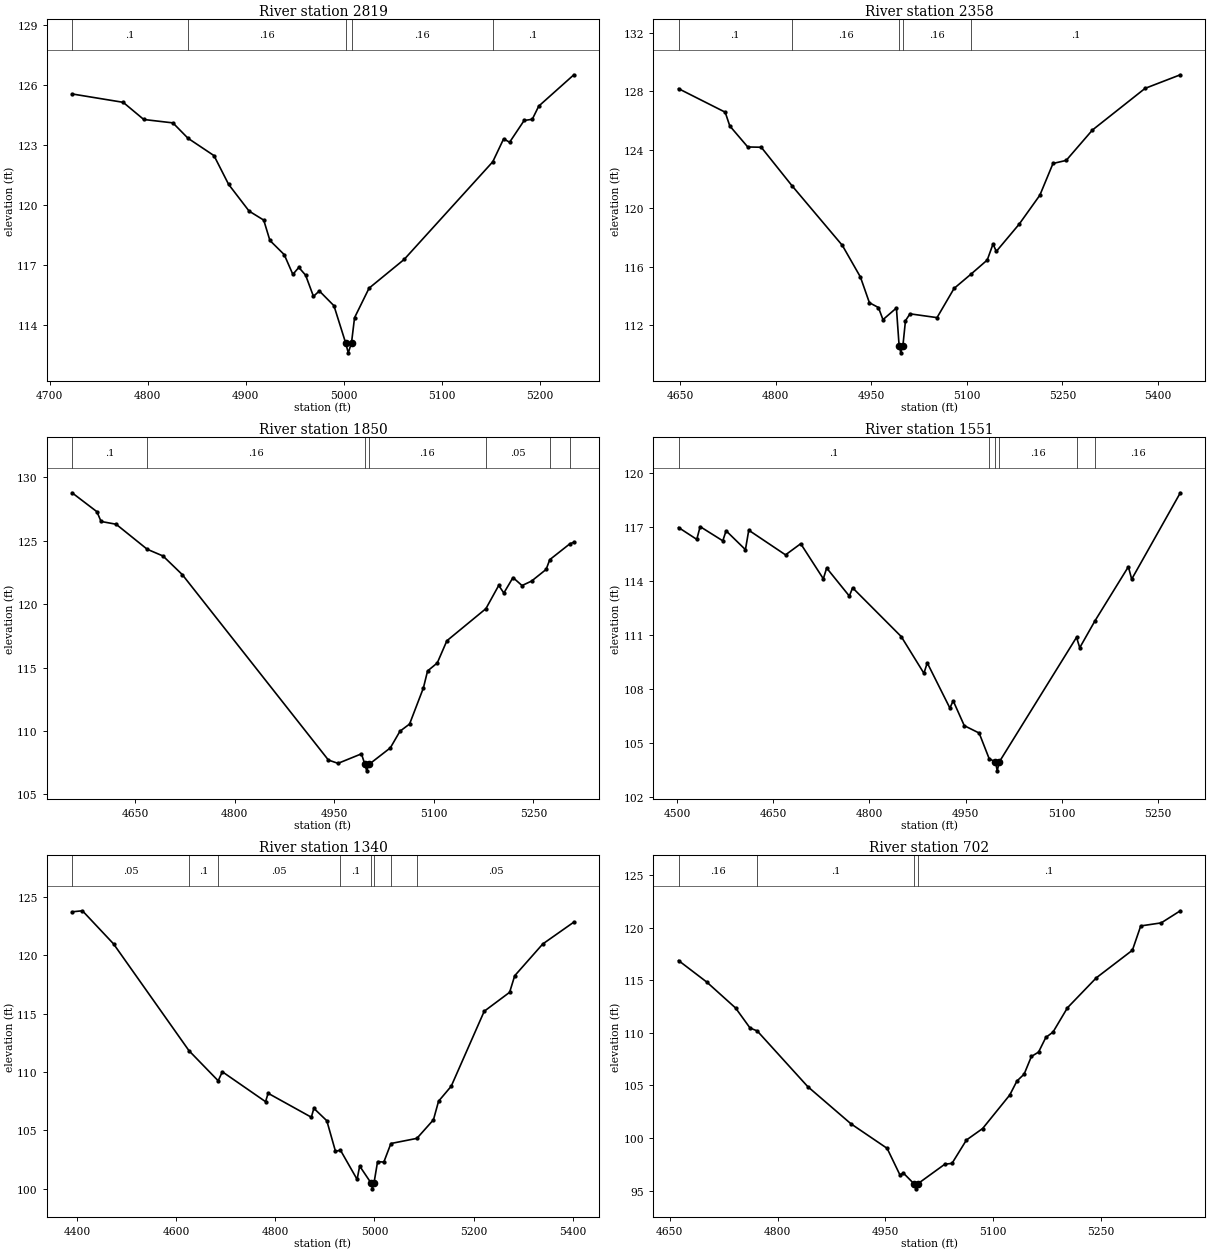
Type RM Length L Ch R = 1,2819,461,461,461
BEGIN DESCRIPTION:
UNT026 IN NURI 6.0
END DESCRIPTION:
XS GIS Cut Line= 2
      2294043.52     13287220.75      2293622.88     13287511.96
#Sta/Elev= 30
  4722.8  125.56  4774.9  125.14  4795.9  124.28  4825.6  124.11  4841.0  123.34
  4867.5  122.47  4882.4  121.03  4903.3  119.69  4918.2  119.24  4924.5  118.22
  4939.1  117.51  4947.9  116.52  4954.0  116.87  4960.9  116.48  4968.9  115.42
  4974.9  115.69  4989.8  114.95  5001.7  113.09  5004.4  112.59  5007.7  113.09
  5010.8  114.35  5025.6  115.83  5061.4  117.27  5151.7  122.16  5162.8  123.31
  5168.9  123.14  5183.7  124.23  5192.0  124.29  5198.6  124.95  5234.4  126.52
#Mann=5,-1,0
  4722.8     0.1       0  4841.0    0.16       0  5001.7    0.07       0
  5007.7    0.16       0  5151.7     0.1       0
Bank Sta=5001.7,5007.7
Exp/Cntr=0.3,0.1

Type RM Length L Ch R = 1,2358,508,508,508
BEGIN DESCRIPTION:
UNT026 IN NURI 5.0
END DESCRIPTION:
XS GIS Cut Line= 3
      2293798.22     13286773.75      2293487.92     13287079.71
      2293401.11     13287420.46
#Sta/Elev= 30
  4647.6  128.19  4720.8  126.58  4728.0  125.64  4756.2  124.20  4777.4  124.18
  4825.4  121.56  4904.7  117.46  4933.0  115.30  4947.1  113.54  4961.3  113.21
  4968.4  112.38  4989.5  113.18  4993.7  110.61  4996.4  110.11  4999.7  110.61
  5003.7  112.31  5010.8  112.78  5053.2  112.52  5080.0  114.52  5106.1  115.48
  5132.0  116.46  5141.1  117.56  5146.2  117.05  5182.0  118.91  5214.6  120.90
  5235.2  123.07  5255.9  123.28  5297.1  125.36  5379.7  128.21  5435.0  129.14
#Mann=5,-1,0
  4647.6     0.1       0  4825.4    0.16       0  4993.7    0.07       0
  4999.7    0.16       0  5106.1     0.1       0
Bank Sta=4993.7,4999.7
Exp/Cntr=0.3,0.1

Type RM Length L Ch R = 1,1850,299,299,299
BEGIN DESCRIPTION:
UNT026 IN NURI 4.0
END DESCRIPTION:
XS GIS Cut Line= 3
      2293596.42     13286233.38      2293247.04     13286686.92
      2293128.11     13286826.65
#Sta/Elev= 30
  4555.0  128.77  4592.4  127.28  4598.7  126.51  4621.4  126.29  4668.2  124.32
  4692.0  123.79  4721.1  122.32  4941.2  107.71  4955.7  107.45  4991.0  108.20
  4996.2  107.36  4998.9  106.86  5002.2  107.36  5034.5  108.67  5049.0  109.98
  5063.5  110.55  5084.3  113.39  5090.6  114.73  5105.2  115.36  5119.7  117.11
  5178.5  119.64  5197.8  121.47  5205.5  120.87  5219.3  122.09  5232.9  121.46
  5247.2  121.81  5269.2  122.73  5274.7  123.50  5305.0  124.75  5311.0  124.87
#Mann=7,-1,0
  4555.0     0.1       0  4668.2    0.16       0  4996.2    0.07       0
  5002.2    0.16       0  5178.5    0.05       0  5274.7    0.08       0
  5305.0    0.05       0
Bank Sta=4996.2,5002.2
Exp/Cntr=0.3,0.1

Type RM Length L Ch R = 1,1551,211,211,211
BEGIN DESCRIPTION:
Mapping XS 91b4fc8b
END DESCRIPTION:
XS GIS Cut Line= 2
      2292995.30     13285925.19      2293192.38     13286683.19
#Sta/Elev= 30
  4502.0  116.95  4530.5  116.29  4535.7  117.00  4571.1  116.21  4576.2  116.77
  4606.4  115.72  4611.6  116.80  4669.0  115.43  4692.7  116.05  4728.0  114.10
  4733.2  114.70  4768.6  113.14  4773.7  113.60  4849.6  110.89  4885.0  108.85
  4890.2  109.43  4925.5  106.92  4930.7  107.32  4948.0  105.94  4971.2  105.53
  4986.9  104.10  4996.7  103.93  4999.4  103.43  5002.7  103.93  5123.2  110.85
  5128.2  110.27  5151.9  111.76  5204.1  114.77  5209.3  114.08  5285.2  118.88
#Mann=6,-1,0
  4502.0     0.1       0  4986.9    0.16       0  4996.7    0.07       0
  5002.7    0.16       0  5123.2    0.05       0  5151.9    0.16       0
Bank Sta=4996.7,5002.7
Exp/Cntr=0.3,0.1

Type RM Length L Ch R = 1,1340,638,638,638
BEGIN DESCRIPTION:
UNT026 IN NURI 3.0
END DESCRIPTION:
XS GIS Cut Line= 2
      2292817.36     13285695.19      2293036.22     13286683.34
#Sta/Elev= 30
  4390.1  123.71  4411.0  123.80  4473.7  120.97  4626.0  111.82  4684.8  109.25
  4693.2  110.02  4780.4  107.46  4785.5  108.18  4872.7  106.13  4877.8  106.89
  4903.9  105.83  4921.4  103.21  4931.4  103.31  4965.0  100.81  4970.2  101.95
  4993.1  100.50  4995.9  100.00  4999.1  100.50  5006.3  102.33  5018.9  102.29
  5033.2  103.88  5085.6  104.32  5119.0  105.91  5129.3  107.50  5154.8  108.78
  5221.4  115.20  5272.6  116.82  5282.9  118.24  5339.5  120.96  5402.2  122.83
#Mann=8,-1,0
  4390.1    0.05       0  4626.0     0.1       0  4684.8    0.05       0
  4931.4     0.1       0  4993.1    0.07       0  4999.1     0.1       0
  5033.2    0.16       0  5085.6    0.05       0
Bank Sta=4993.1,4999.1
Exp/Cntr=0.3,0.1

Type RM Length L Ch R = 1,702,74,74,74
BEGIN DESCRIPTION:
UNT026 IN NURI 2.0
END DESCRIPTION:
XS GIS Cut Line= 2
      2292431.06     13285677.81      2292367.39     13286373.30
#Sta/Elev= 30
  4662.1  116.86  4701.3  114.82  4741.5  112.35  4761.6  110.45  4771.6  110.17
  4841.9  104.88  4902.1  101.34  4952.4   99.01  4970.2   96.49  4975.2   96.65
  4989.5   95.66  4992.3   95.16  4995.5   95.66  5032.7   97.50  5042.7   97.58
  5062.8   99.80  5085.3  100.89  5123.1  104.08  5133.1  105.41  5143.1  106.06
  5153.2  107.74  5163.2  108.16  5173.3  109.55  5183.3  110.06  5203.4  112.37
  5243.6  115.22  5293.8  117.84  5305.4  120.15  5333.9  120.44  5360.5  121.59
#Mann=4,-1,0
  4662.1    0.16       0  4771.6     0.1       0  4989.5    0.07       0
  4995.5     0.1       0
Bank Sta=4989.5,4995.5
Exp/Cntr=0.3,0.1

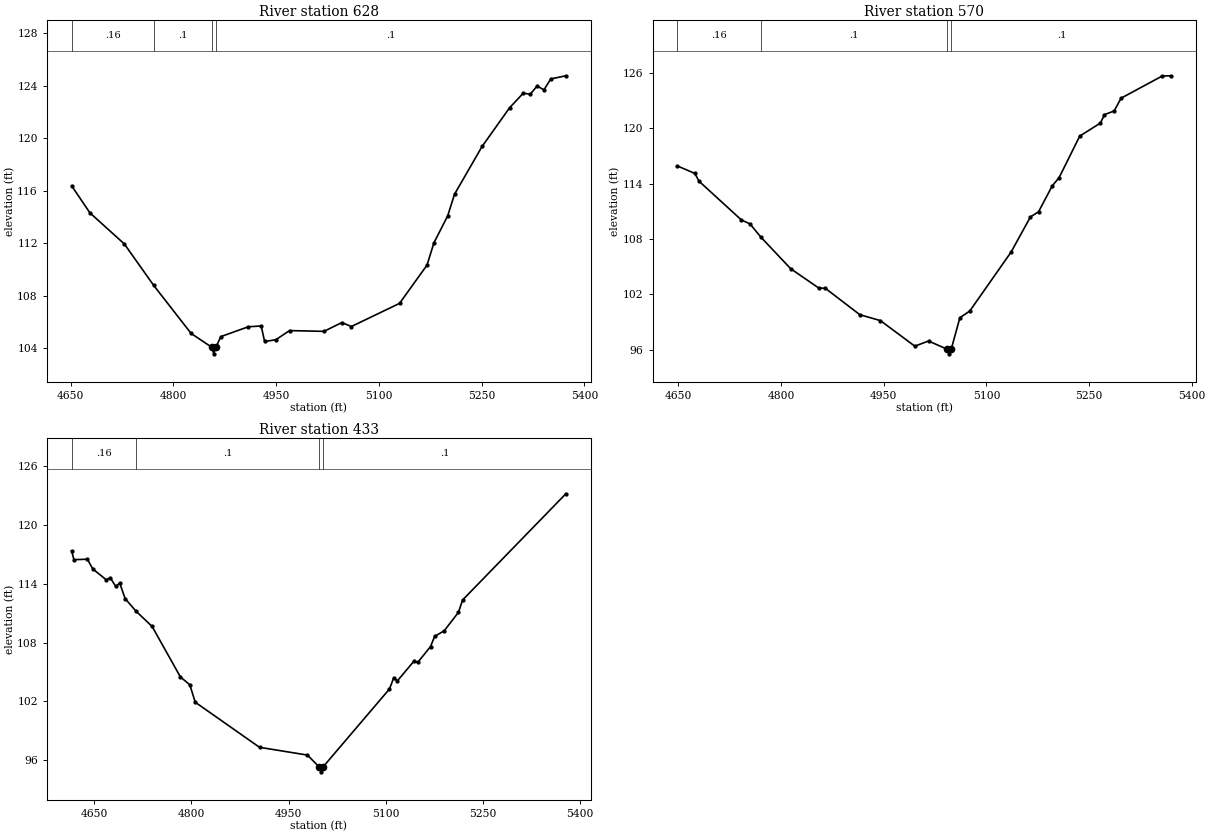
Type RM Length L Ch R = 1,628,58,58,58
BEGIN DESCRIPTION:
Mapping XS 0b9e8b23
END DESCRIPTION:
XS GIS Cut Line= 3
      2292361.62     13285660.41      2292337.75     13285881.80
      2292294.35     13286378.74
#Sta/Elev= 30
  4651.5  116.36  4678.1  114.31  4728.4  111.94  4771.2  108.79  4825.9  105.13
  4856.1  104.08  4858.9  103.58  4862.1  104.08  4869.2  104.89  4909.4  105.64
  4928.2  105.70  4933.2  104.52  4949.5  104.65  4969.6  105.35  5019.8  105.29
  5045.9  105.96  5059.9  105.66  5130.2  107.42  5170.3  110.33  5180.4  112.03
  5200.5  114.08  5210.5  115.73  5250.7  119.36  5290.8  122.30  5310.9  123.42
  5320.9  123.33  5331.0  123.96  5341.0  123.67  5351.0  124.50  5373.0  124.74
#Mann=4,-1,0
  4651.5    0.16       0  4771.2     0.1       0  4856.1    0.07       0
  4862.1     0.1       0
Bank Sta=4856.1,4862.1
Exp/Cntr=0.3,0.1

Type RM Length L Ch R = 1,570,137,137,137
BEGIN DESCRIPTION:
Mapping XS f9e957ed
END DESCRIPTION:
XS GIS Cut Line= 3
      2292329.07     13285656.11      2292285.67     13285821.03
      2292233.58     13286370.13
#Sta/Elev= 30
  4648.2  115.93  4674.0  115.11  4680.0  114.27  4742.0  110.07  4754.6  109.64
  4770.3  108.22  4814.0  104.79  4854.8  102.71  4864.8  102.66  4915.0   99.81
  4945.1   99.17  4995.4   96.40  5015.4   96.96  5042.6   96.07  5045.3   95.57
  5048.6   96.07  5061.2   99.48  5075.7  100.21  5136.0  106.59  5164.3  110.40
  5176.2  110.96  5196.2  113.77  5206.3  114.67  5236.4  119.16  5266.6  120.57
  5272.5  121.48  5286.7  121.88  5296.7  123.26  5357.0  125.67  5370.3  125.69
#Mann=4,-1,0
  4648.2    0.16       0  4770.3     0.1       0  5042.6    0.07       0
  5048.6     0.1       0
Bank Sta=5042.6,5048.6
Exp/Cntr=0.3,0.1

Type RM Length L Ch R = 1,433,0,0,0
BEGIN DESCRIPTION:
UNT026 IN NURI 1.0
END DESCRIPTION:
XS GIS Cut Line= 4
      2292316.07     13285640.88      2292201.03     13285792.82
      2292068.65     13286185.62      2292066.50     13286342.92
#Sta/Elev= 30
  4615.4  117.35  4618.8  116.45  4639.6  116.50  4647.9  115.51  4668.7  114.40
  4675.0  114.61  4683.3  113.72  4689.5  114.07  4697.8  112.49  4714.5  111.21
  4739.5  109.64  4783.1  104.50  4797.7  103.69  4806.0  101.92  4905.2   97.32
  4979.1   96.53  4997.2   95.32  4999.9   94.82  5003.2   95.32  5105.7  103.27
  5112.4  104.43  5117.7  104.08  5143.9  106.14  5149.2  105.97  5169.0  107.59
  5175.4  108.63  5190.1  109.20  5212.1  111.08  5218.5  112.34  5377.8  123.17
#Mann=4,-1,0
  4615.4    0.16       0  4714.5     0.1       0  4997.2    0.07       0
  5003.2     0.1       0
Bank Sta=4997.2,5003.2
Exp/Cntr=0.3,0.1

Chan Stop Cuts=-1