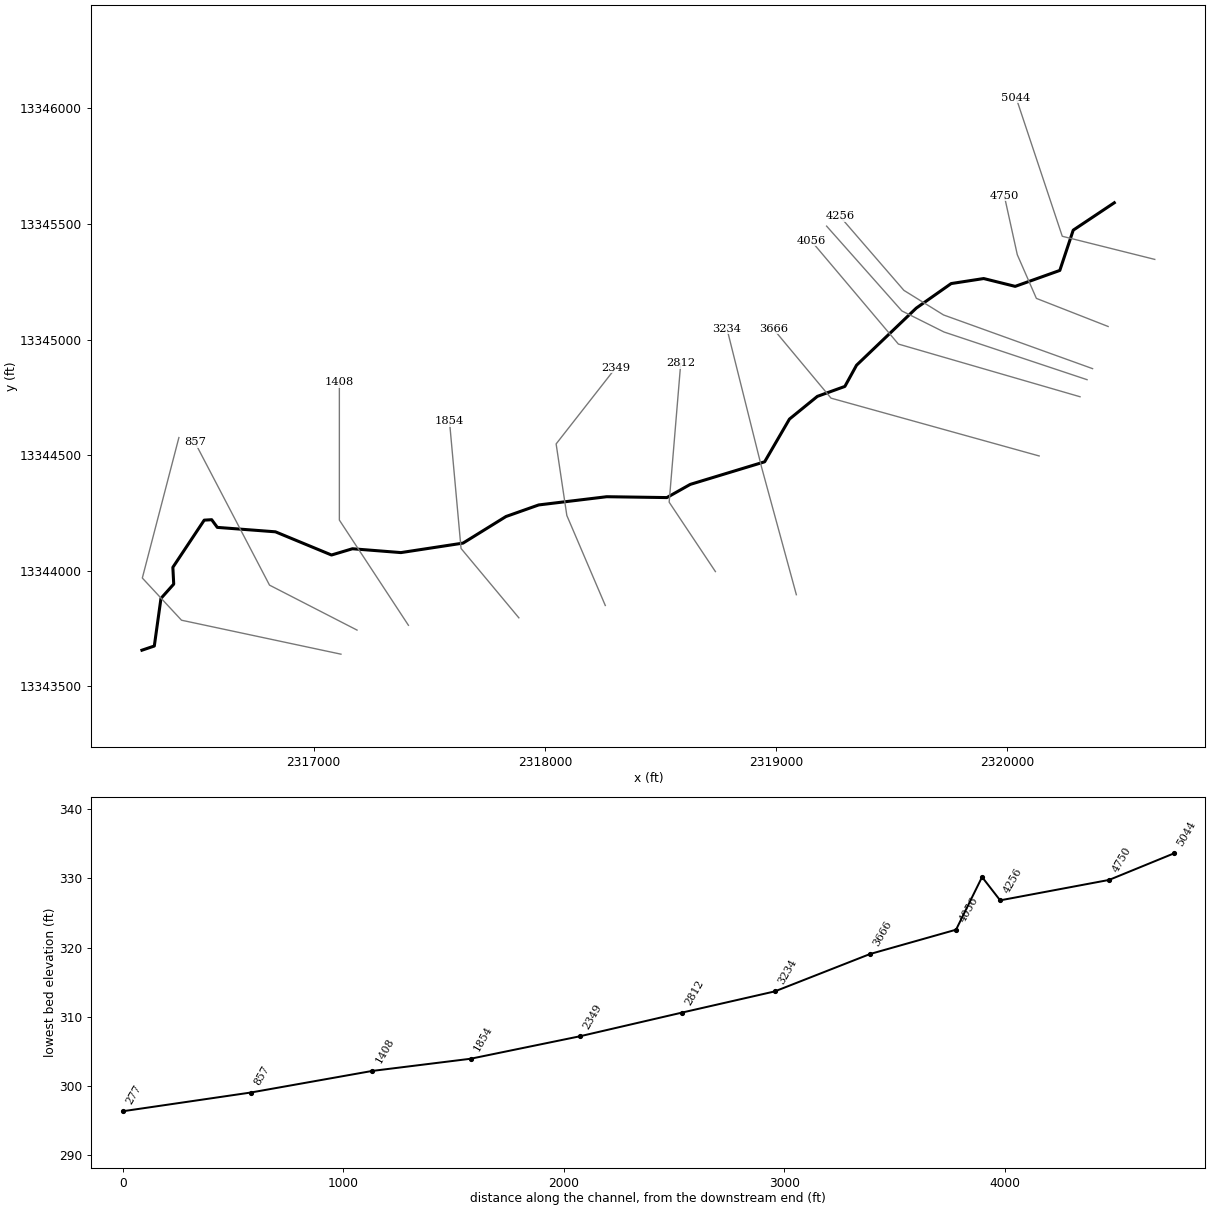
--- UNT028 IN NURI.prj (project) ---

Proj Title=UNT028 IN NURI Base Level Engineering
Current Plan=p01
Default Exp/Contr=0.3,0.1
English Units
Geom File=g01
Flow File=f01
Plan File=p01
BEGIN DESCRIPTION:
UNT028 IN NURI
END DESCRIPTION:

--- UNT028 IN NURI.p01 (plan) ---

Plan Title=Multiple Run
Short Identifier=Multiple
Geom File=g01
Flow File=f01
Subcritical Flow
K Sum by GR= 0
Std Step Tol= 0.01
Critical Tol= 0.01
Num of Std Step Trials= 20
Max Error Tol= 0.3
Flow Tol Ratio= 0.001
Split Flow NTrial= 30
Split Flow Tol= 0.02
Split Flow Ratio= 0.02
Log Output Level= 0
Friction Slope Method= 1
Unsteady Friction Slope Method= 2
Unsteady Bridges Friction Slope Method= 1
Parabolic Critical Depth
Global Vel Dist=  1 , 1 , 1
Global Log Level= 0
CheckData=True
Encroach Param= -1, 0, 0, 0
BEGIN DESCRIPTION:
Multiple Run
END DESCRIPTION:

--- UNT028 IN NURI.f01 (steady flow) ---

Flow Title=Multiple
Number of Profiles=7
Profile Names=10-year,25-year,50-year,1pct_min,100-year,1pct_plu,500-year
River Rch & RM= UNT028 IN NURI,Reach-1,5044
     559     788     981     892    1207    1632    1832
Boundary for River Rch & Prof#=UNT028 IN NURI,Reach-1,1
Up Type=0
Dn Type=3
Dn Slope=0.005
Boundary for River Rch & Prof#=UNT028 IN NURI,Reach-1,2
Up Type=0
Dn Type=3
Dn Slope=0.005
Boundary for River Rch & Prof#=UNT028 IN NURI,Reach-1,3
Up Type=0
Dn Type=3
Dn Slope=0.005
Boundary for River Rch & Prof#=UNT028 IN NURI,Reach-1,4
Up Type=0
Dn Type=3
Dn Slope=0.005
Boundary for River Rch & Prof#=UNT028 IN NURI,Reach-1,5
Up Type=0
Dn Type=3
Dn Slope=0.005
Boundary for River Rch & Prof#=UNT028 IN NURI,Reach-1,6
Up Type=0
Dn Type=3
Dn Slope=0.005
Boundary for River Rch & Prof#=UNT028 IN NURI,Reach-1,7
Up Type=0
Dn Type=3
Dn Slope=0.005

--- UNT028 IN NURI.g01 (geometry) ---

Geom Title=Existing Conditions

River Reach=UNT028 IN NURI,Reach-1
Reach XY= 30
      2320462.72     13345591.85      2320285.07     13345473.30
      2320227.09     13345299.17      2320034.08     13345230.23
      2319897.86     13345264.06      2319757.23     13345242.35
      2319606.22     13345136.13      2319348.01     13344889.21
      2319297.56     13344797.52      2319178.63     13344754.57
      2319057.85     13344656.26      2318950.64     13344471.57
      2318628.94     13344373.90      2318527.72     13344316.85
      2318267.79     13344320.60      2317973.49     13344285.01
      2317831.94     13344234.91      2317646.41     13344119.98
      2317377.82     13344078.96      2317168.06     13344095.52
      2317077.53     13344068.51      2316835.06     13344168.81
      2316583.67     13344187.97      2316559.34     13344221.19
      2316527.09     13344219.25      2316391.45     13344015.22
      2316395.17     13343942.65      2316340.00     13343880.86
      2316311.25     13343674.93      2316257.72     13343656.85

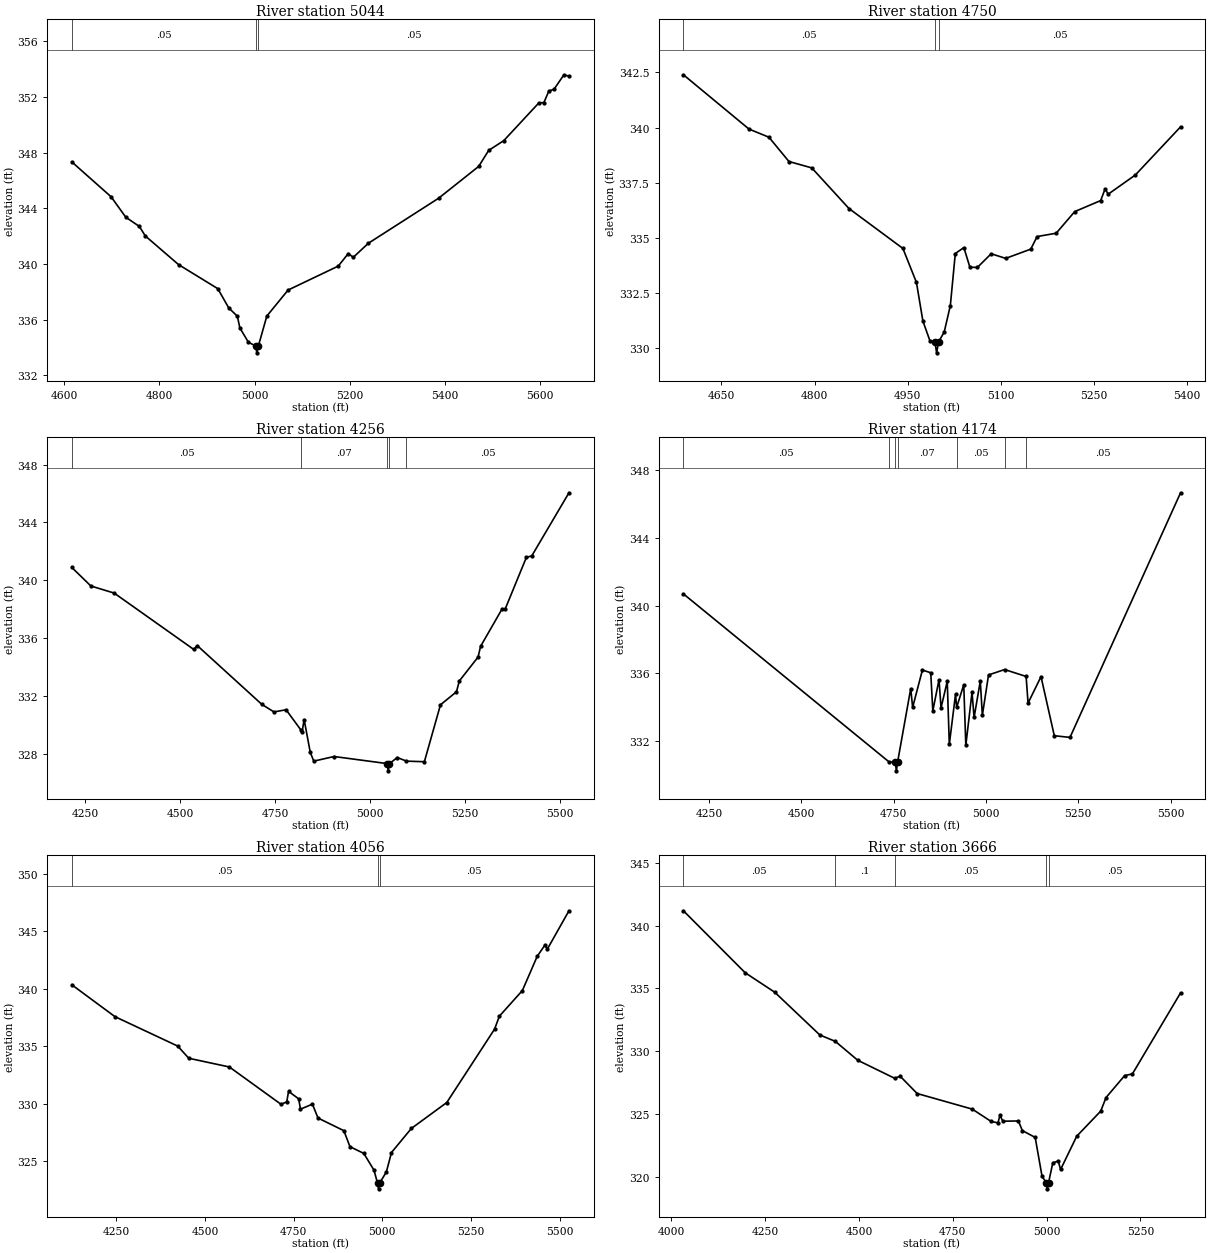
Type RM Length L Ch R = 1,5044,294,294,294
BEGIN DESCRIPTION:
UNT028 IN NURI 10.0
END DESCRIPTION:
XS GIS Cut Line= 3
      2320637.74     13345346.85      2320237.72     13345446.85
      2320037.72     13346046.87
#Sta/Elev= 30
  4616.0  347.33  4698.5  344.83  4729.4  343.36  4757.8  342.70  4770.6  342.01
  4840.2  339.96  4922.7  338.23  4945.9  336.84  4963.9  336.25  4969.1  335.41
  4987.1  334.38  5002.1  334.12  5004.9  333.62  5008.1  334.12  5025.8  336.26
  5070.5  338.13  5175.9  339.85  5197.0  340.75  5207.5  340.48  5239.2  341.49
  5386.7  344.72  5471.1  347.01  5492.1  348.16  5523.8  348.86  5597.5  351.57
  5608.1  351.59  5618.6  352.43  5629.2  352.54  5650.2  353.59  5660.8  353.49
#Mann=3,-1,0
  4616.0    0.05       0  5002.1   0.035       0  5008.1    0.05       0
Bank Sta=5002.1,5008.1
Exp/Cntr=0.3,0.1

Type RM Length L Ch R = 1,4750,494,494,494
BEGIN DESCRIPTION:
Mapping XS 61d23ad5
END DESCRIPTION:
XS GIS Cut Line= 4
      2320436.03     13345056.73      2320125.72     13345178.25
      2320043.25     13345367.05      2319986.96     13345622.54
#Sta/Elev= 30
  4588.8  342.39  4694.4  339.93  4726.6  339.56  4758.8  338.46  4795.6  338.17
  4855.5  336.33  4942.4  334.52  4964.2  332.98  4974.6  331.23  4986.0  330.33
  4993.9  330.29  4996.7  329.79  4999.9  330.29  5008.9  330.73  5018.8  331.93
  5026.8  334.29  5040.6  334.56  5050.3  333.67  5062.4  333.66  5084.6  334.28
  5108.0  334.07  5148.4  334.49  5158.6  335.06  5189.3  335.21  5219.2  336.19
  5261.0  336.69  5268.1  337.22  5273.2  336.98  5316.9  337.85  5389.7  340.03
#Mann=3,-1,0
  4588.8    0.05       0  4993.9    0.03       0  4999.9    0.05       0
Bank Sta=4993.9,4999.9
Exp/Cntr=0.3,0.1

Type RM Length L Ch R = 1,4256,82,82,82
BEGIN DESCRIPTION:
UNT028 IN NURI 9.0
END DESCRIPTION:
XS GIS Cut Line= 4
      2320368.76     13344874.43      2319724.24     13345106.63
      2319552.80     13345212.97      2319276.04     13345532.98
#Sta/Elev= 30
  4214.9  340.89  4265.1  339.61  4326.5  339.12  4536.0  335.23  4545.5  335.49
  4715.6  331.43  4747.5  330.91  4779.4  331.06  4819.1  329.64  4821.7  329.54
  4827.0  330.38  4843.1  328.12  4852.4  327.51  4905.8  327.83  5045.9  327.34
  5048.6  326.84  5051.9  327.34  5072.4  327.76  5096.7  327.51  5143.8  327.47
  5186.2  331.40  5228.3  332.30  5235.9  333.05  5285.3  334.70  5291.9  335.44
  5348.9  338.04  5356.6  338.01  5412.6  341.59  5426.8  341.69  5524.8  346.05
#Mann=5,-1,0
  4214.9    0.05       0  4819.1    0.07       0  5045.9    0.07       0
  5051.9    0.07       0  5096.7    0.05       0
Bank Sta=5045.9,5051.9
Exp/Cntr=0.3,0.1

Type RM Length L Ch R = 1,4174,118,118,118
BEGIN DESCRIPTION:
UNT028 IN NURI 8.0
END DESCRIPTION:
XS GIS Cut Line= 4
      2320344.93     13344826.68      2319726.41     13345032.85
      2319544.12     13345123.99      2319218.57     13345490.78
#Sta/Elev= 30
  4180.8  340.69  4737.0  330.75  4754.6  330.71  4757.4  330.21  4760.6  330.71
  4796.3  335.08  4801.5  333.97  4827.9  336.18  4850.5  336.02  4856.1  333.76
  4872.9  335.61  4878.4  333.94  4895.2  335.51  4900.8  331.78  4917.6  334.74
  4920.7  333.97  4939.9  335.31  4945.5  331.72  4962.3  334.86  4967.9  333.37
  4984.7  335.53  4990.3  333.50  5007.0  335.89  5050.6  336.21  5108.8  335.80
  5114.0  334.22  5149.1  335.79  5185.1  332.29  5227.6  332.19  5527.0  346.68
#Mann=7,-1,0
  4180.8    0.05       0  4737.0    0.07       0  4754.6    0.03       0
  4760.6    0.07       0  4920.7    0.05       0  5050.6    0.07       0
  5108.8    0.05       0
Bank Sta=4754.6,4760.6
Exp/Cntr=0.3,0.1

Type RM Length L Ch R = 1,4056,390,390,390
BEGIN DESCRIPTION:
Mapping XS 68eab16f
END DESCRIPTION:
XS GIS Cut Line= 3
      2320314.51     13344752.90      2319528.93     13344980.76
      2319152.00     13345427.02
#Sta/Elev= 30
  4124.2  340.35  4245.8  337.58  4422.8  335.02  4454.0  333.96  4568.6  333.20
  4714.4  329.95  4730.3  330.17  4735.5  331.08  4763.9  330.43  4769.1  329.53
  4802.7  329.97  4818.5  328.76  4891.4  327.66  4908.6  326.27  4947.7  325.68
  4976.3  324.23  4986.4  323.10  4989.2  322.60  4992.4  323.10  5011.4  324.08
  5025.7  325.76  5081.7  327.85  5181.7  330.11  5316.6  336.50  5330.0  337.62
  5394.9  339.85  5436.6  342.82  5458.6  343.81  5465.2  343.45  5526.3  346.79
#Mann=3,-1,0
  4124.2    0.05       0  4986.4    0.03       0  4992.4    0.05       0
Bank Sta=4986.4,4992.4
Exp/Cntr=0.3,0.1

Type RM Length L Ch R = 1,3666,432,432,432
BEGIN DESCRIPTION:
UNT028 IN NURI 7.0
END DESCRIPTION:
XS GIS Cut Line= 3
      2320137.73     13344496.85      2319237.72     13344746.85
      2318987.72     13345046.86
#Sta/Elev= 30
  4032.5  341.17  4197.0  336.25  4275.9  334.70  4395.8  331.31  4437.2  330.80
  4497.0  329.30  4595.2  327.87  4610.1  328.03  4655.2  326.66  4802.1  325.42
  4852.4  324.44  4870.6  324.33  4875.8  324.93  4883.6  324.46  4925.1  324.48
  4935.4  323.72  4969.8  323.17  4988.1  320.07  4999.4  319.59  5002.1  319.09
  5005.4  319.59  5016.7  321.15  5031.0  321.30  5037.5  320.63  5080.5  323.27
  5144.3  325.26  5158.6  326.34  5208.0  328.08  5228.9  328.22  5357.1  334.65
#Mann=5,-1,0
  4032.5    0.05       0  4437.2     0.1       0  4595.2    0.05       0
  4999.4    0.03       0  5005.4    0.05       0
Bank Sta=4999.4,5005.4
Exp/Cntr=0.3,0.1

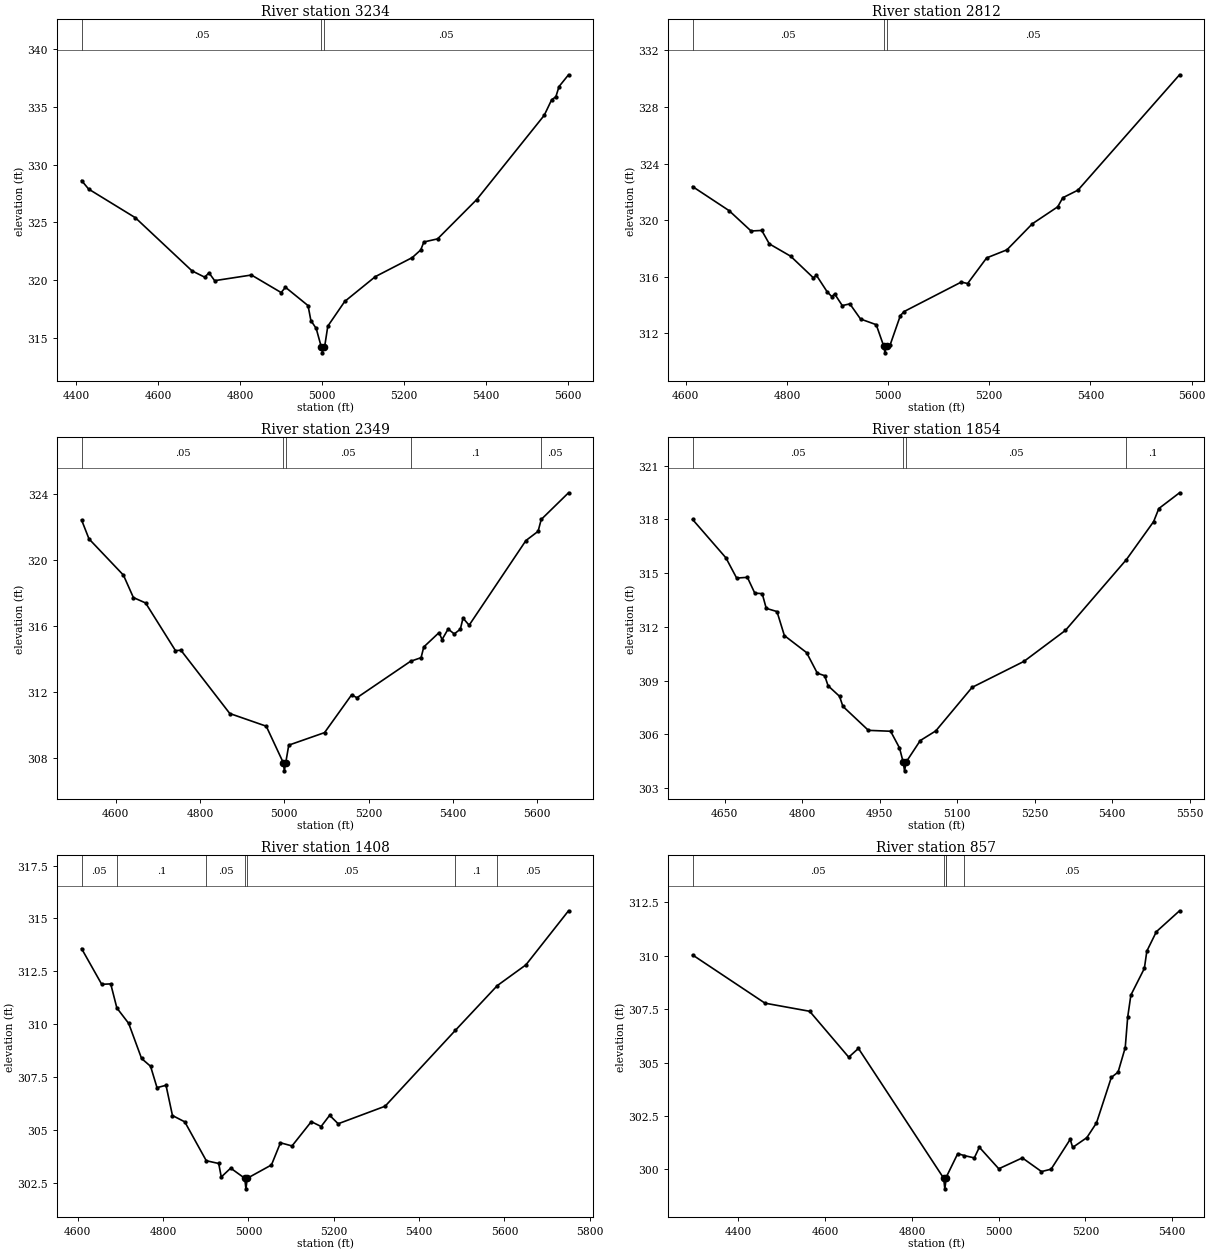
Type RM Length L Ch R = 1,3234,422,422,422
BEGIN DESCRIPTION:
UNT028 IN NURI 6.0
END DESCRIPTION:
XS GIS Cut Line= 3
      2319087.73     13343896.83      2318937.72     13344446.85
      2318787.72     13345046.87
#Sta/Elev= 30
  4412.7  328.61  4430.0  327.87  4544.0  325.39  4682.2  320.79  4713.3  320.24
  4723.7  320.62  4737.5  319.94  4827.3  320.43  4899.9  318.91  4910.3  319.37
  4965.5  317.78  4972.4  316.49  4985.4  315.80  4997.9  314.19  5000.6  313.69
  5003.9  314.19  5006.0  314.22  5013.7  316.00  5055.0  318.14  5129.7  320.29
  5219.9  321.94  5240.5  322.60  5248.2  323.29  5281.7  323.56  5377.1  326.96
  5542.0  334.26  5560.0  335.60  5570.4  335.87  5578.1  336.75  5601.3  337.77
#Mann=3,-1,0
  4412.7    0.05       0  4997.9    0.03       0  5003.9    0.05       0
Bank Sta=4997.9,5003.9
Exp/Cntr=0.3,0.1

Type RM Length L Ch R = 1,2812,463,463,463
BEGIN DESCRIPTION:
UNT028 IN NURI 5.0
END DESCRIPTION:
XS GIS Cut Line= 3
      2318737.70     13343996.89      2318537.72     13344296.85
      2318587.72     13344896.86
#Sta/Elev= 30
  4613.5  322.37  4685.6  320.67  4729.1  319.23  4750.2  319.27  4765.2  318.32
  4807.3  317.45  4852.3  315.92  4858.3  316.10  4879.4  314.94  4888.4  314.60
  4894.4  314.78  4909.4  313.96  4924.4  314.08  4945.5  313.01  4976.5  312.61
  4991.1  311.12  4993.8  310.62  4997.1  311.12  5004.1  311.19  5024.2  313.25
  5031.7  313.54  5144.6  315.62  5157.2  315.52  5194.8  317.33  5234.9  317.90
  5285.1  319.74  5335.3  320.94  5345.3  321.58  5375.4  322.12  5576.1  330.27
#Mann=3,-1,0
  4613.5    0.05       0  4991.1    0.03       0  4997.1    0.05       0
Bank Sta=4991.1,4997.1
Exp/Cntr=0.3,0.1

Type RM Length L Ch R = 1,2349,495,495,495
BEGIN DESCRIPTION:
UNT028 IN NURI 4.0
END DESCRIPTION:
XS GIS Cut Line= 4
      2318261.56     13343850.15      2318095.23     13344239.34
      2318048.90     13344548.91      2318307.15     13344878.78
#Sta/Elev= 30
  4519.3  322.43  4536.9  321.28  4618.6  319.08  4642.2  317.72  4671.2  317.39
  4742.0  314.50  4755.0  314.52  4870.9  310.68  4957.4  309.91  4997.7  307.70
  5000.4  307.20  5003.7  307.70  5010.8  308.76  5095.7  309.52  5159.8  311.81
  5172.6  311.64  5299.7  313.85  5324.7  314.07  5331.1  314.72  5367.3  315.59
  5374.5  315.17  5388.9  315.81  5403.4  315.51  5417.8  315.80  5424.2  316.47
  5438.7  316.04  5573.4  321.18  5602.3  321.74  5609.7  322.46  5674.5  324.08
#Mann=5,-1,0
  4519.3    0.05       0  4997.7    0.03       0  5003.7    0.05       0
  5299.7     0.1       0  5609.7    0.05       0
Bank Sta=4997.7,5003.7
Exp/Cntr=0.3,0.1

Type RM Length L Ch R = 1,1854,446,446,446
BEGIN DESCRIPTION:
UNT028 IN NURI 3.0
END DESCRIPTION:
XS GIS Cut Line= 3
      2317887.75     13343796.82      2317637.72     13344096.85
      2317587.72     13344646.84
#Sta/Elev= 30
  4587.5  317.99  4652.0  315.85  4672.8  314.72  4693.6  314.76  4707.9  313.88
  4722.3  313.85  4730.1  313.03  4750.9  312.85  4765.2  311.51  4808.2  310.56
  4829.0  309.41  4843.3  309.27  4849.8  308.71  4872.0  308.12  4878.5  307.56
  4927.9  306.22  4970.9  306.17  4988.1  305.24  4995.1  304.46  4997.9  303.96
  5001.1  304.46  5028.3  305.65  5058.4  306.19  5128.7  308.62  5229.1  310.07
  5309.4  311.80  5427.4  315.75  5480.1  317.87  5490.2  318.60  5530.3  319.48
#Mann=4,-1,0
  4587.5    0.05       0  4995.1    0.03       0  5001.1    0.05       0
  5427.4     0.1       0
Bank Sta=4995.1,5001.1
Exp/Cntr=0.3,0.1

Type RM Length L Ch R = 1,1408,551,551,551
BEGIN DESCRIPTION:
UNT028 IN NURI 2.0
END DESCRIPTION:
XS GIS Cut Line= 3
      2317410.13     13343764.66      2317111.54     13344219.48
      2317111.54     13344816.71
#Sta/Elev= 30
  4609.0  313.57  4656.2  311.88  4677.3  311.90  4691.7  310.76  4719.4  310.03
  4749.6  308.37  4770.7  308.00  4785.8  306.99  4806.9  307.10  4822.0  305.67
  4850.9  305.37  4901.3  303.53  4930.4  303.40  4936.4  302.76  4958.5  303.18
  4991.4  302.70  4994.2  302.20  4997.4  302.70  5054.0  303.33  5075.1  304.38
  5102.2  304.23  5147.4  305.38  5170.4  305.15  5190.4  305.68  5210.4  305.28
  5320.4  306.11  5485.0  309.70  5583.4  311.82  5650.4  312.80  5750.3  315.36
#Mann=7,-1,0
  4609.0    0.05       0  4691.7     0.1       0  4901.3    0.05       0
  4991.4    0.03       0  4997.4    0.05       0  5485.0     0.1       0
  5583.4    0.05       0
Bank Sta=4991.4,4997.4
Exp/Cntr=0.3,0.1

Type RM Length L Ch R = 1,857,580,580,580
BEGIN DESCRIPTION:
Mapping XS 8072ace9
END DESCRIPTION:
XS GIS Cut Line= 3
      2317187.89     13343743.81      2316809.46     13343938.23
      2316486.53     13344556.30
#Sta/Elev= 30
  4294.2  310.04  4461.2  307.78  4564.2  307.40  4654.2  305.25  4676.6  305.66
  4873.1  299.58  4875.8  299.08  4879.1  299.58  4879.6  299.65  4905.6  300.73
  4920.4  300.64  4943.8  300.53  4955.4  301.03  5000.2  300.02  5054.5  300.53
  5098.7  299.89  5120.8  300.00  5164.9  301.40  5170.6  301.02  5203.3  301.48
  5225.5  302.17  5259.7  304.30  5275.3  304.55  5291.8  305.70  5297.4  307.12
  5304.8  308.16  5335.9  309.41  5341.6  310.22  5363.6  311.13  5417.0  312.11
#Mann=5,-1,0
  4294.2    0.05       0  4873.1    0.03       0  4879.1    0.05       0
  4879.6    0.12       0  4920.4    0.05       0
Bank Sta=4873.1,4879.1
Exp/Cntr=0.3,0.1

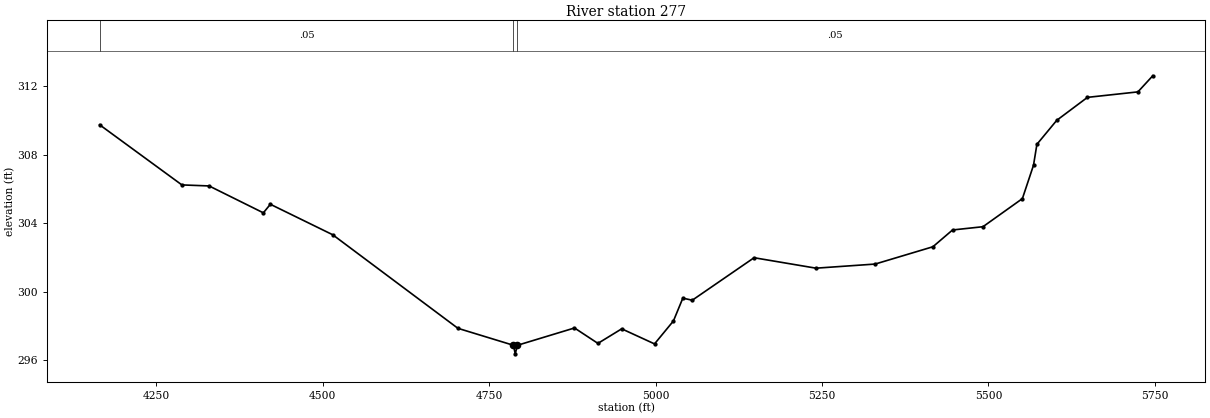
Type RM Length L Ch R = 1,277,0,0,0
BEGIN DESCRIPTION:
UNT028 IN NURI 1.0
END DESCRIPTION:
XS GIS Cut Line= 4
      2317118.47     13343639.62      2316428.86     13343786.54
      2316259.42     13343969.01      2316417.55     13344576.36
#Sta/Elev= 30
  4165.1  309.75  4288.6  306.24  4329.5  306.18  4411.0  304.61  4421.5  305.11
  4515.2  303.33  4703.2  297.87  4786.6  296.88  4789.3  296.38  4792.6  296.88
  4878.3  297.89  4913.5  296.99  4949.2  297.84  4998.5  296.96  5026.9  298.30
  5041.0  299.63  5055.2  299.51  5148.0  301.99  5241.0  301.38  5329.8  301.62
  5416.6  302.63  5446.1  303.61  5491.8  303.80  5551.0  305.44  5567.7  307.39
  5572.8  308.61  5602.6  310.01  5648.7  311.35  5724.5  311.67  5746.8  312.61
#Mann=3,-1,0
  4165.1    0.05       0  4786.6    0.03       0  4792.6    0.05       0
Bank Sta=4786.6,4792.6
Exp/Cntr=0.3,0.1

Chan Stop Cuts=-1