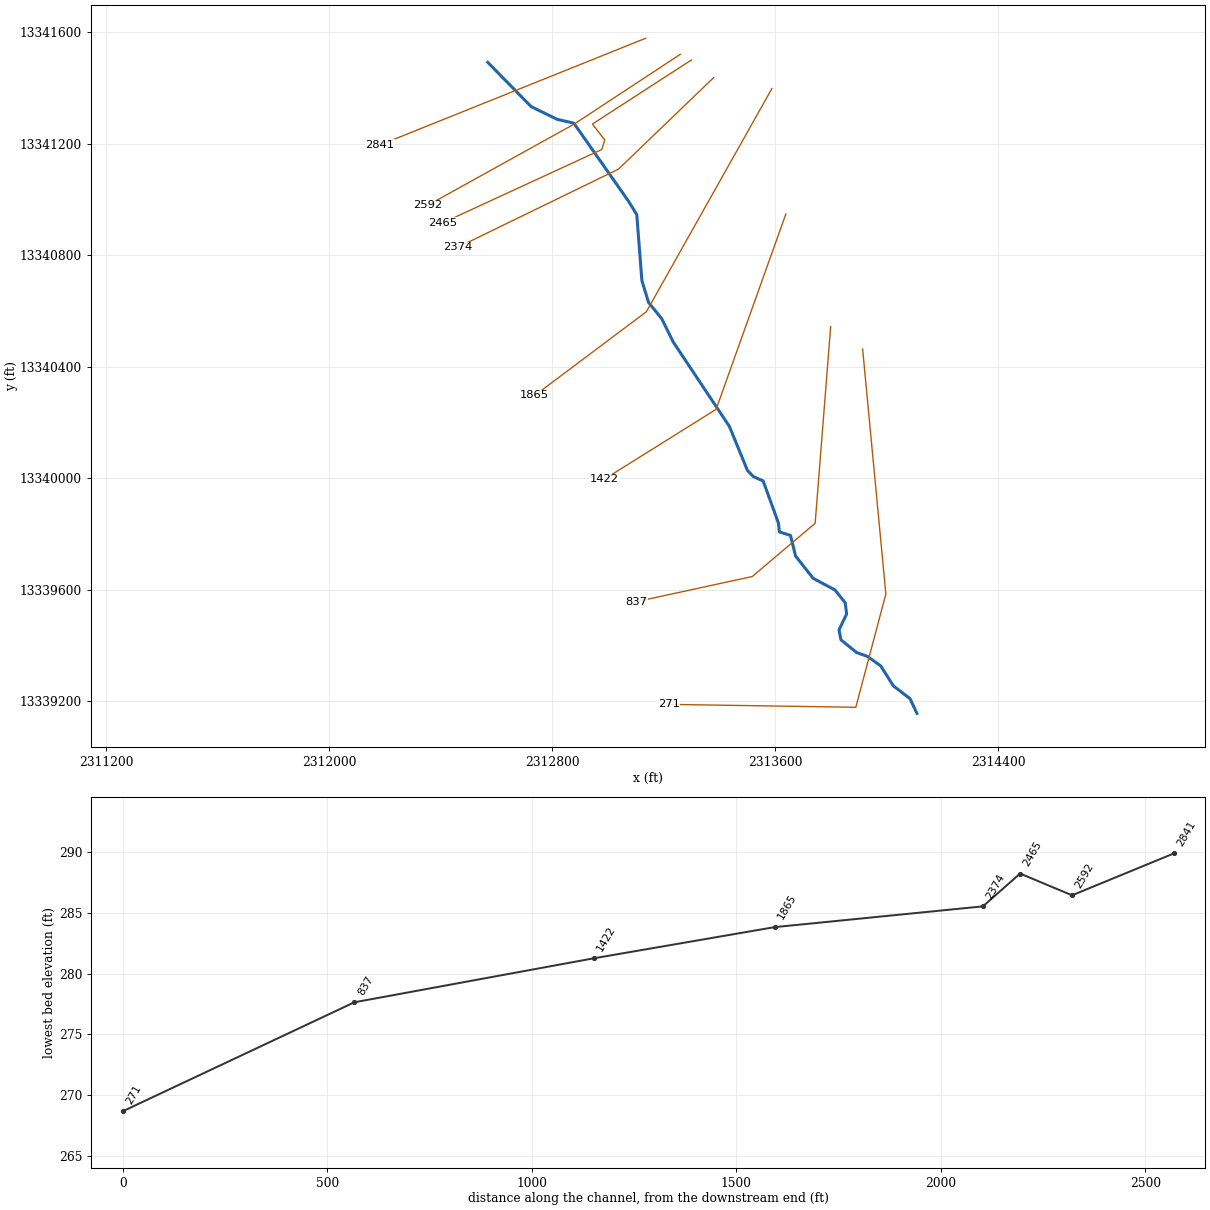
--- UNT029 IN NURI.prj (project) ---

Proj Title=UNT029 IN NURI Base Level Engineering
Current Plan=p01
Default Exp/Contr=0.3,0.1
English Units
Geom File=g01
Flow File=f01
Plan File=p01
BEGIN DESCRIPTION:
UNT029 IN NURI
END DESCRIPTION:

--- UNT029 IN NURI.p01 (plan) ---

Plan Title=Multiple Run
Short Identifier=Multiple
Geom File=g01
Flow File=f01
Subcritical Flow
K Sum by GR= 0
Std Step Tol= 0.01
Critical Tol= 0.01
Num of Std Step Trials= 20
Max Error Tol= 0.3
Flow Tol Ratio= 0.001
Split Flow NTrial= 30
Split Flow Tol= 0.02
Split Flow Ratio= 0.02
Log Output Level= 0
Friction Slope Method= 1
Unsteady Friction Slope Method= 2
Unsteady Bridges Friction Slope Method= 1
Parabolic Critical Depth
Global Vel Dist=  1 , 1 , 1
Global Log Level= 0
CheckData=True
Encroach Param= -1, 0, 0, 0
BEGIN DESCRIPTION:
Multiple Run
END DESCRIPTION:

--- UNT029 IN NURI.f01 (steady flow) ---

Flow Title=Multiple
Number of Profiles=7
Profile Names=10-year,25-year,50-year,1pct_min,100-year,1pct_plu,500-year
River Rch & RM= UNT029 IN NURI,Reach-1,2841
     664     946    1185    1084    1465    1982    2251
Boundary for River Rch & Prof#=UNT029 IN NURI,Reach-1,1
Up Type=0
Dn Type=3
Dn Slope=0.005
Boundary for River Rch & Prof#=UNT029 IN NURI,Reach-1,2
Up Type=0
Dn Type=3
Dn Slope=0.005
Boundary for River Rch & Prof#=UNT029 IN NURI,Reach-1,3
Up Type=0
Dn Type=3
Dn Slope=0.005
Boundary for River Rch & Prof#=UNT029 IN NURI,Reach-1,4
Up Type=0
Dn Type=3
Dn Slope=0.005
Boundary for River Rch & Prof#=UNT029 IN NURI,Reach-1,5
Up Type=0
Dn Type=3
Dn Slope=0.005
Boundary for River Rch & Prof#=UNT029 IN NURI,Reach-1,6
Up Type=0
Dn Type=3
Dn Slope=0.005
Boundary for River Rch & Prof#=UNT029 IN NURI,Reach-1,7
Up Type=0
Dn Type=3
Dn Slope=0.005

--- UNT029 IN NURI.g01 (geometry) ---

Geom Title=Existing Conditions

River Reach=UNT029 IN NURI,Reach-1
Reach XY= 30
      2312569.21     13341490.83      2312724.75     13341332.26
      2312818.64     13341286.38      2312877.63     13341273.04
      2313074.68     13340991.79      2313103.33     13340944.92
      2313121.68     13340708.60      2313145.41     13340630.34
      2313192.95     13340571.63      2313233.53     13340489.19
      2313435.34     13340185.89      2313500.27     13340027.57
      2313521.64     13340005.65      2313556.47     13339990.23
      2313611.27     13339839.06      2313614.60     13339807.40
      2313654.59     13339794.87      2313672.68     13339720.96
      2313735.64     13339641.12      2313814.22     13339599.28
      2313850.71     13339553.22      2313855.63     13339513.00
      2313828.46     13339456.14      2313835.22     13339420.69
      2313891.54     13339375.02      2313930.12     13339361.22
      2313977.98     13339327.01      2314023.32     13339255.41
      2314082.91     13339209.78      2314107.72     13339156.85

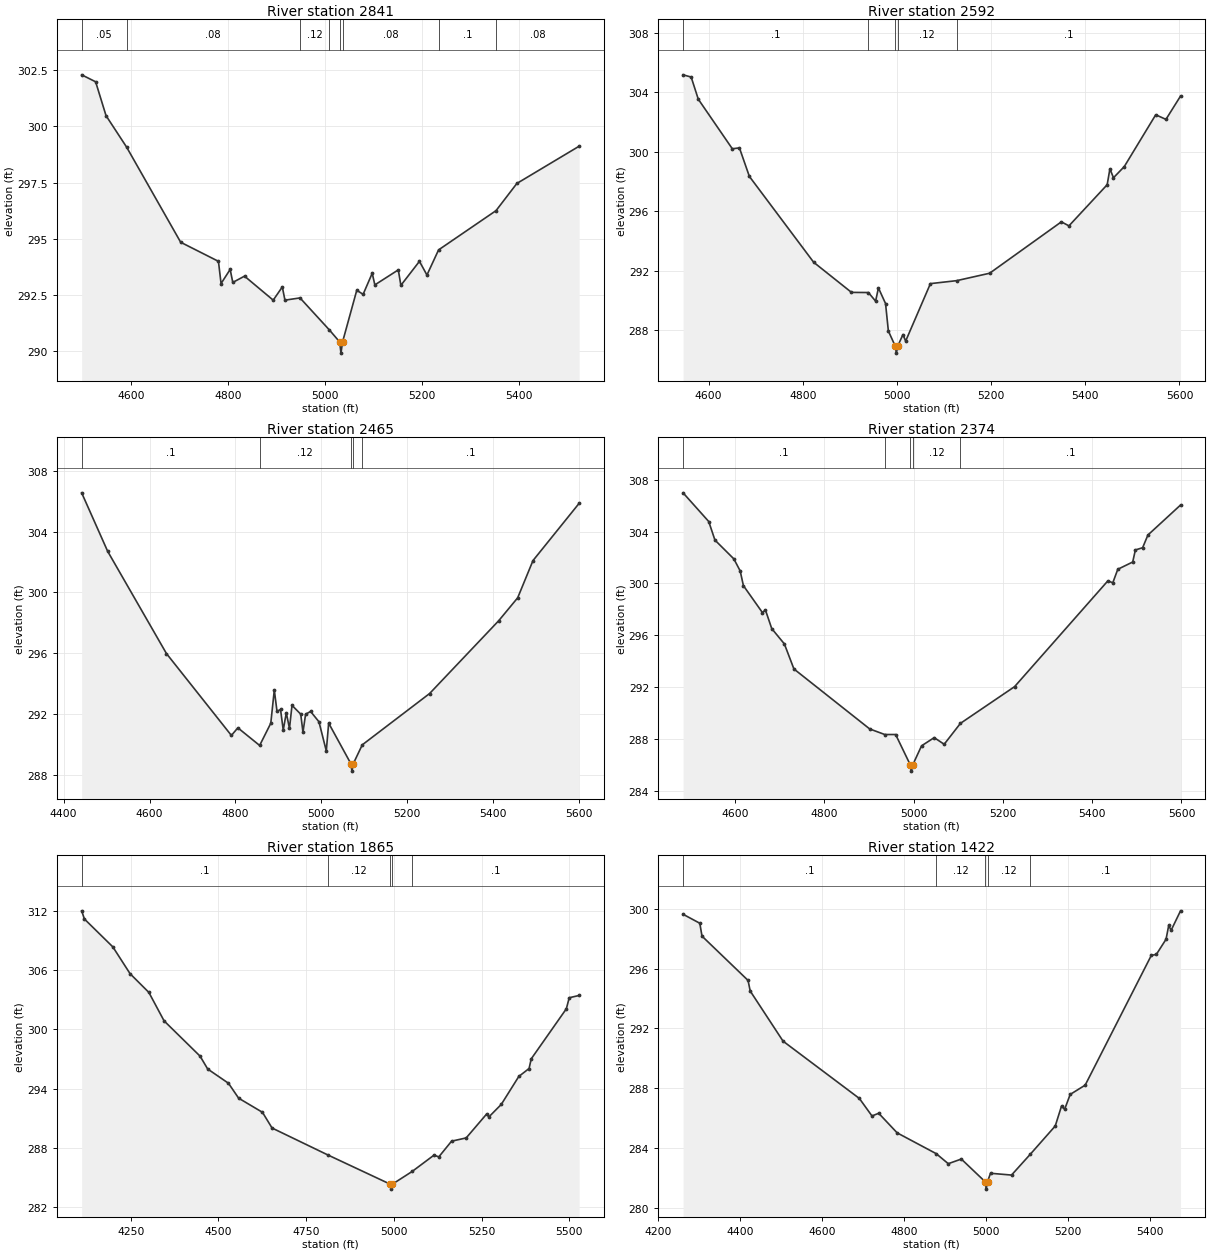
Type RM Length L Ch R = 1,2841,249,249,249
BEGIN DESCRIPTION:
UNT029 IN NURI 5.0
END DESCRIPTION:
XS GIS Cut Line= 2
      2313134.42     13341577.13      2312181.98     13341194.59
#Sta/Elev= 30
  4498.6  302.30  4527.4  301.99  4548.9  300.48  4591.3  299.08  4702.9  294.84
  4780.8  293.99  4786.2  293.00  4805.0  293.63  4810.4  293.05  4834.6  293.33
  4893.8  292.26  4912.6  292.85  4918.0  292.26  4949.1  292.36  5009.8  290.93
  5030.9  290.40  5033.6  289.90  5036.9  290.40  5066.2  292.70  5079.3  292.52
  5098.1  293.46  5103.5  292.94  5151.9  293.61  5157.2  292.92  5195.5  293.99
  5211.0  293.38  5235.0  294.50  5353.6  296.25  5396.5  297.46  5525.0  299.12
#Mann=8,-1,0
  4498.6    0.05       0  4591.3    0.08       0  4949.1    0.12       0
  5009.8    0.08       0  5030.9    0.07       0  5036.9    0.08       0
  5235.0     0.1       0  5353.6    0.08       0
Bank Sta=5030.9,5036.9
Exp/Cntr=0.3,0.1

Type RM Length L Ch R = 1,2592,127,127,127
BEGIN DESCRIPTION:
Mapping XS 11bb4ae7
END DESCRIPTION:
XS GIS Cut Line= 3
      2313259.40     13341519.83      2312879.19     13341269.83
      2312353.17     13340978.17
#Sta/Elev= 30
  4545.8  305.19  4563.0  305.04  4578.1  303.55  4650.4  300.21  4665.5  300.27
  4686.6  298.35  4823.1  292.57  4903.5  290.54  4939.4  290.53  4954.7  289.95
  4960.7  290.84  4975.8  289.79  4981.8  287.94  4996.0  286.95  4998.7  286.45
  5002.0  286.95  5012.8  287.70  5018.5  287.26  5071.1  291.13  5126.8  291.33
  5196.9  291.83  5349.2  295.29  5365.3  295.02  5446.5  297.79  5452.3  298.86
  5459.9  298.26  5482.8  299.01  5549.6  302.50  5571.3  302.19  5602.3  303.76
#Mann=5,-1,0
  4545.8     0.1       0  4939.4    0.12       0  4996.0    0.07       0
  5002.0    0.12       0  5126.8     0.1       0
Bank Sta=4996,5002
Exp/Cntr=0.3,0.1

Type RM Length L Ch R = 1,2465,91,91,91
BEGIN DESCRIPTION:
Mapping XS 8625f61f
END DESCRIPTION:
XS GIS Cut Line= 5
      2313298.48     13341499.01      2312944.30     13341269.83
      2312988.57     13341212.53      2312978.15     13341178.68
      2312407.87     13340915.67
#Sta/Elev= 30
  4442.1  306.56  4502.6  302.71  4639.4  295.98  4790.5  290.59  4805.6  291.09
  4856.3  289.93  4882.2  291.39  4890.4  293.58  4896.7  292.17  4904.9  292.30
  4911.2  290.94  4918.3  292.08  4925.7  291.05  4931.6  292.57  4951.9  291.99
  4957.1  290.80  4963.2  291.98  4974.8  292.17  4994.3  291.49  5011.4  289.57
  5016.9  291.40  5068.4  288.74  5071.1  288.24  5074.4  288.74  5095.1  289.97
  5251.9  293.35  5412.6  298.14  5456.8  299.65  5492.4  302.10  5599.8  305.87
#Mann=5,-1,0
  4442.1     0.1       0  4856.3    0.12       0  5068.4    0.07       0
  5074.4    0.12       0  5095.1     0.1       0
Bank Sta=5068.4,5074.4
Exp/Cntr=0.3,0.1

Type RM Length L Ch R = 1,2374,509,509,509
BEGIN DESCRIPTION:
UNT029 IN NURI 4.0
END DESCRIPTION:
XS GIS Cut Line= 3
      2313379.20     13341436.51      2313038.05     13341108.37
      2312461.32     13340827.80
#Sta/Elev= 30
  4483.2  306.98  4540.7  304.77  4554.6  303.34  4597.0  301.89  4611.2  300.96
  4618.4  299.83  4660.9  297.76  4667.8  297.95  4681.9  296.52  4710.2  295.34
  4731.6  293.41  4901.4  288.79  4935.2  288.36  4959.5  288.36  4992.1  286.04
  4994.8  285.54  4998.1  286.04  5017.6  287.49  5045.9  288.12  5068.3  287.61
  5104.7  289.22  5226.1  292.05  5435.1  300.20  5446.1  300.05  5457.3  301.09
  5490.7  301.65  5496.7  302.58  5512.9  302.75  5524.8  303.73  5597.9  306.04
#Mann=5,-1,0
  4483.2     0.1       0  4935.2    0.12       0  4992.1    0.07       0
  4998.1    0.12       0  5104.7     0.1       0
Bank Sta=4992.1,4998.1
Exp/Cntr=0.3,0.1

Type RM Length L Ch R = 1,1865,443,443,443
BEGIN DESCRIPTION:
UNT029 IN NURI 3.0
END DESCRIPTION:
XS GIS Cut Line= 3
      2313587.71     13341396.84      2313137.72     13340596.85
      2312737.69     13340296.83
#Sta/Elev= 30
  4110.2  311.98  4118.1  311.15  4199.1  308.33  4248.2  305.62  4301.7  303.73
  4345.1  300.85  4447.7  297.28  4469.4  295.98  4528.6  294.54  4557.6  293.03
  4625.5  291.60  4652.9  290.01  4811.7  287.29  4989.7  284.33  4992.4  283.83
  4995.7  284.33  5052.3  285.62  5114.5  287.27  5128.1  287.09  5164.5  288.68
  5206.2  289.01  5264.5  291.43  5270.8  291.13  5306.2  292.40  5356.2  295.23
  5385.4  296.03  5391.6  297.01  5491.6  302.07  5499.9  303.19  5528.1  303.42
#Mann=5,-1,0
  4110.2     0.1       0  4811.7    0.12       0  4989.7    0.07       0
  4995.7    0.12       0  5052.3     0.1       0
Bank Sta=4989.7,4995.7
Exp/Cntr=0.3,0.1

Type RM Length L Ch R = 1,1422,585,585,585
BEGIN DESCRIPTION:
UNT029 IN NURI 2.0
END DESCRIPTION:
XS GIS Cut Line= 3
      2313637.71     13340946.83      2313387.72     13340246.85
      2312987.70     13339996.84
#Sta/Elev= 30
  4260.1  299.63  4301.0  299.03  4306.3  298.17  4418.8  295.21  4424.1  294.50
  4504.3  291.15  4690.7  287.32  4721.5  286.15  4737.9  286.33  4783.0  285.02
  4878.4  283.63  4907.8  282.96  4939.7  283.27  4997.7  281.76  5000.5  281.26
  5003.7  281.76  5011.0  282.32  5062.3  282.20  5107.8  283.58  5169.1  285.48
  5184.4  286.81  5192.1  286.60  5205.6  287.59  5242.2  288.21  5403.7  296.88
  5416.1  296.95  5439.7  297.96  5446.2  298.88  5452.1  298.56  5475.1  299.86
#Mann=5,-1,0
  4260.1     0.1       0  4878.4    0.12       0  4997.7    0.07       0
  5003.7    0.12       0  5107.8     0.1       0
Bank Sta=4997.7,5003.7
Exp/Cntr=0.3,0.1

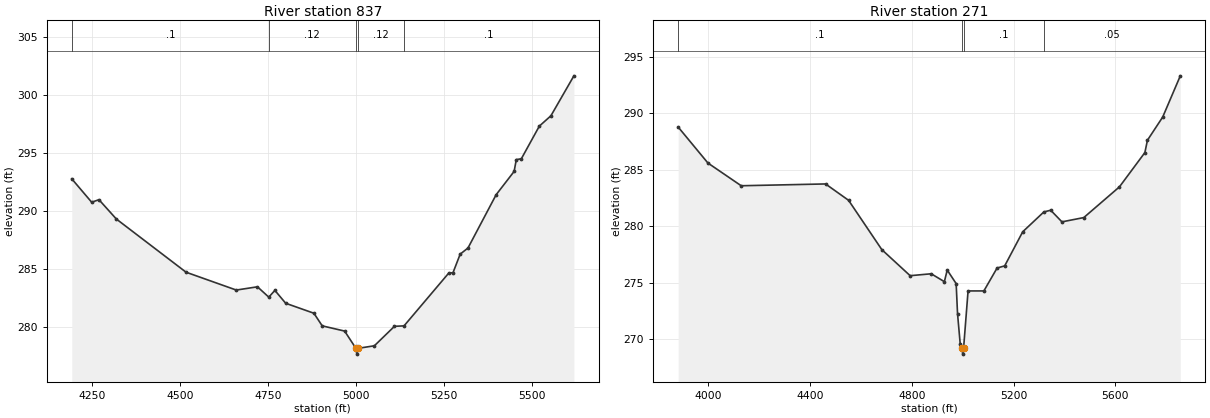
Type RM Length L Ch R = 1,837,566,566,566
BEGIN DESCRIPTION:
Mapping XS 79272fb0
END DESCRIPTION:
XS GIS Cut Line= 4
      2313798.46     13340543.23      2313742.91     13339838.40
      2313517.21     13339647.43      2313101.62     13339557.39
#Sta/Elev= 30
  4191.1  292.77  4247.7  290.75  4268.4  290.97  4317.9  289.30  4516.1  284.71
  4658.9  283.17  4719.1  283.45  4751.3  282.56  4768.7  283.14  4799.4  282.03
  4879.6  281.17  4903.3  280.08  4967.0  279.63  4999.1  278.14  5001.9  277.64
  5005.1  278.14  5051.6  278.36  5108.7  280.04  5136.0  280.08  5263.5  284.65
  5275.1  284.66  5295.6  286.27  5317.8  286.80  5397.9  291.40  5449.0  293.41
  5455.2  294.43  5469.5  294.50  5520.7  297.32  5553.6  298.21  5619.0  301.66
#Mann=5,-1,0
  4191.1     0.1       0  4751.3    0.12       0  4999.1    0.07       0
  5005.1    0.12       0  5136.0     0.1       0
Bank Sta=4999.1,5005.1
Exp/Cntr=0.3,0.1

Type RM Length L Ch R = 1,271,0,0,0
BEGIN DESCRIPTION:
UNT029 IN NURI 1.0
END DESCRIPTION:
XS GIS Cut Line= 4
      2313913.05     13340463.38      2313996.38     13339584.93
      2313888.74     13339178.68      2313218.58     13339189.10
#Sta/Elev= 30
  3882.3  288.79  3999.3  285.60  4129.9  283.59  4461.4  283.75  4551.8  282.30
  4682.4  277.93  4793.7  275.62  4876.5  275.79  4928.2  275.09  4939.4  276.12
  4974.5  274.92  4979.9  272.26  4990.3  269.61  4997.6  269.17  5000.4  268.67
  5003.6  269.17  5021.3  274.27  5083.4  274.27  5135.3  276.30  5165.2  276.49
  5236.0  279.51  5319.1  281.27  5346.0  281.42  5390.1  280.39  5476.0  280.77
  5616.0  283.49  5716.0  286.53  5726.0  287.62  5786.1  289.68  5855.2  293.33
#Mann=4,-1,0
  3882.3     0.1       0  4997.6    0.07       0  5003.6     0.1       0
  5319.1    0.05       0
Bank Sta=4997.6,5003.6
Exp/Cntr=0.3,0.1

Chan Stop Cuts=-1