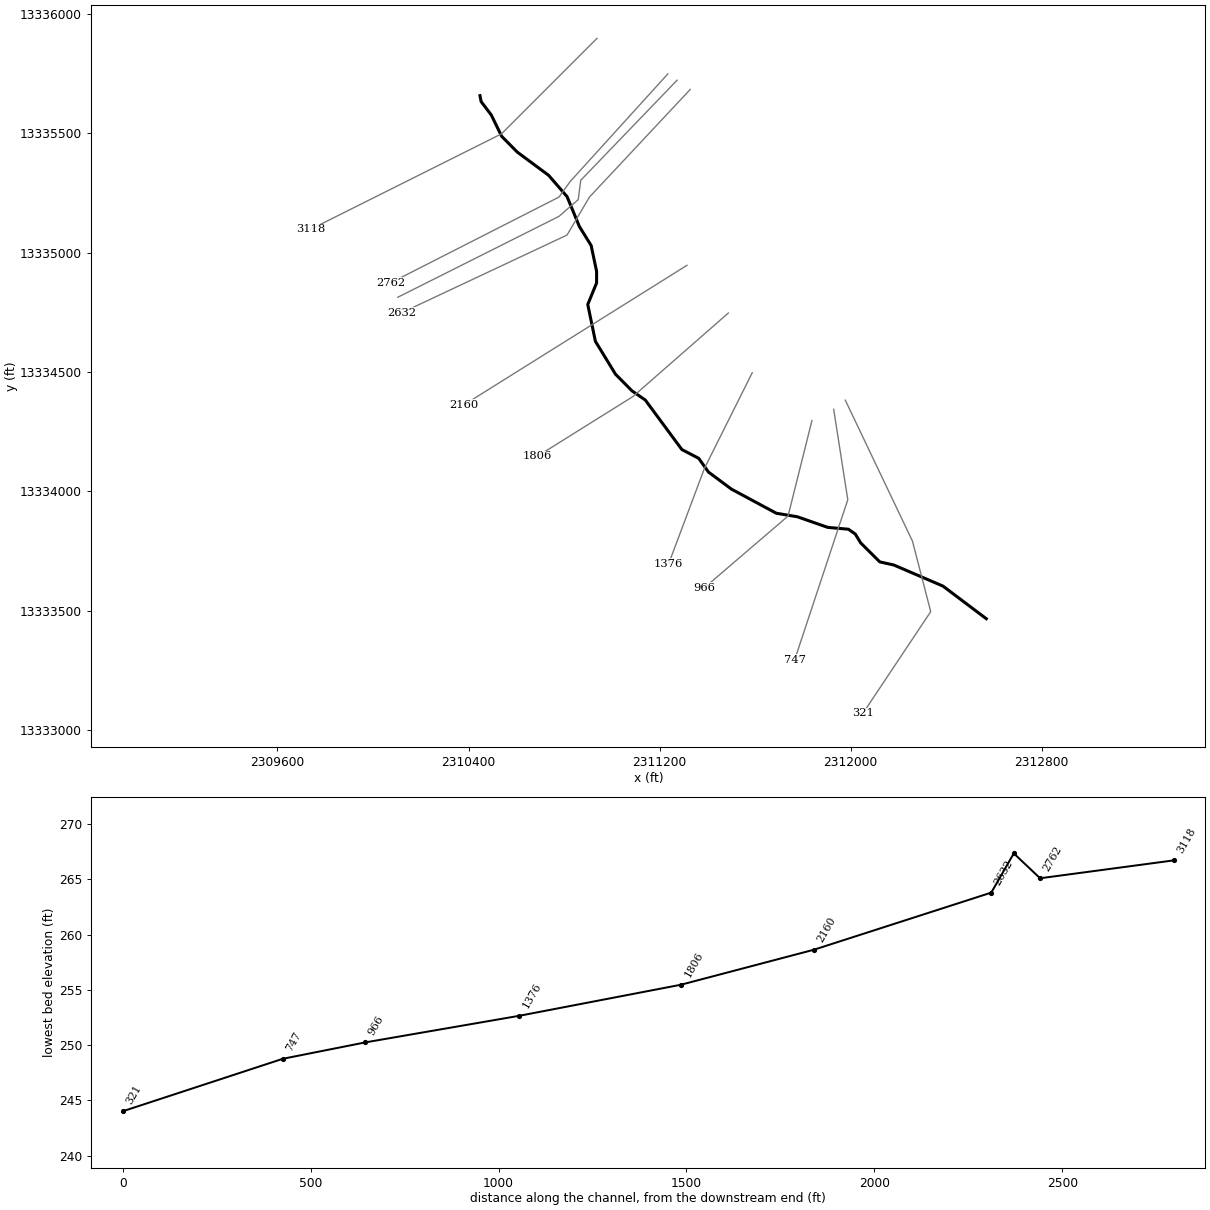
--- UNT030 IN NURI.prj (project) ---

Proj Title=UNT030 IN NURI Base Level Engineering
Current Plan=p01
Default Exp/Contr=0.3,0.1
English Units
Geom File=g01
Flow File=f01
Plan File=p01
BEGIN DESCRIPTION:
UNT030 IN NURI
END DESCRIPTION:

--- UNT030 IN NURI.p01 (plan) ---

Plan Title=Multiple Run
Short Identifier=Multiple
Geom File=g01
Flow File=f01
Subcritical Flow
K Sum by GR= 0
Std Step Tol= 0.01
Critical Tol= 0.01
Num of Std Step Trials= 20
Max Error Tol= 0.3
Flow Tol Ratio= 0.001
Split Flow NTrial= 30
Split Flow Tol= 0.02
Split Flow Ratio= 0.02
Log Output Level= 0
Friction Slope Method= 1
Unsteady Friction Slope Method= 2
Unsteady Bridges Friction Slope Method= 1
Parabolic Critical Depth
Global Vel Dist=  1 , 1 , 1
Global Log Level= 0
CheckData=True
Encroach Param= -1, 0, 0, 0
BEGIN DESCRIPTION:
Multiple Run
END DESCRIPTION:

--- UNT030 IN NURI.f01 (steady flow) ---

Flow Title=Multiple
Number of Profiles=7
Profile Names=10-year,25-year,50-year,1pct_min,100-year,1pct_plu,500-year
River Rch & RM= UNT030 IN NURI,Reach-1,3118
     805    1159    1462    1346    1821    2462    2835
Boundary for River Rch & Prof#=UNT030 IN NURI,Reach-1,1
Up Type=0
Dn Type=3
Dn Slope=0.005
Boundary for River Rch & Prof#=UNT030 IN NURI,Reach-1,2
Up Type=0
Dn Type=3
Dn Slope=0.005
Boundary for River Rch & Prof#=UNT030 IN NURI,Reach-1,3
Up Type=0
Dn Type=3
Dn Slope=0.005
Boundary for River Rch & Prof#=UNT030 IN NURI,Reach-1,4
Up Type=0
Dn Type=3
Dn Slope=0.005
Boundary for River Rch & Prof#=UNT030 IN NURI,Reach-1,5
Up Type=0
Dn Type=3
Dn Slope=0.005
Boundary for River Rch & Prof#=UNT030 IN NURI,Reach-1,6
Up Type=0
Dn Type=3
Dn Slope=0.005
Boundary for River Rch & Prof#=UNT030 IN NURI,Reach-1,7
Up Type=0
Dn Type=3
Dn Slope=0.005

--- UNT030 IN NURI.g01 (geometry) ---

Geom Title=Existing Conditions

River Reach=UNT030 IN NURI,Reach-1
Reach XY= 30
      2310447.72     13335656.86      2310452.67     13335631.88
      2310495.10     13335575.87      2310538.73     13335486.44
      2310603.79     13335420.73      2310735.26     13335323.26
      2310812.30     13335234.28      2310864.00     13335108.92
      2310913.17     13335029.72      2310936.12     13334920.97
      2310935.96     13334872.70      2310899.02     13334782.55
      2310931.06     13334628.21      2311015.26     13334490.63
      2311084.55     13334420.64      2311139.77     13334382.69
      2311293.07     13334175.17      2311363.38     13334138.57
      2311404.73     13334080.69      2311500.82     13334009.37
      2311688.43     13333908.57      2311776.44     13333893.77
      2311903.76     13333849.34      2311990.43     13333841.62
      2312018.98     13333821.57      2312041.86     13333784.21
      2312121.55     13333704.92      2312180.35     13333691.85
      2312386.31     13333603.46      2312567.72     13333466.85

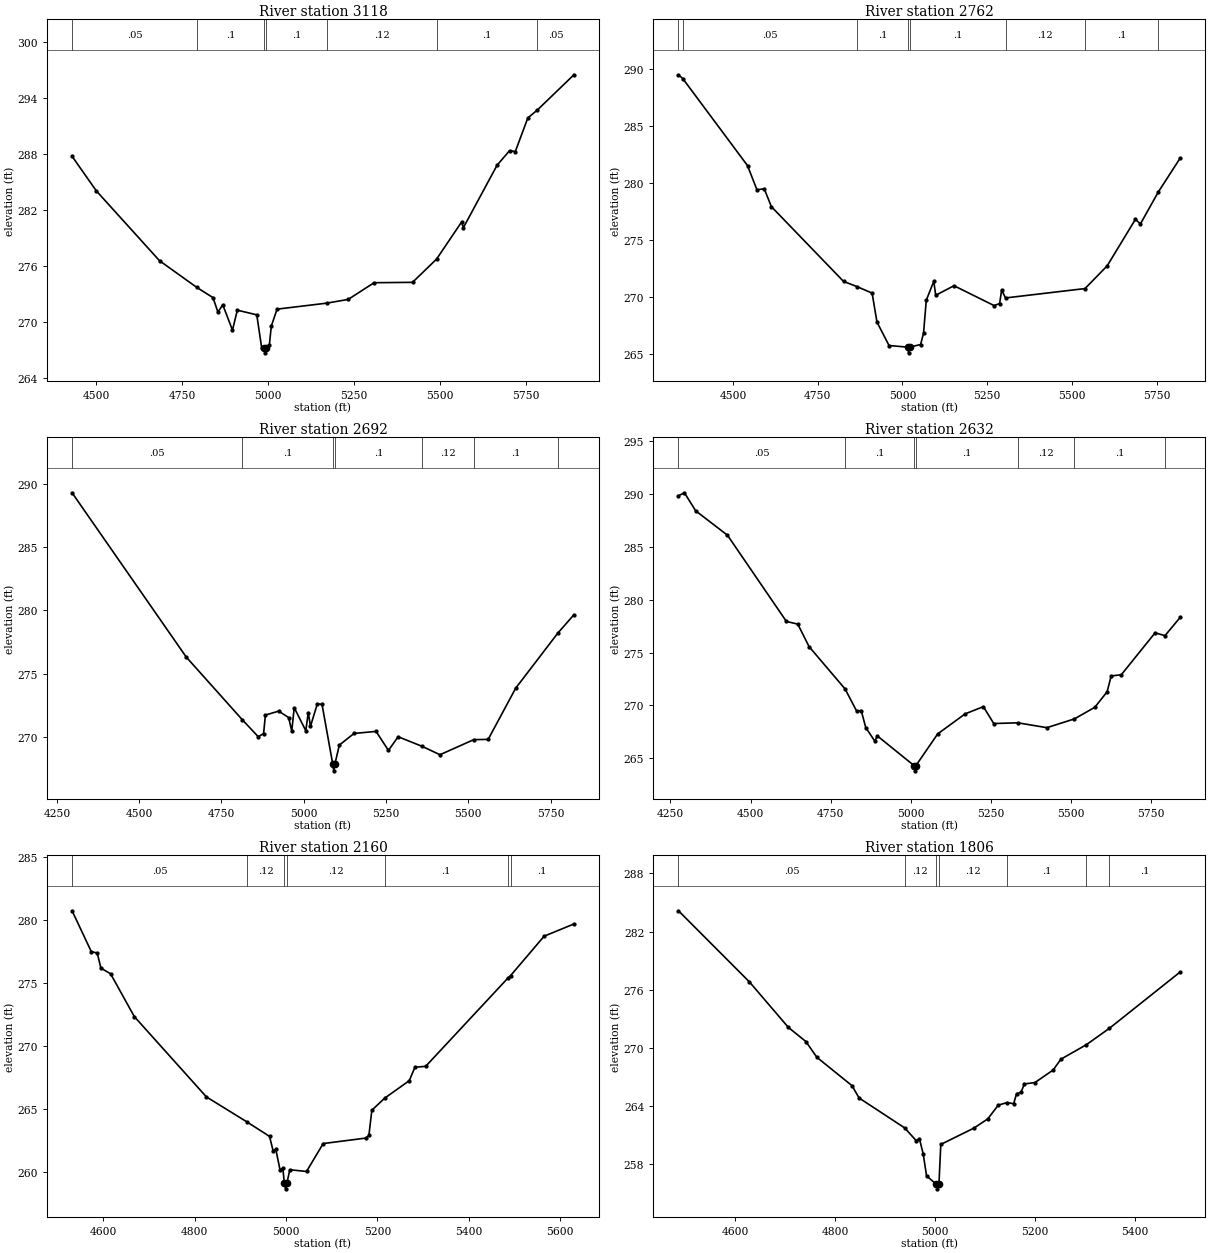
Type RM Length L Ch R = 1,3118,356,356,356
BEGIN DESCRIPTION:
UNT030 IN NURI 7.0
END DESCRIPTION:
XS GIS Cut Line= 3
      2310937.72     13335896.85      2310537.72     13335496.85
      2309737.73     13335096.86
#Sta/Elev= 30
  4429.8  287.77  4500.5  284.06  4684.4  276.58  4793.0  273.72  4839.9  272.63
  4854.1  271.08  4868.2  271.87  4896.5  269.15  4910.6  271.29  4967.2  270.79
  4981.3  267.29  4988.9  267.22  4991.7  266.72  4994.9  267.22  5003.9  267.60
  5009.5  269.59  5026.2  271.40  5170.4  272.04  5233.1  272.44  5308.5  274.23
  5420.3  274.27  5490.3  276.76  5562.9  280.72  5568.5  280.14  5666.3  286.81
  5702.6  288.37  5719.4  288.28  5755.7  291.87  5783.9  292.74  5889.9  296.50
#Mann=7,-1,0
  4429.8    0.05       0  4793.0     0.1       0  4988.9    0.07       0
  4994.9     0.1       0  5170.4    0.12       0  5490.3     0.1       0
  5783.9    0.05       0
Bank Sta=4988.9,4994.9
Exp/Cntr=0.3,0.1

Type RM Length L Ch R = 1,2762,70,70,70
BEGIN DESCRIPTION:
Mapping XS 3b0809b4
END DESCRIPTION:
XS GIS Cut Line= 4
      2311234.11     13335747.75      2310825.29     13335297.26
      2310778.41     13335232.15      2310072.71     13334872.79
#Sta/Elev= 30
  4339.2  289.46  4351.8  289.13  4542.9  281.50  4570.6  279.39  4592.2  279.47
  4613.2  277.91  4826.1  271.36  4866.9  270.89  4910.5  270.33  4924.7  267.80
  4960.4  265.74  5015.1  265.60  5017.9  265.10  5021.1  265.60  5053.5  265.83
  5062.2  266.83  5070.2  269.70  5092.4  271.37  5098.0  270.14  5152.0  270.98
  5270.3  269.24  5286.6  269.42  5292.6  270.60  5304.1  269.91  5538.5  270.73
  5603.9  272.72  5687.3  276.80  5701.9  276.39  5754.7  279.19  5819.7  282.18
#Mann=8,-1,0
  4339.2     0.1       0  4351.8    0.05       0  4866.9     0.1       0
  5015.1    0.07       0  5021.1     0.1       0  5304.1    0.12       0
  5538.5     0.1       0  5754.7    0.05       0
Bank Sta=5015.1,5021.1
Exp/Cntr=0.3,0.1

Type RM Length L Ch R = 1,2692,60,60,60
BEGIN DESCRIPTION:
UNT030 IN NURI 6.0
END DESCRIPTION:
XS GIS Cut Line= 5
      2311273.17     13335721.70      2310869.56     13335302.47
      2310859.14     13335221.74      2310778.41     13335151.42
      2310103.91     13334812.87
#Sta/Elev= 30
  4296.0  289.28  4642.8  276.33  4813.3  271.38  4861.9  270.04  4878.0  270.29
  4883.6  271.75  4923.9  272.06  4954.2  271.55  4963.6  270.48  4971.1  272.33
  5006.2  270.52  5013.9  271.95  5020.5  270.86  5041.4  272.64  5055.6  272.59
  5088.4  267.85  5091.2  267.35  5094.4  267.85  5108.2  269.38  5152.9  270.30
  5219.9  270.46  5257.4  268.96  5286.9  270.04  5360.8  269.27  5414.0  268.62
  5516.8  269.81  5560.5  269.83  5644.2  273.87  5772.1  278.21  5821.1  279.66
#Mann=7,-1,0
  4296.0    0.05       0  4813.3     0.1       0  5088.4    0.07       0
  5094.4     0.1       0  5360.8    0.12       0  5516.8     0.1       0
  5772.1    0.05       0
Bank Sta=5088.4,5094.4
Exp/Cntr=0.3,0.1

Type RM Length L Ch R = 1,2632,472,472,472
BEGIN DESCRIPTION:
Mapping XS e8b707b0
END DESCRIPTION:
XS GIS Cut Line= 4
      2311327.87     13335682.65      2310906.01     13335232.15
      2310812.26     13335073.30      2310121.11     13334748.51
#Sta/Elev= 30
  4275.3  289.86  4293.8  290.14  4329.0  288.43  4428.1  286.12  4612.0  277.95
  4647.4  277.70  4682.6  275.57  4795.1  271.55  4831.2  269.45  4845.3  269.51
  4859.4  267.90  4887.6  266.62  4895.9  267.10  5010.0  264.30  5012.7  263.80
  5016.0  264.30  5083.9  267.30  5169.6  269.20  5226.3  269.88  5258.7  268.28
  5333.4  268.35  5424.5  267.89  5510.3  268.72  5573.9  269.82  5612.3  271.29
  5625.0  272.79  5656.5  272.90  5761.8  276.87  5792.9  276.61  5840.6  278.35
#Mann=7,-1,0
  4275.3    0.05       0  4795.1     0.1       0  5010.0    0.07       0
  5016.0     0.1       0  5333.4    0.12       0  5510.3     0.1       0
  5792.9    0.05       0
Bank Sta=5010,5016
Exp/Cntr=0.3,0.1

Type RM Length L Ch R = 1,2160,354,354,354
BEGIN DESCRIPTION:
UNT030 IN NURI 5.0
END DESCRIPTION:
XS GIS Cut Line= 2
      2311314.42     13334946.55      2310382.42     13334363.40
#Sta/Elev= 30
  4531.3  280.74  4573.3  277.50  4586.4  277.38  4594.5  276.18  4615.7  275.73
  4667.6  272.33  4825.6  265.94  4914.5  263.95  4963.9  262.80  4971.8  261.64
  4977.7  261.76  4987.1  260.10  4993.0  260.28  4996.2  259.13  4999.0  258.63
  5002.2  259.13  5008.3  260.15  5044.9  260.01  5081.4  262.23  5175.7  262.67
  5181.6  262.89  5188.0  264.88  5216.1  265.84  5270.0  267.23  5282.4  268.30
  5305.9  268.37  5485.9  275.38  5491.8  275.58  5565.5  278.72  5630.7  279.69
#Mann=7,-1,0
  4531.3    0.05       0  4914.5    0.12       0  4996.2    0.07       0
  5002.2    0.12       0  5216.1     0.1       0  5485.9    0.05       0
  5491.8     0.1       0
Bank Sta=4996.2,5002.2
Exp/Cntr=0.3,0.1

Type RM Length L Ch R = 1,1806,430,430,430
BEGIN DESCRIPTION:
UNT030 IN NURI 4.0
END DESCRIPTION:
XS GIS Cut Line= 3
      2311487.70     13334746.84      2311087.72     13334396.85
      2310687.70     13334146.84
#Sta/Elev= 30
  4486.9  284.14  4628.8  276.80  4706.6  272.11  4741.7  270.65  4763.5  269.03
  4833.8  266.10  4848.0  264.83  4939.2  261.74  4961.9  260.44  4968.6  260.62
  4976.1  259.07  4982.8  256.80  5001.6  255.96  5004.4  255.46  5007.6  255.96
  5011.3  260.04  5077.3  261.72  5105.1  262.67  5126.3  264.10  5144.4  264.36
  5156.9  264.24  5162.8  265.28  5171.7  265.41  5178.2  266.28  5199.4  266.42
  5236.0  267.72  5251.3  268.83  5302.1  270.32  5348.4  272.02  5490.1  277.84
#Mann=7,-1,0
  4486.9    0.05       0  4939.2    0.12       0  5001.6    0.07       0
  5007.6    0.12       0  5144.4     0.1       0  5302.1    0.05       0
  5348.4     0.1       0
Bank Sta=5001.6,5007.6
Exp/Cntr=0.3,0.1

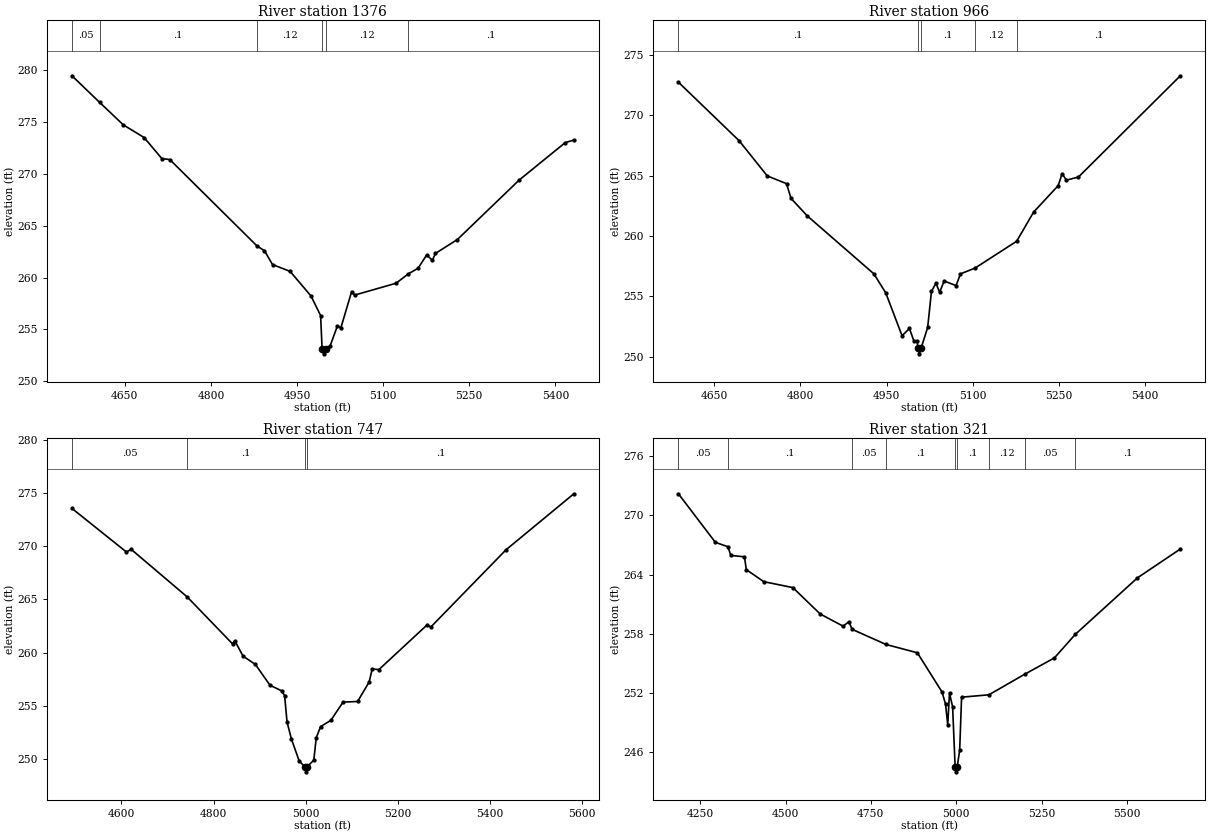
Type RM Length L Ch R = 1,1376,410,410,410
BEGIN DESCRIPTION:
UNT030 IN NURI 3.0
END DESCRIPTION:
XS GIS Cut Line= 3
      2311587.73     13334496.86      2311387.72     13334096.85
      2311237.73     13333696.88
#Sta/Elev= 30
  4557.8  279.43  4606.0  276.87  4647.3  274.70  4683.6  273.48  4714.3  271.46
  4728.3  271.36  4880.2  263.04  4893.2  262.58  4907.2  261.25  4937.9  260.59
  4974.3  258.22  4991.0  256.34  4993.6  253.15  4996.4  252.65  4999.6  253.15
  5007.7  253.43  5020.2  255.33  5026.4  255.17  5045.1  258.65  5050.4  258.31
  5122.5  259.45  5144.0  260.36  5160.8  260.89  5175.9  262.18  5185.7  261.65
  5191.0  262.32  5229.3  263.66  5337.0  269.39  5417.1  272.99  5432.2  273.24
#Mann=6,-1,0
  4557.8    0.05       0  4606.0     0.1       0  4880.2    0.12       0
  4993.6    0.07       0  4999.6    0.12       0  5144.0     0.1       0
Bank Sta=4993.6,4999.6
Exp/Cntr=0.3,0.1

Type RM Length L Ch R = 1,966,219,219,219
BEGIN DESCRIPTION:
UNT030 IN NURI 2.0
END DESCRIPTION:
XS GIS Cut Line= 3
      2311837.73     13334296.88      2311737.72     13333896.85
      2311387.73     13333596.87
#Sta/Elev= 30
  4587.7  272.73  4693.4  267.88  4742.3  264.97  4775.8  264.33  4783.6  263.11
  4811.9  261.66  4927.9  256.86  4948.5  255.28  4976.8  251.74  4989.7  252.34
  4997.5  251.29  5003.3  251.29  5004.2  250.74  5006.9  250.24  5010.2  250.74
  5021.4  252.43  5028.0  255.41  5035.7  256.08  5042.3  255.34  5050.0  256.27
  5070.8  255.89  5078.5  256.86  5103.8  257.34  5176.2  259.56  5205.8  261.98
  5248.6  264.17  5255.2  265.15  5262.9  264.62  5283.8  264.88  5461.0  273.26
#Mann=5,-1,0
  4587.7     0.1       0  5004.2    0.07       0  5010.2     0.1       0
  5103.8    0.12       0  5176.2     0.1       0
Bank Sta=5004.2,5010.2
Exp/Cntr=0.3,0.1

Type RM Length L Ch R = 1,747,426,426,426
BEGIN DESCRIPTION:
Mapping XS 40255723
END DESCRIPTION:
XS GIS Cut Line= 3
      2311928.67     13334343.76      2311987.70     13333965.31
      2311765.49     13333295.22
#Sta/Elev= 30
  4492.7  273.58  4611.0  269.47  4621.1  269.73  4742.8  265.24  4841.1  260.82
  4846.1  261.11  4864.0  259.66  4890.7  258.88  4922.4  256.92  4947.8  256.39
  4954.1  255.95  4959.4  253.46  4968.9  251.85  4985.8  249.78  4997.5  249.26
  5000.3  248.76  5003.5  249.26  5017.5  249.87  5022.7  251.96  5032.1  253.02
  5054.4  253.61  5080.9  255.33  5112.5  255.39  5137.5  257.22  5144.2  258.46
  5158.6  258.39  5263.9  262.63  5271.0  262.39  5434.7  269.69  5581.7  274.96
#Mann=4,-1,0
  4492.7    0.05       0  4742.8     0.1       0  4997.5    0.07       0
  5003.5     0.1       0
Bank Sta=4997.5,5003.5
Exp/Cntr=0.3,0.1

Type RM Length L Ch R = 1,321,0,0,0
BEGIN DESCRIPTION:
UNT030 IN NURI 1.0
END DESCRIPTION:
XS GIS Cut Line= 4
      2311977.30     13334381.95      2312258.53     13333791.70
      2312334.92     13333496.56      2312050.96     13333070.63
#Sta/Elev= 30
  4186.1  272.20  4294.3  267.28  4331.2  266.83  4339.7  265.95  4379.6  265.81
  4385.1  264.51  4436.1  263.29  4521.4  262.69  4601.6  260.01  4668.6  258.78
  4685.8  259.23  4694.9  258.46  4794.6  256.92  4886.2  256.08  4958.6  252.10
  4968.9  250.86  4975.2  248.78  4980.4  251.98  4989.5  250.61  4996.9  244.51
  4999.6  244.01  5002.9  244.51  5010.2  246.20  5015.8  251.58  5095.9  251.82
  5200.9  253.91  5287.8  255.56  5349.3  257.96  5531.2  263.68  5656.7  266.60
#Mann=9,-1,0
  4186.1    0.05       0  4331.2     0.1       0  4694.9    0.05       0
  4794.6     0.1       0  4996.9    0.07       0  5002.9     0.1       0
  5095.9    0.12       0  5200.9    0.05       0  5349.3     0.1       0
Bank Sta=4996.9,5002.9
Exp/Cntr=0.3,0.1

Chan Stop Cuts=-1