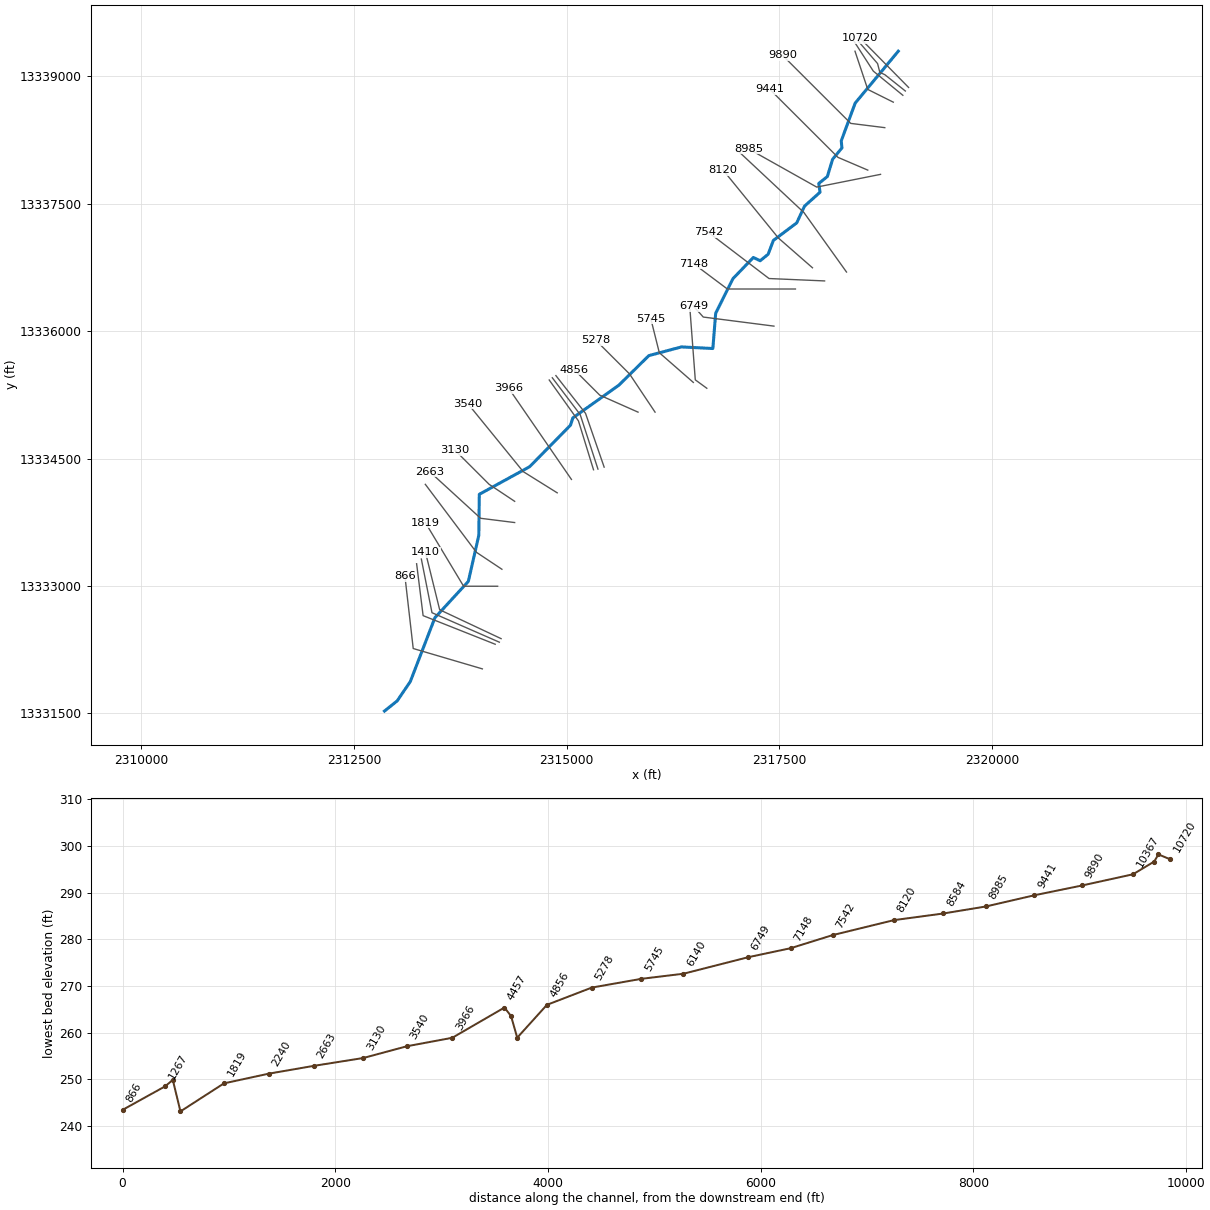
--- UNT031 IN NURI.prj (project) ---

Proj Title=UNT031 IN NURI Base Level Engineering
Current Plan=p01
Default Exp/Contr=0.3,0.1
English Units
Geom File=g01
Flow File=f01
Plan File=p01
BEGIN DESCRIPTION:
UNT031 IN NURI
END DESCRIPTION:

--- UNT031 IN NURI.p01 (plan) ---

Plan Title=Multiple Run
Short Identifier=Multiple
Geom File=g01
Flow File=f01
Subcritical Flow
K Sum by GR= 0
Std Step Tol= 0.01
Critical Tol= 0.01
Num of Std Step Trials= 20
Max Error Tol= 0.3
Flow Tol Ratio= 0.001
Split Flow NTrial= 30
Split Flow Tol= 0.02
Split Flow Ratio= 0.02
Log Output Level= 0
Friction Slope Method= 1
Unsteady Friction Slope Method= 2
Unsteady Bridges Friction Slope Method= 1
Parabolic Critical Depth
Global Vel Dist=  1 , 1 , 1
Global Log Level= 0
CheckData=True
Encroach Param= -1, 0, 0, 0
BEGIN DESCRIPTION:
Multiple Run
END DESCRIPTION:

--- UNT031 IN NURI.f01 (steady flow) ---

Flow Title=Multiple
Number of Profiles=7
Profile Names=10-year,25-year,50-year,1pct_min,100-year,1pct_plu,500-year
River Rch & RM= UNT031 IN NURI,Reach-1,10720
     634     901    1126    1029    1391    1881    2131
River Rch & RM= UNT031 IN NURI,Reach-1,9890
     793    1138    1432    1315    1779    2405    2755
River Rch & RM= UNT031 IN NURI,Reach-1,6140
    1189    1739    2216    2057    2782    3762    4405
Boundary for River Rch & Prof#=UNT031 IN NURI,Reach-1,1
Up Type=0
Dn Type=3
Dn Slope=0.005
Boundary for River Rch & Prof#=UNT031 IN NURI,Reach-1,2
Up Type=0
Dn Type=3
Dn Slope=0.005
Boundary for River Rch & Prof#=UNT031 IN NURI,Reach-1,3
Up Type=0
Dn Type=3
Dn Slope=0.005
Boundary for River Rch & Prof#=UNT031 IN NURI,Reach-1,4
Up Type=0
Dn Type=3
Dn Slope=0.005
Boundary for River Rch & Prof#=UNT031 IN NURI,Reach-1,5
Up Type=0
Dn Type=3
Dn Slope=0.005
Boundary for River Rch & Prof#=UNT031 IN NURI,Reach-1,6
Up Type=0
Dn Type=3
Dn Slope=0.005
Boundary for River Rch & Prof#=UNT031 IN NURI,Reach-1,7
Up Type=0
Dn Type=3
Dn Slope=0.005

--- UNT031 IN NURI.g01 (geometry) ---

Geom Title=Existing Conditions

River Reach=UNT031 IN NURI,Reach-1
Reach XY= 30
      2318896.42     13339296.99      2318389.72     13338685.84
      2318225.98     13338240.47      2318234.14     13338158.51
      2318123.97     13338023.75      2318062.84     13337821.09
      2317961.97     13337739.70      2317976.80     13337636.52
      2317794.91     13337473.17      2317702.33     13337275.07
      2317428.70     13337069.13      2317366.49     13336905.50
      2317273.02     13336829.67      2317193.06     13336868.22
      2316953.40     13336618.96      2316750.14     13336210.67
      2316717.13     13335796.08      2316348.26     13335814.98
      2315964.70     13335712.47      2315613.39     13335365.23
      2315071.66     13334979.15      2315044.24     13334893.44
      2314564.06     13334404.48      2313972.12     13334079.35
      2313966.54     13333597.34      2313843.28     13333053.98
      2313450.21     13332625.82      2313161.49     13331874.74
      2313006.68     13331646.38      2312857.72     13331526.85

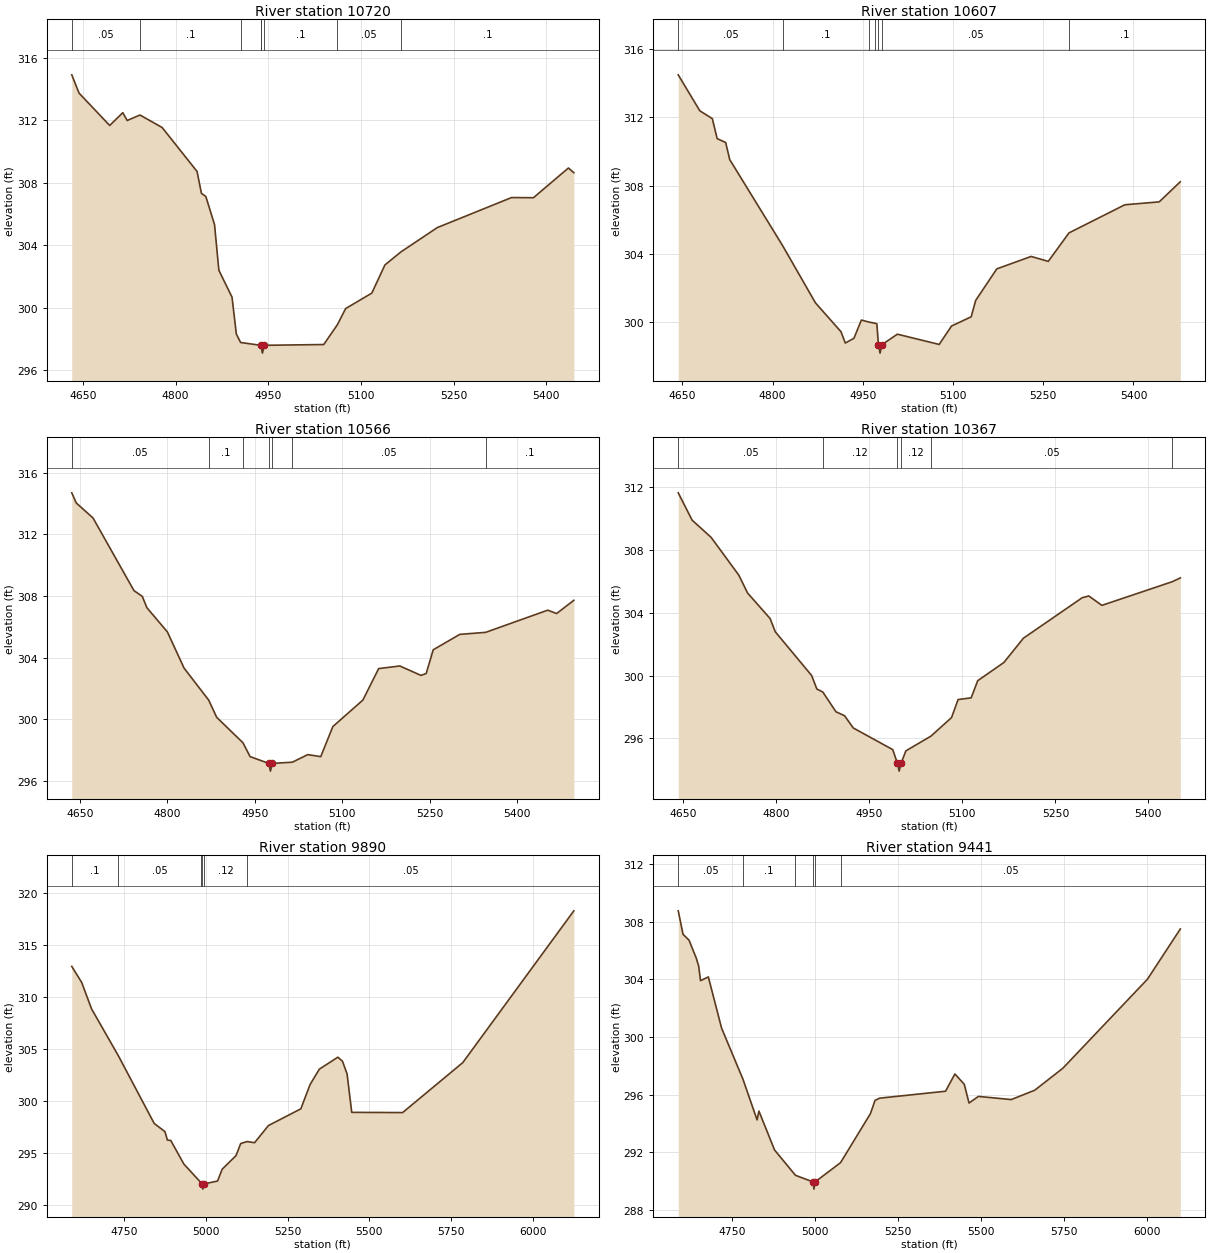
Type RM Length L Ch R = 1,10720,113,113,113
BEGIN DESCRIPTION:
UNT031 IN NURI 22.0
END DESCRIPTION:
XS GIS Cut Line= 2
      2319017.66     13338869.99      2318448.22     13339449.84
#Sta/Elev= 30
  4632.0  314.91  4643.8  313.74  4693.4  311.67  4714.6  312.49  4721.7  311.99
  4742.4  312.34  4778.3  311.54  4834.8  308.73  4841.9  307.33  4849.0  307.13
  4863.1  305.33  4870.1  302.41  4891.4  300.69  4898.4  298.33  4905.3  297.79
  4937.8  297.61  4937.9  297.61  4940.6  297.11  4943.9  297.61  5039.9  297.66
  5062.0  298.93  5075.3  299.96  5117.7  300.95  5138.9  302.75  5165.0  303.59
  5223.7  305.14  5343.9  307.06  5379.3  307.05  5435.9  308.95  5444.7  308.65
#Mann=8,-1,0
  4632.0    0.05       0  4742.4     0.1       0  4905.3    0.12       0
  4937.8     0.1       0  4937.9    0.07       0  4943.9     0.1       0
  5062.0    0.05       0  5165.0     0.1       0
Bank Sta=4937.9,4943.9
Exp/Cntr=0.3,0.1

Type RM Length L Ch R = 1,10607,41,41,41
BEGIN DESCRIPTION:
Mapping XS aaa4e4b7
END DESCRIPTION:
XS GIS Cut Line= 5
      2318979.41     13338828.36      2318739.87     13339019.31
      2318679.10     13339048.82      2318653.06     13339151.25
      2318421.67     13339420.64
#Sta/Elev= 30
  4643.2  314.50  4679.1  312.39  4699.9  311.93  4707.9  310.76  4722.1  310.53
  4728.8  309.53  4816.8  304.48  4871.3  301.13  4913.9  299.43  4920.9  298.77
  4935.3  299.05  4947.7  300.12  4960.4  300.00  4970.8  299.93  4973.4  299.90
  4976.0  298.68  4978.7  298.18  4982.0  298.68  5007.5  299.29  5077.0  298.69
  5097.6  299.77  5130.2  300.31  5137.7  301.27  5172.8  303.12  5229.9  303.85
  5258.4  303.56  5292.8  305.23  5385.7  306.88  5442.8  307.05  5477.9  308.23
#Mann=7,-1,0
  4643.2    0.05       0  4816.8     0.1       0  4960.4    0.12       0
  4970.8    0.05       0  4976.0    0.03       0  4982.0    0.05       0
  5292.8     0.1       0
Bank Sta=4976,4982
Exp/Cntr=0.3,0.1

Type RM Length L Ch R = 1,10566,199,199,199
BEGIN DESCRIPTION:
Mapping XS 22e93bf5
END DESCRIPTION:
XS GIS Cut Line= 3
      2318949.97     13338777.96      2318602.72     13339062.71
      2318378.73     13339409.97
#Sta/Elev= 30
  4635.6  314.69  4643.4  314.03  4672.1  313.06  4742.4  308.35  4756.8  307.97
  4764.6  307.24  4799.8  305.67  4828.5  303.32  4870.7  301.25  4884.5  300.13
  4929.6  298.48  4941.9  297.58  4974.1  297.14  4976.8  296.64  4980.1  297.14
  5014.5  297.22  5040.9  297.71  5063.2  297.58  5084.0  299.53  5135.6  301.25
  5162.7  303.29  5199.0  303.46  5235.3  302.85  5244.3  302.97  5256.4  304.51
  5302.0  305.51  5346.4  305.64  5453.1  307.08  5468.3  306.86  5497.9  307.72
#Mann=7,-1,0
  4635.6    0.05       0  4870.7     0.1       0  4929.6    0.12       0
  4974.1    0.07       0  4980.1    0.12       0  5014.5    0.05       0
  5346.4     0.1       0
Bank Sta=4974.1,4980.1
Exp/Cntr=0.3,0.1

Type RM Length L Ch R = 1,10367,477,477,477
BEGIN DESCRIPTION:
UNT031 IN NURI 21.0
END DESCRIPTION:
XS GIS Cut Line= 3
      2318837.74     13338696.85      2318537.72     13338846.85
      2318387.71     13339296.88
#Sta/Elev= 30
  4641.7  311.65  4664.1  309.91  4694.8  308.81  4739.5  306.40  4753.5  305.27
  4789.9  303.64  4798.2  302.80  4856.9  300.01  4865.3  299.15  4874.9  298.96
  4896.1  297.70  4910.0  297.45  4924.0  296.67  4987.7  295.29  4995.2  294.42
  4998.0  293.92  5001.2  294.42  5008.8  295.21  5049.3  296.15  5082.5  297.33
  5093.1  298.48  5114.2  298.59  5124.7  299.68  5166.9  300.84  5198.5  302.39
  5293.4  304.97  5303.9  305.08  5325.0  304.48  5438.7  305.99  5451.5  306.23
#Mann=6,-1,0
  4641.7    0.05       0  4874.9    0.12       0  4995.2    0.07       0
  5001.2    0.12       0  5049.3    0.05       0  5438.7     0.1       0
Bank Sta=4995.2,5001.2
Exp/Cntr=0.3,0.1

Type RM Length L Ch R = 1,9890,449,449,449
BEGIN DESCRIPTION:
UNT031 IN NURI 20.0
END DESCRIPTION:
XS GIS Cut Line= 3
      2318737.74     13338396.85      2318337.72     13338446.85
      2317537.73     13339246.85
#Sta/Elev= 30
  4590.4  312.97  4620.7  311.43  4650.9  308.88  4732.8  304.37  4842.4  297.85
  4875.1  297.07  4882.7  296.25  4892.8  296.22  4933.1  293.94  4986.3  292.12
  4988.0  292.03  4990.8  291.53  4994.0  292.03  5036.0  292.31  5050.1  293.45
  5092.5  294.76  5106.7  295.92  5126.2  296.11  5149.1  296.00  5191.5  297.65
  5290.5  299.26  5318.8  301.60  5347.1  303.08  5403.7  304.23  5417.8  303.84
  5431.9  302.61  5446.1  298.92  5601.6  298.90  5785.5  303.71  6124.9  318.32
#Mann=6,-1,0
  4590.4     0.1       0  4732.8    0.05       0  4986.3    0.12       0
  4988.0    0.07       0  4994.0    0.12       0  5126.2    0.05       0
Bank Sta=4988,4994
Exp/Cntr=0.3,0.1

Type RM Length L Ch R = 1,9441,456,456,456
BEGIN DESCRIPTION:
UNT031 IN NURI 19.0
END DESCRIPTION:
XS GIS Cut Line= 3
      2318537.73     13337896.85      2318187.72     13338046.85
      2317387.70     13338846.88
#Sta/Elev= 30
  4588.2  308.76  4602.7  307.13  4620.8  306.72  4642.6  305.47  4649.9  304.91
  4655.3  303.91  4678.9  304.17  4718.8  300.61  4782.9  297.08  4825.7  294.24
  4831.2  294.85  4878.3  292.15  4941.3  290.39  4994.3  289.93  4997.0  289.43
  5000.3  289.93  5077.1  291.27  5167.0  294.67  5181.1  295.60  5195.3  295.75
  5393.3  296.23  5421.5  297.43  5449.8  296.71  5464.0  295.41  5492.3  295.87
  5591.2  295.65  5662.0  296.30  5746.8  297.83  6001.4  304.01  6100.4  307.50
#Mann=6,-1,0
  4588.2    0.05       0  4782.9     0.1       0  4941.3    0.12       0
  4994.3    0.07       0  5000.3    0.12       0  5077.1    0.05       0
Bank Sta=4994.3,5000.3
Exp/Cntr=0.3,0.1

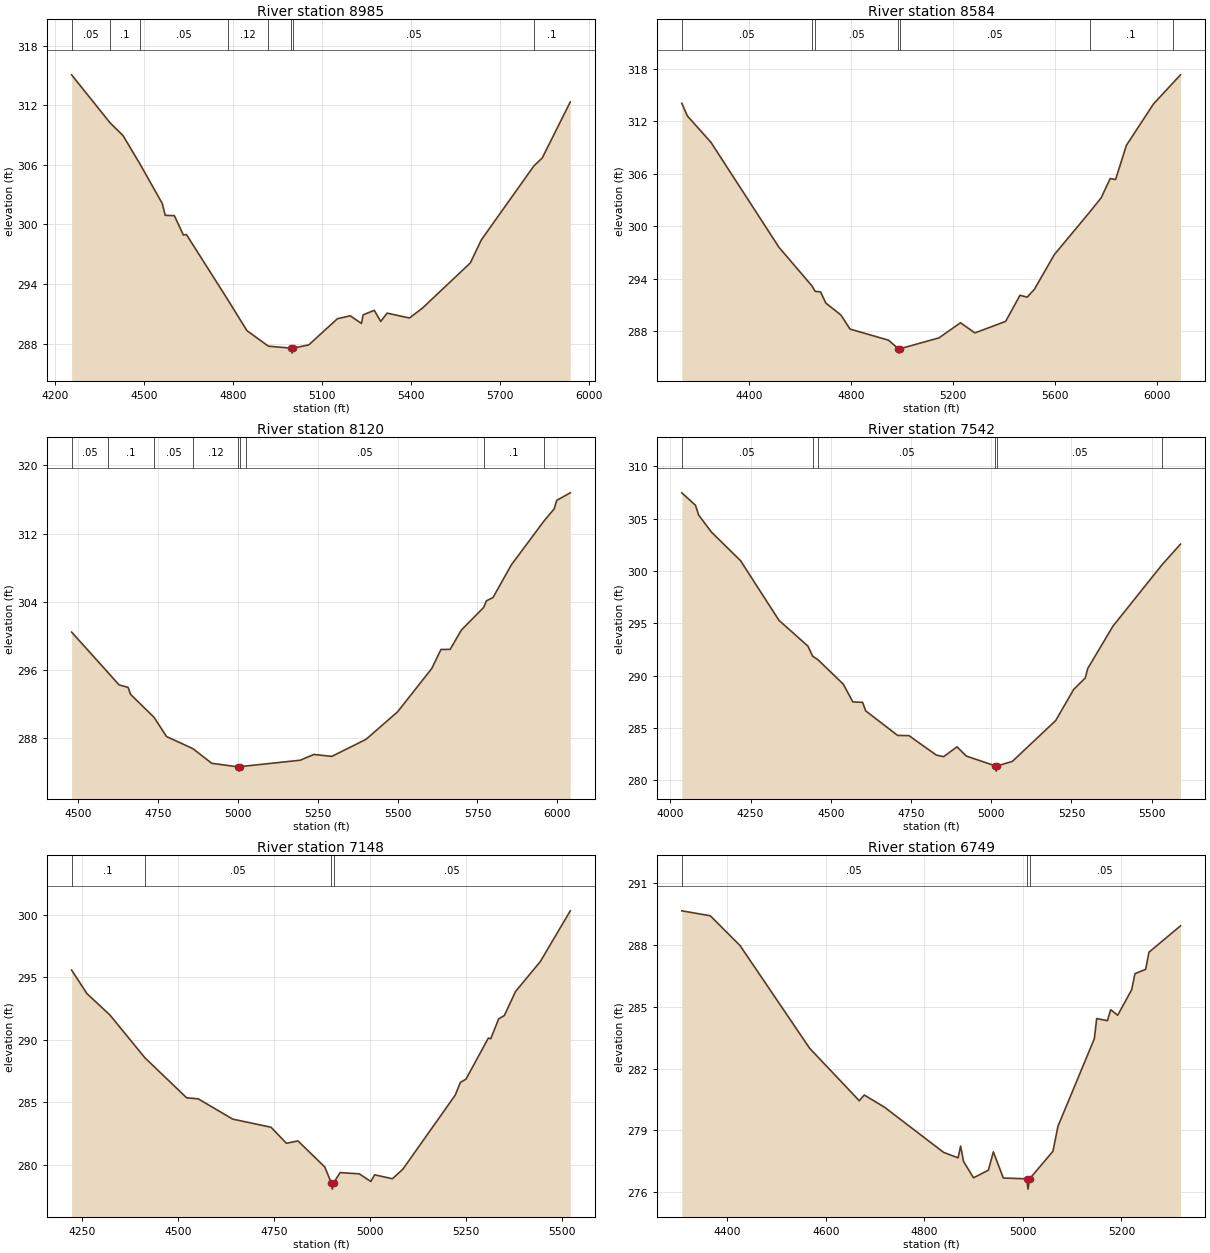
Type RM Length L Ch R = 1,8985,401,401,401
BEGIN DESCRIPTION:
UNT031 IN NURI 18.0
END DESCRIPTION:
XS GIS Cut Line= 3
      2318687.70     13337846.85      2317937.72     13337696.85
      2317137.73     13338146.85
#Sta/Elev= 30
  4254.4  315.07  4384.9  310.21  4427.7  308.96  4484.5  306.12  4560.3  302.11
  4570.5  300.91  4601.1  300.88  4631.7  298.93  4641.9  298.98  4783.2  292.33
  4845.9  289.30  4918.4  287.73  4995.8  287.53  4998.6  287.03  5001.8  287.53
  5054.6  287.86  5151.5  290.50  5194.8  290.79  5232.4  290.02  5238.2  290.89
  5275.8  291.34  5297.5  290.22  5319.1  291.06  5394.3  290.57  5437.7  291.55
  5599.6  296.11  5637.2  298.45  5814.5  305.90  5842.4  306.69  5937.1  312.34
#Mann=8,-1,0
  4254.4    0.05       0  4384.9     0.1       0  4484.5    0.05       0
  4783.2    0.12       0  4918.4    0.05       0  4995.8    0.04       0
  5001.8    0.05       0  5814.5     0.1       0
Bank Sta=4995.8,5001.8
Exp/Cntr=0.3,0.1

Type RM Length L Ch R = 1,8584,464,464,464
BEGIN DESCRIPTION:
UNT031 IN NURI 17.0
END DESCRIPTION:
XS GIS Cut Line= 3
      2318287.74     13336696.83      2317787.72     13337396.85
      2316987.76     13338146.82
#Sta/Elev= 30
  4136.4  314.08  4158.6  312.62  4250.7  309.62  4517.4  297.63  4646.6  293.22
  4659.8  292.58  4680.8  292.52  4701.7  291.24  4760.7  289.88  4796.4  288.27
  4947.5  287.00  4986.3  286.02  4989.0  285.52  4992.3  286.02  5145.4  287.26
  5229.9  288.99  5286.6  287.83  5407.2  289.15  5463.4  292.13  5491.7  291.92
  5520.1  292.82  5598.2  296.78  5736.2  301.61  5781.9  303.27  5817.5  305.48
  5838.5  305.36  5881.0  309.27  5987.0  313.99  6063.2  316.39  6093.2  317.33
#Mann=7,-1,0
  4136.4    0.05       0  4646.6     0.1       0  4659.8    0.05       0
  4986.3    0.04       0  4992.3    0.05       0  5736.2     0.1       0
  6063.2    0.05       0
Bank Sta=4986.3,4992.3
Exp/Cntr=0.3,0.1

Type RM Length L Ch R = 1,8120,578,578,578
BEGIN DESCRIPTION:
UNT031 IN NURI 16.0
END DESCRIPTION:
XS GIS Cut Line= 3
      2317887.74     13336746.84      2317487.72     13337096.85
      2316837.73     13337896.85
#Sta/Elev= 30
  4478.4  300.43  4591.4  295.73  4627.0  294.23  4655.4  293.94  4663.0  293.12
  4736.5  290.43  4776.0  288.16  4858.5  286.74  4917.4  285.02  4999.8  284.60
  5002.6  284.10  5005.8  284.60  5024.1  284.70  5194.5  285.38  5237.6  286.06
  5293.6  285.83  5400.7  287.83  5499.8  291.07  5606.8  296.16  5635.6  298.39
  5664.3  298.40  5699.5  300.67  5769.4  303.33  5777.8  304.10  5798.6  304.49
  5856.1  308.33  5958.4  313.48  5990.4  314.92  5998.3  315.91  6040.7  316.79
#Mann=9,-1,0
  4478.4    0.05       0  4591.4     0.1       0  4736.5    0.05       0
  4858.5    0.12       0  4999.8    0.07       0  5005.8    0.12       0
  5024.1    0.05       0  5769.4     0.1       0  5958.4    0.05       0
Bank Sta=4999.8,5005.8
Exp/Cntr=0.3,0.1

Type RM Length L Ch R = 1,7542,394,394,394
BEGIN DESCRIPTION:
UNT031 IN NURI 15.0
END DESCRIPTION:
XS GIS Cut Line= 3
      2318030.35     13336592.00      2317377.14     13336620.21
      2316661.86     13337166.42
#Sta/Elev= 30
  4035.8  307.46  4078.5  306.27  4088.5  305.33  4128.5  303.70  4218.6  300.99
  4338.7  295.28  4428.8  292.82  4443.5  291.86  4460.4  291.51  4538.9  289.19
  4568.9  287.49  4599.0  287.45  4609.0  286.63  4708.3  284.29  4743.6  284.27
  4828.9  282.41  4851.6  282.26  4893.3  283.20  4922.3  282.32  5012.8  281.38
  5015.6  280.88  5018.8  281.38  5065.7  281.81  5200.8  285.71  5257.0  288.69
  5292.8  289.77  5300.6  290.68  5379.5  294.74  5533.2  300.63  5589.6  302.56
#Mann=6,-1,0
  4035.8    0.05       0  4443.5     0.1       0  4460.4    0.05       0
  5012.8    0.03       0  5018.8    0.05       0  5533.2     0.1       0
Bank Sta=5012.8,5018.8
Exp/Cntr=0.3,0.1

Type RM Length L Ch R = 1,7148,399,399,399
BEGIN DESCRIPTION:
UNT031 IN NURI 14.0
END DESCRIPTION:
XS GIS Cut Line= 3
      2317687.71     13336496.85      2316887.72     13336496.85
      2316487.71     13336796.86
#Sta/Elev= 30
  4221.6  295.57  4261.6  293.69  4321.6  291.98  4412.6  288.57  4521.6  285.37
  4551.6  285.29  4641.6  283.67  4741.6  283.02  4781.6  281.74  4811.6  281.93
  4881.6  279.85  4898.6  278.58  4901.3  278.08  4904.6  278.58  4921.6  279.40
  4971.6  279.30  5001.6  278.69  5011.6  279.22  5058.0  278.91  5085.1  279.67
  5221.6  285.58  5235.1  286.60  5249.7  286.86  5308.0  290.14  5314.3  290.09
  5335.1  291.68  5349.7  291.94  5378.9  293.86  5443.5  296.25  5521.6  300.30
#Mann=4,-1,0
  4221.6     0.1       0  4412.6    0.05       0  4898.6    0.03       0
  4904.6    0.05       0
Bank Sta=4898.6,4904.6
Exp/Cntr=0.3,0.1

Type RM Length L Ch R = 1,6749,609,609,609
BEGIN DESCRIPTION:
UNT031 IN NURI 13.0
END DESCRIPTION:
XS GIS Cut Line= 3
      2317435.15     13336059.82      2316604.39     13336166.59
      2316487.69     13336296.88
#Sta/Elev= 30
  4307.3  289.66  4365.2  289.42  4425.7  287.97  4566.8  282.99  4667.7  280.44
  4677.7  280.72  4719.3  280.12  4839.1  277.93  4868.3  277.67  4873.4  278.24
  4879.4  277.49  4899.6  276.70  4929.8  277.07  4939.9  277.96  4960.1  276.69
  5007.5  276.65  5010.2  276.15  5013.5  276.65  5060.9  277.99  5071.0  279.20
  5144.9  283.45  5149.7  284.43  5171.4  284.33  5178.1  284.86  5192.3  284.59
  5220.7  285.83  5227.4  286.61  5249.1  286.82  5255.8  287.65  5319.8  288.93
#Mann=3,-1,0
  4307.3    0.05       0  5007.5    0.03       0  5013.5    0.05       0
Bank Sta=5007.5,5013.5
Exp/Cntr=0.3,0.1

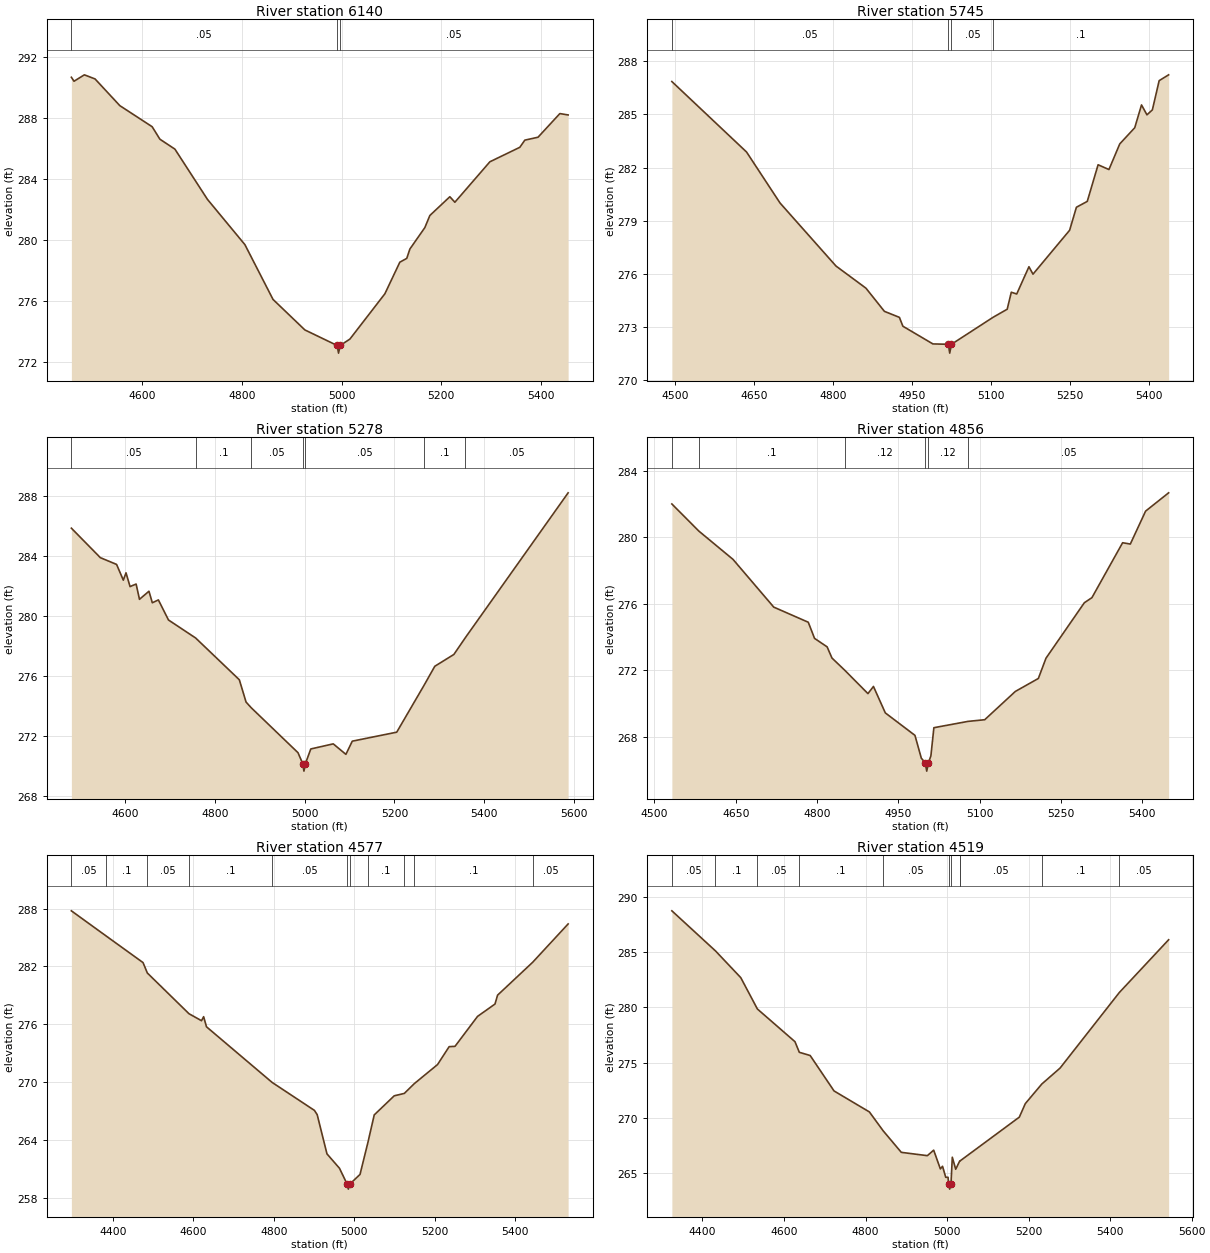
Type RM Length L Ch R = 1,6140,395,395,395
BEGIN DESCRIPTION:
UNT031 IN NURI 12.0
END DESCRIPTION:
XS GIS Cut Line= 3
      2316646.05     13335328.06      2316510.64     13335427.01
      2316448.27     13336253.45
#Sta/Elev= 30
  4458.0  290.69  4463.3  290.43  4484.1  290.85  4505.5  290.58  4555.2  288.83
  4620.0  287.45  4635.6  286.63  4665.7  285.98  4730.9  282.69  4806.1  279.72
  4862.5  276.13  4926.4  274.13  4991.2  273.11  4993.9  272.61  4997.2  273.11
  5016.7  273.53  5086.9  276.50  5116.9  278.57  5130.8  278.82  5137.0  279.43
  5167.1  280.84  5177.1  281.63  5217.2  282.86  5227.3  282.50  5297.5  285.15
  5357.6  286.10  5367.7  286.57  5394.1  286.76  5437.9  288.31  5454.5  288.22
#Mann=3,-1,0
  4458.0    0.05       0  4991.2    0.03       0  4997.2    0.05       0
Bank Sta=4991.2,4997.2
Exp/Cntr=0.3,0.1

Type RM Length L Ch R = 1,5745,467,467,467
BEGIN DESCRIPTION:
UNT031 IN NURI 11.0
END DESCRIPTION:
XS GIS Cut Line= 3
      2316487.70     13335396.87      2316087.72     13335746.85
      2315987.72     13336146.86
#Sta/Elev= 30
  4493.3  286.86  4635.2  282.88  4698.8  280.00  4805.1  276.44  4862.0  275.19
  4897.1  273.88  4925.6  273.54  4932.2  273.04  4989.2  272.04  5018.5  272.02
  5021.2  271.52  5024.5  272.02  5103.9  273.55  5130.4  274.00  5138.2  274.96
  5148.5  274.86  5171.7  276.40  5179.4  275.98  5249.0  278.46  5261.9  279.76
  5282.5  280.09  5303.1  282.16  5323.7  281.89  5344.3  283.34  5372.7  284.25
  5385.6  285.54  5395.9  284.98  5406.2  285.26  5419.1  286.91  5437.1  287.24
#Mann=4,-1,0
  4493.3    0.05       0  5018.5    0.03       0  5024.5    0.05       0
  5103.9     0.1       0
Bank Sta=5018.5,5024.5
Exp/Cntr=0.3,0.1

Type RM Length L Ch R = 1,5278,422,422,422
BEGIN DESCRIPTION:
UNT031 IN NURI 10.0
END DESCRIPTION:
XS GIS Cut Line= 3
      2316037.72     13335046.86      2315737.72     13335496.85
      2315337.73     13335896.84
#Sta/Elev= 30
  4480.3  285.86  4544.9  283.89  4581.0  283.44  4596.0  282.39  4602.0  282.88
  4611.0  281.96  4624.5  282.13  4632.0  281.11  4653.1  281.65  4660.6  280.88
  4674.1  281.07  4696.6  279.73  4757.0  278.53  4854.4  275.74  4869.4  274.25
  4881.3  273.86  4985.1  270.87  4995.6  270.14  4998.3  269.64  5001.6  270.14
  5013.6  271.12  5063.6  271.46  5091.8  270.76  5106.0  271.64  5205.0  272.24
  5265.3  275.34  5289.8  276.64  5332.3  277.43  5358.1  278.56  5586.8  288.22
#Mann=7,-1,0
  4480.3    0.05       0  4757.0     0.1       0  4881.3    0.05       0
  4995.6    0.03       0  5001.6    0.05       0  5265.3     0.1       0
  5358.1    0.05       0
Bank Sta=4995.6,5001.6
Exp/Cntr=0.3,0.1

Type RM Length L Ch R = 1,4856,279,279,279
BEGIN DESCRIPTION:
UNT031 IN NURI 9.0
END DESCRIPTION:
XS GIS Cut Line= 3
      2315837.68     13335046.87      2315387.72     13335246.85
      2315087.70     13335546.88
#Sta/Elev= 30
  4532.1  282.00  4581.9  280.37  4644.9  278.67  4720.1  275.80  4783.8  274.89
  4795.4  273.92  4818.6  273.41  4827.5  272.74  4851.6  271.99  4893.9  270.60
  4904.1  271.03  4926.0  269.44  4980.7  268.09  4992.4  266.72  4999.6  266.44
  5002.4  265.94  5005.6  266.44  5010.1  266.86  5015.6  268.55  5078.6  268.93
  5109.4  269.03  5165.9  270.73  5208.4  271.51  5222.5  272.73  5293.2  276.06
  5307.3  276.37  5363.9  279.67  5378.1  279.59  5406.3  281.57  5448.8  282.67
#Mann=6,-1,0
  4532.1    0.05       0  4581.9     0.1       0  4851.6    0.12       0
  4999.6    0.07       0  5005.6    0.12       0  5078.6    0.05       0
Bank Sta=4999.6,5005.6
Exp/Cntr=0.3,0.1

Type RM Length L Ch R = 1,4577,58,58,58
BEGIN DESCRIPTION:
Mapping XS 3a7bbf79
END DESCRIPTION:
XS GIS Cut Line= 3
      2315439.53     13334399.48      2315220.77     13335032.33
      2314872.27     13335477.05
#Sta/Elev= 30
  4297.0  287.77  4382.4  285.19  4475.1  282.40  4485.8  281.32  4589.2  277.10
  4620.4  276.37  4625.7  276.79  4632.8  275.74  4795.9  269.97  4901.0  267.07
  4907.9  266.63  4932.2  262.56  4963.4  261.06  4982.5  259.40  4985.3  258.90
  4988.5  259.40  5014.4  260.43  5034.2  263.78  5049.7  266.60  5099.4  268.58
  5124.5  268.83  5149.2  269.84  5207.0  271.82  5235.9  273.68  5250.4  273.71
  5306.5  276.82  5349.8  278.10  5356.2  279.02  5443.4  282.43  5531.6  286.41
#Mann=11,-1,0
  4297.0    0.05       0  4382.4     0.1       0  4485.8    0.05       0
  4589.2     0.1       0  4795.9    0.05       0  4982.5    0.03       0
  4988.5    0.05       0  5034.2     0.1       0  5124.5    0.05       0
  5149.2     0.1       0  5443.4    0.05       0
Bank Sta=4982.5,4988.5
Exp/Cntr=0.3,0.1

Type RM Length L Ch R = 1,4519,62,62,62
BEGIN DESCRIPTION:
UNT031 IN NURI 8.0
END DESCRIPTION:
XS GIS Cut Line= 3
      2315366.60     13334376.10      2315157.83     13335018.01
      2314830.14     13335451.61
#Sta/Elev= 30
  4325.0  288.74  4432.0  285.11  4494.0  282.69  4534.8  279.85  4627.0  276.89
  4637.6  275.93  4664.2  275.64  4722.8  272.43  4809.5  270.53  4843.3  268.82
  4887.8  266.87  4951.7  266.57  4967.2  267.07  4983.6  265.37  4988.9  265.61
  4996.8  264.61  5002.4  264.61  5003.7  264.04  5006.4  263.54  5009.7  264.04
  5012.9  266.43  5021.2  265.34  5031.1  266.09  5031.4  266.08  5177.3  270.06
  5191.9  271.28  5232.5  273.06  5277.2  274.50  5422.5  281.34  5543.5  286.12
#Mann=11,-1,0
  4325.0    0.05       0  4432.0     0.1       0  4534.8    0.05       0
  4637.6     0.1       0  4843.3    0.05       0  5003.7    0.03       0
  5009.7    0.05       0  5031.1     0.1       0  5031.4    0.05       0
  5232.5     0.1       0  5422.5    0.05       0
Bank Sta=5003.7,5009.7
Exp/Cntr=0.3,0.1

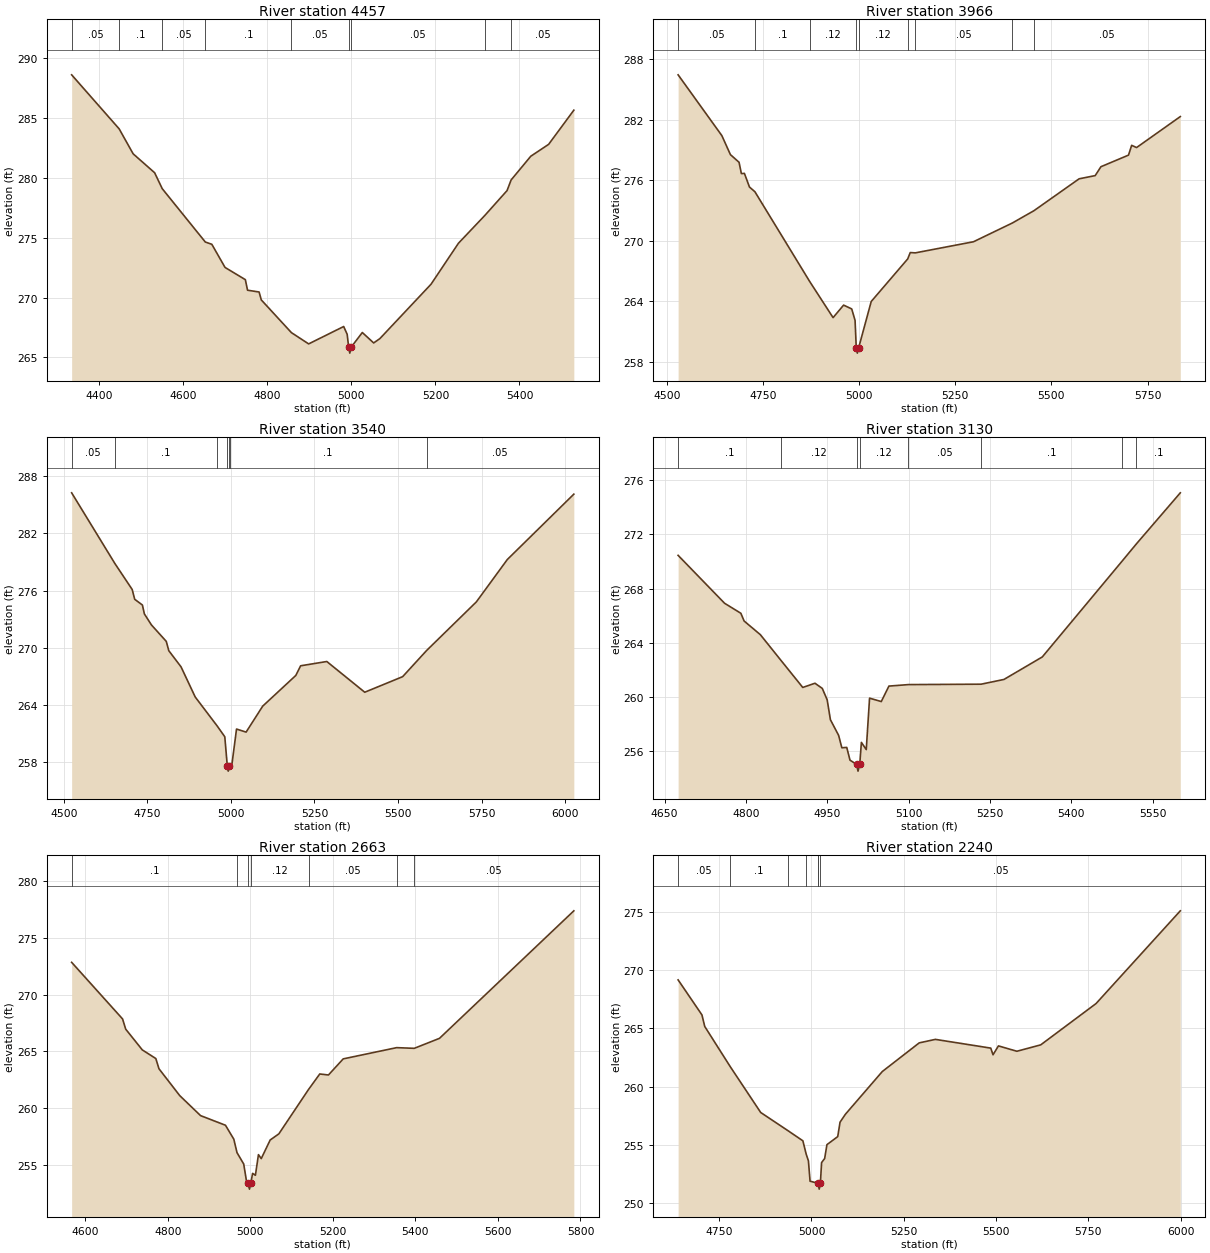
Type RM Length L Ch R = 1,4457,491,491,491
BEGIN DESCRIPTION:
Mapping XS f1afc575
END DESCRIPTION:
XS GIS Cut Line= 3
      2315314.52     13334368.27      2315137.44     13334943.78
      2314793.67     13335425.58
#Sta/Elev= 30
  4335.2  288.58  4448.2  284.07  4481.4  281.99  4532.5  280.41  4550.6  279.08
  4653.0  274.63  4668.5  274.44  4699.9  272.51  4748.2  271.49  4753.4  270.61
  4780.9  270.46  4786.1  269.80  4857.7  267.07  4898.7  266.13  4982.0  267.58
  4990.3  266.93  4993.8  265.86  4996.5  265.36  4999.8  265.86  5026.3  267.08
  5053.3  266.21  5068.0  266.57  5189.7  271.11  5254.9  274.53  5317.4  276.84
  5370.4  278.92  5380.1  279.81  5426.9  281.79  5469.3  282.78  5529.2  285.63
#Mann=9,-1,0
  4335.2    0.05       0  4448.2     0.1       0  4550.6    0.05       0
  4653.0     0.1       0  4857.7    0.05       0  4993.8    0.03       0
  4999.8    0.05       0  5317.4     0.1       0  5380.1    0.05       0
Bank Sta=4993.8,4999.8
Exp/Cntr=0.3,0.1

Type RM Length L Ch R = 1,3966,426,426,426
BEGIN DESCRIPTION:
UNT031 IN NURI 7.0
END DESCRIPTION:
XS GIS Cut Line= 2
      2315054.87     13334254.74      2314315.28     13335331.14
#Sta/Elev= 30
  4529.2  286.47  4643.0  280.44  4665.2  278.56  4687.7  277.80  4693.7  276.68
  4701.6  276.70  4714.7  275.35  4728.9  274.88  4871.4  265.98  4932.2  262.40
  4959.6  263.64  4980.7  263.26  4989.4  262.12  4992.5  259.38  4995.3  258.88
  4998.5  259.38  5031.4  264.00  5126.3  268.22  5132.9  268.85  5146.1  268.82
  5297.3  269.92  5398.4  271.78  5454.6  273.00  5572.0  276.16  5613.9  276.48
  5628.8  277.36  5700.5  278.51  5708.7  279.48  5721.5  279.26  5835.2  282.33
#Mann=9,-1,0
  4529.2    0.05       0  4728.9     0.1       0  4871.4    0.12       0
  4992.5    0.07       0  4998.5    0.12       0  5126.3     0.1       0
  5146.1    0.05       0  5398.4     0.1       0  5454.6    0.05       0
Bank Sta=4992.5,4998.5
Exp/Cntr=0.3,0.1

Type RM Length L Ch R = 1,3540,410,410,410
BEGIN DESCRIPTION:
UNT031 IN NURI 6.0
END DESCRIPTION:
XS GIS Cut Line= 3
      2314887.75     13334096.84      2314487.72     13334346.85
      2313837.73     13335146.84
#Sta/Elev= 30
  4523.7  286.24  4652.9  278.84  4704.8  276.11  4712.4  275.08  4735.4  274.48
  4741.3  273.55  4762.5  272.39  4806.8  270.67  4814.4  269.69  4851.0  268.00
  4893.4  264.84  4959.4  261.79  4981.9  260.67  4989.5  257.57  4992.2  257.07
  4995.5  257.57  4996.7  257.57  5002.6  257.62  5017.0  261.48  5045.7  261.16
  5095.3  263.88  5194.4  267.10  5208.8  268.11  5287.1  268.56  5400.6  265.34
  5514.0  266.97  5585.9  269.72  5734.6  274.81  5827.2  279.25  6026.2  286.10
#Mann=7,-1,0
  4523.7    0.05       0  4652.9     0.1       0  4959.4    0.12       0
  4989.5    0.07       0  4995.5    0.12       0  4996.7     0.1       0
  5585.9    0.05       0
Bank Sta=4989.5,4995.5
Exp/Cntr=0.3,0.1

Type RM Length L Ch R = 1,3130,467,467,467
BEGIN DESCRIPTION:
UNT031 IN NURI 5.0
END DESCRIPTION:
XS GIS Cut Line= 3
      2314387.73     13333996.85      2314087.72     13334196.85
      2313687.75     13334596.82
#Sta/Elev= 30
  4674.8  270.46  4760.4  266.93  4790.5  266.19  4796.5  265.62  4826.5  264.61
  4865.2  262.68  4904.7  260.72  4927.2  261.03  4940.7  260.65  4949.7  259.81
  4955.7  258.34  4970.8  257.19  4976.8  256.27  4985.8  256.30  4991.8  255.36
  5003.8  255.05  5006.6  254.55  5009.8  255.05  5012.8  256.67  5021.8  256.14
  5027.9  259.93  5049.5  259.68  5063.6  260.82  5099.6  260.93  5233.7  260.96
  5275.8  261.31  5346.5  262.97  5494.2  270.06  5519.9  271.30  5601.0  275.07
#Mann=8,-1,0
  4674.8     0.1       0  4865.2    0.12       0  5003.8    0.07       0
  5009.8    0.12       0  5099.6    0.05       0  5233.7     0.1       0
  5494.2    0.05       0  5519.9     0.1       0
Bank Sta=5003.8,5009.8
Exp/Cntr=0.3,0.1

Type RM Length L Ch R = 1,2663,423,423,423
BEGIN DESCRIPTION:
UNT031 IN NURI 4.0
END DESCRIPTION:
XS GIS Cut Line= 3
      2314387.69     13333746.86      2313987.72     13333796.85
      2313387.74     13334346.84
#Sta/Elev= 30
  4567.0  272.85  4690.4  267.86  4698.0  266.96  4738.3  265.13  4771.0  264.37
  4778.6  263.47  4829.0  261.10  4879.4  259.34  4939.8  258.49  4960.0  257.26
  4967.7  256.08  4984.0  255.07  4991.4  253.41  4995.1  253.36  4997.9  252.86
  5001.1  253.36  5005.5  254.25  5012.3  254.08  5019.7  255.90  5026.5  255.55
  5048.1  257.19  5069.1  257.73  5141.0  261.64  5168.3  263.01  5189.3  262.92
  5225.1  264.34  5354.5  265.33  5397.3  265.27  5458.4  266.15  5784.0  277.39
#Mann=7,-1,0
  4567.0     0.1       0  4967.7    0.12       0  4995.1    0.07       0
  5001.1    0.12       0  5141.0    0.05       0  5354.5     0.1       0
  5397.3    0.05       0
Bank Sta=4995.1,5001.1
Exp/Cntr=0.3,0.1

Type RM Length L Ch R = 1,2240,421,421,421
BEGIN DESCRIPTION:
UNT031 IN NURI 3.0
END DESCRIPTION:
XS GIS Cut Line= 3
      2314237.71     13333196.86      2313937.72     13333396.85
      2313337.74     13334196.82
#Sta/Elev= 30
  4638.8  269.16  4703.4  266.15  4710.9  265.16  4780.6  261.68  4862.6  257.77
  4936.4  256.21  4976.8  255.34  4985.8  254.19  4991.8  253.62  4996.3  251.87
  5017.4  251.70  5018.2  251.69  5021.0  251.19  5024.2  251.69  5027.5  253.47
  5035.8  253.82  5042.0  255.01  5071.2  255.70  5077.5  256.94  5092.0  257.62
  5192.0  261.29  5292.0  263.75  5335.8  264.05  5485.8  263.30  5492.0  262.73
  5506.6  263.49  5556.6  263.03  5621.2  263.58  5771.2  267.13  5999.3  275.09
#Mann=7,-1,0
  4638.8    0.05       0  4780.6     0.1       0  4936.4    0.05       0
  4985.8    0.12       0  5017.4    0.05       0  5018.2    0.07       0
  5024.2    0.05       0
Bank Sta=5018.2,5024.2
Exp/Cntr=0.3,0.1

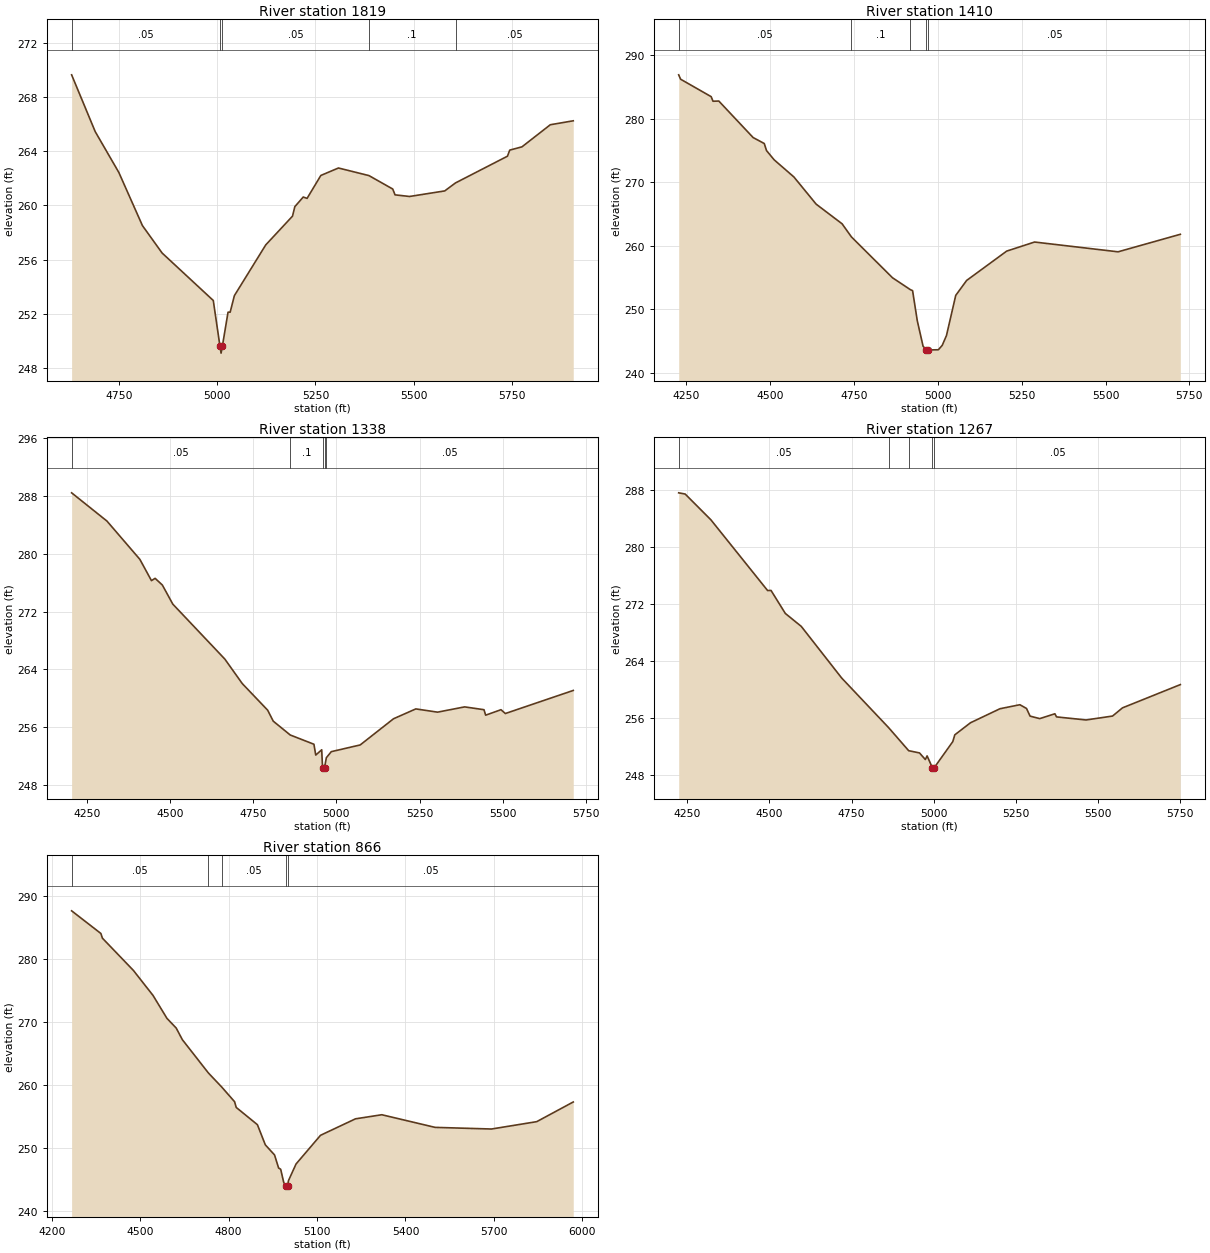
Type RM Length L Ch R = 1,1819,409,409,409
BEGIN DESCRIPTION:
UNT031 IN NURI 2.0
END DESCRIPTION:
XS GIS Cut Line= 3
      2314187.74     13332996.85      2313787.72     13332996.85
      2313337.70     13333746.88
#Sta/Elev= 30
  4630.4  269.63  4690.4  265.44  4750.4  262.43  4810.4  258.51  4860.4  256.49
  4990.4  252.99  5007.4  249.61  5010.2  249.11  5013.4  249.61  5027.9  252.13
  5033.3  252.13  5044.0  253.35  5123.7  257.09  5191.7  259.21  5197.6  259.91
  5219.0  260.62  5228.7  260.52  5263.7  262.21  5308.4  262.76  5385.9  262.20
  5446.4  261.21  5452.2  260.78  5489.1  260.66  5578.5  261.07  5605.9  261.66
  5737.9  263.63  5743.7  264.08  5774.8  264.32  5846.8  265.95  5905.1  266.24
#Mann=5,-1,0
  4630.4    0.05       0  5007.4    0.03       0  5013.4    0.05       0
  5385.9     0.1       0  5605.9    0.05       0
Bank Sta=5007.4,5013.4
Exp/Cntr=0.3,0.1

Type RM Length L Ch R = 1,1410,72,72,72
BEGIN DESCRIPTION:
Mapping XS 6f87fc5a
END DESCRIPTION:
XS GIS Cut Line= 3
      2314228.47     13332379.73      2313506.28     13332720.00
      2313339.62     13333397.05
#Sta/Elev= 30
  4227.5  286.94  4233.2  286.25  4324.3  283.50  4329.8  282.78  4347.1  282.81
  4449.4  277.06  4482.6  276.12  4489.3  275.01  4512.1  273.55  4571.0  270.85
  4637.3  266.57  4714.7  263.47  4742.6  261.40  4865.0  254.97  4918.5  253.09
  4924.8  252.95  4938.8  248.21  4956.1  244.19  4966.0  243.60  4968.7  243.10
  4972.0  243.60  5001.7  243.63  5013.2  244.33  5025.8  245.86  5053.5  252.20
  5086.0  254.55  5205.4  259.17  5288.5  260.60  5537.5  259.06  5723.1  261.82
#Mann=5,-1,0
  4227.5    0.05       0  4742.6     0.1       0  4918.5    0.05       0
  4966.0    0.03       0  4972.0    0.05       0
Bank Sta=4966,4972
Exp/Cntr=0.3,0.1

Type RM Length L Ch R = 1,1338,71,71,71
BEGIN DESCRIPTION:
Mapping XS 03afbd42
END DESCRIPTION:
XS GIS Cut Line= 3
      2314207.63     13332338.07      2313416.00     13332685.28
      2313291.00     13333317.20
#Sta/Elev= 30
  4203.8  288.46  4310.1  284.54  4409.1  279.23  4443.9  276.28  4454.9  276.60
  4476.7  275.67  4508.0  273.03  4664.6  265.40  4716.9  262.01  4793.4  258.31
  4810.2  256.79  4861.3  254.87  4932.5  253.59  4938.0  252.09  4955.9  252.82
  4958.4  250.36  4961.1  249.86  4964.4  250.36  4969.9  251.72  4984.7  252.56
  5071.6  253.49  5171.8  257.12  5238.9  258.49  5304.3  258.04  5385.8  258.77
  5443.9  258.38  5449.0  257.62  5495.1  258.38  5508.2  257.85  5712.4  261.05
#Mann=5,-1,0
  4203.8    0.05       0  4861.3     0.1       0  4958.4    0.03       0
  4964.4     0.1       0  4969.9    0.05       0
Bank Sta=4958.4,4964.4
Exp/Cntr=0.3,0.1

Type RM Length L Ch R = 1,1267,401,401,401
BEGIN DESCRIPTION:
Mapping XS 17fa67b1
END DESCRIPTION:
XS GIS Cut Line= 3
      2314159.04     13332313.75      2313311.83     13332650.56
      2313235.44     13333261.69
#Sta/Elev= 30
  4223.7  287.60  4243.4  287.43  4321.7  283.81  4494.4  273.87  4504.9  273.88
  4548.4  270.65  4597.0  268.83  4720.1  261.57  4863.0  254.60  4924.1  251.36
  4956.9  251.05  4974.8  250.12  4980.1  250.63  4996.1  248.99  4998.8  248.49
  5002.1  248.99  5058.4  252.64  5064.5  253.59  5112.4  255.29  5202.2  257.26
  5262.7  257.82  5282.8  257.30  5293.7  256.22  5323.2  255.87  5369.3  256.55
  5374.3  256.11  5464.2  255.68  5544.9  256.23  5575.1  257.38  5751.3  260.65
#Mann=5,-1,0
  4223.7    0.05       0  4863.0     0.1       0  4924.1    0.05       0
  4996.1    0.03       0  5002.1    0.05       0
Bank Sta=4996.1,5002.1
Exp/Cntr=0.3,0.1

Type RM Length L Ch R = 1,866,0,0,0
BEGIN DESCRIPTION:
UNT031 IN NURI 1.0
END DESCRIPTION:
XS GIS Cut Line= 3
      2314007.97     13332023.83      2313195.51     13332263.40
      2313098.35     13333112.42
#Sta/Elev= 30
  4267.6  287.69  4366.8  284.09  4372.1  283.34  4477.2  278.21  4543.8  274.23
  4591.1  270.58  4622.3  269.05  4643.2  267.20  4731.4  261.91  4776.3  259.69
  4820.4  257.33  4826.0  256.42  4897.8  253.68  4924.7  250.47  4956.0  248.86
  4969.7  246.79  4976.8  246.59  4987.2  244.47  4994.7  243.93  4997.4  243.43
  5000.7  243.93  5003.0  244.76  5028.9  247.43  5111.9  251.99  5230.5  254.61
  5319.8  255.26  5500.6  253.25  5691.8  252.99  5845.3  254.16  5969.2  257.29
#Mann=5,-1,0
  4267.6    0.05       0  4731.4     0.1       0  4776.3    0.05       0
  4994.7    0.03       0  5000.7    0.05       0
Bank Sta=4994.7,5000.7
Exp/Cntr=0.3,0.1

Chan Stop Cuts=-1