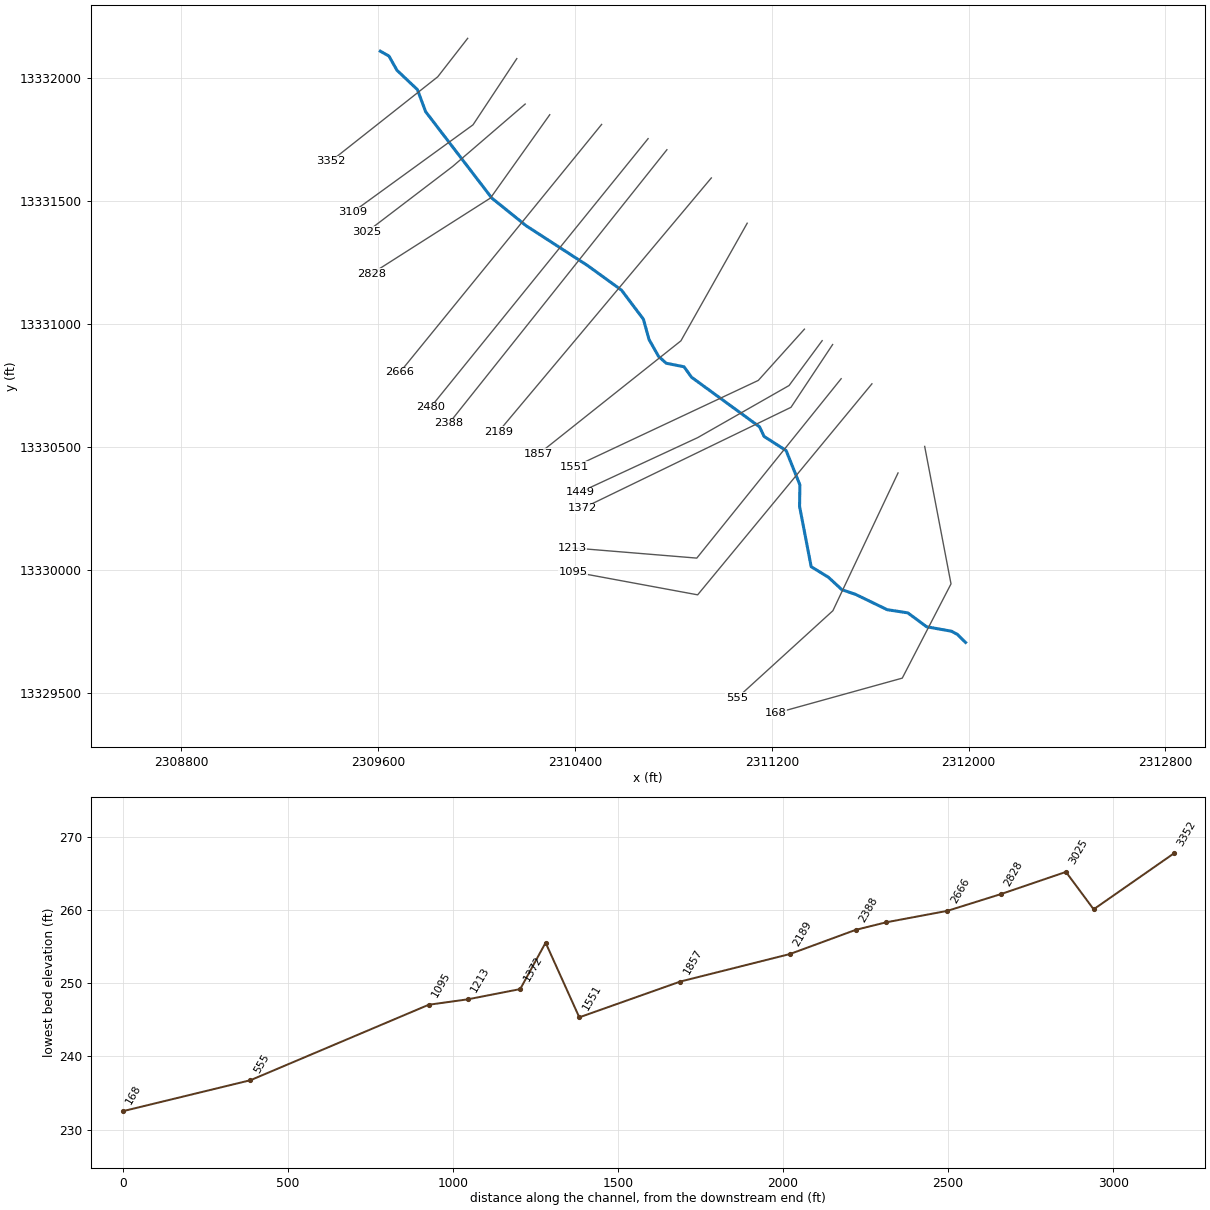
--- UNT032 IN NURI.prj (project) ---

Proj Title=UNT032 IN NURI Base Level Engineering
Current Plan=p01
Default Exp/Contr=0.3,0.1
English Units
Geom File=g01
Flow File=f01
Plan File=p01
Y Axis Title=Elevation
X Axis Title(PF)=Main Channel Distance
X Axis Title(XS)=Station
BEGIN DESCRIPTION:
UNT032 IN NURI
END DESCRIPTION:
DSS Export Rating Curves= 0
DSS Export Rating Curve Sorted= 0
DSS Export Volume Flow Curves= 0
DXF OffsetX= 0
DXF OffsetY= 0
DXF ScaleX= 1
DXF ScaleY= 10

--- UNT032 IN NURI.p01 (plan) ---

Plan Title=Multiple Run
Short Identifier=Multiple
Geom File=g01
Flow File=f01
Subcritical Flow
K Sum by GR= 0
Std Step Tol= 0.01
Critical Tol= 0.01
Num of Std Step Trials= 20
Max Error Tol= 0.3
Flow Tol Ratio= 0.001
Split Flow NTrial= 30
Split Flow Tol= 0.02
Split Flow Ratio= 0.02
Log Output Level= 0
Friction Slope Method= 1
Unsteady Friction Slope Method= 2
Unsteady Bridges Friction Slope Method= 1
Parabolic Critical Depth
Global Vel Dist=  1 , 1 , 1
Global Log Level= 0
CheckData=True
Encroach Param= -1, 0, 0, 0
BEGIN DESCRIPTION:
Multiple Run
END DESCRIPTION:

--- UNT032 IN NURI.f01 (steady flow) ---

Flow Title=Multiple
Number of Profiles=7
Profile Names=10-year,25-year,50-year,1pct_min,100-year,1pct_plu,500-year
River Rch & RM= UNT032 IN NURI,Reach-1,3352
     277     375     454     403     545     737     787
River Rch & RM= UNT032 IN NURI,Reach-1,2388
     387     535     657     591     799    1081    1186
River Rch & RM= UNT032 IN NURI,Reach-1,1095
     602     856    1071     980    1325    1792    2036
Boundary for River Rch & Prof#=UNT032 IN NURI,Reach-1,1
Up Type=0
Dn Type=3
Dn Slope=0.005
Boundary for River Rch & Prof#=UNT032 IN NURI,Reach-1,2
Up Type=0
Dn Type=3
Dn Slope=0.005
Boundary for River Rch & Prof#=UNT032 IN NURI,Reach-1,3
Up Type=0
Dn Type=3
Dn Slope=0.005
Boundary for River Rch & Prof#=UNT032 IN NURI,Reach-1,4
Up Type=0
Dn Type=3
Dn Slope=0.005
Boundary for River Rch & Prof#=UNT032 IN NURI,Reach-1,5
Up Type=0
Dn Type=3
Dn Slope=0.005
Boundary for River Rch & Prof#=UNT032 IN NURI,Reach-1,6
Up Type=0
Dn Type=3
Dn Slope=0.005
Boundary for River Rch & Prof#=UNT032 IN NURI,Reach-1,7
Up Type=0
Dn Type=3
Dn Slope=0.005

--- UNT032 IN NURI.g01 (geometry) ---

Geom Title=Existing Conditions
Program Version=4.10

River Reach=UNT032 IN NURI  ,Reach-1
Reach XY= 30
      2309609.01     13332109.96      2309644.13     13332090.13
      2309676.51     13332032.51      2309759.87     13331953.66
      2309793.05     13331864.32      2310062.04     13331513.08
      2310202.01     13331400.24      2310451.58     13331238.56
      2310589.38     13331138.74      2310678.36     13331020.46
      2310701.14       13330938.      2310739.69     13330869.89
      2310770.89     13330841.74      2310843.29     13330827.32
      2310873.67       13330785.      2311150.36     13330583.18
      2311168.81     13330544.12      2311258.31     13330486.78
      2311314.25     13330347.32      2311312.95     13330260.08
      2311360.11     13330014.85      2311430.38     13329971.74
      2311484.83     13329921.25      2311540.52     13329902.29
      2311669.04     13329840.04      2311752.83     13329827.11
      2311829.32     13329770.71      2311930.59      13329752.4
       2311954.3      13329739.6      2311987.72     13329706.85

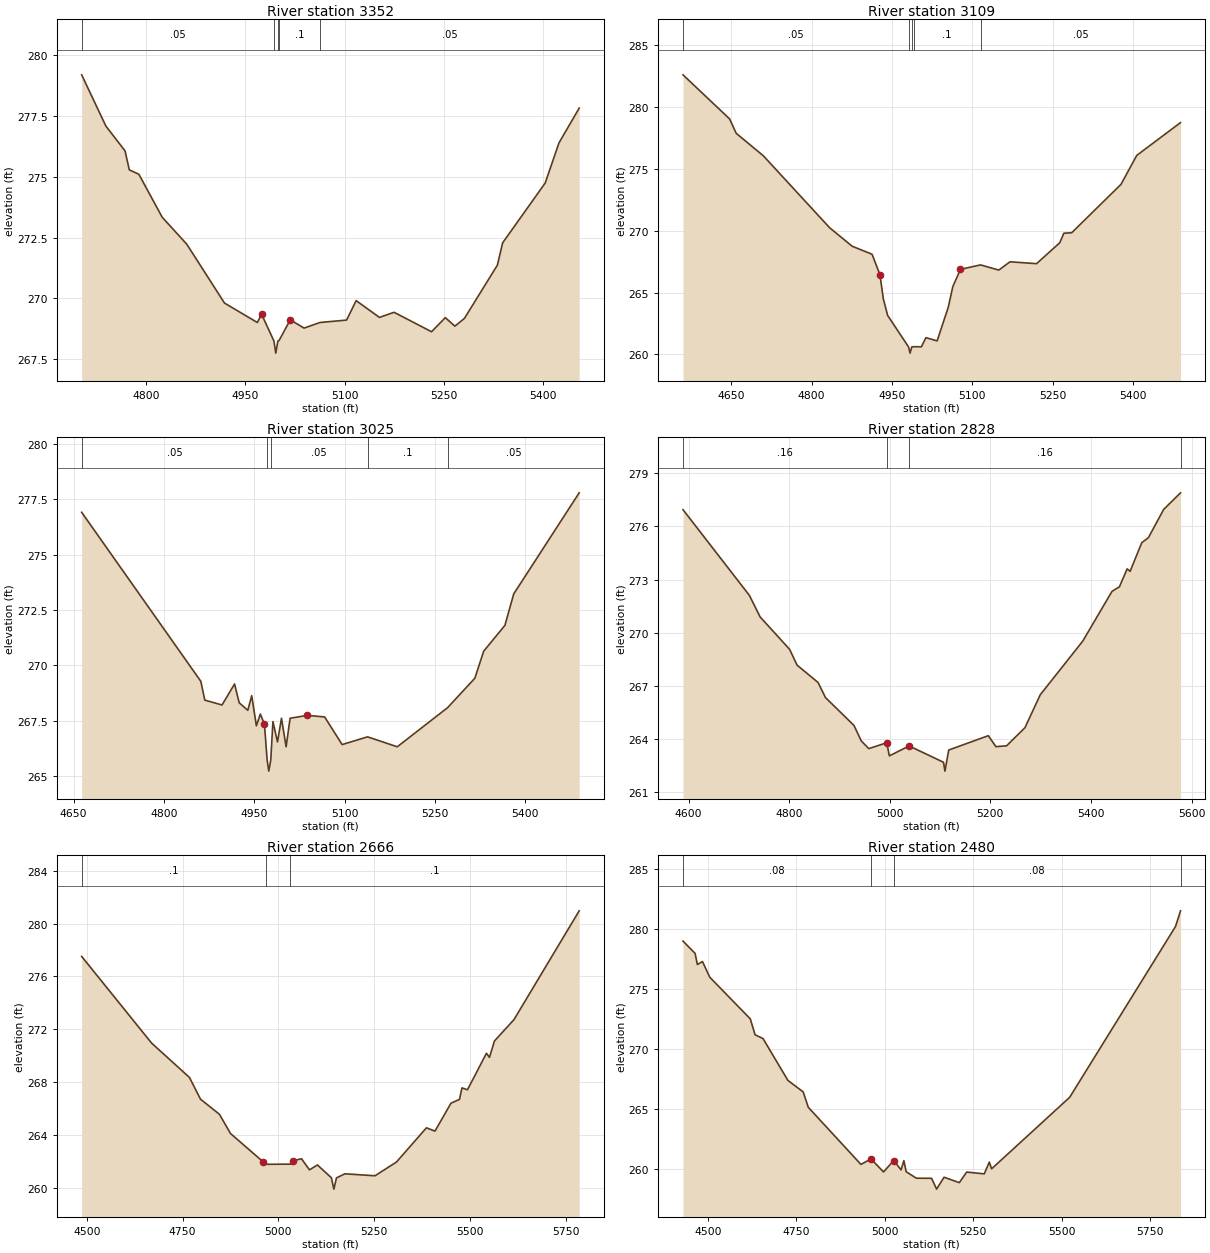
Type RM Length L Ch R = 1 ,3352    ,243,243,243
BEGIN DESCRIPTION:
UNT032 IN NURI 7.0
END DESCRIPTION:
XS GIS Cut Line= 3
      2309964.01     13332162.23       2309842.5       13332006.
       2309408.5     13331663.15
#Sta/Elev= 30
  4703.1   279.2  4739.7  277.09  4768.6  276.07    4775  275.29  4789.4  275.11
  4824.7  273.34  4861.8  272.23  4918.7  269.81  4968.3  269.01  4974.7  269.35
  4993.3  268.25  4996.1  267.75  4999.3  268.25  5001.1  268.27    5018  269.12
  5038.8  268.78  5062.8  269.01    5103  269.11  5117.4  269.91  5152.6  269.22
  5174.7  269.43  5231.2  268.63    5252  269.21  5266.5  268.86  5280.9  269.18
  5330.6  271.37  5338.6  272.29  5402.8  274.75  5423.6   276.4  5454.1  277.83
#Mann= 5 ,-1 , 0
  4703.1     .05       0  4993.3     .03       0  4999.3     .05       0
  5001.1      .1       0  5062.8     .05       0
Bank Sta=4974.7,5018
XS Rating Curve= 0 ,0
Exp/Cntr=0.3,0.1

Type RM Length L Ch R = 1 ,3109    ,84,84,84
BEGIN DESCRIPTION:
Mapping XS ad4e2a23
END DESCRIPTION:
XS GIS Cut Line= 3
      2310163.69      13332079.8      2309985.73     13331810.69
      2309495.29      13331454.8
#Sta/Elev= 30
  4559.9   282.6  4646.8  279.04  4659.3  277.87    4710  276.05  4833.4  270.25
  4875.5  268.75  4912.8   268.1  4927.5  266.44  4933.7  264.52  4941.8  263.16
  4980.9  260.61  4983.7  260.11  4986.9  260.61  4990.4  260.63  5004.8  260.62
  5013.3  261.36  5034.2   261.1    5055  263.82  5063.5  265.49  5077.8  266.88
  5115.3  267.24  5149.3  266.82  5170.2  267.49  5219.8  267.34  5263.1  269.03
  5270.7   269.8  5285.4  269.84  5377.4  273.75  5406.8  276.09  5488.5  278.74
#Mann= 5 ,-1 , 0
  4559.9     .05       0  4980.9     .07       0  4986.9     .05       0
  4990.4      .1       0  5115.3     .05       0
Bank Sta=4927.5,5077.8
XS Rating Curve= 0 ,0
Exp/Cntr=0.3,0.1

Type RM Length L Ch R = 1 ,3025    ,197,197,197
BEGIN DESCRIPTION:
Mapping XS 5623cb06
END DESCRIPTION:
XS GIS Cut Line= 3
      2310197.74     13331895.15      2309902.63     13331641.27
      2309555.44     13331376.53
#Sta/Elev= 30
  4663.5  276.92  4861.3  269.28  4867.9  268.43  4896.5  268.21  4917.3  269.16
    4925  268.31  4939.3  267.97  4945.8  268.63  4953.5  267.27  4960.1   267.8
  4966.9  267.34  4971.4  265.72  4974.1  265.22  4977.4  265.72    4981  267.46
  4988.6  266.54  4995.2  267.61  5002.9  266.32  5009.5  267.61    5038  267.74
  5066.8  267.67  5095.9  266.42  5138.1  266.77  5187.4  266.32    5271  268.09
  5316.2  269.42  5330.8  270.64  5366.1  271.81  5380.7  273.23  5489.4   277.8
#Mann= 5 ,-1 , 0
  4663.5     .05       0  4971.4     .03       0  4977.4     .05       0
  5138.1      .1       0    5271     .05       0
Bank Sta=4966.9,5038
XS Rating Curve= 0 ,0
Exp/Cntr=0.3,0.1

Type RM Length L Ch R = 1 ,2828    ,162,162,162
BEGIN DESCRIPTION:
Mapping XS c503c6c9
END DESCRIPTION:
XS GIS Cut Line= 3
      2310297.62      13331851.8      2310056.71     13331513.23
      2309572.73     13331205.05
#Sta/Elev= 30
  4588.9  276.94    4721   272.1  4742.2  270.89  4800.9  269.06  4815.7  268.17
  4857.5  267.19  4872.2  266.34  4928.8  264.77  4943.5  263.89  4958.3  263.46
    4994  263.79  4999.2  263.05  5038.5  263.61  5106.9  262.69  5109.7  262.19
  5117.3  263.38    5196  264.19  5211.2  263.57  5232.4  263.62  5268.8  264.64
  5299.3   266.5  5383.9  269.53  5441.9  272.33  5456.7  272.59    5472   273.6
  5477.9  273.46  5501.2  275.08  5514.3  275.36  5544.8  276.96  5578.2  277.89
#Mann= 4 ,-1 , 0
  4588.9     .16       0    4994     .07       0  5038.5     .16       0
  5578.2     .05       0
Bank Sta=4994,5038.5
XS Rating Curve= 0 ,0
Exp/Cntr=0.3,0.1

Type RM Length L Ch R = 1 ,2666    ,186,186,186
BEGIN DESCRIPTION:
Mapping XS c503c6c
END DESCRIPTION:
XS GIS Cut Line= 2
      2310508.42     13331812.28        2309689.     13330805.37
#Sta/Elev= 30
  4486.9  277.51  4669.1  270.96  4768.2  268.35  4796.9  266.71  4846.5  265.56
  4875.2  264.11  4959.9  261.98  4967.9  261.78  5031.8  261.79  5038.2  262.04
  5060.5   262.2  5081.3  261.36  5102.1  261.73  5138.5  260.76    5145   259.9
  5151.7  260.75    5174  261.06  5252.3  260.91  5308.3  261.95  5386.5  264.54
  5408.8  264.29  5450.5   266.4  5472.8  266.69  5479.2  267.56  5493.6  267.42
  5543.1  270.18    5551  269.87    5564  271.11    5615  272.73  5785.1  280.96
#Mann= 3 ,-1 , 0
  4486.9      .1       0  4967.9     .07       0  5031.8      .1       0
Bank Sta=4959.9,5038.2
XS Rating Curve= 0 ,0
Exp/Cntr=0.3,0.1

Type RM Length L Ch R = 1 ,2480    ,92,92,92
BEGIN DESCRIPTION:
Mapping XS c805c9d8
END DESCRIPTION:
XS GIS Cut Line= 2
      2310697.36     13331754.58      2309812.77     13330661.86
#Sta/Elev= 30
  4430.1  278.97  4464.3  277.95  4470.7  277.02  4485.1  277.27  4505.9  275.96
  4620.2   272.5  4633.8  271.17  4656.2  270.86  4726.5  267.38  4769.7  266.42
  4784.1  265.14  4932.8  260.39  4961.5  260.84  4996.7  259.76  5025.5  260.71
  5046.3  259.93  5054.2   260.7  5060.7  259.78  5089.4  259.24  5132.6  259.23
  5146.7  258.33  5167.8  259.32  5210.9  258.87  5231.7  259.75  5281.3   259.6
  5295.7  260.58  5302.1  260.02  5522.7  265.97  5821.7  280.18    5836  281.49
#Mann= 4 ,-1 , 0
  4430.1     .08       0  4961.5     .06       0  5025.5     .08       0
    5836     .07       0
Bank Sta=4961.5,5025.5
XS Rating Curve= 0 ,0
Exp/Cntr=0.3,0.1

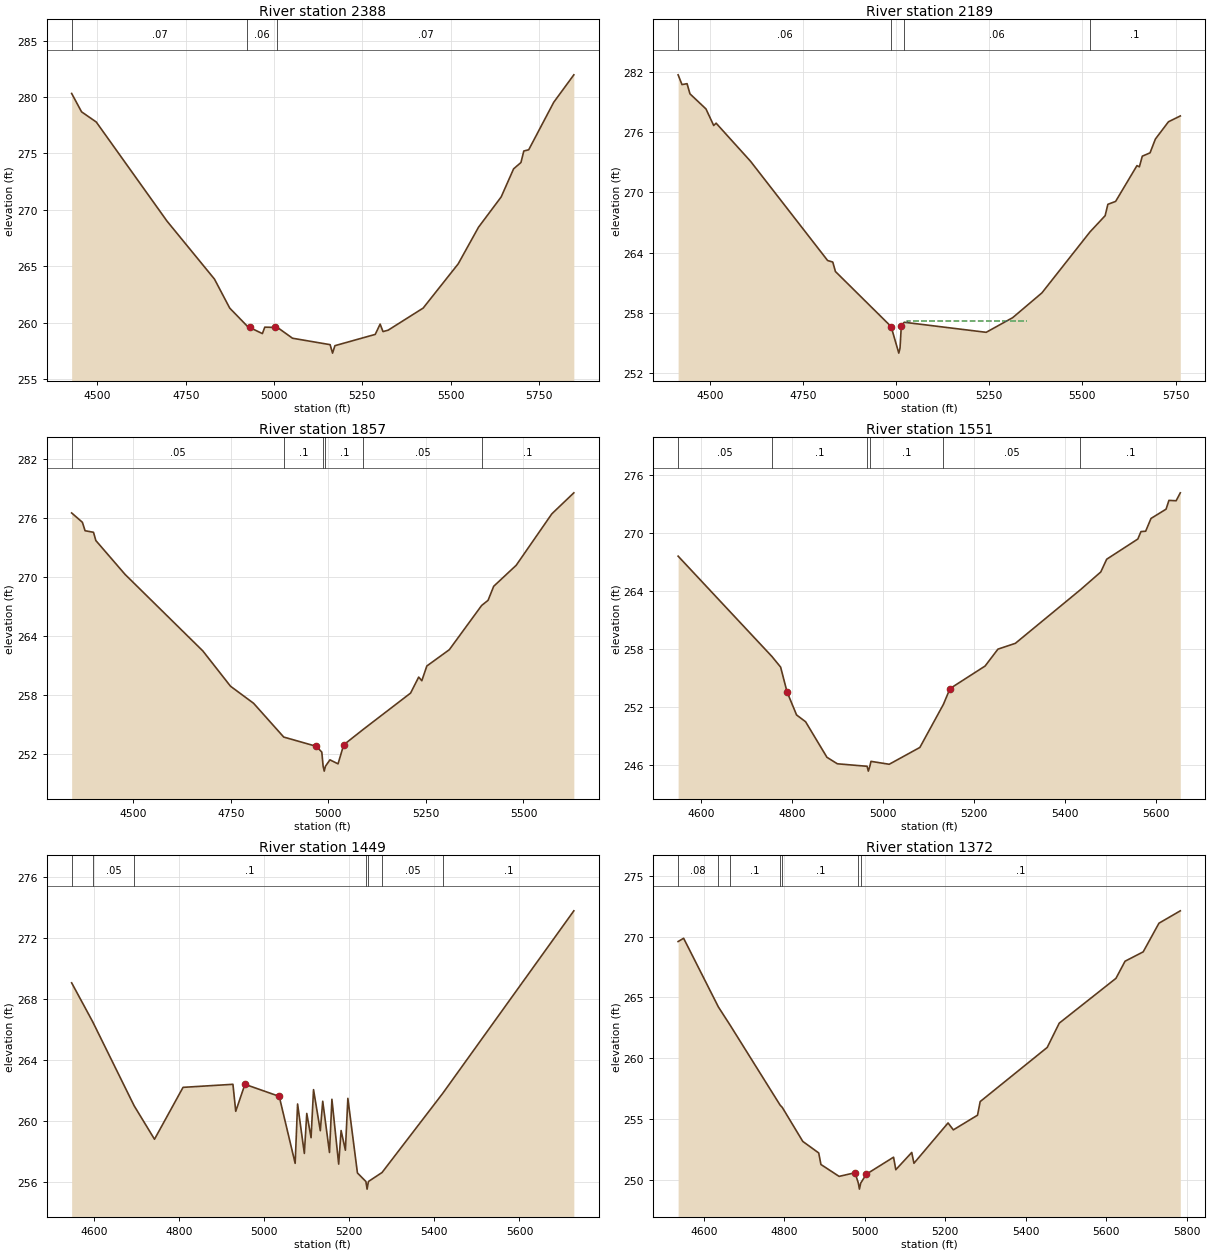
Type RM Length L Ch R = 1 ,2388    ,199,199,199
BEGIN DESCRIPTION:
UNT032 IN NURI 5.0
END DESCRIPTION:
XS GIS Cut Line= 2
      2310773.75     13331709.44      2309887.71     13330596.85
#Sta/Elev= 30
  4426.9  280.31    4455  278.68  4496.6  277.78  4696.9     269  4831.4  263.86
  4874.6  261.29  4924.3  259.69  4930.7  259.58  4967.1  259.03  4973.9   259.6
  5002.8  259.58  5009.2  259.59  5052.4  258.62  5158.9  258.05  5165.9   257.3
  5172.5  257.96  5286.7  258.96  5300.6  259.87  5308.7  259.21  5323.1  259.33
  5422.4  261.29  5521.7  265.21  5579.3  268.46  5643.4  271.14  5678.6  273.63
  5699.4  274.19  5707.5  275.21  5721.4  275.32  5792.3  279.53  5849.2  281.96
#Mann= 3 ,-1 , 0
  4426.9     .07       0  4924.3     .06       0  5009.2     .07       0
#XS Ineff= 1 ,-1
 5009.27 5406.65259.5881
Permanent Ineff=
       F
Bank Sta=4930.7,5002.8
XS Rating Curve= 0 ,0
Exp/Cntr=0.3,0.1

Type RM Length L Ch R = 1 ,2189    ,332,332,332
BEGIN DESCRIPTION:
UNT032 IN NURI 4.1
END DESCRIPTION:
XS GIS Cut Line= 2
      2310954.28     13331594.83       2310088.3      13330562.3
#Sta/Elev= 30
  4415.1  281.68  4425.5  280.71  4439.1   280.8  4446.9  279.79  4489.8  278.29
  4510.6  276.64  4517.1  276.87  4609.5  273.08  4816.3  263.21  4830.1  263.06
  4837.2  262.12  4986.7  256.64  5007.3     254  5010.6   254.5  5014.1  256.74
  5021.9  257.07  5241.8  256.07    5313  257.53  5391.3  259.99  5520.2  266.05
    5561  267.67  5568.3   268.8  5589.1  269.09  5646.4  272.65  5652.9  272.53
  5660.7  273.59  5681.5  273.92  5695.8  275.29  5730.9  277.01  5762.7  277.59
#Mann= 4 ,-1 , 0
  4415.1     .06       0  4986.7     .04       0  5021.9     .06       0
  5520.2      .1       0
#XS Ineff= 1 ,-1
  5029.3 5351.29  257.24
Permanent Ineff=
       F
Bank Sta=4986.7,5014.1
XS Rating Curve= 0 ,0
Exp/Cntr=0.3,0.1

Type RM Length L Ch R = 1 ,1857    ,306,306,306
BEGIN DESCRIPTION:
UNT032 IN NURI 4.0
END DESCRIPTION:
XS GIS Cut Line= 3
      2311100.14     13331410.84      2310830.64     13330932.69
      2310252.89      13330473.3
#Sta/Elev= 30
  4342.1  276.54  4369.6  275.59  4376.5  274.73  4398.1  274.57  4404.1  273.73
    4479  270.28  4678.4  262.48  4749.2  258.89  4808.4  257.15  4885.6  253.71
  4968.8  252.77  4983.2  252.18  4986.6  250.74  4989.4  250.24  4992.6  250.74
    5004  251.39  5024.8  250.98  5039.3  252.92    5090  254.51  5210.7  258.19
  5231.5  259.82  5239.5  259.45  5252.4  260.95    5310  262.61  5392.7  267.11
  5409.3  267.64  5423.7  269.07  5481.4  271.21  5572.7  276.45  5629.1  278.59
#Mann= 6 ,-1 , 0
  4342.1     .05       0  4885.6      .1       0  4986.6     .07       0
  4992.6      .1       0    5090     .05       0  5392.7      .1       0
Bank Sta=4968.8,5039.3
XS Rating Curve= 0 ,0
Exp/Cntr=0.3,0.1

Type RM Length L Ch R = 1 ,1551    ,102,102,102
BEGIN DESCRIPTION:
Mapping XS f6fb8ec5
END DESCRIPTION:
XS GIS Cut Line= 3
      2311332.73     13330980.22      2311145.25     13330771.91
       2310399.4     13330421.53
#Sta/Elev= 30
  4549.3  267.59  4755.8   257.2  4774.7  256.11  4788.9  253.54  4809.8  251.16
  4829.6  250.46  4876.6  246.78  4899.4  246.11  4964.9  245.85  4967.6  245.35
  4970.9  245.85  4973.4  246.36  5013.5  246.06  5080.9   247.8  5132.7  252.26
  5147.2  253.89  5224.3  256.22  5252.6  257.97  5290.9  258.57  5434.1  264.12
  5478.7  265.95  5491.7  267.27  5560.2  269.36  5567.1  270.13  5577.4  270.17
  5589.2  271.49  5622.3  272.45  5628.6  273.36  5644.4  273.32  5653.6  274.14
#Mann= 6 ,-1 , 0
  4549.3     .05       0  4755.8      .1       0  4964.9     .07       0
  4970.9      .1       0  5132.7     .05       0  5434.1      .1       0
Bank Sta=4788.9,5147.2
XS Rating Curve= 0 ,0
Exp/Cntr=0.3,0.1

Type RM Length L Ch R = 1 ,1449    ,77,77,77
BEGIN DESCRIPTION:
UNT032 IN NURI 3.0
END DESCRIPTION:
XS GIS Cut Line= 4
      2311404.83     13330933.41      2311270.25     13330751.08
      2310898.86     13330539.35      2310421.16     13330317.79
#Sta/Elev= 30
  4547.2  269.07  4596.5  266.53    4694  261.02    4742  258.82  4809.1  262.22
  4926.4  262.42    4933  260.65  4954.6  262.42  5035.2  261.63  5072.7  257.24
  5078.4  261.13  5094.3  257.89    5100  260.51  5110.1  258.92  5115.9  262.07
  5131.8  259.38  5137.5  261.31  5153.4  257.95  5159.1  261.44    5175  257.19
  5180.7  259.39  5190.8   258.1  5196.6   261.5  5219.1  256.61    5239  256.05
  5241.8  255.55    5245  256.05    5277  256.64    5420  261.84  5727.9  273.79
#Mann= 7 ,-1 , 0
  4547.2     .08       0  4596.5     .05       0    4694      .1       0
    5239     .07       0    5245      .1       0    5277     .05       0
    5420      .1       0
Bank Sta=4954.6,5035.2
XS Rating Curve= 0 ,0
Exp/Cntr=0.3,0.1

Type RM Length L Ch R = 1 ,1372    ,159,159,159
BEGIN DESCRIPTION:
Mapping XS f45cdf57
END DESCRIPTION:
XS GIS Cut Line= 3
      2311447.32     13330917.71      2311278.06     13330662.53
      2310429.93     13330251.48
#Sta/Elev= 30
  4535.9   269.6  4549.6  269.87  4636.1  264.21  4665.3  262.71  4789.7  256.12
  4794.9  255.94  4845.9  253.14  4885.5  252.19    4891  251.24  4936.2  250.26
  4975.8  250.56    4984  249.71  4986.7  249.21    4990  249.71  5003.9  250.44
  5071.6  251.84  5077.2  250.81  5116.8  252.23  5122.3  251.34  5207.1  254.66
  5220.3  254.09  5280.4   255.3    5287  256.42  5453.7  260.88  5483.6  262.88
  5624.6  266.57  5647.2  267.98  5692.3  268.75  5731.5  271.11  5784.6  272.13
#Mann= 7 ,-1 , 0
  4535.9     .08       0  4636.1     .05       0  4665.3      .1       0
  4789.7     .08       0  4794.9      .1       0    4984     .07       0
    4990      .1       0
Bank Sta=4975.8,5003.9
XS Rating Curve= 0 ,0
Exp/Cntr=0.3,0.1

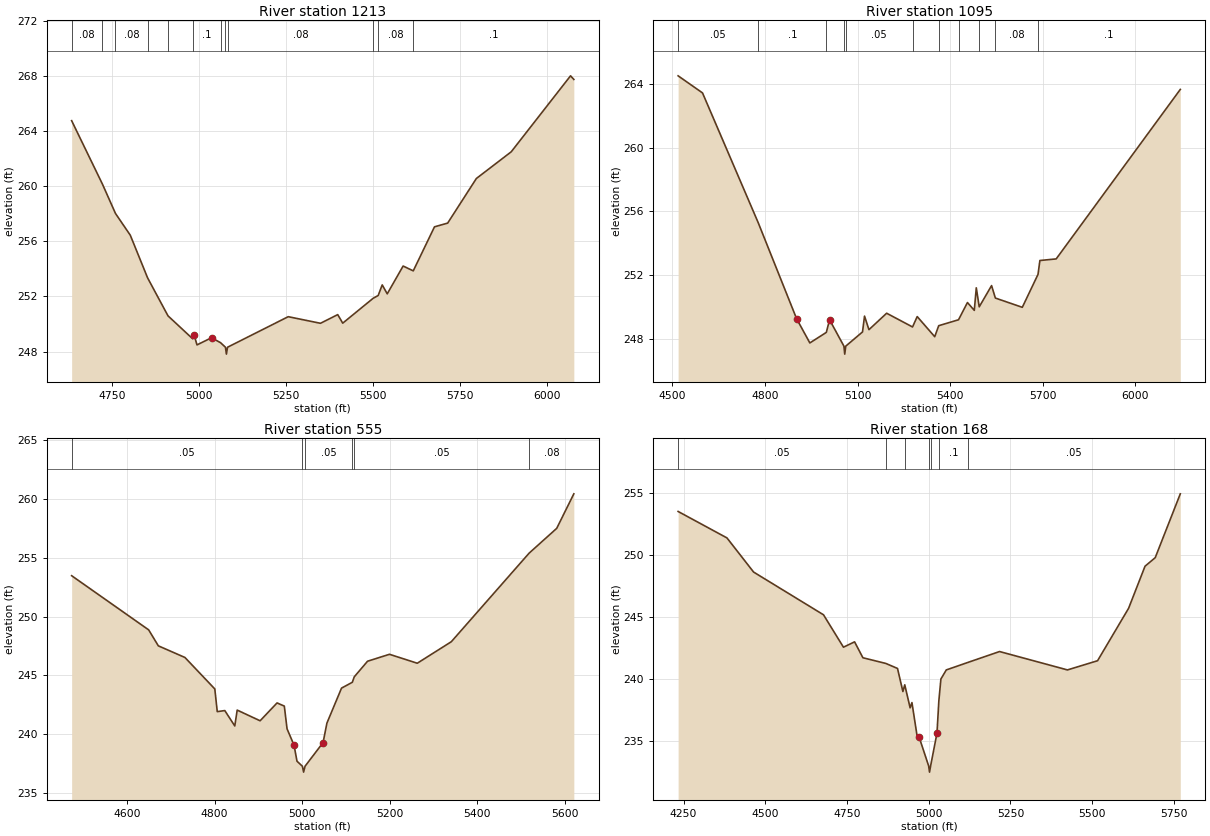
Type RM Length L Ch R = 1 ,1213    ,118,118,118
BEGIN DESCRIPTION:
Mapping XS a35373e4
END DESCRIPTION:
XS GIS Cut Line= 3
      2311482.03     13330778.82      2310895.25     13330049.69
      2310388.28     13330091.36
#Sta/Elev= 30
  4632.9  264.77  4721.5  260.16    4759  258.03  4801.6  256.45  4851.4  253.35
  4910.1  250.59  4981.2  248.92  4985.6  249.17  4993.5  248.48  5035.2     249
  5061.3  248.64  5075.3  248.31  5078.1  247.81  5081.3  248.31  5255.9  250.53
  5348.7  250.05  5398.3  250.68  5412.7  250.06  5500.4  251.87  5514.7  252.07
  5526.3  252.84  5540.7  252.19  5586.4  254.21  5615.6  253.86  5676.7  257.06
  5714.6  257.33  5797.1  260.57  5897.4  262.51    6068  268.03  6077.5  267.77
#Mann= 12 ,-1 , 0
  4632.9     .08       0  4721.5     .05       0    4759     .08       0
  4851.4      .1       0  4910.1     .08       0  4981.2      .1       0
  5061.3     .08       0  5075.3     .07       0  5081.3     .08       0
  5500.4      .1       0  5514.7     .08       0  5615.6      .1       0
Bank Sta=4985.6,5035.2
XS Rating Curve= 0 ,0
Exp/Cntr=0.3,0.1

Type RM Length L Ch R = 1 ,1095    ,540,540,540
BEGIN DESCRIPTION:
Mapping XS b7599a29
END DESCRIPTION:
XS GIS Cut Line= 3
      2311607.07     13330758.04      2310898.72     13329900.38
      2310392.27     13329994.04
#Sta/Elev= 30
  4518.3  264.49  4597.4  263.42  4777.8   255.3  4902.2  249.29  4945.2  247.77
  4998.6  248.43  5009.1  249.22  5055.6  247.57  5058.3  247.07  5061.6  247.57
  5115.9  248.46  5122.4  249.45  5136.7   248.6  5194.1  249.63    5278  248.77
  5293.1  249.42  5349.9  248.16  5362.8  248.85    5427  249.22  5455.9   250.3
  5478.1  249.81  5484.6  251.22  5494.1  250.03  5534.1  251.36  5546.4  250.58
  5633.7     250  5684.6  252.06  5690.7  252.93  5743.5  253.03  6145.7  263.64
#Mann= 11 ,-1 , 0
  4518.3     .05       0  4777.8      .1       0  4998.6     .05       0
  5055.6     .03       0  5061.6     .05       0    5278      .1       0
  5362.8     .05       0    5427      .1       0  5494.1     .05       0
  5546.4     .08       0  5684.6      .1       0
Bank Sta=4902.2,5009.1
XS Rating Curve= 0 ,0
Exp/Cntr=0.3,0.1

Type RM Length L Ch R = 1 ,555     ,387,387,387
BEGIN DESCRIPTION:
Mapping XS ec2a408a
END DESCRIPTION:
XS GIS Cut Line= 3
      2311713.17     13330395.79       2311448.4     13329835.87
      2311058.82     13329480.92
#Sta/Elev= 30
  4473.8  253.48  4649.6  248.87  4671.7  247.51  4732.4  246.52  4800.6  243.84
  4806.2  241.91  4823.4     242  4846.2  240.69  4851.7  242.04    4904  241.13
  4942.7  242.65  4959.3  242.38  4965.5  240.45  4981.5  239.05  4988.2  237.69
  5000.6  237.26  5003.3  236.76  5006.6  237.26  5047.8  239.28  5056.5  240.93
  5089.9  243.91  5114.6  244.41  5118.9  244.87  5149.3   246.2  5199.3  246.79
  5262.8  246.03  5340.5  247.86  5518.1   255.4  5581.1  257.51  5620.2  260.45
#Mann= 6 ,-1 , 0
  4473.8     .05       0  5000.6     .03       0  5006.6     .05       0
  5114.6      .1       0  5118.9     .05       0  5518.1     .08       0
Bank Sta=4981.5,5047.8
XS Rating Curve= 0 ,0
Exp/Cntr=0.3,0.1

Type RM Length L Ch R = 1 ,168     ,0,0,0
BEGIN DESCRIPTION:
UNT032 IN NURI 1.0
END DESCRIPTION:
XS GIS Cut Line= 4
      2311821.47     13330503.63      2311928.49     13329944.93
      2311730.32     13329561.84      2311213.79      13329418.6
#Sta/Elev= 30
  4233.3  253.51  4382.7  251.38  4464.2  248.63    4678  245.19  4739.1  242.58
  4773.1  243.01  4798.6  241.73  4868.9  241.27  4904.4  240.87  4920.9  239.01
  4926.6  239.55    4943   237.7  4948.6  238.12  4965.2  235.29  4970.8  235.32
  4999.7  233.02  5002.4  232.52  5005.7  233.02  5025.2  235.66  5030.9  238.26
  5037.2  240.02  5053.7  240.75  5119.4  241.35  5216.6  242.23  5424.3  240.75
  5516.4  241.49  5611.3  245.71  5661.6   249.1  5692.8  249.79  5769.5  254.93
#Mann= 7 ,-1 , 0
  4233.3     .05       0  4868.9      .1       0  4926.6     .05       0
  4999.7     .03       0  5005.7     .05       0  5030.9      .1       0
  5119.4     .05       0
Bank Sta=4970.8,5025.2
XS Rating Curve= 0 ,0
Exp/Cntr=0.3,0.1

Chan Stop Cuts=-1
Use User Specified Reach Order=0
Composite Channel Slope=5