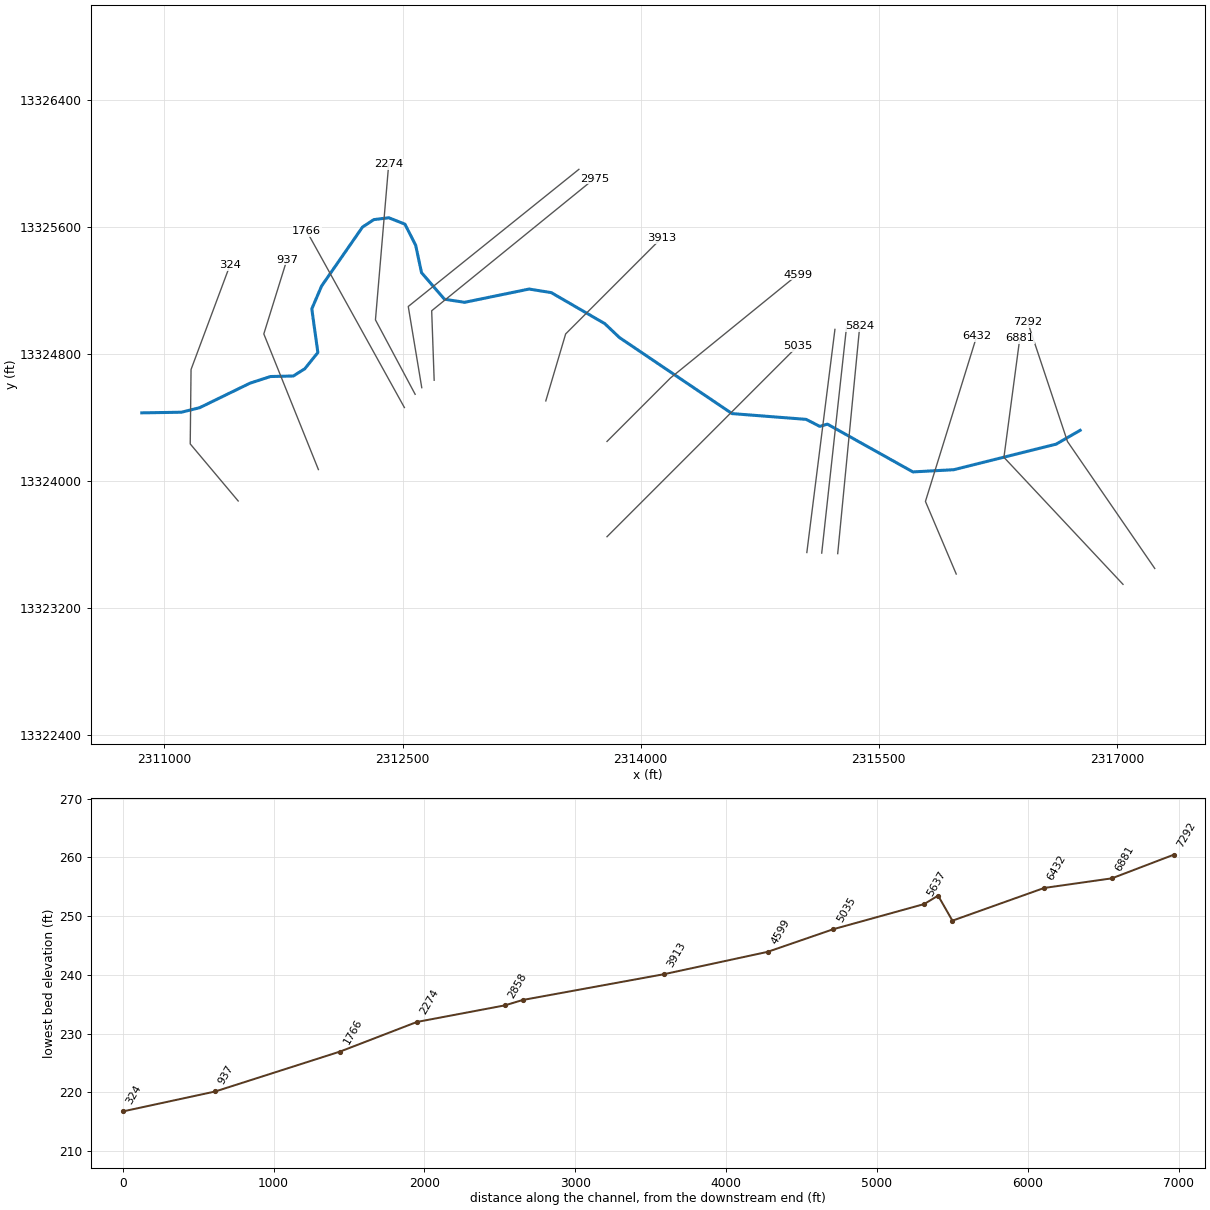
--- UNT033 IN NURI.prj (project) ---

Proj Title=UNT033 IN NURI Base Level Engineering
Current Plan=p01
Default Exp/Contr=0.3,0.1
English Units
Geom File=g01
Flow File=f01
Plan File=p01
BEGIN DESCRIPTION:
UNT033 IN NURI
END DESCRIPTION:

--- UNT033 IN NURI.p01 (plan) ---

Plan Title=Multiple Run
Short Identifier=Multiple
Geom File=g01
Flow File=f01
Subcritical Flow
K Sum by GR= 0
Std Step Tol= 0.01
Critical Tol= 0.01
Num of Std Step Trials= 20
Max Error Tol= 0.3
Flow Tol Ratio= 0.001
Split Flow NTrial= 30
Split Flow Tol= 0.02
Split Flow Ratio= 0.02
Log Output Level= 0
Friction Slope Method= 1
Unsteady Friction Slope Method= 2
Unsteady Bridges Friction Slope Method= 1
Parabolic Critical Depth
Global Vel Dist=  1 , 1 , 1
Global Log Level= 0
CheckData=True
Encroach Param= -1, 0, 0, 0
BEGIN DESCRIPTION:
Multiple Run
END DESCRIPTION:

--- UNT033 IN NURI.f01 (steady flow) ---

Flow Title=Multiple
Number of Profiles=7
Profile Names=10-year,25-year,50-year,1pct_min,100-year,1pct_plu,500-year
River Rch & RM= UNT033 IN NURI,Reach-1,7292
     970    1412    1795    1665    2251    3044    3556
River Rch & RM= UNT033 IN NURI,Reach-1,2858
    1021    1489    1895    1758    2378    3216    3762
Boundary for River Rch & Prof#=UNT033 IN NURI,Reach-1,1
Up Type=0
Dn Type=3
Dn Slope=0.005
Boundary for River Rch & Prof#=UNT033 IN NURI,Reach-1,2
Up Type=0
Dn Type=3
Dn Slope=0.005
Boundary for River Rch & Prof#=UNT033 IN NURI,Reach-1,3
Up Type=0
Dn Type=3
Dn Slope=0.005
Boundary for River Rch & Prof#=UNT033 IN NURI,Reach-1,4
Up Type=0
Dn Type=3
Dn Slope=0.005
Boundary for River Rch & Prof#=UNT033 IN NURI,Reach-1,5
Up Type=0
Dn Type=3
Dn Slope=0.005
Boundary for River Rch & Prof#=UNT033 IN NURI,Reach-1,6
Up Type=0
Dn Type=3
Dn Slope=0.005
Boundary for River Rch & Prof#=UNT033 IN NURI,Reach-1,7
Up Type=0
Dn Type=3
Dn Slope=0.005

--- UNT033 IN NURI.g01 (geometry) ---

Geom Title=Existing Conditions

River Reach=UNT033 IN NURI,Reach-1
Reach XY= 30
      2316767.72     13324316.85      2316616.49     13324229.82
      2315971.98     13324068.80      2315714.41     13324054.99
      2315175.90     13324355.86      2315128.20     13324341.60
      2315041.72     13324385.92      2314575.14     13324422.20
      2313865.04     13324901.83      2313773.76     13324988.70
      2313436.60     13325184.17      2313296.97     13325206.57
      2312890.74     13325123.00      2312763.79     13325142.53
      2312619.47     13325309.63      2312582.70     13325482.04
      2312514.99     13325615.38      2312412.81     13325655.58
      2312318.96     13325643.89      2312247.72     13325596.93
      2311990.21     13325225.82      2311928.38     13325081.65
      2311966.54     13324806.81      2311884.09     13324704.48
      2311811.98     13324659.02      2311667.92     13324655.65
      2311538.99     13324613.72      2311222.10     13324459.45
      2311107.03     13324430.91      2310857.72     13324426.85

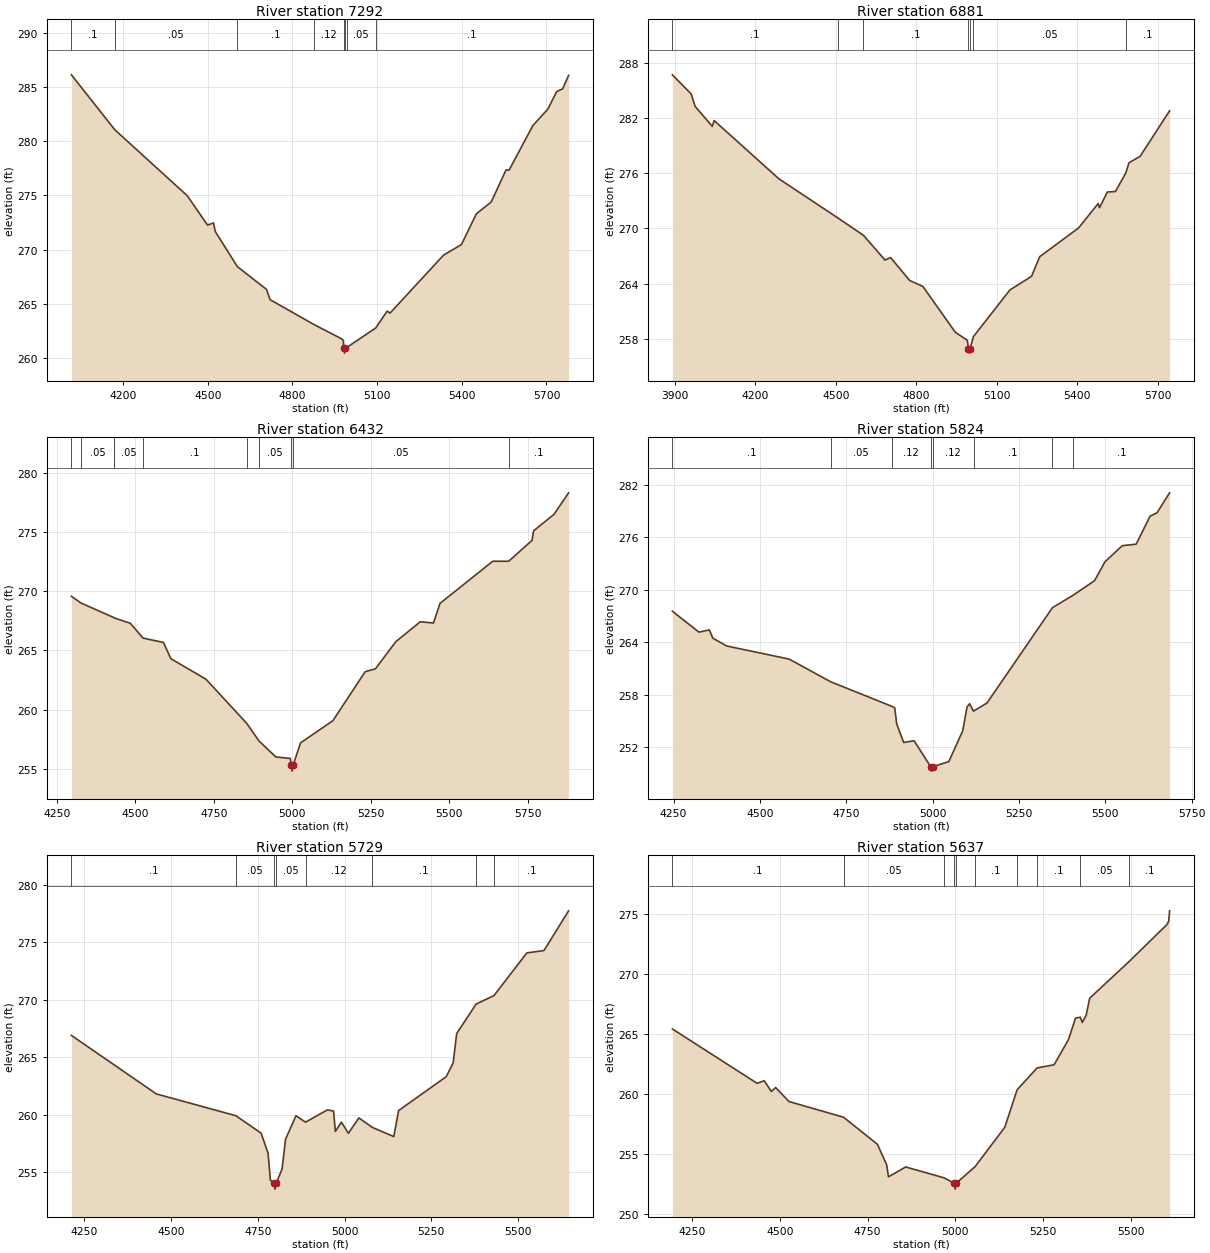
Type RM Length L Ch R = 1,7292,411,411,411
BEGIN DESCRIPTION:
UNT033 IN NURI 9.0
END DESCRIPTION:
XS GIS Cut Line= 3
      2317237.72     13323446.86      2316687.72     13324246.85
      2316437.72     13324996.87
#Sta/Elev= 30
  4017.0  286.12  4170.7  281.06  4427.7  274.97  4499.4  272.27  4520.3  272.47
  4526.7  271.68  4605.0  268.44  4708.4  266.34  4720.8  265.40  4875.2  263.12
  4974.3  261.79  4980.4  261.65  4981.8  260.97  4984.5  260.47  4987.8  260.97
  4992.0  260.98  5095.1  262.79  5135.4  264.34  5145.9  264.16  5335.7  269.51
  5398.9  270.48  5451.6  273.31  5504.3  274.40  5557.0  277.37  5567.6  277.34
  5651.9  281.45  5704.6  282.95  5736.2  284.58  5757.3  284.83  5778.4  286.07
#Mann=8,-1,0
  4017.0     0.1       0  4170.7    0.05       0  4605.0     0.1       0
  4875.2    0.12       0  4981.8    0.03       0  4987.8    0.12       0
  4992.0    0.05       0  5095.1     0.1       0
Bank Sta=4981.8,4987.8
Exp/Cntr=0.3,0.1

Type RM Length L Ch R = 1,6881,449,449,449
BEGIN DESCRIPTION:
UNT033 IN NURI 8.0
END DESCRIPTION:
XS GIS Cut Line= 3
      2317037.69     13323346.89      2316287.72     13324146.85
      2316387.72     13324896.88
#Sta/Elev= 30
  3891.2  286.70  3961.7  284.61  3975.9  283.27  4039.9  281.10  4046.7  281.73
  4287.5  275.41  4507.5  271.15  4603.3  269.25  4683.7  266.56  4704.7  266.83
  4775.5  264.34  4824.9  263.69  4945.5  258.72  4990.3  257.84  4994.8  256.94
  4997.6  256.44  5000.8  256.94  5013.1  258.23  5149.2  263.31  5229.9  264.79
  5260.1  266.92  5405.2  270.05  5478.3  272.71  5483.3  272.25  5512.3  273.96
  5542.6  274.01  5581.1  276.03  5593.0  277.14  5634.7  277.84  5744.4  282.79
#Mann=7,-1,0
  3891.2     0.1       0  4507.5    0.05       0  4603.3     0.1       0
  4994.8    0.07       0  5000.8     0.1       0  5013.1    0.05       0
  5581.1     0.1       0
Bank Sta=4994.8,5000.8
Exp/Cntr=0.3,0.1

Type RM Length L Ch R = 1,6432,608,608,608
BEGIN DESCRIPTION:
UNT033 IN NURI 7.0
END DESCRIPTION:
XS GIS Cut Line= 3
      2315987.28     13323411.76      2315793.29     13323869.14
      2316115.74     13324908.35
#Sta/Elev= 30
  4296.1  269.57  4326.8  269.00  4432.4  267.76  4432.8  267.74  4484.0  267.29
  4524.5  266.04  4589.5  265.67  4613.2  264.30  4725.3  262.56  4855.4  258.82
  4894.0  257.35  4947.6  256.00  4994.1  255.87  4996.9  255.30  4999.7  254.80
  5002.9  255.30  5026.6  257.19  5129.6  259.06  5232.6  263.20  5265.2  263.44
  5330.3  265.74  5408.3  267.42  5450.2  267.31  5471.1  268.97  5639.2  272.53
  5690.0  272.53  5764.3  274.29  5769.5  275.10  5834.7  276.50  5881.0  278.31
#Mann=10,-1,0
  4296.1     0.1       0  4326.8    0.05       0  4432.4     0.1       0
  4432.8    0.05       0  4524.5     0.1       0  4855.4    0.12       0
  4894.0    0.05       0  4996.9    0.03       0  5002.9    0.05       0
  5690.0     0.1       0
Bank Sta=4996.9,5002.9
Exp/Cntr=0.3,0.1

Type RM Length L Ch R = 1,5824,95,95,95
BEGIN DESCRIPTION:
UNT033 IN NURI 6.0
END DESCRIPTION:
XS GIS Cut Line= 2
      2315240.74     13323540.31      2315379.51     13324973.11
#Sta/Elev= 30
  4246.6  267.54  4323.5  265.15  4353.6  265.40  4363.7  264.46  4403.9  263.56
  4584.7  262.06  4704.9  259.46  4882.1  256.65  4890.3  256.49  4896.2  254.61
  4916.3  252.51  4946.4  252.71  4994.5  249.73  4997.2  249.23  5000.5  249.73
  5046.9  250.32  5087.1  253.84  5099.6  256.56  5107.1  256.95  5118.4  256.10
  5157.4  257.03  5347.0  267.95  5406.3  269.36  5468.8  271.04  5499.0  273.20
  5549.2  275.05  5589.4  275.22  5629.6  278.43  5649.7  278.81  5686.1  281.10
#Mann=8,-1,0
  4246.6     0.1       0  4704.9    0.05       0  4882.1    0.12       0
  4994.5    0.07       0  5000.5    0.12       0  5118.4     0.1       0
  5347.0    0.05       0  5406.3     0.1       0
Bank Sta=4994.5,5000.5
Exp/Cntr=0.3,0.1

Type RM Length L Ch R = 1,5729,92,92,92
BEGIN DESCRIPTION:
UNT033 IN NURI 5.0
END DESCRIPTION:
XS GIS Cut Line= 2
      2315140.04     13323543.70      2315296.29     13324967.35
#Sta/Elev= 30
  4213.3  266.90  4457.9  261.80  4687.1  259.90  4759.7  258.38  4779.8  256.63
  4786.4  254.29  4797.0  254.00  4799.7  253.50  4803.0  254.00  4820.1  255.25
  4830.1  257.85  4860.3  259.90  4887.8  259.34  4950.9  260.41  4968.5  260.30
  4973.6  258.53  4991.1  259.34  5011.2  258.37  5041.4  259.71  5080.2  258.88
  5142.0  258.08  5155.8  260.35  5292.9  263.30  5313.0  264.50  5323.1  267.06
  5379.1  269.63  5430.4  270.37  5525.2  274.09  5574.6  274.30  5645.5  277.76
#Mann=8,-1,0
  4213.3     0.1       0  4687.1    0.05       0  4797.0    0.07       0
  4803.0    0.05       0  4887.8    0.12       0  5080.2     0.1       0
  5379.1    0.05       0  5430.4     0.1       0
Bank Sta=4797,4803
Exp/Cntr=0.3,0.1

Type RM Length L Ch R = 1,5637,602,602,602
BEGIN DESCRIPTION:
Mapping XS 70668db2
END DESCRIPTION:
XS GIS Cut Line= 2
      2315046.30     13323547.25      2315223.27     13324952.65
#Sta/Elev= 30
  4193.7  265.43  4435.2  260.89  4455.4  261.11  4475.5  260.21  4487.9  260.54
  4525.9  259.37  4681.5  258.06  4777.9  255.80  4804.2  254.09  4809.3  253.09
  4858.5  253.91  4968.0  253.00  4996.6  252.56  4999.4  252.06  5002.6  252.56
  5056.2  253.94  5140.7  257.22  5175.8  260.35  5232.8  262.18  5281.2  262.44
  5322.1  264.54  5342.3  266.34  5355.9  266.41  5361.5  265.97  5372.5  266.57
  5382.6  268.00  5494.6  271.05  5602.5  274.14  5607.6  274.42  5610.2  275.29
#Mann=10,-1,0
  4193.7     0.1       0  4681.5    0.05       0  4968.0    0.12       0
  4996.6    0.07       0  5002.6    0.12       0  5056.2     0.1       0
  5175.8    0.05       0  5232.8     0.1       0  5355.9    0.05       0
  5494.6     0.1       0
Bank Sta=4996.6,5002.6
Exp/Cntr=0.3,0.1

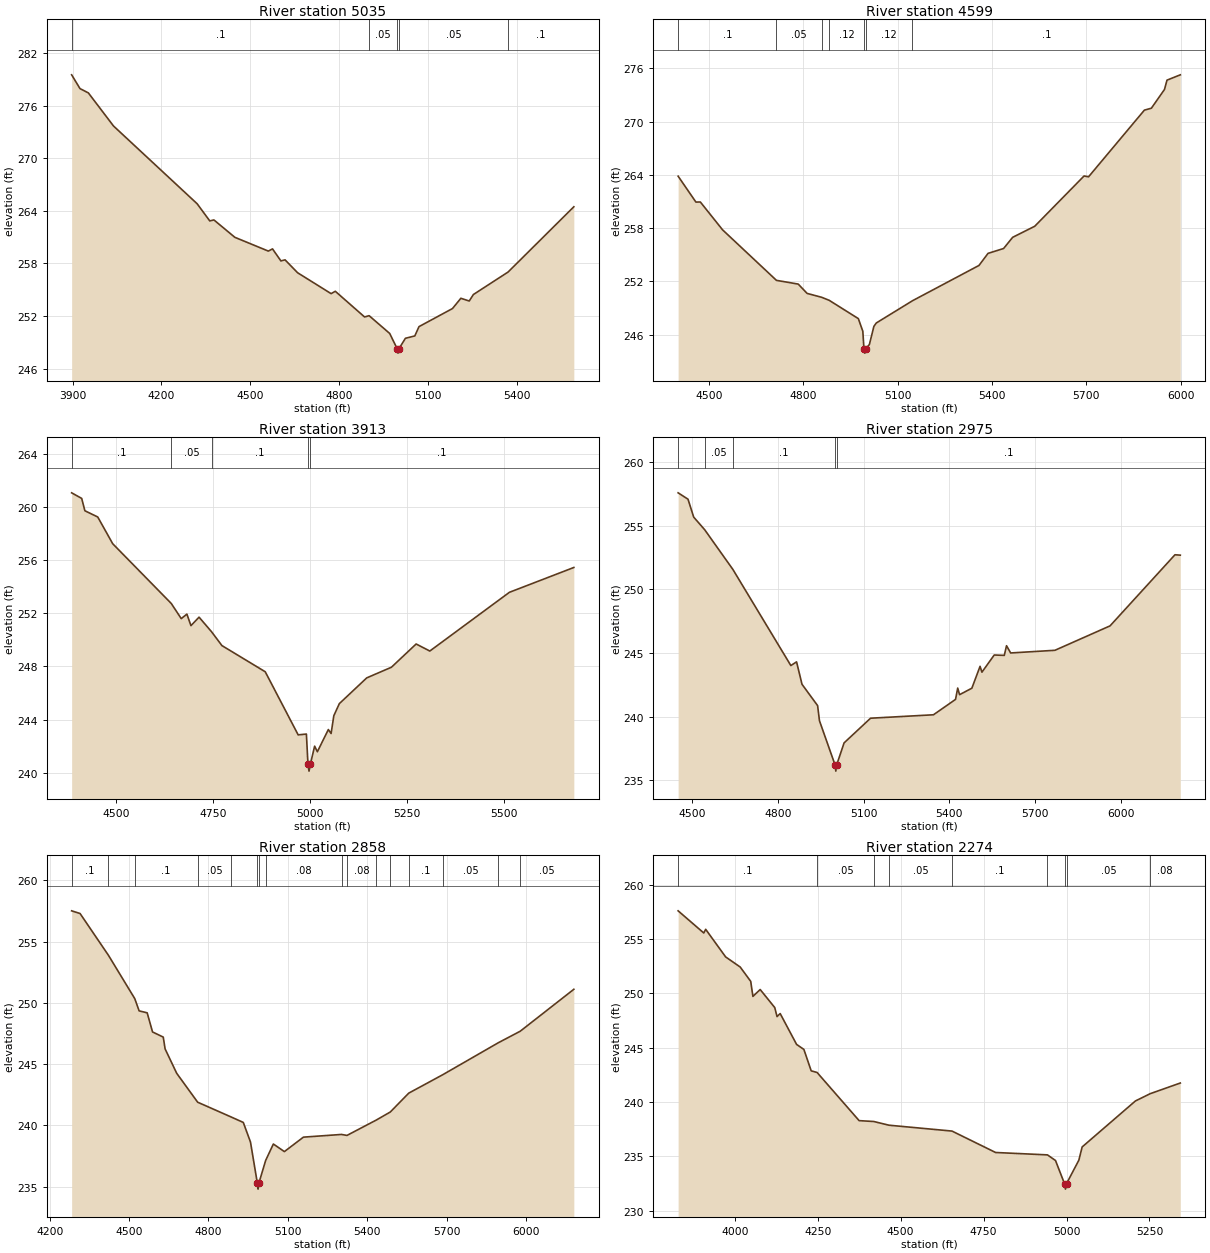
Type RM Length L Ch R = 1,5035,436,436,436
BEGIN DESCRIPTION:
UNT033 IN NURI 4.0
END DESCRIPTION:
XS GIS Cut Line= 3
      2313787.75     13323646.88      2314587.72     13324446.85
      2314987.71     13324846.84
#Sta/Elev= 30
  3896.7  279.50  3924.9  277.93  3953.2  277.44  4038.1  273.67  4320.9  264.80
  4363.4  262.85  4377.5  262.96  4448.2  260.98  4561.3  259.41  4575.5  259.66
  4603.8  258.29  4617.9  258.41  4660.3  256.94  4773.5  254.56  4787.6  254.83
  4886.6  251.90  4901.8  252.05  4971.5  250.02  4996.7  248.28  4999.5  247.78
  5002.7  248.28  5024.5  249.47  5056.3  249.74  5070.5  250.80  5183.6  252.86
  5211.9  254.03  5240.2  253.72  5254.3  254.46  5371.4  257.02  5593.7  264.46
#Mann=5,-1,0
  3896.7     0.1       0  4901.8    0.05       0  4996.7    0.03       0
  5002.7    0.05       0  5371.4     0.1       0
Bank Sta=4996.7,5002.7
Exp/Cntr=0.3,0.1

Type RM Length L Ch R = 1,4599,686,686,686
BEGIN DESCRIPTION:
UNT033 IN NURI 3.0
END DESCRIPTION:
XS GIS Cut Line= 3
      2313787.73     13324246.87      2314187.72     13324646.85
      2314987.69     13325296.83
#Sta/Elev= 30
  4402.3  263.86  4458.9  260.94  4473.0  260.95  4543.7  257.81  4714.9  252.12
  4784.1  251.70  4812.4  250.65  4858.7  250.21  4882.6  249.87  4975.2  247.81
  4989.5  246.38  4993.0  244.42  4995.7  243.92  4999.0  244.42  5010.3  244.89
  5024.7  246.94  5032.4  247.32  5147.2  249.82  5358.7  253.80  5387.5  255.16
  5437.0  255.71  5465.8  256.97  5536.1  258.22  5692.7  263.88  5707.1  263.79
  5884.5  271.30  5906.8  271.52  5948.4  273.63  5956.4  274.68  5998.7  275.28
#Mann=7,-1,0
  4402.3     0.1       0  4714.9    0.05       0  4858.7     0.1       0
  4882.6    0.12       0  4993.0    0.07       0  4999.0    0.12       0
  5147.2     0.1       0
Bank Sta=4993,4999
Exp/Cntr=0.3,0.1

Type RM Length L Ch R = 1,3913,938,938,938
BEGIN DESCRIPTION:
UNT033 IN NURI 2.0
END DESCRIPTION:
XS GIS Cut Line= 3
      2313402.18     13324502.03      2313527.20     13324923.95
      2314131.38     13325528.14
#Sta/Elev= 30
  4384.7  261.07  4410.6  260.65  4418.8  259.72  4452.0  259.25  4490.5  257.24
  4641.5  252.74  4667.2  251.60  4681.8  251.94  4692.2  251.07  4713.1  251.71
  4745.4  250.61  4772.1  249.57  4883.7  247.60  4968.6  242.85  4989.8  242.91
  4993.9  240.62  4996.6  240.12  4999.9  240.62  5011.0  242.00  5018.1  241.58
  5046.4  243.25  5053.5  242.95  5060.5  244.29  5074.7  245.20  5145.4  247.14
  5209.0  247.94  5272.7  249.69  5308.0  249.16  5513.1  253.58  5679.2  255.45
#Mann=5,-1,0
  4384.7     0.1       0  4641.5    0.05       0  4745.4     0.1       0
  4993.9    0.07       0  4999.9     0.1       0
Bank Sta=4993.9,4999.9
Exp/Cntr=0.3,0.1

Type RM Length L Ch R = 1,2975,117,117,117
BEGIN DESCRIPTION:
Mapping XS 6278dd0c
END DESCRIPTION:
XS GIS Cut Line= 3
      2312699.07     13324632.28      2312683.45     13325069.78
      2313708.71     13325902.49
#Sta/Elev= 30
  4450.1  257.60  4484.7  257.10  4504.7  255.69  4543.1  254.70  4641.8  251.58
  4844.9  244.02  4864.9  244.31  4883.9  242.55  4938.6  240.87  4945.1  239.68
  4999.5  236.22  5002.3  235.72  5005.5  236.22  5031.3  237.94  5124.0  239.88
  5344.3  240.15  5421.6  241.36  5429.2  242.25  5435.7  241.73  5478.8  242.24
  5507.5  243.96  5514.0  243.50  5557.1  244.85  5592.3  244.82  5600.2  245.58
  5614.6  245.01  5769.7  245.22  5962.7  247.14  6190.0  252.73  6208.7  252.70
#Mann=5,-1,0
  4450.1     0.1       0  4543.1    0.05       0  4641.8     0.1       0
  4999.5    0.07       0  5005.5     0.1       0
Bank Sta=4999.5,5005.5
Exp/Cntr=0.3,0.1

Type RM Length L Ch R = 1,2858,584,584,584
BEGIN DESCRIPTION:
Mapping XS 053e0e7c
END DESCRIPTION:
XS GIS Cut Line= 3
      2312620.94     13324585.45      2312535.87     13325096.84
      2313610.56     13325960.43
#Sta/Elev= 30
  4283.1  257.51  4314.9  257.29  4421.9  253.89  4521.5  250.35  4538.0  249.35
  4568.4  249.19  4588.7  247.63  4629.2  247.21  4636.1  246.25  4679.9  244.26
  4759.1  241.90  4886.1  240.69  4931.5  240.25  4958.7  238.65  4984.5  235.31
  4987.3  234.81  4990.5  235.31  5016.0  237.15  5045.1  238.49  5086.7  237.87
  5158.7  239.05  5302.6  239.27  5323.2  239.19  5433.5  240.44  5486.8  241.10
  5556.6  242.64  5684.9  244.14  5894.1  246.74  5977.7  247.69  6180.2  251.11
#Mann=16,-1,0
  4283.1     0.1       0  4421.9    0.05       0  4521.5     0.1       0
  4759.1    0.05       0  4886.1     0.1       0  4984.5    0.07       0
  4990.5     0.1       0  5016.0    0.08       0  5302.6     0.1       0
  5323.2    0.08       0  5433.5     0.1       0  5486.8    0.08       0
  5556.6     0.1       0  5684.9    0.05       0  5894.1     0.1       0
  5977.7    0.05       0
Bank Sta=4984.5,4990.5
Exp/Cntr=0.3,0.1

Type RM Length L Ch R = 1,2274,508,508,508
BEGIN DESCRIPTION:
Mapping XS 5943fa3f
END DESCRIPTION:
XS GIS Cut Line= 3
      2312579.28     13324543.74      2312329.28     13325012.49
      2312412.61     13325991.69
#Sta/Elev= 30
  3829.1  257.58  3906.5  255.54  3912.2  255.88  3972.4  253.34  4016.3  252.41
  4048.0  251.09  4054.6  249.71  4076.5  250.34  4120.5  248.68  4127.3  247.85
  4136.8  248.13  4186.3  245.29  4208.3  244.83  4230.3  242.86  4248.1  242.71
  4374.8  238.28  4419.0  238.20  4464.8  237.86  4654.8  237.32  4786.3  235.35
  4942.6  235.13  4966.9  234.61  4994.0  232.48  4996.8  231.98  5000.0  232.48
  5037.2  234.64  5047.2  235.86  5207.8  240.09  5252.4  240.76  5343.1  241.74
#Mann=9,-1,0
  3829.1     0.1       0  4248.1    0.05       0  4419.0     0.1       0
  4464.8    0.05       0  4654.8     0.1       0  4942.6    0.05       0
  4994.0    0.03       0  5000.0    0.05       0  5252.4    0.08       0
Bank Sta=4994,5000
Exp/Cntr=0.3,0.1

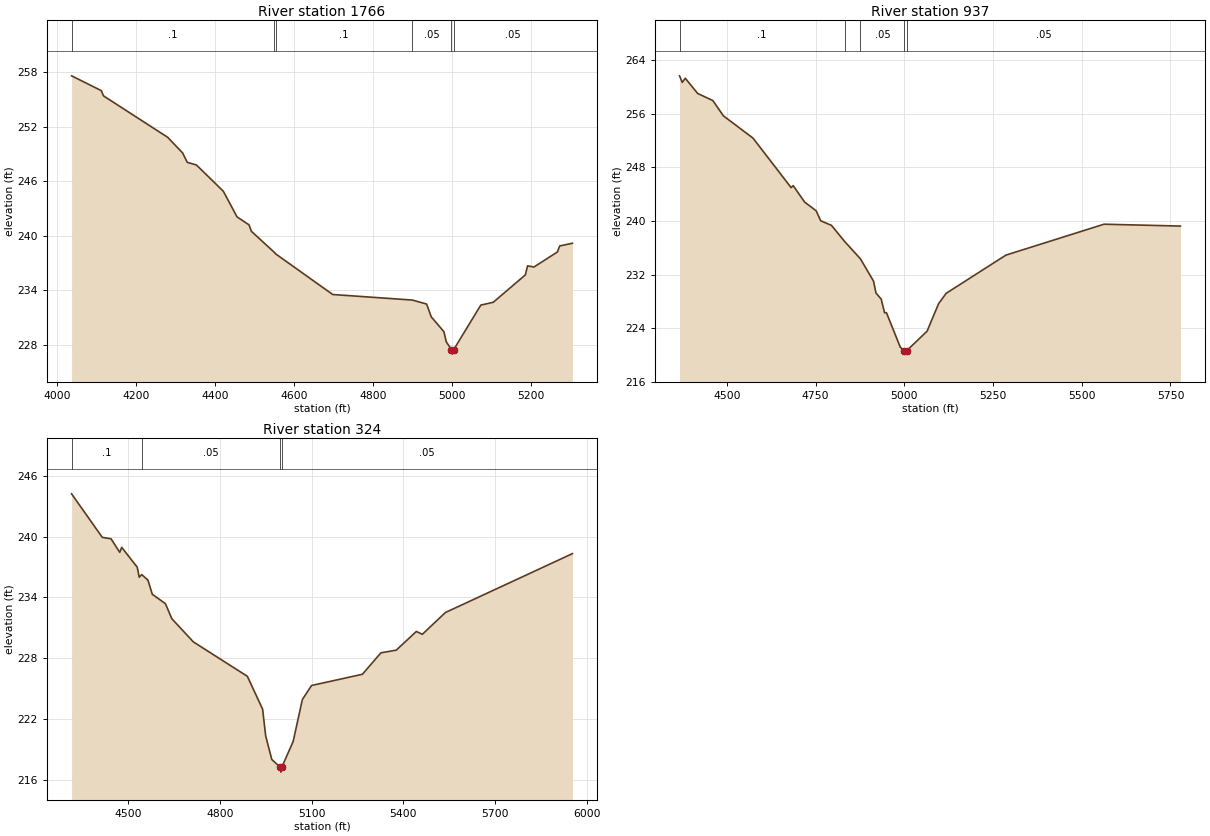
Type RM Length L Ch R = 1,1766,829,829,829
BEGIN DESCRIPTION:
Mapping XS 1a1d5cc3
END DESCRIPTION:
XS GIS Cut Line= 2
      2312511.56     13324460.43      2311896.99     13325569.78
#Sta/Elev= 30
  4036.3  257.62  4111.5  255.99  4117.2  255.41  4279.8  250.84  4317.5  249.12
  4329.4  248.08  4352.3  247.80  4420.6  244.90  4455.2  242.08  4485.8  241.19
  4491.5  240.49  4550.1  238.15  4553.0  238.00  4697.6  233.52  4899.1  232.91
  4935.3  232.47  4947.2  231.05  4979.2  229.42  4985.0  228.32  4998.0  227.45
  5000.7  226.95  5004.0  227.45  5072.5  232.35  5104.0  232.66  5185.3  235.68
  5191.0  236.68  5207.1  236.55  5266.6  238.21  5272.3  238.87  5304.5  239.17
#Mann=6,-1,0
  4036.3     0.1       0  4550.1    0.05       0  4553.0     0.1       0
  4899.1    0.05       0  4998.0    0.03       0  5004.0    0.05       0
Bank Sta=4998,5004
Exp/Cntr=0.3,0.1

Type RM Length L Ch R = 1,937,613,613,613
BEGIN DESCRIPTION:
Mapping XS 5541f37f
END DESCRIPTION:
XS GIS Cut Line= 3
      2311969.91     13324069.77      2311626.15     13324923.95
      2311771.85     13325392.25
#Sta/Elev= 30
  4366.8  261.63  4374.4  260.65  4382.9  261.27  4417.9  259.00  4460.7  257.94
  4490.4  255.66  4573.7  252.35  4681.2  244.96  4687.0  245.26  4719.4  242.80
  4751.7  241.51  4764.5  240.02  4794.8  239.34  4831.8  236.95  4876.4  234.35
  4913.4  231.02  4920.3  229.25  4935.0  228.34  4944.5  226.30  4949.8  226.32
  4988.9  221.16  5000.6  220.64  5003.3  220.14  5006.6  220.64  5064.3  223.56
  5096.7  227.66  5118.2  229.21  5286.4  234.90  5562.9  239.51  5778.0  239.23
#Mann=5,-1,0
  4366.8     0.1       0  4831.8    0.08       0  4876.4    0.05       0
  5000.6    0.03       0  5006.6    0.05       0
Bank Sta=5000.6,5006.6
Exp/Cntr=0.3,0.1

Type RM Length L Ch R = 1,324,0,0,0
BEGIN DESCRIPTION:
UNT033 IN NURI 1.0
END DESCRIPTION:
XS GIS Cut Line= 4
      2311464.69     13323871.88      2311162.61     13324231.24
      2311167.82     13324699.99      2311412.63     13325356.28
#Sta/Elev= 30
  4314.6  244.24  4415.0  239.94  4443.6  239.80  4472.2  238.46  4478.7  238.95
  4529.4  236.99  4535.9  236.00  4544.2  236.26  4564.5  235.71  4578.8  234.31
  4621.6  233.39  4642.6  231.90  4713.0  229.61  4889.7  226.21  4939.7  222.96
  4949.7  220.32  4969.7  217.99  4996.7  217.24  4999.4  216.74  5002.7  217.24
  5039.7  219.78  5069.7  223.91  5099.7  225.30  5266.2  226.41  5326.8  228.53
  5376.8  228.79  5442.7  230.64  5462.4  230.36  5537.7  232.51  5953.3  238.33
#Mann=4,-1,0
  4314.6     0.1       0  4544.2    0.05       0  4996.7    0.03       0
  5002.7    0.05       0
Bank Sta=4996.7,5002.7
Exp/Cntr=0.3,0.1

Chan Stop Cuts=-1