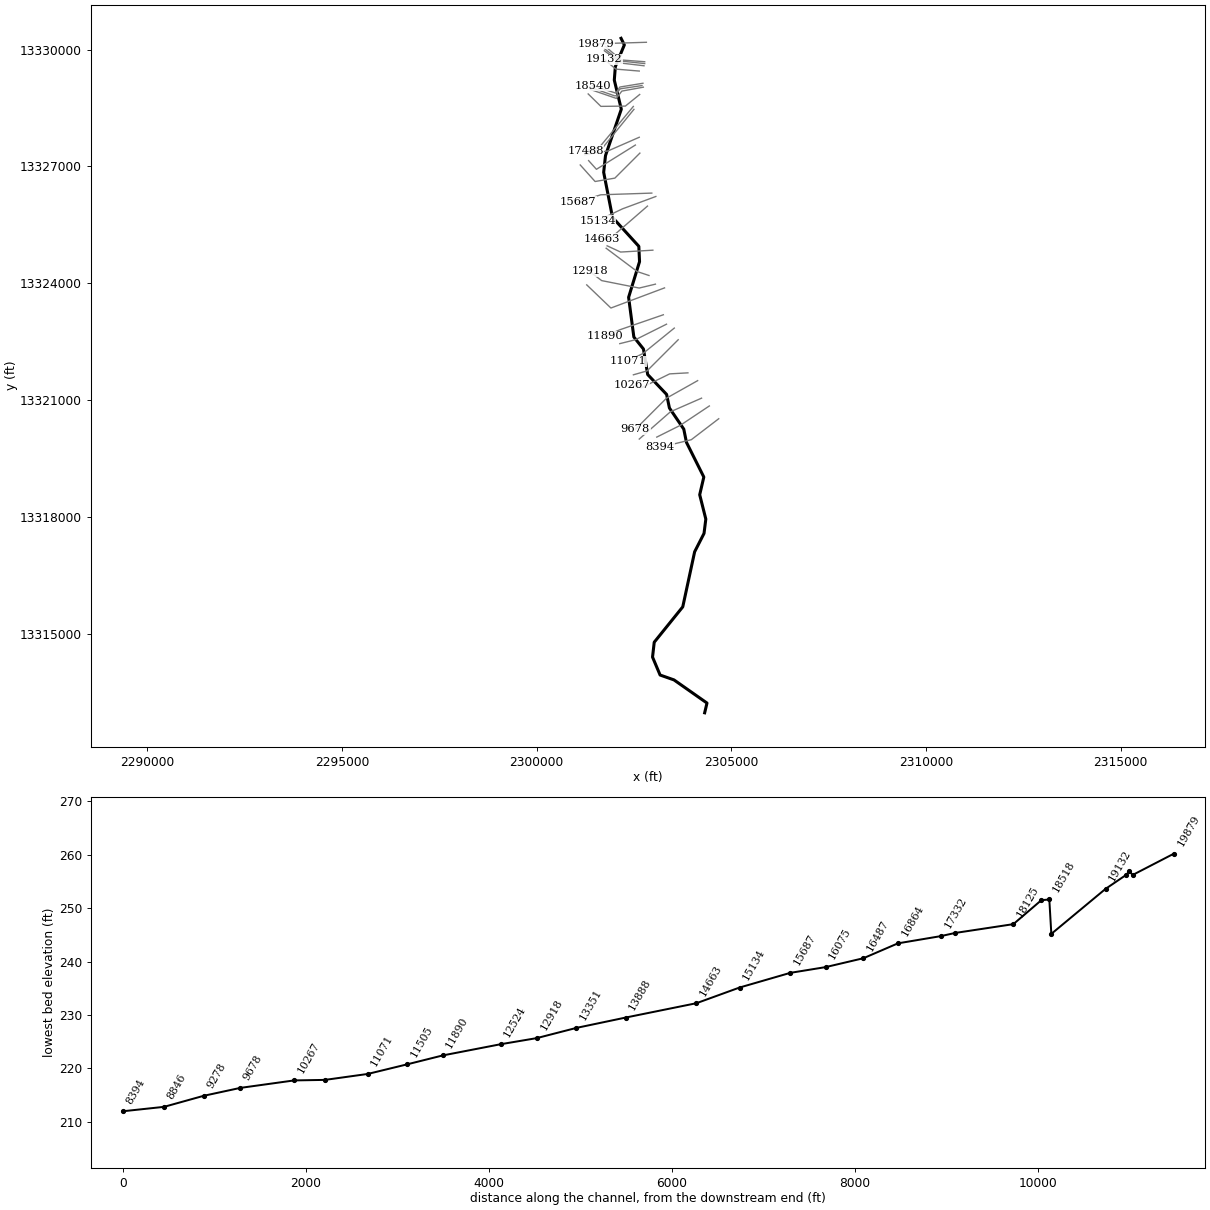
--- UNT034 IN NURI.prj (project) ---

Proj Title=UNT034 IN NURI Base Level Engineering
Current Plan=p01
Default Exp/Contr=0.3,0.1
English Units
Geom File=g01
Flow File=f01
Plan File=p01
Y Axis Title=Elevation
X Axis Title(PF)=Main Channel Distance
X Axis Title(XS)=Station
BEGIN DESCRIPTION:
UNT034 IN NURI
END DESCRIPTION:
DSS Export Rating Curves= 0
DSS Export Rating Curve Sorted= 0
DSS Export Volume Flow Curves= 0
DXF OffsetX= 0
DXF OffsetY= 0
DXF ScaleX= 1
DXF ScaleY= 10

--- UNT034 IN NURI.p01 (plan) ---

Plan Title=Multiple Run
Short Identifier=Multiple
Geom File=g01
Flow File=f01
Subcritical Flow
K Sum by GR= 0
Std Step Tol= 0.01
Critical Tol= 0.01
Num of Std Step Trials= 20
Max Error Tol= 0.3
Flow Tol Ratio= 0.001
Split Flow NTrial= 30
Split Flow Tol= 0.02
Split Flow Ratio= 0.02
Log Output Level= 0
Friction Slope Method= 1
Unsteady Friction Slope Method= 2
Unsteady Bridges Friction Slope Method= 1
Parabolic Critical Depth
Global Vel Dist=  1 , 1 , 1
Global Log Level= 0
CheckData=True
Encroach Param= -1, 0, 0, 0
BEGIN DESCRIPTION:
Multiple Run
END DESCRIPTION:

--- UNT034 IN NURI.f01 (steady flow) ---

Flow Title=Multiple
Program Version=4.10
Number of Profiles= 7
Profile Names=10-year,25-year,50-year,1pct_min,100-year,1pct_plu,500-year
River Rch & RM=UNT034 IN NURI,Reach-1         ,19879
     593     842    1052     960    1299    1756    1987
River Rch & RM=UNT034 IN NURI,Reach-1         ,17332
     886    1287    1632    1510    2042    2761    3211
River Rch & RM=UNT034 IN NURI,Reach-1         ,15687
    1337    1975    2533    2366    3200    4328    5134
River Rch & RM=UNT034 IN NURI,Reach-1         ,15134
    1337    1975    2533    2366    3200    4328    5134
River Rch & RM=UNT034 IN NURI,Reach-1         ,11890
    1765    2637    3406    3202    4330    5856    7035
River Rch & RM=UNT034 IN NURI,Reach-1         ,7539
    1979    2962    3832    3604    4874    6592    7932
Boundary for River Rch & Prof#=UNT034 IN NURI,Reach-1         , 1
Up Type= 0
Dn Type= 3
Dn Slope=0.005
Boundary for River Rch & Prof#=UNT034 IN NURI,Reach-1         , 2
Up Type= 0
Dn Type= 3
Dn Slope=0.005
Boundary for River Rch & Prof#=UNT034 IN NURI,Reach-1         , 3
Up Type= 0
Dn Type= 3
Dn Slope=0.005
Boundary for River Rch & Prof#=UNT034 IN NURI,Reach-1         , 4
Up Type= 0
Dn Type= 3
Dn Slope=0.005
Boundary for River Rch & Prof#=UNT034 IN NURI,Reach-1         , 5
Up Type= 0
Dn Type= 3
Dn Slope=0.005
Boundary for River Rch & Prof#=UNT034 IN NURI,Reach-1         , 6
Up Type= 0
Dn Type= 3
Dn Slope=0.005
Boundary for River Rch & Prof#=UNT034 IN NURI,Reach-1         , 7
Up Type= 0
Dn Type= 3
Dn Slope=0.005
DSS Import GetInterval= 0
DSS Import GetPeak= 0
DSS Import FillOption= 0

--- UNT034 IN NURI.g01 (geometry) ---

Geom Title=Existing Conditions
Program Version=4.10

River Reach=UNT034 IN NURI  ,Reach-1
Reach XY= 30
      2302170.24     13330287.98      2302254.49     13330118.01
      2302023.53     13329560.33      2301996.92     13329214.65
      2302176.72     13328467.28      2301770.75     13327275.64
      2301723.82      13326846.9      2301951.39     13325688.36
      2302626.72     13324946.36      2302645.02     13324552.81
      2302364.43     13323636.53      2302498.93     13322616.92
      2302745.34     13322309.28      2302853.94     13321653.58
      2303339.77      13321143.3      2303412.61     13320794.45
      2303781.26     13320251.45      2303849.79     13319912.57
      2304295.96     13319021.29      2304190.18      13318566.8
       2304347.3     13317941.67      2304301.29     13317573.61
      2304059.97     13317101.39      2303755.14     13315687.92
      2303022.42     13314779.63      2302978.75     13314397.56
      2303172.94     13313937.02      2303530.18     13313811.41
      2304377.22      13313217.2      2304317.72     13312966.85

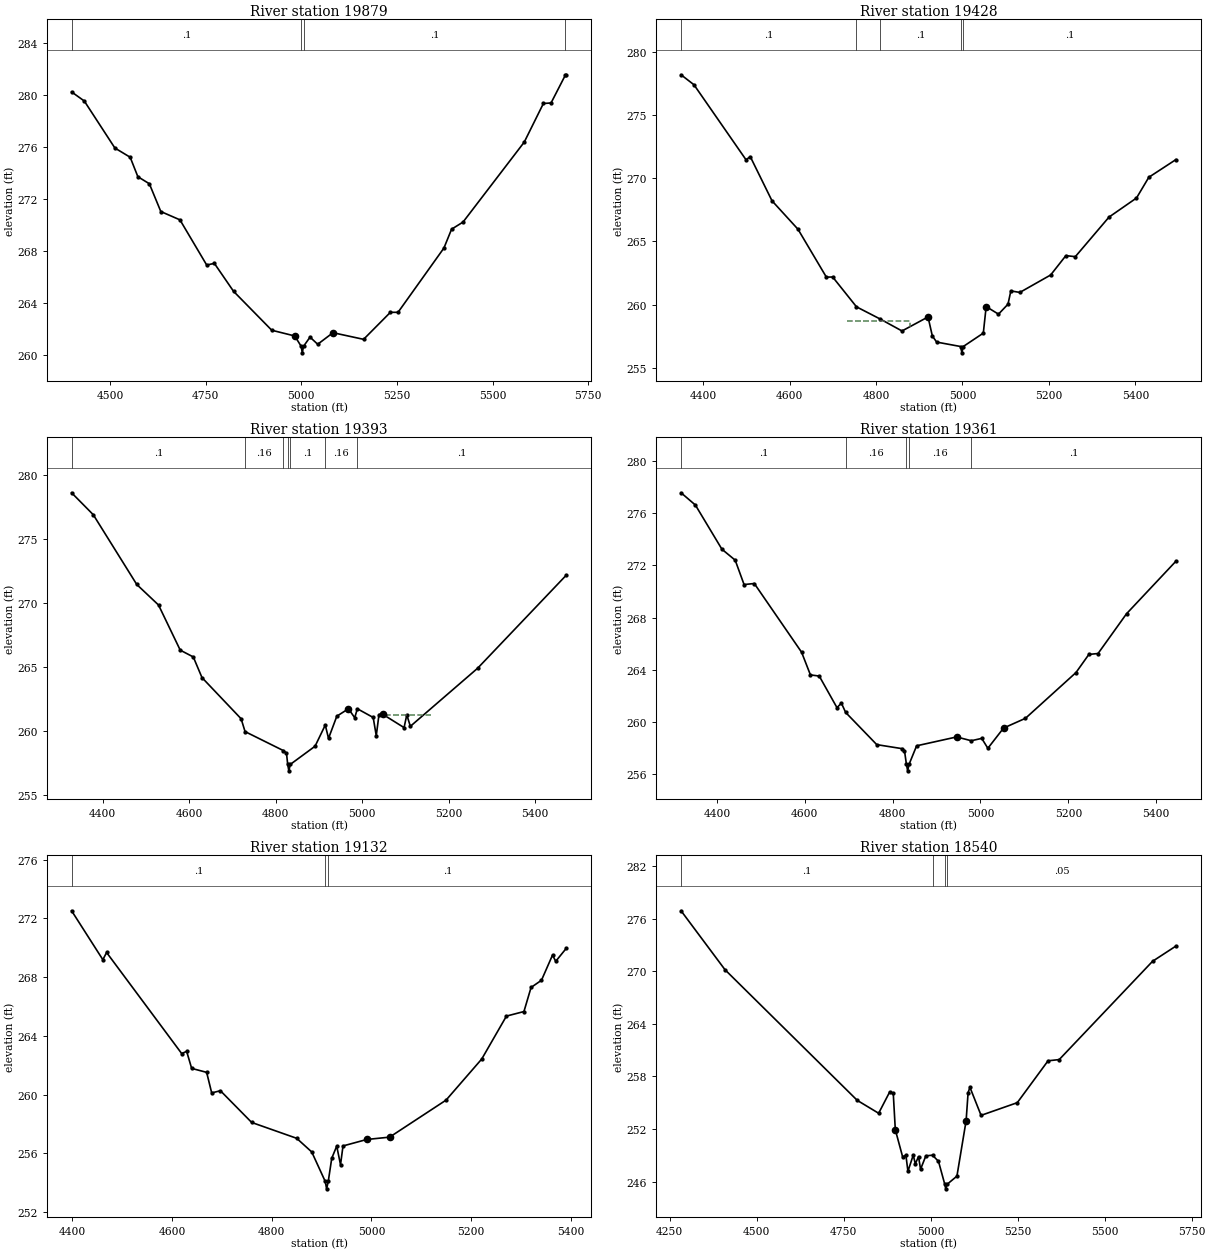
Type RM Length L Ch R = 1 ,19879   ,451,451,451
BEGIN DESCRIPTION:
UNT034 IN NURI 33.0
END DESCRIPTION:
XS GIS Cut Line= 2
      2302820.89     13330185.81      2301527.48     13330146.75
#Sta/Elev= 30
  4399.2  280.26  4432.4  279.56  4512.4  275.94  4552.4  275.23  4572.5  273.73
  4602.5  273.19  4632.5  271.05  4682.5  270.41  4752.5  266.93  4772.5  267.06
  4822.6  264.91  4922.6  261.91  4982.6  261.47  4999.6  260.67  5002.4  260.17
  5005.6  260.67  5022.7  261.38  5042.7  260.83  5082.7  261.72  5162.7  261.21
  5232.8  263.29  5252.8  263.29  5372.8  268.24  5392.8  269.69  5422.8  270.24
  5582.9   276.4  5632.9  279.37  5652.9  279.41  5689.9  281.53  5693.2  281.58
#Mann= 4 ,-1 , 0
  4399.2      .1       0  4999.6     .07       0  5005.6      .1       0
  5689.9     .05       0
Bank Sta=4982.6,5082.7
XS Rating Curve= 0 ,0
Exp/Cntr=0.3,0.1

Type RM Length L Ch R = 1 ,19428   ,35,35,35
BEGIN DESCRIPTION:
Mapping XS 7b0fd880
END DESCRIPTION:
XS GIS Cut Line= 3
       2302777.5     13329686.68      2302169.85     13329732.25
        2301764.     13330081.67
#Sta/Elev= 30
  4348.9  278.18  4378.8  277.39  4499.1  271.46  4509.1   271.7  4559.3  268.21
  4619.4  265.96  4685.1  262.17  4699.7  262.18  4754.8  259.82  4809.9  258.85
  4860.1  257.91  4920.3  259.02  4930.3  257.51  4940.3  257.03  4995.8  256.68
  4998.6  256.18  5001.8  256.68  5048.2  257.74  5054.8  259.84  5083.3  259.24
  5105.3  260.03  5111.9  261.08  5132.7  260.96    5204  262.34  5239.2  263.87
  5261.1  263.79    5339  266.92  5402.6  268.43  5431.1  270.07  5493.8  271.47
#Mann= 5 ,-1 , 0
  4348.9      .1       0  4754.8     .16       0  4809.9      .1       0
  4995.8     .07       0  5001.8      .1       0
#XS Ineff= 1 ,-1
  4733.9 4878.25  258.71
Permanent Ineff=
       F
Bank Sta=4920.3,5054.8
XS Rating Curve= 0 ,0
Exp/Cntr=0.3,0.1

Type RM Length L Ch R = 1 ,19393   ,32,32,32
BEGIN DESCRIPTION:
Mapping XS d2238b66
END DESCRIPTION:
XS GIS Cut Line= 3
      2302777.53     13329638.93      2302150.31     13329706.21
      2301744.52     13330020.86
#Sta/Elev= 30
    4328   278.6  4378.1  276.89  4478.7  271.45    4529  269.85  4579.2  266.33
  4609.4   265.8  4629.5  264.19    4720  260.98  4729.1  259.98  4817.6   258.5
  4824.9   258.3  4827.7  257.42  4830.4  256.92  4833.7  257.42    4891  258.84
  4914.6  260.49  4922.1  259.45  4941.3  261.18  4968.2  261.76  4982.7  261.06
  4988.8  261.76  5025.4  261.08  5032.5  259.66  5038.8  261.31    5047  261.34
  5096.8  260.29  5103.1  261.29  5111.3  260.39  5266.9  264.92  5472.3  272.19
#Mann= 7 ,-1 , 0
    4328      .1       0  4729.1     .16       0  4817.6      .1       0
  4827.7     .07       0  4833.7      .1       0  4914.6     .16       0
  4988.8      .1       0
#XS Ineff= 2 ,-1
 4682.88 4951.88  261.24 5056.37 5158.64  261.31
Permanent Ineff=
       F       F
Bank Sta=4968.2,5047
XS Rating Curve= 0 ,0
Exp/Cntr=0.3,0.1

Type RM Length L Ch R = 1 ,19361   ,229,229,229
BEGIN DESCRIPTION:
Mapping XS 6762185c
END DESCRIPTION:
XS GIS Cut Line= 3
       2302760.1     13329582.52      2302172.02     13329651.96
      2301741.44     13329967.86
#Sta/Elev= 30
  4318.6  277.57  4351.2  276.63  4411.6  273.24  4441.8   272.4    4462  270.53
  4485.3  270.61  4592.9  265.34    4613   263.6  4633.1  263.51  4673.4  261.09
  4683.5  261.43  4693.2  260.72    4764  258.25    4822  257.94  4827.1  257.78
  4831.5  256.74  4834.3  256.24  4837.5  256.74  4854.7  258.16  4945.7  258.84
  4979.1  258.55  5002.9  258.73  5016.8  257.97  5052.5  259.52  5102.4  260.27
  5217.4  263.78  5246.7  265.17  5267.6  265.24  5332.4  268.29  5444.8  272.32
#Mann= 5 ,-1 , 0
  4318.6      .1       0  4693.2     .16       0  4831.5     .07       0
  4837.5     .16       0  4979.1      .1       0
#XS Ineff= 1 ,-1
 4727.97 4905.93  258.42
Permanent Ineff=
       F
Bank Sta=4945.7,5052.5
XS Rating Curve= 0 ,0
Exp/Cntr=0.3,0.1

Type RM Length L Ch R = 1 ,19132   ,592,592,592
BEGIN DESCRIPTION:
UNT034 IN NURI 32.0
END DESCRIPTION:
XS GIS Cut Line= 3
      2302637.71     13329446.86      2302037.72     13329496.85
      2301737.71     13329746.87
#Sta/Elev= 30
  4398.5  272.51  4461.2  269.18  4468.7  269.67  4619.3  262.79  4629.3  262.94
  4639.3  261.78  4669.4  261.51  4679.5  260.11    4697  260.26  4759.7   258.1
    4850  257.02  4880.2  256.09  4907.3  254.08    4910  253.58  4913.3  254.08
  4920.3  255.66  4930.3  256.49  4937.9  255.22  4942.9   256.5  4990.5  256.94
  5036.4   257.1  5149.6  259.62  5221.2  262.42  5270.7  265.34  5305.8  265.65
  5320.1  267.29    5341  267.78  5363.1  269.49  5369.6  269.07  5391.1  269.97
#Mann= 3 ,-1 , 0
  4398.5      .1       0  4907.3     .07       0  4913.3      .1       0
Bank Sta=4990.5,5036.4
XS Rating Curve= 0 ,0
Exp/Cntr=0.3,0.1

Type RM Length L Ch R = 1 ,18540   ,22,22,22
BEGIN DESCRIPTION:
Mapping XS 5c5c817d
END DESCRIPTION:
XS GIS Cut Line= 4
      2302732.38     13329133.74       2302138.6     13329036.51
       2302037.9     13328880.26       2301433.7     13329074.71
#Sta/Elev= 30
  4282.5  276.92  4408.8  270.19    4789  255.27  4850.4   253.8  4882.1  256.23
  4892.4  256.09  4898.3  251.92  4919.5   248.8  4928.7  249.02  4934.6  247.17
  4949.8  249.02  4955.8  248.03    4965  248.85  4970.9  247.41  4986.1  248.94
  5005.2  249.01  5022.4  248.31  5040.6  245.67  5043.3  245.17  5046.6  245.67
  5075.4  246.62  5101.8  252.95  5107.5  256.15  5112.7  256.77  5144.8  253.56
  5248.9  255.01  5337.3  259.79  5369.4  259.93  5637.6  271.15  5704.8  272.89
#Mann= 4 ,-1 , 0
  4282.5      .1       0  5005.2     .05       0  5040.6     .07       0
  5046.6     .05       0
Bank Sta=4898.3,5101.8
XS Rating Curve= 0 ,0
Exp/Cntr=0.3,0.1

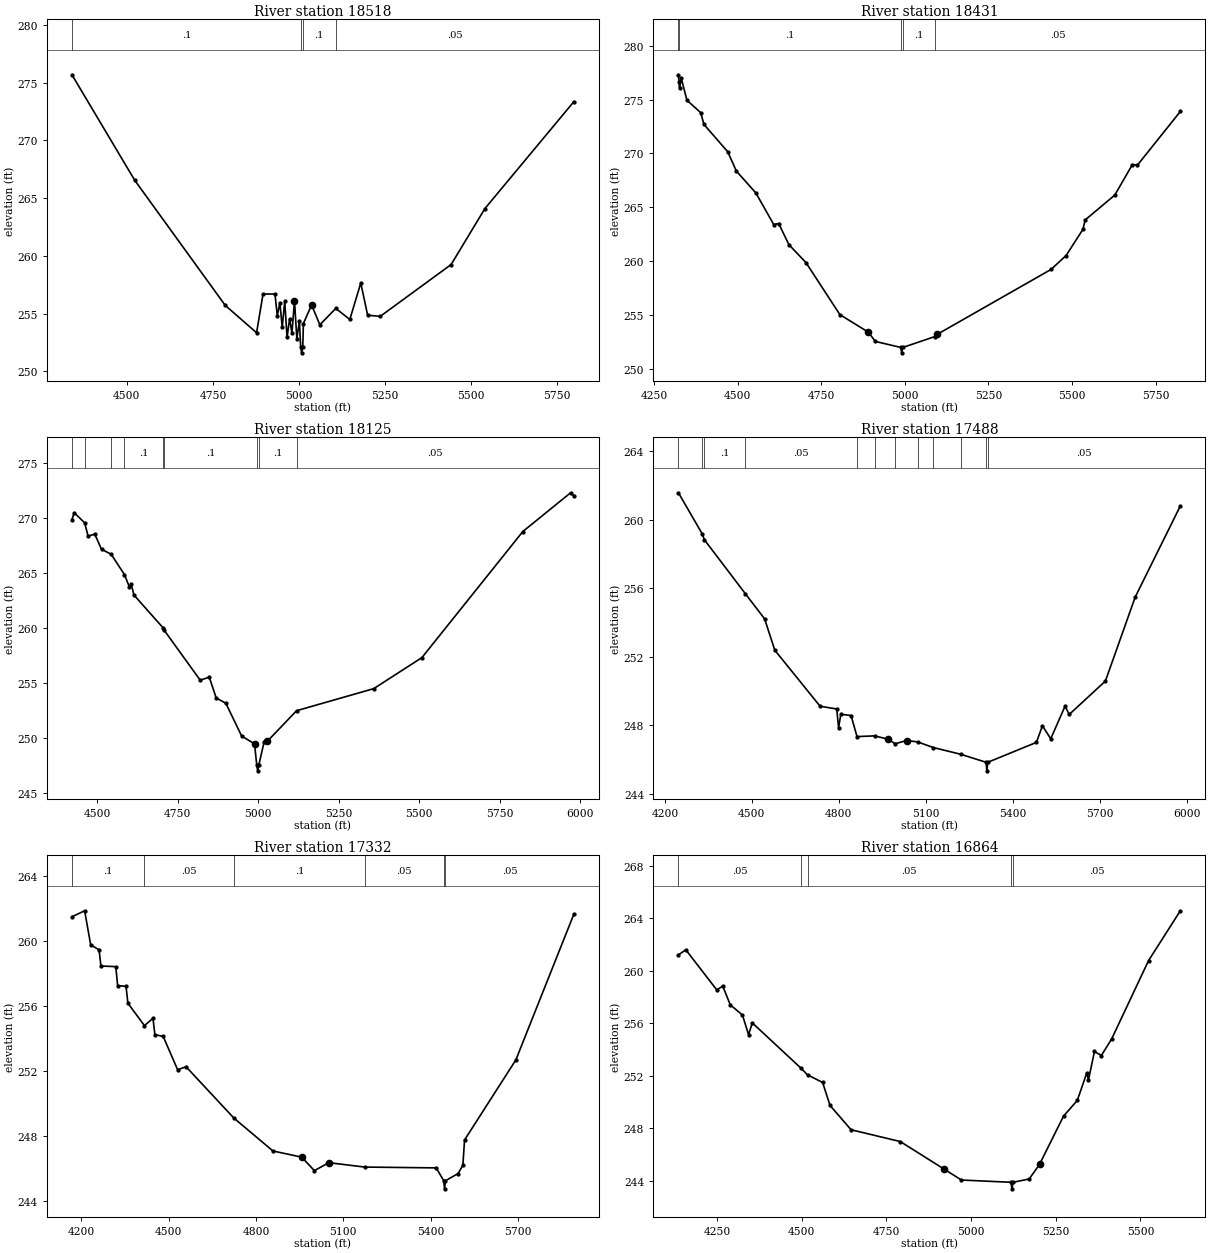
Type RM Length L Ch R = 1 ,18518   ,87,87,87
BEGIN DESCRIPTION:
UNT034 IN NURI 31.0
END DESCRIPTION:
XS GIS Cut Line= 6
      2302708.01      13329074.7      2302152.48     13328991.37
       2302076.1     13328908.04      2302069.15     13328817.76
      2302003.18     13328810.81      2301412.93     13329019.14
#Sta/Elev= 30
  4340.6  275.69  4522.9  266.55  4785.8  255.71  4876.8  253.34  4895.5  256.69
  4930.2   256.7    4937   254.8  4944.4  255.96  4951.2  253.82  4958.6  256.06
  4965.3  252.94  4972.7  254.56  4979.5   253.3  4986.9  256.11  4993.7  252.82
  5001.1  254.33  5004.9   252.1  5007.6   251.6  5010.9   252.1  5012.8  254.14
  5036.6  255.75  5060.5  254.03  5106.8  255.45  5147.6  254.49  5179.4  257.65
  5199.3  254.86  5235.9  254.76  5441.8  259.25  5539.9   264.1  5798.2  273.36
#Mann= 4 ,-1 , 0
  4340.6      .1       0  5004.9     .07       0  5010.9      .1       0
  5106.8     .05       0
Bank Sta=4986.9,5036.6
XS Rating Curve= 0 ,0
Exp/Cntr=0.3,0.1

Type RM Length L Ch R = 1 ,18431   ,306,306,306
BEGIN DESCRIPTION:
Mapping XS 7fab4338
END DESCRIPTION:
XS GIS Cut Line= 4
       2302742.8     13329033.04      2302190.68     13328932.34
      2302048.32     13328744.84      2301382.23     13328973.81
#Sta/Elev= 30
    4323   277.3  4324.9  276.61  4326.3  276.11  4331.4     277  4348.5  274.93
  4389.8  273.78  4399.3  272.69  4470.5  270.15  4496.4  268.35  4554.7  266.32
    4608  263.39  4622.9  263.48  4653.4  261.52  4704.3  259.86  4805.9  255.02
  4891.1  253.39  4911.9  252.53    4988  251.97  4990.7  251.47    4994  251.97
  5089.9  252.98  5097.1  253.19  5437.5  259.22  5482.4  260.51  5532.7  262.94
  5539.6  263.82  5627.9  266.12  5680.7  268.96  5695.8  268.91    5824  273.89
#Mann= 5 ,-1 , 0
    4323     .08       0  4324.9      .1       0    4988     .07       0
    4994      .1       0  5089.9     .05       0
Bank Sta=4891.1,5097.1
XS Rating Curve= 0 ,0
Exp/Cntr=0.3,0.1

Type RM Length L Ch R = 1 ,18125   ,637,637,637
BEGIN DESCRIPTION:
UNT034 IN NURI 30.0
END DESCRIPTION:
XS GIS Cut Line= 4
      2302649.02     13328845.54      2302280.96     13328546.92
      2301652.48     13328539.98      2301326.08     13328859.44
#Sta/Elev= 30
  4421.7  269.88  4428.7  270.52  4461.2  269.59  4471.8  268.38  4492.6  268.56
  4513.5  267.18  4543.4  266.73  4584.7  264.88  4599.7  263.78  4606.1  263.99
  4614.1  263.02  4706.1  259.98  4708.3   259.8  4820.2  255.25  4848.3  255.53
  4869.8  253.63  4899.8  253.15  4948.9  250.16  4988.9  249.45  4995.9  247.49
  4998.7  246.99  5001.9  247.49  5018.9  249.65  5028.9  249.69  5119.5  252.47
  5359.2  254.48  5508.9  257.31  5822.4   268.8  5970.8  272.33  5980.9  272.05
#Mann= 9 ,-1 , 0
  4421.7     .05       0  4461.2      .1       0  4543.4     .05       0
  4584.7      .1       0  4706.1     .05       0  4708.3      .1       0
  4995.9     .07       0  5001.9      .1       0  5119.5     .05       0
Bank Sta=4988.9,5028.9
XS Rating Curve= 0 ,0
Exp/Cntr=0.3,0.1

Type RM Length L Ch R = 1 ,17488   ,156,156,156
BEGIN DESCRIPTION:
UNT034 IN NURI 29.0
END DESCRIPTION:
XS GIS Cut Line= 3
      2302485.09     13328537.75      2301611.86     13327487.43
      2301255.99     13327404.98
#Sta/Elev= 30
  4246.9  261.57  4329.8  259.15  4336.4  258.83  4478.2  255.67  4544.2  254.21
  4579.4  252.38  4735.6  249.11  4792.9  248.95  4799.4  247.86  4807.2  248.64
  4842.4  248.57  4862.9  247.34  4923.3  247.38    4970  247.19  4994.5  246.92
  5033.8  247.11  5071.7  247.03  5126.2   246.7    5220  246.31  5308.1  245.84
  5310.9  245.34  5314.1  245.84  5481.7     247  5502.5  247.97  5531.1  247.21
  5580.6  249.12  5594.9  248.63  5719.7  250.58  5822.4  255.48  5978.1   260.8
#Mann= 12 ,-1 , 0
  4246.9      .1       0  4329.8     .05       0  4336.4      .1       0
  4478.2     .05       0  4862.9      .1       0  4923.3     .05       0
  4994.5      .1       0  5071.7     .05       0  5126.2      .1       0
    5220     .05       0  5308.1     .07       0  5314.1     .05       0
Bank Sta=4970,5033.8
XS Rating Curve= 0 ,0
Exp/Cntr=0.3,0.1

Type RM Length L Ch R = 1 ,17332   ,468,468,468
BEGIN DESCRIPTION:
UNT034 IN NURI 28.0
END DESCRIPTION:
XS GIS Cut Line= 3
      2302501.59     13328463.96      2301663.94     13327435.35
      2301270.81     13327374.87
#Sta/Elev= 30
  4168.1   261.5  4211.7  261.87  4232.5  259.77  4261.2  259.47  4267.7  258.47
  4318.7  258.43  4325.1  257.26  4353.9  257.22  4360.3  256.18  4417.1   254.8
  4446.5  255.25    4453  254.25  4481.7  254.13  4531.2  252.08    4560  252.27
  4724.2  249.11  4858.7  247.08  4957.8   246.7  5000.9  245.87  5050.5  246.36
  5174.5  246.09  5419.6  246.04  5445.3  245.25  5448.1  244.75  5451.3  245.25
  5494.6  245.69  5511.1   246.2  5516.9  247.76  5693.2  252.69  5892.4  261.66
#Mann= 6 ,-1 , 0
  4168.1      .1       0  4417.1     .05       0  4724.2      .1       0
  5174.5     .05       0  5445.3     .07       0  5451.3     .05       0
Bank Sta=4957.8,5050.5
XS Rating Curve= 0 ,0
Exp/Cntr=0.3,0.1

Type RM Length L Ch R = 1 ,16864   ,377,377,377
BEGIN DESCRIPTION:
UNT034 IN NURI 27.0
END DESCRIPTION:
XS GIS Cut Line= 3
      2302637.68     13327746.84      2301837.72     13327396.85
      2301237.77     13327296.86
#Sta/Elev= 30
  4136.3  261.21  4158.1   261.6  4249.7  258.54  4267.2  258.84  4289.1  257.42
  4325.3  256.63  4343.3  255.14  4354.6  256.03  4497.5   252.6  4517.3  252.08
  4561.9   251.5  4583.8  249.75  4645.8   247.9  4791.2     247  4919.4  244.92
  4971.7  244.07    5118   243.9  5120.7   243.4    5124   243.9  5171.7  244.15
  5202.1  245.26  5273.1  248.94  5313.6  250.13  5341.5  252.22  5346.6  251.69
  5364.3  253.86  5384.6  253.55    5415  254.81    5524  260.78  5617.7  264.57
#Mann= 5 ,-1 , 0
  4136.3     .05       0  4497.5      .1       0  4517.3     .05       0
    5118     .03       0    5124     .05       0
Bank Sta=4919.4,5202.1
XS Rating Curve= 0 ,0
Exp/Cntr=0.3,0.1

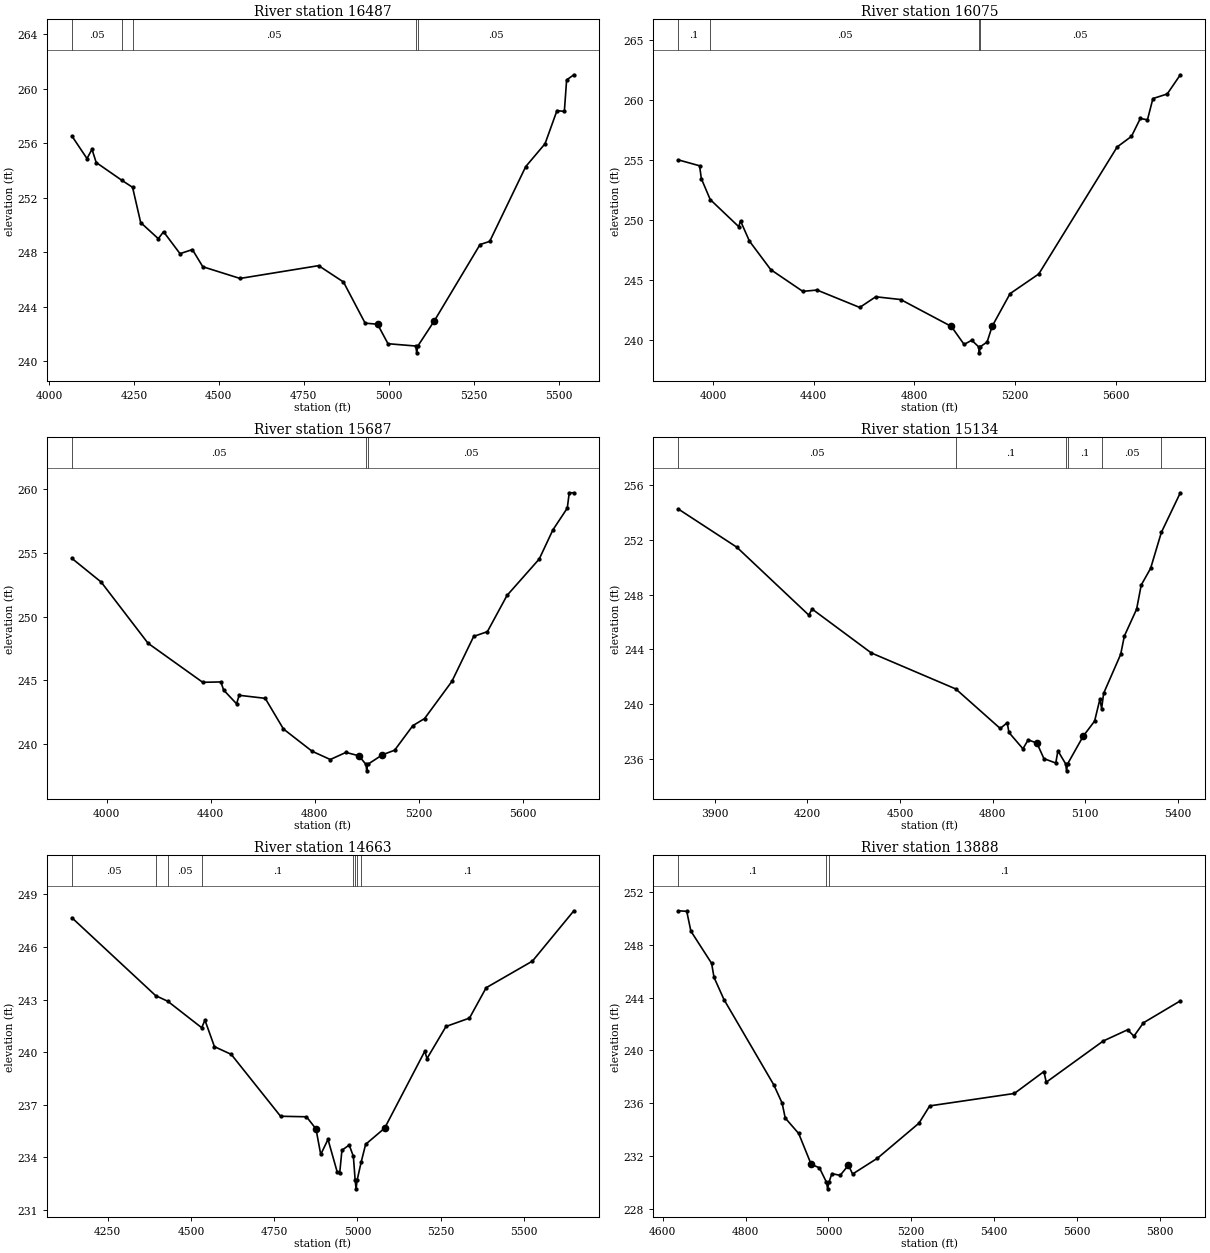
Type RM Length L Ch R = 1 ,16487   ,412,412,412
BEGIN DESCRIPTION:
UNT034 IN NURI 26.0
END DESCRIPTION:
XS GIS Cut Line= 3
      2302537.76     13327546.88      2301538.05     13326923.79
      2301337.72     13327146.85
#Sta/Elev= 30
  4067.4  256.53  4111.7  254.88  4126.4  255.56  4138.8  254.59  4214.5  253.28
  4245.9  252.77  4269.8  250.18  4321.7     249  4337.1  249.51  4385.6   247.9
    4422   248.2  4452.7  246.94  4562.3  246.08  4793.7  247.02  4866.9  245.82
  4930.6   242.8  4967.2  242.72  4997.9  241.29  5079.8  241.12  5082.5  240.62
  5085.8  241.12  5134.7  242.98    5269  248.57  5297.4   248.8  5403.5  254.29
  5460.4  255.97  5495.5   258.4  5517.2  258.34  5523.9  260.65  5545.2  261.03
#Mann= 5 ,-1 , 0
  4067.4     .05       0  4214.5      .1       0  4245.9     .05       0
  5079.8     .03       0  5085.8     .05       0
Bank Sta=4967.2,5134.7
XS Rating Curve= 0 ,0
Exp/Cntr=0.3,0.1

Type RM Length L Ch R = 1 ,16075   ,388,388,388
BEGIN DESCRIPTION:
UNT034 IN NURI 25.0
END DESCRIPTION:
XS GIS Cut Line= 4
      2302653.56      13327339.9      2302011.17      13326697.5
      2301503.35      13326610.7       2301122.1     13327035.28
#Sta/Elev= 30
  3862.1  255.03  3946.2  254.54  3953.2  253.47  3988.4  251.73  4101.7  249.47
  4108.8  249.95  4144.2  248.27    4229  245.89  4356.3  244.08  4412.9  244.19
  4582.6  242.74  4646.2  243.63  4745.2   243.4  4946.5  241.16  4997.3  239.66
  5027.7  240.01  5055.1  239.46  5057.9  238.96  5061.1  239.46  5088.6  239.86
  5108.9  241.18  5179.9  243.89    5294  245.53  5605.5  256.11  5662.3  256.99
  5697.4  258.48  5725.8  258.37  5747.5  260.14  5804.3  260.52  5856.4  262.12
#Mann= 4 ,-1 , 0
  3862.1      .1       0  3988.4     .05       0  5055.1     .03       0
  5061.1     .05       0
Bank Sta=4946.5,5108.9
XS Rating Curve= 0 ,0
Exp/Cntr=0.3,0.1

Type RM Length L Ch R = 1 ,15687   ,553,553,553
BEGIN DESCRIPTION:
UNT034 IN NURI 24.0
END DESCRIPTION:
XS GIS Cut Line= 3
      2302959.91     13326312.95      2301649.19     13326269.55
      2301060.84     13326083.53
#Sta/Elev= 30
    3867  254.58  3979.3  252.72  4159.4  247.91  4369.5  244.84  4439.5  244.87
  4449.5  244.24  4499.5  243.15  4509.5  243.82  4609.6  243.58  4679.6  241.17
  4789.7  239.42  4859.7  238.77  4919.8  239.33  4969.8  239.06  4996.8  238.38
  4999.6  237.88  5002.8  238.38  5059.8  239.14  5106.8   239.5  5176.7  241.43
  5221.9  241.99  5326.8  244.91  5410.7  248.45  5463.2  248.82  5538.7  251.67
  5662.4  254.53  5714.9  256.82  5770.2  258.53  5777.8  259.74  5795.5  259.74
#Mann= 3 ,-1 , 0
    3867     .05       0  4996.8     .03       0  5002.8     .05       0
#XS Ineff= 1 ,-1
 4724.61 4919.92   239.2
Permanent Ineff=
       F
Bank Sta=4969.8,5059.8
XS Rating Curve= 0 ,0
Exp/Cntr=0.3,0.1

Type RM Length L Ch R = 1 ,15134   ,471,471,471
BEGIN DESCRIPTION:
UNT034 IN NURI 23.0
END DESCRIPTION:
XS GIS Cut Line= 3
      2303064.16     13326226.17      2302208.92     13325909.58
      2301563.28     13325601.58
#Sta/Elev= 30
  3781.5  254.23  3970.9  251.45  4204.2   246.5  4214.9  246.94  4406.8  243.74
  4680.9  241.11  4824.9  238.23  4847.6  238.65  4853.1  237.94  4898.5  236.75
  4915.6   237.4  4943.9  237.16  4966.6  236.03    5005  235.71  5011.9   236.6
  5037.2  235.64  5039.9  235.14  5043.2  235.64  5093.7  237.66  5130.9  238.77
  5148.1  240.37  5153.7  239.68  5160.1  240.79  5215.5  243.64  5227.3  244.97
  5267.1  246.93    5282  248.69  5312.5  249.91  5347.3  252.53  5408.8  255.42
#Mann= 6 ,-1 , 0
  3781.5     .05       0  4680.9      .1       0  5037.2     .07       0
  5043.2      .1       0  5153.7     .05       0  5347.3      .1       0
Bank Sta=4943.9,5093.7
XS Rating Curve= 0 ,0
Exp/Cntr=0.3,0.1

Type RM Length L Ch R = 1 ,14663   ,775,775,775
BEGIN DESCRIPTION:
UNT034 IN NURI 22.0
END DESCRIPTION:
XS GIS Cut Line= 3
      2302848.87     13325979.63      2301859.25     13325120.23
      2301663.91     13325137.59
#Sta/Elev= 30
  4142.9  247.67  4394.2  243.23  4430.5  242.91  4532.4   241.4  4542.2  241.83
  4570.7  240.32  4621.1  239.88  4769.2  236.35    4847  236.32  4875.5  235.63
  4889.8  234.17  4911.6  235.03  4939.1  233.18  4946.8  233.12  4953.4  234.41
  4975.3  234.71  4987.8  234.06  4993.1  232.71  4995.9  232.21  4999.1  232.71
  5011.1  233.73  5024.6  234.75  5081.6  235.67  5202.2  240.06  5208.8  239.64
  5265.8  241.47  5336.4  241.95  5386.4  243.68  5525.4   245.2  5649.7  248.07
#Mann= 8 ,-1 , 0
  4142.9     .05       0  4394.2      .1       0  4430.5     .05       0
  4532.4      .1       0  4987.8     .05       0  4993.1     .04       0
  4999.1     .05       0  5011.1      .1       0
Bank Sta=4875.5,5081.6
XS Rating Curve= 0 ,0
Exp/Cntr=0.3,0.1

Type RM Length L Ch R = 1 ,13888   ,537,537,537
BEGIN DESCRIPTION:
UNT034 IN NURI 21.0
END DESCRIPTION:
XS GIS Cut Line= 3
      2302987.77     13324846.86      2302158.73     13324799.05
      2301812.12     13324959.36
#Sta/Elev= 30
  4637.6  250.57  4657.7  250.53  4667.7  249.03  4717.8  246.59  4723.6  245.53
  4747.8  243.84    4868  237.39  4888.1  236.01  4895.6  234.88  4928.1  233.71
  4958.2  231.38  4978.2  231.11  4995.2  230.02    4998  229.52  5001.2  230.02
  5008.3  230.67  5028.3  230.54  5048.3  231.31  5058.3  230.64  5118.4  231.84
  5218.6  234.49  5244.6   235.8    5449  236.74  5520.5   238.4    5526  237.59
  5663.6  240.71  5722.5  241.56  5737.9  241.08  5760.8  242.09  5849.9  243.75
#Mann= 3 ,-1 , 0
  4637.6      .1       0  4995.2     .07       0  5001.2      .1       0
Bank Sta=4958.2,5048.3
XS Rating Curve= 0 ,0
Exp/Cntr=0.3,0.1

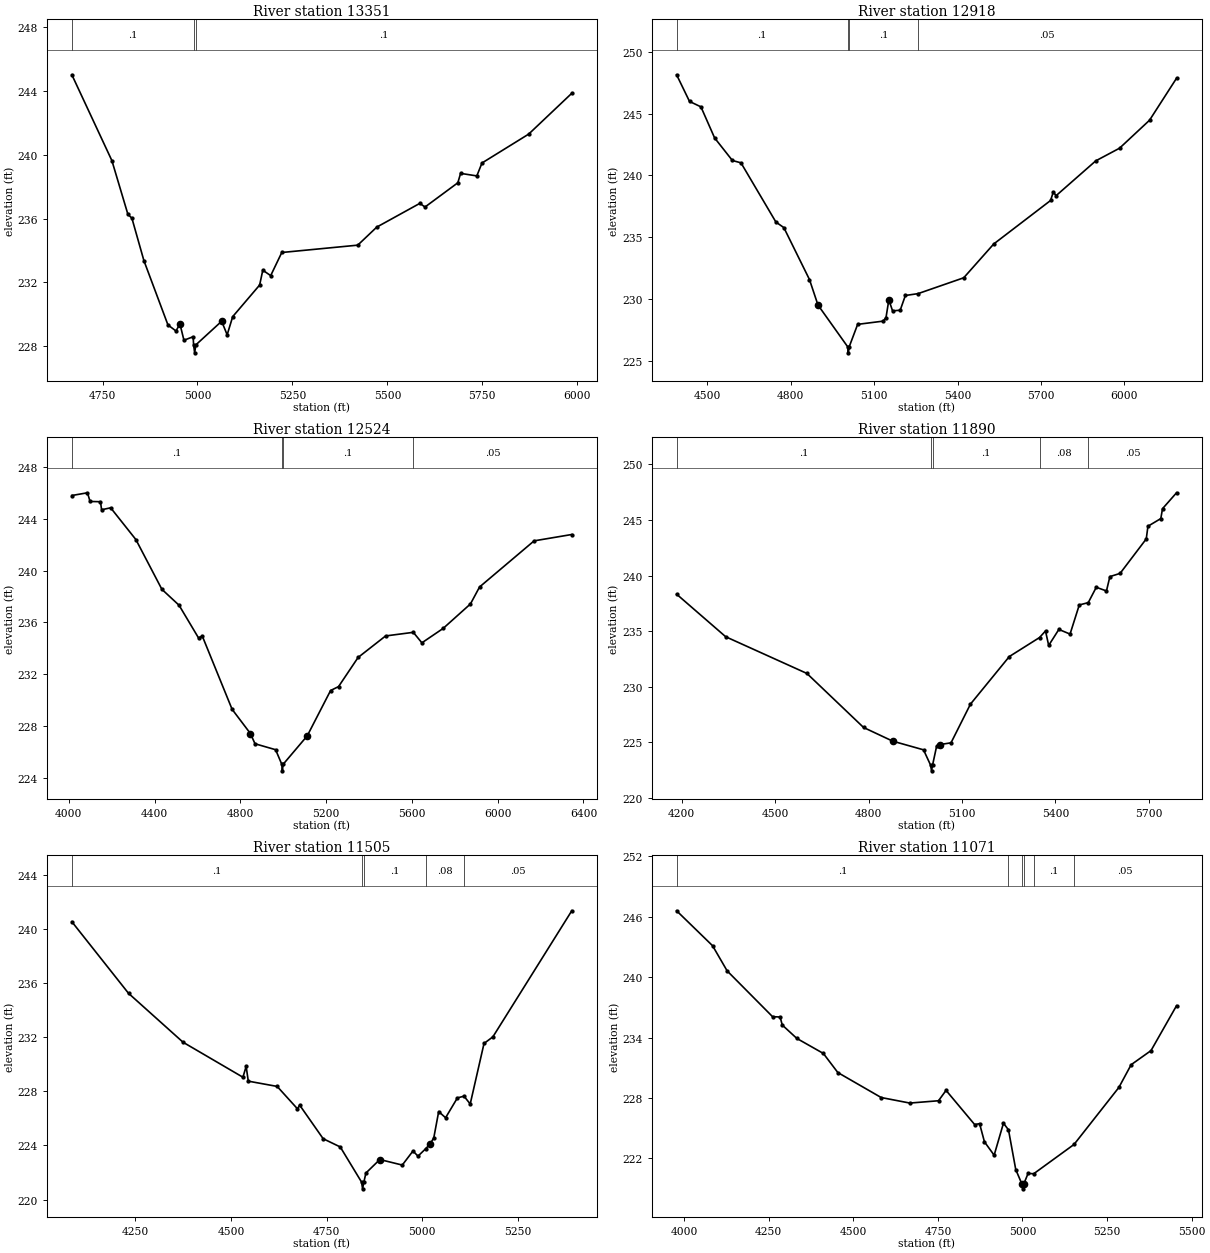
Type RM Length L Ch R = 1 ,13351   ,433,433,433
BEGIN DESCRIPTION:
UNT034 IN NURI 20.0
END DESCRIPTION:
XS GIS Cut Line= 3
      2302887.72     13324196.86      2302587.72     13324296.85
      2301787.74     13324896.84
#Sta/Elev= 30
  4669.2  245.02  4774.6  239.64  4816.8  236.27  4827.3  236.03  4858.9  233.37
  4922.2  229.34  4943.3  228.96  4953.8   229.4  4964.3  228.38  4988.6   228.6
  4989.7  228.09  4992.5  227.59  4995.7  228.09  5063.6  229.57  5078.1  228.72
  5092.7  229.86  5163.6  231.84  5171.9  232.77  5192.7  232.43  5221.9  233.88
  5421.9  234.34  5471.9  235.47  5585.4  236.96    5599  236.73  5685.4  238.25
  5692.7  238.84  5735.4  238.68    5749  239.49  5871.9   241.3  5985.4  243.86
#Mann= 3 ,-1 , 0
  4669.2      .1       0  4989.7     .07       0  4995.7      .1       0
Bank Sta=4953.8,5063.6
XS Rating Curve= 0 ,0
Exp/Cntr=0.3,0.1

Type RM Length L Ch R = 1 ,12918   ,394,394,394
BEGIN DESCRIPTION:
UNT034 IN NURI 19.0
END DESCRIPTION:
XS GIS Cut Line= 4
      2303052.83      13323974.4      2302636.16     13323874.57
      2301672.62     13324065.54      2301364.46     13324299.92
#Sta/Elev= 30
  4389.4  248.13  4435.8  245.98  4476.9  245.54  4526.1  243.03    4590  241.21
  4620.9  241.02  4746.5  236.24  4775.1  235.79  4867.2   231.6  4897.8  229.54
  5004.3  226.18    5007  225.68  5010.3  226.18  5040.5  227.98  5132.3  228.24
  5142.5  228.53  5152.7  229.96    5166  229.07  5193.5  229.12  5212.1  230.31
  5257.7  230.46    5422  231.74  5529.9  234.47  5734.3  237.98    5744  238.66
  5754.2  238.37  5896.8  241.18  5982.2   242.2  6090.2  244.46  6187.3  247.85
#Mann= 4 ,-1 , 0
  4389.4      .1       0  5004.3     .07       0  5010.3      .1       0
  5257.7     .05       0
Bank Sta=4897.8,5152.7
XS Rating Curve= 0 ,0
Exp/Cntr=0.3,0.1

Type RM Length L Ch R = 1 ,12524   ,634,634,634
BEGIN DESCRIPTION:
UNT034 IN NURI 18.0
END DESCRIPTION:
XS GIS Cut Line= 3
      2303287.19     13323878.91       2301909.6     13323361.57
      2301288.91     13323956.22
#Sta/Elev= 30
  4014.3  245.79  4087.2     246  4099.2  245.33  4147.7  245.31    4153  244.69
  4195.3  244.84  4312.8  242.39  4434.1  238.55  4514.2  237.32  4604.9   234.8
  4622.6  234.94  4761.5  229.29  4846.9  227.42  4868.3  226.63  4964.4  226.17
  4993.3  225.04    4996  224.54  4999.3  225.04  5111.9  227.24  5220.8  230.74
  5257.8  231.04    5349  233.29  5477.2  234.95  5606.4  235.23  5646.5  234.42
  5745.5  235.53  5872.9  237.42  5915.4  238.73  6169.8  242.29  6345.4  242.78
#Mann= 4 ,-1 , 0
  4014.3      .1       0  4993.3     .07       0  4999.3      .1       0
  5606.4     .05       0
Bank Sta=4846.9,5111.9
XS Rating Curve= 0 ,0
Exp/Cntr=0.3,0.1

Type RM Length L Ch R = 1 ,11890   ,385,385,385
BEGIN DESCRIPTION:
UNT034 IN NURI 17.0
END DESCRIPTION:
XS GIS Cut Line= 3
       2303256.8      13323188.8      2302137.03     13322802.52
      2301751.72     13322633.68
#Sta/Elev= 30
  4183.7  238.33  4341.4   234.5  4602.1   231.2    4784  226.34  4877.6  225.11
  4976.5  224.33  4999.4  222.94  5002.2  222.44  5005.4  222.94  5018.4  224.63
  5028.3   224.8  5064.8  224.96  5127.2  228.44    5252  232.72    5349  234.43
  5368.2  235.02  5378.4  233.72  5411.1  235.16    5447  234.74  5476.6  237.36
  5505.5  237.57  5531.2  238.95  5563.9  238.62  5574.9  239.91  5607.7   240.2
  5691.7   243.3  5697.1  244.44  5738.4  245.13  5743.9  246.02  5788.9  247.45
#Mann= 5 ,-1 , 0
  4183.7      .1       0  4999.4     .07       0  5005.4      .1       0
    5349     .08       0  5505.5     .05       0
Bank Sta=4877.6,5028.3
XS Rating Curve= 0 ,0
Exp/Cntr=0.3,0.1

Type RM Length L Ch R = 1 ,11505   ,434,434,434
BEGIN DESCRIPTION:
UNT034 IN NURI 16.0
END DESCRIPTION:
XS GIS Cut Line= 3
      2303337.75     13322946.87      2302537.72     13322546.85
      2302137.69     13322446.85
#Sta/Elev= 30
  4084.3  240.56  4232.5  235.26    4375  231.64  4531.5  229.05  4539.9  229.85
  4545.5  228.76    4621  228.37  4674.1  226.71  4679.7  226.99  4741.2   224.5
  4785.9  223.89  4841.6  221.29  4844.3  220.79  4847.6  221.29    4853  221.96
  4889.3  222.96    4948  222.55    4976  223.59  4989.1  223.21  5008.9  223.75
    5020  224.09  5030.3  224.55  5043.2  226.51  5061.2  226.05  5092.1  227.52
  5109.4  227.65  5125.6  227.07  5161.7  231.55  5184.9  232.04  5391.1  241.37
#Mann= 5 ,-1 , 0
  4084.3      .1       0  4841.6     .07       0  4847.6      .1       0
  5008.9     .08       0  5109.4     .05       0
Bank Sta=4889.3,5020
XS Rating Curve= 0 ,0
Exp/Cntr=0.3,0.1

Type RM Length L Ch R = 1 ,11071   ,466,466,466
BEGIN DESCRIPTION:
UNT034 IN NURI 15.0
END DESCRIPTION:
XS GIS Cut Line= 3
      2303537.69     13322846.83      2302737.72     13322196.85
      2302337.68     13321996.83
#Sta/Elev= 30
  3977.4   246.6  4083.7  243.13  4126.8  240.63  4261.1  236.08  4283.4  236.05
  4289.8  235.25  4332.9  233.92  4411.2  232.43  4454.1  230.53  4582.2  228.05
  4666.9   227.5  4751.7  227.73    4774  228.76  4858.7  225.36  4873.1  225.46
  4887.5  223.65  4916.2  222.32  4943.7   225.5  4958.6  224.84  4980.1  220.89
    4998  219.48  5000.7  218.98    5004  219.48  5016.5  220.51  5033.2  220.48
  5152.4  223.39  5284.9  229.05  5321.2  231.31  5379.9  232.71  5455.4  237.17
#Mann= 6 ,-1 , 0
  3977.4      .1       0  4958.6     .08       0    4998     .07       0
    5004     .08       0  5033.2      .1       0  5152.4     .05       0
Bank Sta=4998,5004
XS Rating Curve= 0 ,0
Exp/Cntr=0.3,0.1

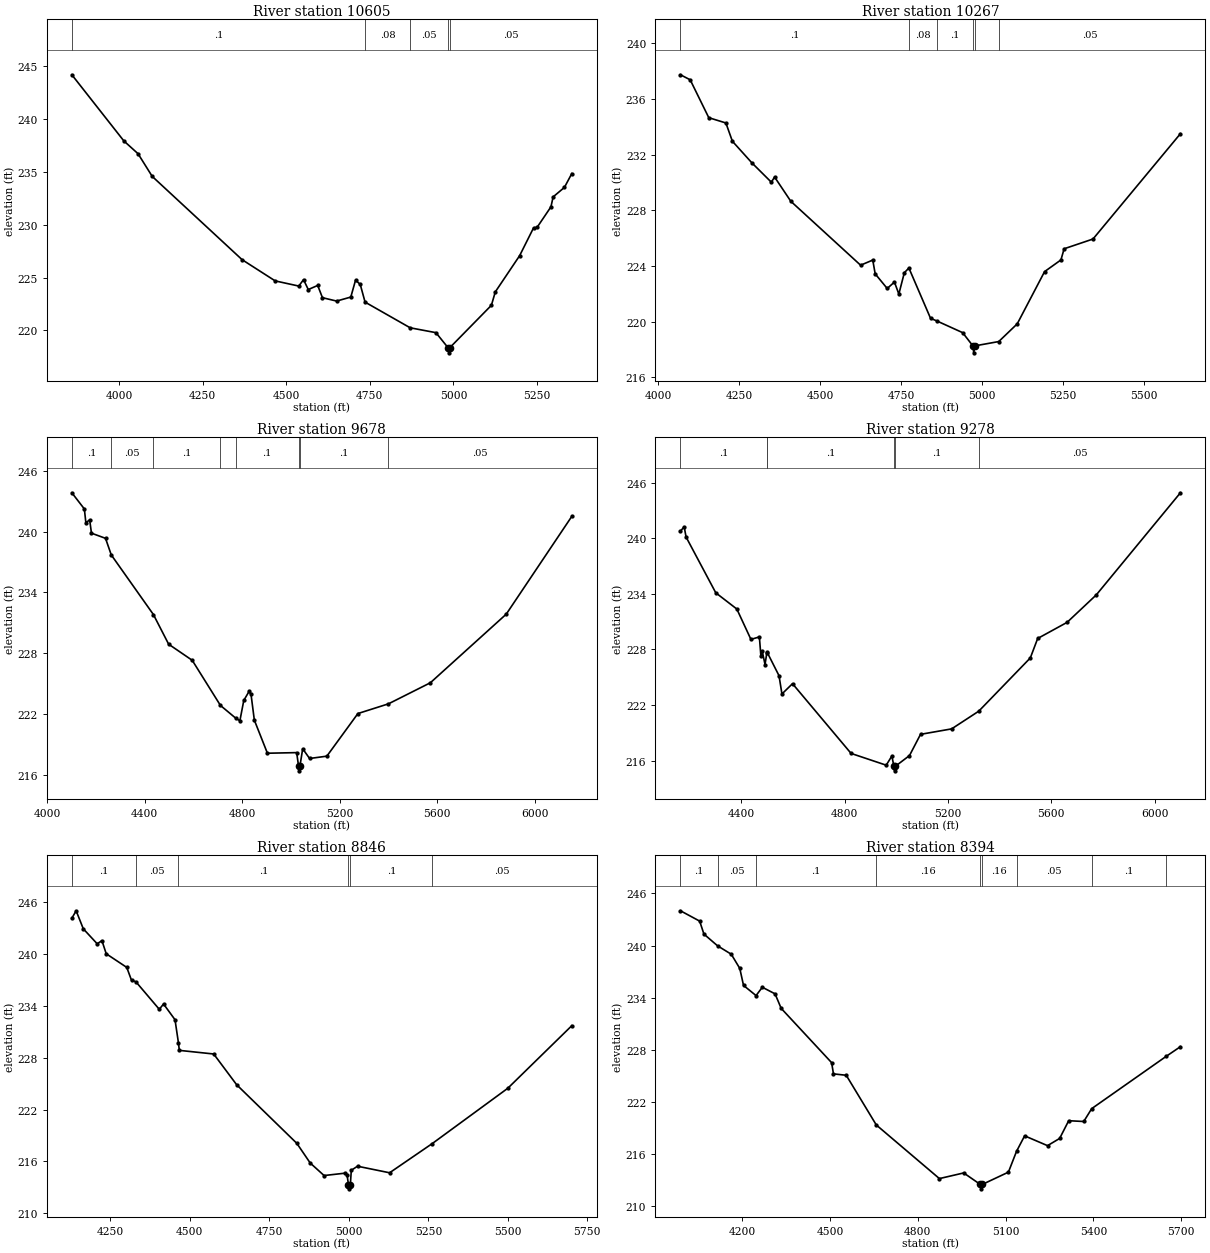
Type RM Length L Ch R = 1 ,10605   ,338,338,338
BEGIN DESCRIPTION:
UNT034 IN NURI 14.0
END DESCRIPTION:
XS GIS Cut Line= 3
      2303637.69     13322546.82      2302837.72     13321746.85
      2302487.75     13321646.86
#Sta/Elev= 30
  3858.8  244.19  4014.3  237.93  4056.7  236.72  4099.2  234.57  4367.9  226.69
  4466.9  224.68  4537.6  224.19  4551.7   224.8  4565.9  223.86  4594.1  224.25
  4608.3  223.09  4650.7  222.77  4693.1  223.15  4707.3  224.75  4721.4  224.34
  4735.8  222.67  4870.7  220.24  4947.7  219.78  4983.6  218.37  4986.3  217.87
  4989.6  218.37  5113.6  222.37  5125.3  223.64  5198.1  227.07  5239.7   229.7
  5250.1  229.74  5291.7  231.69  5298.2  232.63    5332  233.53  5354.1  234.84
#Mann= 5 ,-1 , 0
  3858.8      .1       0  4735.8     .08       0  4870.7     .05       0
  4983.6     .03       0  4989.6     .05       0
Bank Sta=4983.6,4989.6
XS Rating Curve= 0 ,0
Exp/Cntr=0.3,0.1

Type RM Length L Ch R = 1 ,10267   ,589,589,589
BEGIN DESCRIPTION:
UNT034 IN NURI 13.0
END DESCRIPTION:
XS GIS Cut Line= 4
      2303887.72     13321696.85      2303419.13     13321670.66
      2302692.56     13321313.89      2302437.35      13321381.6
#Sta/Elev= 30
  4069.3  237.73  4099.3  237.37  4156.7  234.65  4209.5  234.27  4229.5  232.96
  4289.6  231.41  4349.7  230.02  4359.8  230.39  4409.8  228.65  4625.2  224.06
  4662.7  224.43  4670.2  223.44  4707.3  222.39  4729.6  222.85  4743.2  221.99
  4760.1  223.52  4774.2  223.86    4841  220.25  4860.4  220.06    4940  219.22
  4971.7  218.27  4974.4  217.77  4977.7  218.27  5051.5  218.58  5108.5  219.85
  5192.9   223.6  5243.4  224.44  5253.2  225.24  5342.3  225.94  5612.1   233.5
#Mann= 6 ,-1 , 0
  4069.3      .1       0  4774.2     .08       0  4860.4      .1       0
  4971.7     .07       0  4977.7      .1       0  5051.5     .05       0
Bank Sta=4971.7,4977.7
XS Rating Curve= 0 ,0
Exp/Cntr=0.3,0.1

Type RM Length L Ch R = 1 ,9678    ,400,400,400
BEGIN DESCRIPTION:
UNT034 IN NURI 12.0
END DESCRIPTION:
XS GIS Cut Line= 3
      2304137.75     13321496.87      2303337.72     13321046.85
      2302537.71     13320246.85
#Sta/Elev= 30
  4102.1  243.84  4153.4  242.24  4159.5  240.89  4175.1  241.16  4182.5  239.85
  4240.1  239.34  4263.7   237.7  4436.4  231.81  4498.9  228.88  4595.5  227.29
  4711.2  222.83    4775  221.55  4790.9  221.32  4806.8  223.32  4828.5  224.22
  4836.4  223.95  4850.1  221.38  4903.7  218.11  5023.6  218.17  5031.2  216.87
  5033.9  216.37  5037.2  216.87  5048.3  218.55  5076.6  217.59  5147.3  217.82
  5274.6  222.03  5399.9  222.99  5571.6  225.07  5882.7  231.85  6151.4  241.51
#Mann= 8 ,-1 , 0
  4102.1      .1       0  4263.7     .05       0  4436.4      .1       0
  4711.2     .05       0    4775      .1       0  5031.2     .07       0
  5037.2      .1       0  5399.9     .05       0
Bank Sta=5031.2,5037.2
XS Rating Curve= 0 ,0
Exp/Cntr=0.3,0.1

Type RM Length L Ch R = 1 ,9278    ,432,432,432
BEGIN DESCRIPTION:
UNT034 IN NURI 11.0
END DESCRIPTION:
XS GIS Cut Line= 3
      2304237.74     13321046.86      2303437.72     13320696.85
      2302637.75     13319996.88
#Sta/Elev= 30
    4164  240.77  4178.4  241.24  4185.8  240.13  4300.8  234.11  4382.3  232.36
  4436.9  229.08  4469.6  229.35  4475.5  227.29  4480.9  227.78  4491.5  226.37
    4499  227.72  4500.3  227.66  4545.7  225.16    4557  223.19  4597.9   224.3
  4824.8  216.77  4960.8   215.5  4982.7  216.49  4990.6  215.39  4993.3  214.89
  4996.6  215.39    5051  216.54  5093.7  218.83  5214.2  219.42  5319.2  221.33
  5518.9  227.08  5547.4  229.18  5661.3  230.92  5774.2  233.88  6100.2  244.91
#Mann= 6 ,-1 , 0
    4164      .1       0    4499     .05       0  4500.3      .1       0
  4990.6     .07       0  4996.6      .1       0  5319.2     .05       0
Bank Sta=4990.6,4996.6
XS Rating Curve= 0 ,0
Exp/Cntr=0.3,0.1

Type RM Length L Ch R = 1 ,8846    ,452,452,452
BEGIN DESCRIPTION:
UNT034 IN NURI 10.0
END DESCRIPTION:
XS GIS Cut Line= 3
      2304437.68     13320846.83      2303687.72     13320346.85
      2303087.68     13320046.84
#Sta/Elev= 30
    4129  244.18  4142.5  245.04    4165  242.95  4208.6  241.22  4223.6  241.58
  4237.1  240.06  4301.7  238.48  4316.7  236.98  4330.3  236.82  4403.9  233.63
  4417.4  234.24  4453.4  232.42  4464.2  229.74    4467  228.87  4575.1  228.45
  4647.2  224.89  4836.5   218.1  4878.6  215.82  4922.2  214.37  4986.8  214.64
  4994.3  214.48  4998.8  213.33  5001.5  212.83  5004.8  213.33  5007.8  214.98
  5027.3  215.45  5128.2  214.69  5262.6  218.08  5499.9  224.48  5701.2  231.73
#Mann= 6 ,-1 , 0
    4129      .1       0  4330.3     .05       0  4464.2      .1       0
  4998.8     .07       0  5004.8      .1       0  5262.6     .05       0
Bank Sta=4998.8,5004.8
XS Rating Curve= 0 ,0
Exp/Cntr=0.3,0.1

Type RM Length L Ch R = 1 ,8394    ,405,405,405
BEGIN DESCRIPTION:
UNT034 IN NURI 9.0
END DESCRIPTION:
XS GIS Cut Line= 3
      2304678.73     13320518.71      2303975.57     13319980.49
      2303177.01     13319785.19
#Sta/Elev= 30
  3989.3     244  4054.9  242.81  4069.4  241.32  4115.9  239.97  4162.8     239
  4191.9  237.37  4204.7  235.41  4247.5  234.24  4268.9   235.2  4312.4  234.44
  4333.3  232.77  4505.6  226.52  4511.9  225.23  4555.5  225.07  4658.2  219.35
  4873.7  213.18  4956.7  213.83  5013.7   212.5  5016.5     212  5019.7   212.5
  5109.4  213.92  5137.2  216.32  5164.8   218.1    5243  216.97  5284.4   217.8
  5315.3  219.84  5366.7  219.75  5393.9  221.23  5648.4  227.25  5696.9  228.36
#Mann= 9 ,-1 , 0
  3989.3      .1       0  4115.9     .05       0  4247.5      .1       0
  4658.2     .16       0  5013.7     .07       0  5019.7     .16       0
  5137.2     .05       0  5393.9      .1       0  5648.4     .05       0
Bank Sta=5013.7,5019.7
XS Rating Curve= 0 ,0
Exp/Cntr=0.3,0.1