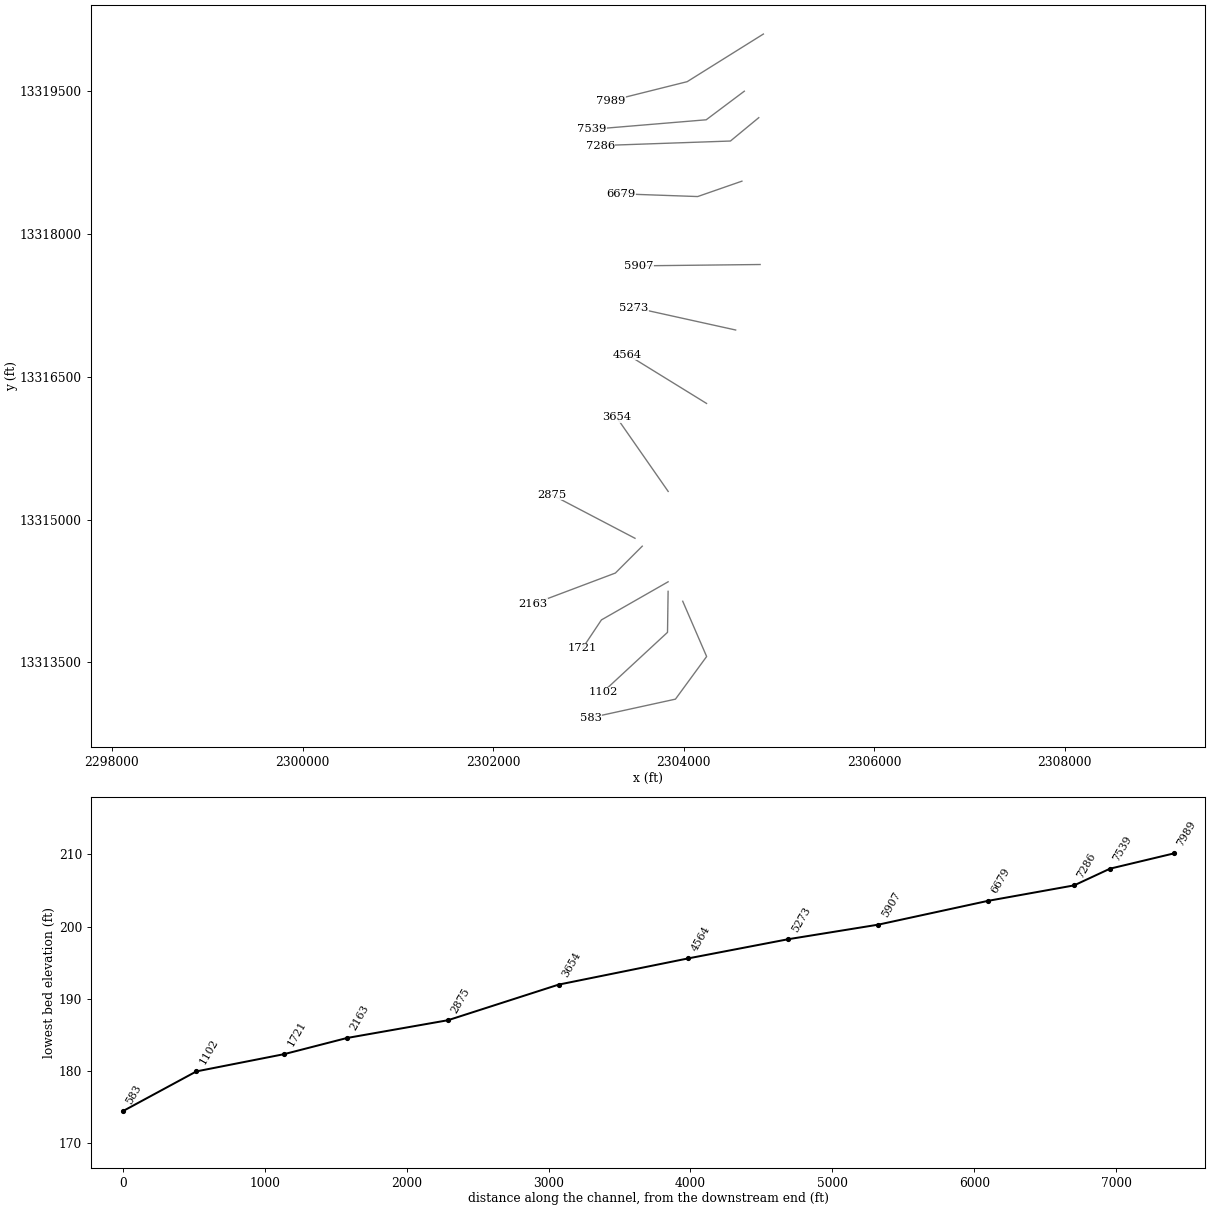
HEC-RAS study UNT034 IN NURI.prj: UNT034 IN NURI Base Level Engineering

--- UNT034 IN NURI.g01 (geometry) --- (continued)

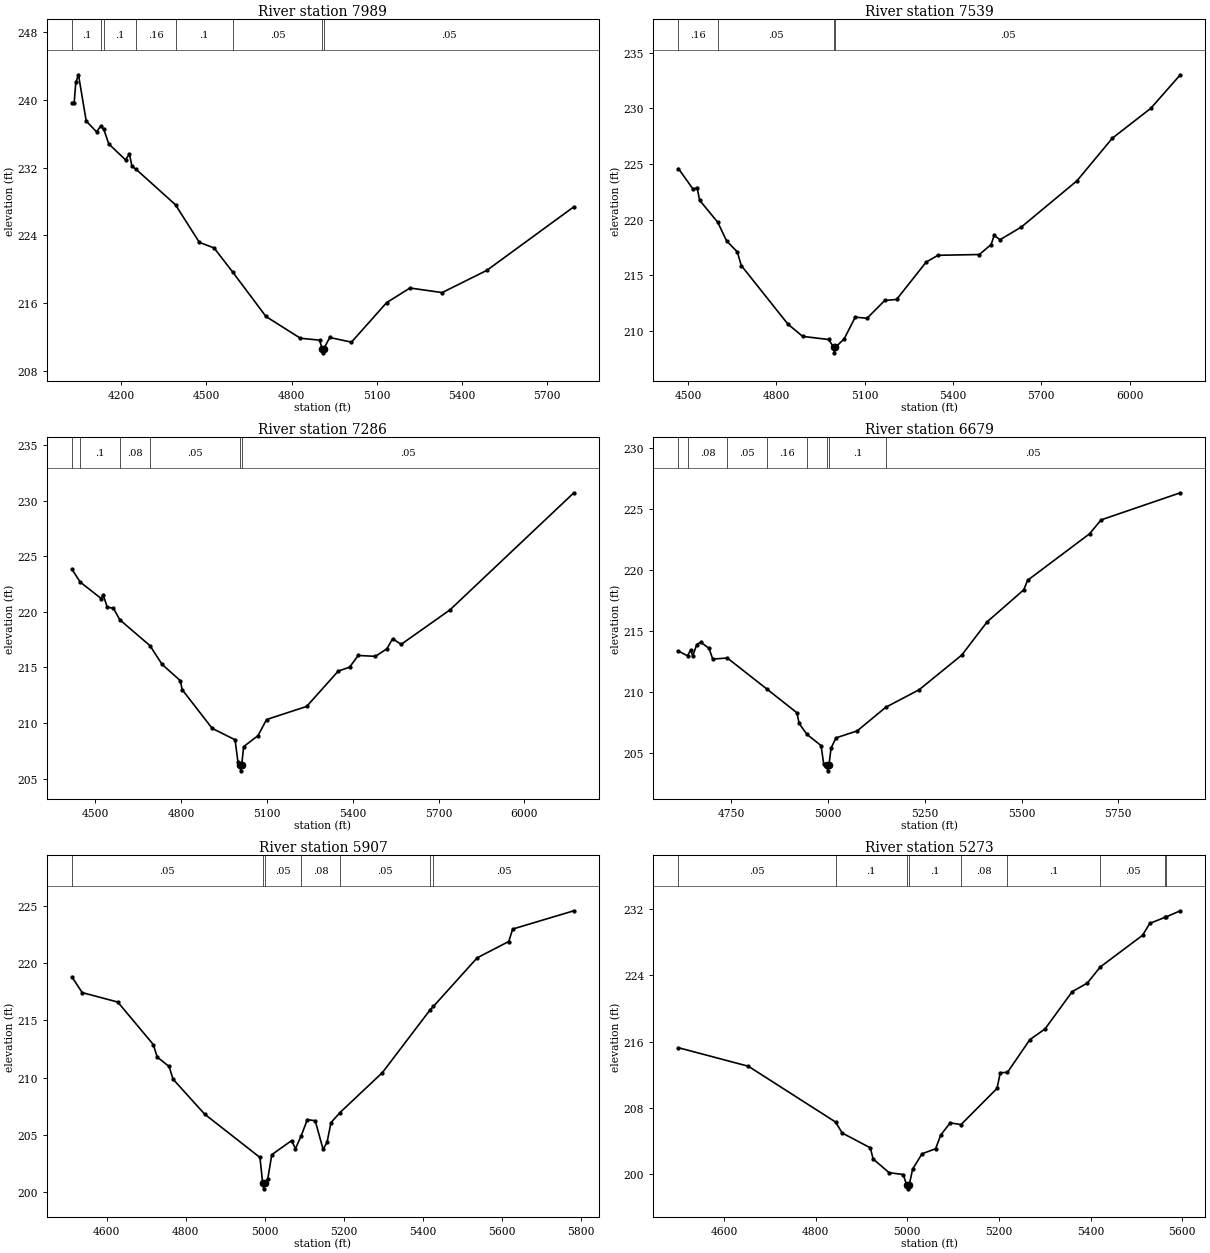
Type RM Length L Ch R = 1 ,7989    ,450,450,450
BEGIN DESCRIPTION:
UNT034 IN NURI 8.0
END DESCRIPTION:
XS GIS Cut Line= 3
      2304837.75     13320096.88      2304037.72     13319596.85
      2303237.68     13319396.84
#Sta/Elev= 30
  4026.5  239.67  4034.2  239.61  4040.1  242.06  4049.5  242.96  4076.7  237.51
  4113.2  236.22  4128.3  236.94  4138.6  236.52  4156.3   234.8  4215.2  232.92
  4228.8  233.61  4238.2  232.14  4252.3  231.81  4391.3  227.62  4475.2  223.19
  4527.1  222.53  4593.5  219.65  4709.9  214.44  4831.4  211.87  4898.6  211.65
    4908  210.65  4910.7  210.15    4914  210.65  4934.6  211.96  5011.2  211.41
  5134.9  216.07  5217.3   217.8  5330.7  217.26  5487.9  219.88  5794.6  227.38
#Mann= 8 ,-1 , 0
  4026.5      .1       0  4128.3     .05       0  4138.6      .1       0
  4252.3     .16       0  4391.3      .1       0  4593.5     .05       0
    4908     .03       0    4914     .05       0
Bank Sta=4908,4914
XS Rating Curve= 0 ,0
Exp/Cntr=0.3,0.1

Type RM Length L Ch R = 1 ,7539    ,253,253,253
BEGIN DESCRIPTION:
UNT034 IN NURI 7.0
END DESCRIPTION:
XS GIS Cut Line= 3
      2304637.73     13319496.86      2304237.72     13319196.85
      2303037.69     13319096.85
#Sta/Elev= 30
  4467.6   224.6  4517.6  222.74  4531.1  222.89  4539.5  221.75  4601.2  219.77
  4631.1   218.1  4667.6   217.1  4681.1  215.88  4839.5  210.61  4889.5  209.51
  4977.6  209.23  4994.7  208.53  4997.5  208.03  5000.7  208.53  5030.3  209.28
    5068  211.24  5108.1  211.14  5168.3  212.74  5208.4  212.83  5308.8  216.19
  5348.9   216.8  5489.4  216.87  5529.5  217.77  5539.6  218.58  5559.7   218.2
  5632.4  219.35  5820.6  223.49    5941  227.33  6071.4  230.01  6171.8  233.03
#Mann= 4 ,-1 , 0
  4467.6     .16       0  4601.2     .05       0  4994.7     .03       0
  5000.7     .05       0
Bank Sta=4994.7,5000.7
XS Rating Curve= 0 ,0
Exp/Cntr=0.3,0.1

Type RM Length L Ch R = 1 ,7286    ,607,607,607
BEGIN DESCRIPTION:
UNT034 IN NURI 6.0
END DESCRIPTION:
XS GIS Cut Line= 3
       2304789.4     13319219.03      2304492.12     13318973.83
       2303124.9     13318926.08
#Sta/Elev= 30
  4419.4  223.83    4448  222.68  4521.9  221.19  4528.4  221.53  4542.7  220.42
  4564.2  220.32  4586.8  219.28    4692  216.96  4734.2  215.28  4798.1  213.81
  4804.4  213.01  4909.2  209.53  4989.3   208.5  4999.3  206.52  5006.3  206.21
    5009  205.71  5012.3  206.21  5019.3  207.89  5069.3  208.87  5099.3  210.32
  5239.4   211.5  5349.5  214.67  5389.5  215.03  5419.5  216.08  5479.6     216
  5519.6  216.68  5539.6  217.58  5569.6  217.08  5739.7  220.17  6172.8   230.7
#Mann= 6 ,-1 , 0
  4419.4     .08       0    4448      .1       0  4586.8     .08       0
    4692     .05       0  5006.3     .03       0  5012.3     .05       0
Bank Sta=5006.3,5012.3
XS Rating Curve= 0 ,0
Exp/Cntr=0.3,0.1

Type RM Length L Ch R = 1 ,6679    ,772,772,772
BEGIN DESCRIPTION:
UNT034 IN NURI 5.0
END DESCRIPTION:
XS GIS Cut Line= 3
      2304612.37      13318552.4      2304147.93     13318390.93
      2303343.24     13318419.57
#Sta/Elev= 30
  4613.2  213.37  4636.7  212.98  4644.9  213.46  4650.2  212.96  4660.5   213.9
  4670.8  214.09  4692.2   213.6  4701.9  212.71  4739.6   212.8  4842.5  210.24
  4919.6  208.31  4925.1  207.44  4945.5  206.54  4981.8  205.63  4988.7   204.1
  4996.3  204.06    4999  203.56  5002.3  204.06  5007.6  205.42  5020.4  206.26
  5075.1  206.83  5149.2  208.77  5235.2   210.2  5345.3  213.04  5411.2  215.77
  5505.4  218.38  5515.4  219.16  5675.5  222.97  5705.5  224.11  5910.1  226.33
#Mann= 8 ,-1 , 0
  4613.2     .05       0  4636.7     .08       0  4739.6     .05       0
  4842.5     .16       0  4945.5      .1       0  4996.3     .07       0
  5002.3      .1       0  5149.2     .05       0
Bank Sta=4996.3,5002.3
XS Rating Curve= 0 ,0
Exp/Cntr=0.3,0.1

Type RM Length L Ch R = 1 ,5907    ,634,634,634
BEGIN DESCRIPTION:
Mapping XS 3e58d930
END DESCRIPTION:
XS GIS Cut Line= 2
      2304803.67     13317677.54      2303532.84     13317663.65
#Sta/Elev= 30
    4512  218.81  4537.9  217.44    4628  216.61    4718  212.89    4728  211.79
    4758  210.97    4768  209.86    4848   206.8    4988  203.01    4995  200.76
  4997.7  200.26    5001  200.76    5008  201.16    5018  203.25    5068  204.48
    5078  203.78  5092.7  204.92    5108  206.32    5128  206.22    5148  203.71
    5158  204.35    5168  206.06  5190.8  206.94    5298  210.43    5419  215.93
  5427.3  216.23    5538  220.48    5618  221.91    5628     223  5782.9   224.6
#Mann= 7 ,-1 , 0
    4512     .05       0    4995     .03       0    5001     .05       0
  5092.7     .08       0  5190.8     .05       0    5419      .1       0
  5427.3     .05       0
Bank Sta=4995,5001
XS Rating Curve= 0 ,0
Exp/Cntr=0.3,0.1

Type RM Length L Ch R = 1 ,5273    ,709,709,709
BEGIN DESCRIPTION:
Mapping XS d6a7f439
END DESCRIPTION:
XS GIS Cut Line= 2
      2304546.72     13316990.05      2303477.27     13317226.16
#Sta/Elev= 30
  4500.6  215.28  4653.2  213.04  4843.4  206.31    4858  204.98  4919.4  203.19
  4925.5  201.84  4960.4  200.19  4991.1  199.97  4998.4  198.74  5001.1  198.24
  5004.4  198.74  5011.6  200.61  5032.1  202.47  5061.7  203.08  5073.1  204.74
  5093.5   206.2  5117.3     206  5195.9  210.37  5202.9  212.26  5218.5   212.3
  5267.6  216.26  5300.5  217.54  5359.8  222.04    5393  223.09    5421  225.02
  5513.4  228.85  5529.1  230.28  5562.8  231.03  5564.7  231.07  5595.8  231.81
#Mann= 9 ,-1 , 0
  4500.6     .05       0  4843.4      .1       0  4998.4     .07       0
  5004.4      .1       0  5117.3     .08       0  5218.5      .1       0
    5421     .05       0  5562.8      .1       0  5564.7     .05       0
Bank Sta=4998.4,5004.4
XS Rating Curve= 0 ,0
Exp/Cntr=0.3,0.1

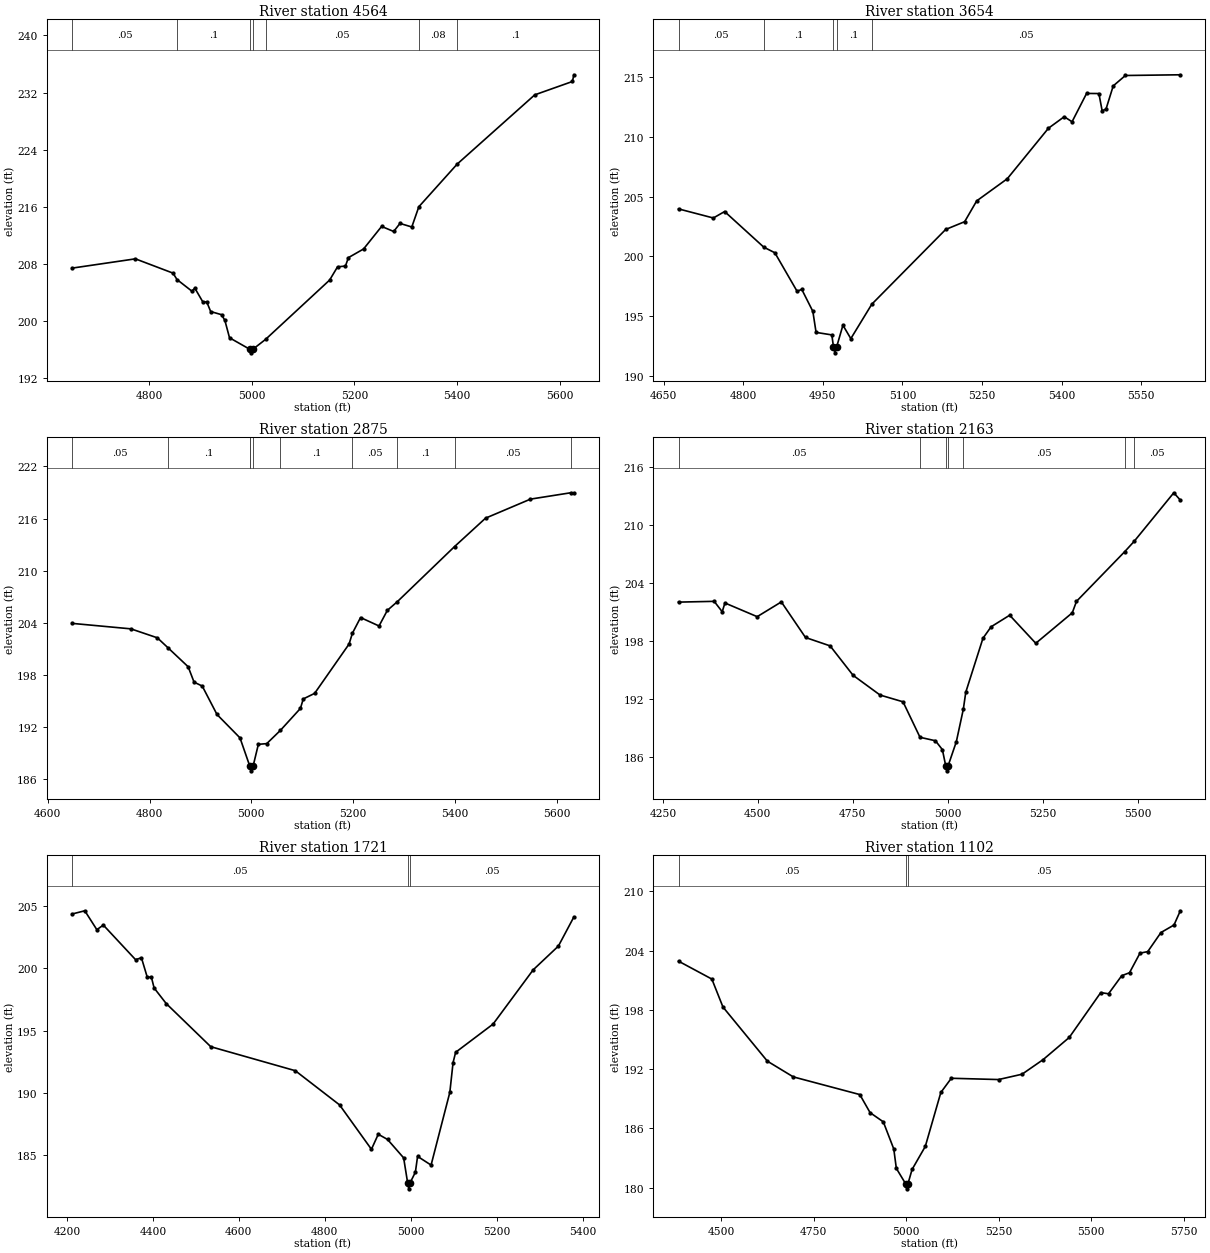
Type RM Length L Ch R = 1 ,4564    ,910,910,910
BEGIN DESCRIPTION:
Mapping XS 2d039005
END DESCRIPTION:
XS GIS Cut Line= 2
      2304241.18     13316219.22       2303408.9     13316732.45
#Sta/Elev= 30
  4649.8  207.42  4773.2  208.72  4846.5  206.72  4854.3  205.82  4883.2   204.2
  4889.1  204.61  4904.5   202.7  4912.3  202.68  4919.9  201.34  4941.2   200.9
  4947.6  200.09  4956.6  197.67  4996.1  196.06  4998.9  195.56  5002.1  196.06
  5026.8  197.44  5151.7  205.75  5167.1   207.6  5182.5  207.71  5188.3  208.89
  5217.8   210.1    5253  213.26  5276.5  212.55  5288.8  213.68  5311.8  213.18
  5325.5  216.01  5400.3  221.99  5551.4  231.68  5624.8  233.55  5627.6  234.49
#Mann= 7 ,-1 , 0
  4649.8     .05       0  4854.3      .1       0  4996.1     .07       0
  5002.1      .1       0  5026.8     .05       0  5325.5     .08       0
  5400.3      .1       0
Bank Sta=4996.1,5002.1
XS Rating Curve= 0 ,0
Exp/Cntr=0.3,0.1

Type RM Length L Ch R = 1 ,3654    ,779,779,779
BEGIN DESCRIPTION:
Mapping XS 7bfef426
END DESCRIPTION:
XS GIS Cut Line= 2
      2303838.45     13315295.55      2303297.82     13316071.85
#Sta/Elev= 30
  4677.9  203.97  4743.5  203.21  4764.8  203.75  4838.6  200.77  4859.5   200.3
  4901.4  197.08  4910.2  197.24  4931.1   195.4  4937.2  193.64  4966.9  193.43
    4970  192.43  4972.7  191.93    4976  192.43  4987.8  194.24  5002.7  193.12
  5042.3     196  5181.5  202.25  5217.3   202.9    5240  204.64  5297.6  206.49
  5375.3  210.72    5405  211.68  5419.8  211.26  5447.2  213.63  5470.4  213.62
  5476.5  212.18  5483.8  212.32  5497.4  214.26  5520.3  215.13  5623.9  215.19
#Mann= 5 ,-1 , 0
  4677.9     .05       0  4838.6      .1       0    4970     .07       0
    4976      .1       0  5042.3     .05       0
Bank Sta=4970,4976
XS Rating Curve= 0 ,0
Exp/Cntr=0.3,0.1

Type RM Length L Ch R = 1 ,2875    ,712,712,712
BEGIN DESCRIPTION:
UNT034 IN NURI 4.1
END DESCRIPTION:
XS GIS Cut Line= 2
       2303490.2     13314803.64      2302616.18     13315260.88
#Sta/Elev= 30
  4647.7  203.95  4763.4  203.32  4815.3  202.29  4836.7  201.12  4875.9  198.96
  4887.5  197.19  4903.6  196.74  4932.6  193.47  4977.8  190.78  4997.2  187.51
  4997.4  187.49  5000.1  186.99  5003.4  187.49  5013.9  190.04  5030.4  190.12
    5057  191.63  5096.6  194.17  5102.2  195.26  5124.5   195.9  5192.2  201.57
  5198.8  202.82  5214.8  204.62  5251.1  203.65  5267.5  205.45    5287  206.44
  5399.5  212.78  5460.5  216.05  5548.8  218.24  5627.8  218.97  5634.1  218.95
#Mann= 10 ,-1 , 0
  4647.7     .05       0  4836.7      .1       0  4997.2     .16       0
  4997.4     .07       0  5003.4     .16       0    5057      .1       0
  5198.8     .05       0    5287      .1       0  5399.5     .05       0
  5627.8      .1       0
Bank Sta=4997.4,5003.4
XS Rating Curve= 0 ,0
Exp/Cntr=0.3,0.1

Type RM Length L Ch R = 1 ,2163    ,442,442,442
BEGIN DESCRIPTION:
UNT034 IN NURI 4.0
END DESCRIPTION:
XS GIS Cut Line= 3
      2303566.35     13314720.92      2303284.24     13314438.82
      2302421.63     13314113.71
#Sta/Elev= 30
  4291.2  202.02    4385   202.1  4406.2  201.02  4413.3  201.93  4498.2  200.51
  4561.8  202.04  4625.4  198.35  4690.2  197.48  4750.6  194.43  4821.7  192.38
  4882.1  191.68  4926.8     188  4967.4  187.64  4985.7  186.72  4994.6  185.02
  4997.3  184.52  5000.6  185.02  5022.4  187.54  5040.8  190.91  5047.3  192.68
  5092.5  198.27  5113.9  199.46  5162.8  200.66  5231.5  197.75  5327.6  200.91
  5338.7   202.1  5465.8  207.26  5490.2  208.31  5594.8  213.36    5612   212.6
#Mann= 7 ,-1 , 0
  4291.2     .05       0  4926.8      .1       0  4994.6     .07       0
  5000.6      .1       0  5040.8     .05       0  5465.8      .1       0
  5490.2     .05       0
Bank Sta=4994.6,5000.6
XS Rating Curve= 0 ,0
Exp/Cntr=0.3,0.1

Type RM Length L Ch R = 1 ,1721    ,619,619,619
BEGIN DESCRIPTION:
UNT034 IN NURI 3.0
END DESCRIPTION:
XS GIS Cut Line= 3
      2303837.75     13314346.87      2303137.72     13313946.85
      2302937.73     13313646.87
#Sta/Elev= 30
  4212.2  204.38  4241.8  204.64  4269.8  203.12  4284.9  203.49  4359.8  200.71
  4373.5  200.86  4387.2  199.28  4396.5  199.32    4403  198.43  4431.1  197.18
  4534.7  193.71  4731.2  191.78  4834.2  189.03  4908.3  185.46  4924.2  186.67
  4945.8  186.25  4983.2  184.77  4992.4  182.78  4995.2  182.28  4998.4  182.78
  5010.5  183.62  5015.6  184.89    5047  184.19  5090.6  190.04  5098.1  192.43
  5104.1  193.26  5191.2  195.53  5284.4  199.89    5343   201.8    5379  204.14
#Mann= 3 ,-1 , 0
  4212.2     .05       0  4992.4     .03       0  4998.4     .05       0
Bank Sta=4992.4,4998.4
XS Rating Curve= 0 ,0
Exp/Cntr=0.3,0.1

Type RM Length L Ch R = 1 ,1102    ,519,519,519
BEGIN DESCRIPTION:
UNT034 IN NURI 2.0
END DESCRIPTION:
XS GIS Cut Line= 3
      2303837.72     13314246.85      2303831.48     13313816.43
      2303152.61     13313187.93
#Sta/Elev= 30
  4385.1  202.92  4475.1  201.11  4505.1  198.28  4625.1   192.8  4695.1  191.21
  4874.8  189.42  4902.6  187.59  4938.3  186.66  4966.6  183.91  4973.5  181.95
  4998.8  180.38  5001.5  179.88  5004.8  180.38    5016  181.84  5051.7  184.17
  5093.7  189.63    5122  191.07  5249.6  190.94  5313.1  191.48  5369.8  192.95
  5440.6   195.2  5525.7  199.74  5546.7  199.62  5582.4  201.45  5603.4  201.75
  5631.7  203.73  5652.7  203.89  5688.4  205.82  5723.6  206.58  5740.7  208.02
#Mann= 3 ,-1 , 0
  4385.1     .05       0  4998.8     .03       0  5004.8     .05       0
Bank Sta=4998.8,5004.8
XS Rating Curve= 0 ,0
Exp/Cntr=0.3,0.1

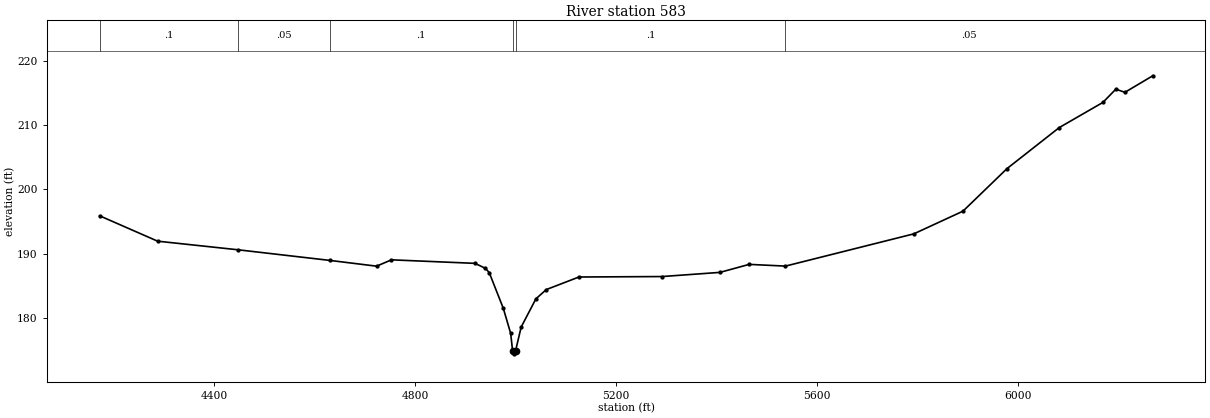
Type RM Length L Ch R = 1 ,583     ,0,0,0
BEGIN DESCRIPTION:
UNT034 IN NURI 1.0
END DESCRIPTION:
XS GIS Cut Line= 4
      2303991.18     13314142.86      2304242.14     13313562.44
      2303914.81     13313115.04      2303025.93      13312920.6
#Sta/Elev= 30
  4171.5  195.89    4287  191.93  4446.6  190.59  4629.8  188.93  4722.8  188.03
  4752.5  189.02  4918.7  188.47  4939.6  187.69  4947.1  187.03  4975.1  181.46
  4989.8  177.55  4993.6  174.85  4996.4  174.35  4999.6  174.85  5010.7  178.53
    5040  182.93  5060.8  184.38  5125.7  186.34  5290.9  186.41  5406.4  187.06
  5464.7  188.31  5536.8  188.04  5792.3  193.07  5890.2  196.61    5978  203.26
    6082  209.66  6168.8  213.58  6194.6  215.65  6212.7  215.16  6268.1  217.74
#Mann= 6 ,-1 , 0
  4171.5      .1       0  4446.6     .05       0  4629.8      .1       0
  4993.6     .07       0  4999.6      .1       0  5536.8     .05       0
Bank Sta=4993.6,4999.6
XS Rating Curve= 0 ,0
Exp/Cntr=0.3,0.1

Chan Stop Cuts=-1
Use User Specified Reach Order=0
Composite Channel Slope=5