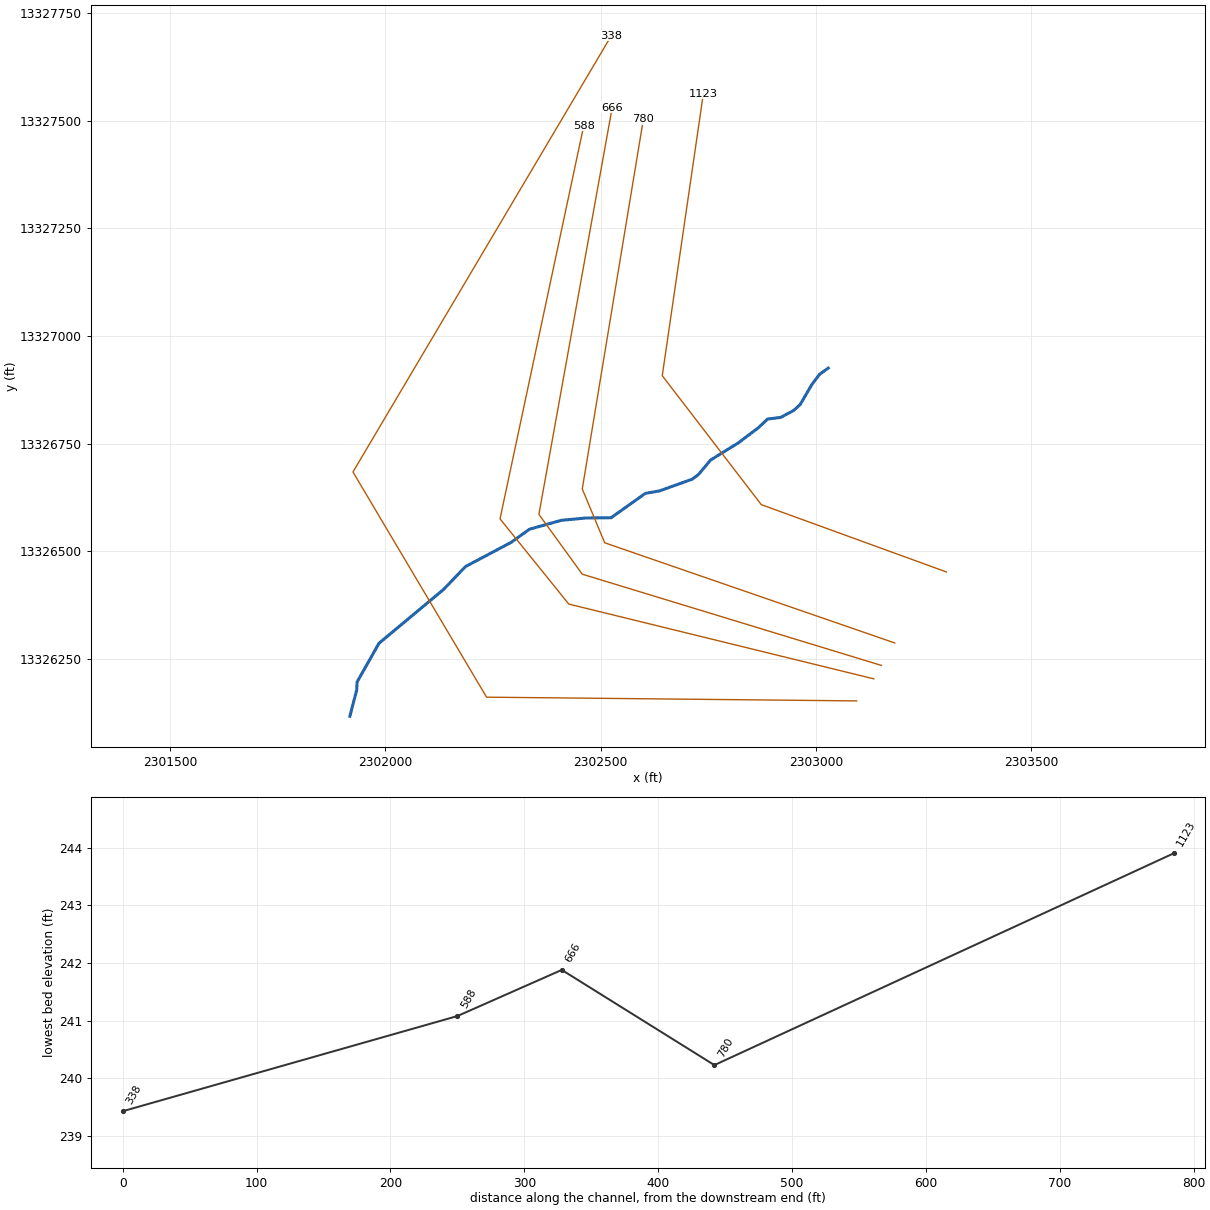
--- UNT035 IN NURI.prj (project) ---

Proj Title=UNT035 IN NURI Base Level Engineering
Current Plan=p01
Default Exp/Contr=0.3,0.1
English Units
Geom File=g01
Flow File=f01
Plan File=p01
Y Axis Title=Elevation
X Axis Title(PF)=Main Channel Distance
X Axis Title(XS)=Station
BEGIN DESCRIPTION:
UNT035 IN NURI
END DESCRIPTION:
DSS Export Rating Curves= 0
DSS Export Rating Curve Sorted= 0
DSS Export Volume Flow Curves= 0
DXF OffsetX= 0
DXF OffsetY= 0
DXF ScaleX= 1
DXF ScaleY= 10

--- UNT035 IN NURI.p01 (plan) ---

Plan Title=Multiple Run
Short Identifier=Multiple
Geom File=g01
Flow File=f01
Subcritical Flow
K Sum by GR= 0
Std Step Tol= 0.01
Critical Tol= 0.01
Num of Std Step Trials= 20
Max Error Tol= 0.3
Flow Tol Ratio= 0.001
Split Flow NTrial= 30
Split Flow Tol= 0.02
Split Flow Ratio= 0.02
Log Output Level= 0
Friction Slope Method= 1
Unsteady Friction Slope Method= 2
Unsteady Bridges Friction Slope Method= 1
Parabolic Critical Depth
Global Vel Dist=  1 , 1 , 1
Global Log Level= 0
CheckData=True
Encroach Param= -1, 0, 0, 0
BEGIN DESCRIPTION:
Multiple Run
END DESCRIPTION:

--- UNT035 IN NURI.f01 (steady flow) ---

Flow Title=Multiple
Number of Profiles=7
Profile Names=10-year,25-year,50-year,1pct_min,100-year,1pct_plu,500-year
River Rch & RM= UNT035 IN NURI,Reach-1,1123
     653     927    1159    1057    1430    1934    2187
Boundary for River Rch & Prof#=UNT035 IN NURI,Reach-1,1
Up Type=0
Dn Type=3
Dn Slope=0.005
Boundary for River Rch & Prof#=UNT035 IN NURI,Reach-1,2
Up Type=0
Dn Type=3
Dn Slope=0.005
Boundary for River Rch & Prof#=UNT035 IN NURI,Reach-1,3
Up Type=0
Dn Type=3
Dn Slope=0.005
Boundary for River Rch & Prof#=UNT035 IN NURI,Reach-1,4
Up Type=0
Dn Type=3
Dn Slope=0.005
Boundary for River Rch & Prof#=UNT035 IN NURI,Reach-1,5
Up Type=0
Dn Type=3
Dn Slope=0.005
Boundary for River Rch & Prof#=UNT035 IN NURI,Reach-1,6
Up Type=0
Dn Type=3
Dn Slope=0.005
Boundary for River Rch & Prof#=UNT035 IN NURI,Reach-1,7
Up Type=0
Dn Type=3
Dn Slope=0.005

--- UNT035 IN NURI.g01 (geometry) ---

Geom Title=Existing Conditions
Program Version=4.10

River Reach=UNT035 IN NURI  ,Reach-1
Reach XY= 25
      2303028.52     13326925.32       2303008.2     13326910.51
      2302989.89     13326886.08      2302963.36     13326840.53
      2302947.86     13326826.55      2302917.86     13326810.64
      2302887.72     13326806.86      2302866.73     13326787.06
       2302820.3     13326751.95      2302755.34     13326711.69
      2302726.75     13326677.73      2302712.58     13326667.17
      2302636.45     13326639.94      2302603.78     13326634.24
      2302524.39     13326577.77      2302466.06     13326577.11
      2302408.56     13326571.69      2302334.77     13326551.07
      2302292.45     13326520.69      2302186.12     13326464.27
      2302135.12      13326411.1      2301985.38     13326286.32
      2301934.57      13326196.6      2301933.52     13326177.62
      2301917.72     13326116.85

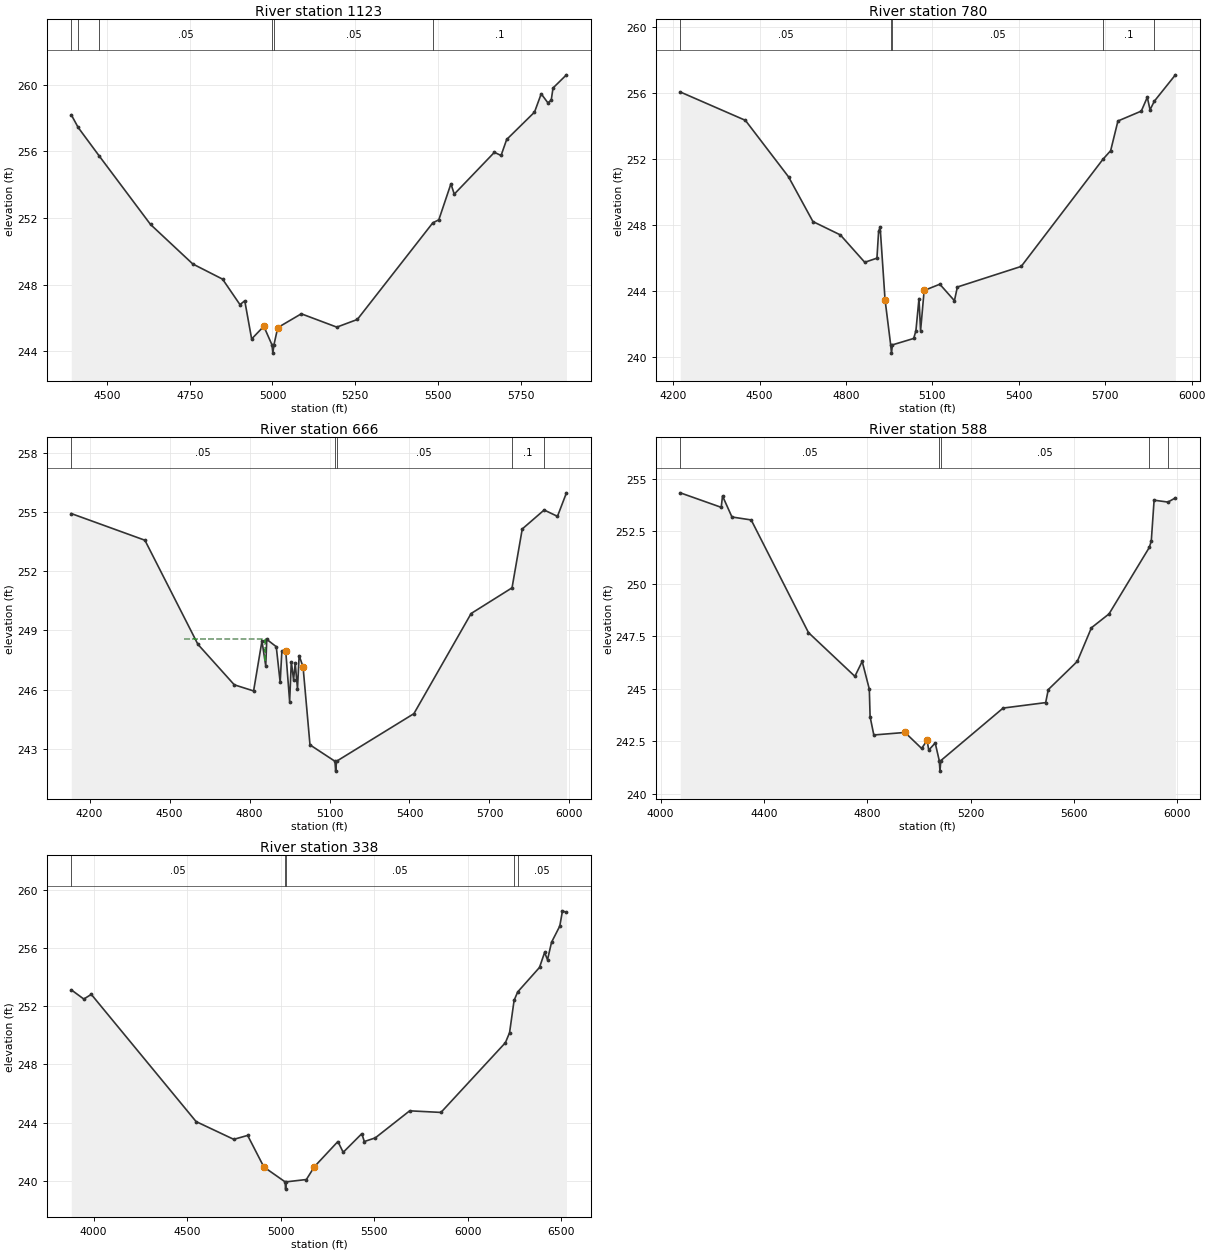
Type RM Length L Ch R = 1 ,1123    ,343,343,343
BEGIN DESCRIPTION:
UNT035 IN NURI 2.0
END DESCRIPTION:
XS GIS Cut Line= 4
      2303302.85     13326451.84      2302873.14     13326608.09
      2302643.11     13326907.57      2302738.51      13327562.4
#Sta/Elev= 30
  4391.9   258.2  4412.7  257.44  4477.1  255.71  4631.4  251.62  4759.1  249.25
  4849.1  248.34  4901.7  246.81  4916.2  247.04    4937  244.75  4973.7  245.51
  4998.4   244.4  5001.1   243.9  5004.4   244.4  5015.9  245.43  5087.1  246.26
  5194.4  245.46  5256.4  245.92  5484.6  251.72  5502.7   251.9  5539.3  254.06
  5549.4  253.44  5670.7  255.95  5690.9  255.76  5707.8  256.72  5791.9  258.36
  5812.2  259.46  5832.4  258.92  5842.5  259.08  5847.9  259.81  5888.5   260.6
#Mann= 6 ,-1 , 0
  4391.9     .05       0  4412.7      .1       0  4477.1     .05       0
  4998.4     .03       0  5004.4     .05       0  5484.6      .1       0
Bank Sta=4973.7,5015.9
XS Rating Curve= 0 ,0
Exp/Cntr=0.3,0.1

Type RM Length L Ch R = 1 ,780     ,114,114,114
BEGIN DESCRIPTION:
Mapping XS fd9217c9
END DESCRIPTION:
XS GIS Cut Line= 4
        2303183.     13326286.93      2302509.43     13326519.55
      2302457.35     13326644.55      2302599.39     13327503.77
#Sta/Elev= 30
  4224.8  256.07  4450.8  254.35  4600.7  250.92  4685.3  248.21  4780.5   247.4
  4865.2  245.74  4907.5  245.99  4913.3  247.62  4918.6  247.87  4935.7  243.46
  4955.2  240.73    4958  240.23  4961.2  240.73  5035.1  241.12  5042.8  241.59
  5053.5  243.54    5059  241.59  5071.4  244.03  5125.8  244.41  5176.5  243.41
  5186.7  244.24  5408.4  245.49  5691.7  251.98  5718.8  252.51  5744.1  254.31
  5825.2  254.91    5846  255.75  5855.6  254.99  5870.4  255.51  5943.7  257.11
#Mann= 5 ,-1 , 0
  4224.8     .05       0  4955.2     .03       0  4961.2     .05       0
  5691.7      .1       0  5870.4     .05       0
Bank Sta=4935.7,5071.4
XS Rating Curve= 0 ,0
Exp/Cntr=0.3,0.1

Type RM Length L Ch R = 1 ,666     ,78,78,78
BEGIN DESCRIPTION:
Mapping XS 0422a8a4
END DESCRIPTION:
XS GIS Cut Line= 4
      2303151.82     13326234.82      2302457.35     13326446.63
      2302356.65     13326585.52       2302526.8     13327530.01
#Sta/Elev= 30
  4131.5  254.92  4407.6  253.57  4606.4   248.3  4742.9  246.25  4815.3  245.94
  4846.7  248.47  4860.8  247.21  4864.7  248.55  4900.3  248.18    4915  246.37
  4921.2  247.94  4935.8  247.97  4950.5   245.4  4956.7  247.42  4965.2  246.51
  4971.4  247.34  4979.9  246.05  4986.1  247.73  5000.8  247.16  5026.8  243.21
  5120.4  242.38  5123.1  241.88  5126.4  242.38  5416.6  244.79  5631.2  249.86
  5784.7  251.16    5823  254.14  5905.1   255.1  5955.1  254.78  5988.8  255.97
#Mann= 5 ,-1 , 0
  4131.5     .05       0  5120.4     .03       0  5126.4     .05       0
  5784.7      .1       0  5905.1     .05       0
#XS Ineff= 2 ,-1
 4555.31 4857.95  248.56 4996.37 5602.72246.9903
Permanent Ineff=
       F       F
Bank Sta=4935.8,5000.8
XS Rating Curve= 0 ,0
Exp/Cntr=0.3,0.1

Type RM Length L Ch R = 1 ,588     ,250,250,250
BEGIN DESCRIPTION:
Mapping XS ae0e64fa
END DESCRIPTION:
XS GIS Cut Line= 4
      2303134.41     13326203.58       2302426.1     13326377.19
      2302266.37     13326575.11      2302460.82     13327488.33
#Sta/Elev= 30
  4075.9  254.32  4234.4  253.63  4239.5  254.17    4276  253.17  4350.5  253.03
  4572.3  247.67    4752  245.59  4780.3   246.3  4807.9  244.98  4810.9  243.67
  4825.3   242.8  4946.1  242.92  5010.4  242.16  5031.6  242.54    5038  242.08
    5063  242.42  5078.7  241.58  5081.5  241.08  5084.7  241.58    5326  244.08
  5490.7  244.34  5500.9  244.96  5613.2   246.3  5667.9   247.9  5736.1  248.56
  5891.9  251.72  5899.7  252.03  5910.6  253.97  5964.3  253.88  5993.2  254.08
#Mann= 5 ,-1 , 0
  4075.9     .05       0  5078.7     .03       0  5084.7     .05       0
  5891.9      .1       0  5964.3     .05       0
Bank Sta=4946.1,5031.6
XS Rating Curve= 0 ,0
Exp/Cntr=0.3,0.1

Type RM Length L Ch R = 1 ,338     ,0,0,0
BEGIN DESCRIPTION:
UNT035 IN NURI 1.0
END DESCRIPTION:
XS GIS Cut Line= 4
      2303094.48     13326152.36      2302235.12     13326161.04
      2301924.85     13326683.99      2302525.06     13327697.54
#Sta/Elev= 30
  3881.2  253.12    3948  252.49    3988  252.81    4548  244.07  4749.2  242.85
  4823.3  243.12  4910.1  240.95  5023.4  239.93  5026.2  239.43  5029.4  239.93
  5137.1  240.09  5179.9  240.97  5305.5   242.7  5333.9  241.96  5433.3  243.24
  5446.7   242.7  5505.2  242.95    5689  244.81  5856.1   244.7  6200.4  249.49
  6222.7  250.18  6246.9   252.4  6266.2  252.98  6382.6  254.66  6409.8  255.69
  6425.4  255.19  6446.9  256.39  6490.9   257.5  6505.4  258.55  6526.6  258.44
#Mann= 5 ,-1 , 0
  3881.2     .05       0  5023.4     .03       0  5029.4     .05       0
  6246.9      .1       0  6266.2     .05       0
Bank Sta=4910.1,5179.9
XS Rating Curve= 0 ,0
Exp/Cntr=0.3,0.1

Chan Stop Cuts=-1
Use User Specified Reach Order=0
Composite Channel Slope=5