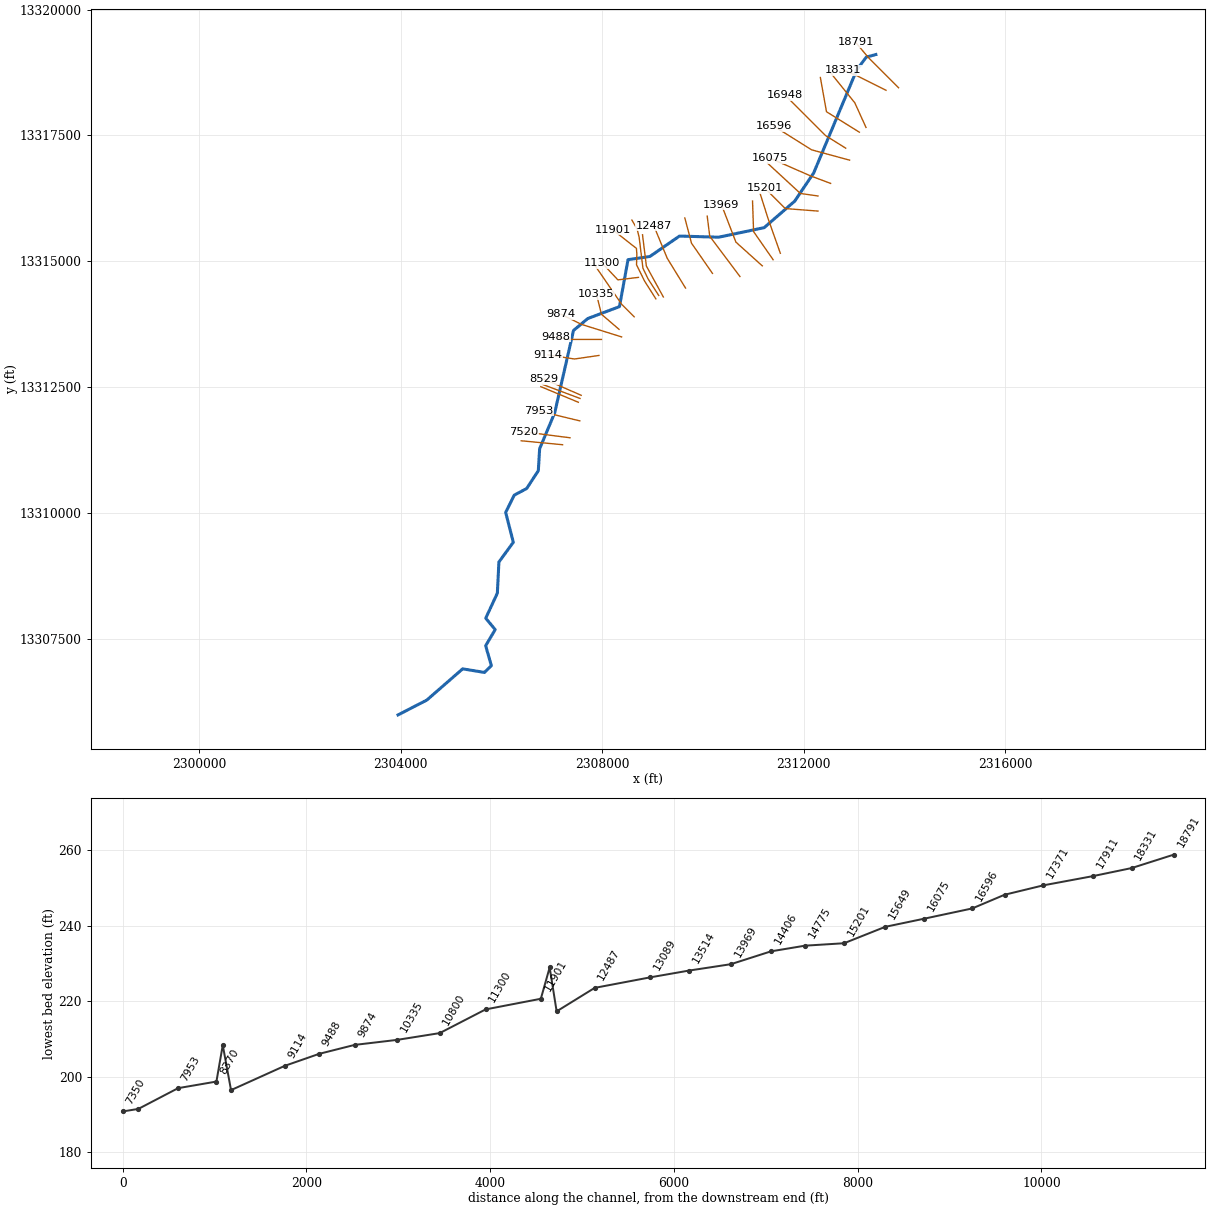
--- UNT036 IN NURI.prj (project) ---

Proj Title=UNT036 IN NURI Base Level Engineering
Current Plan=p01
Default Exp/Contr=0.3,0.1
English Units
Geom File=g01
Flow File=f01
Plan File=p01
Y Axis Title=Elevation
X Axis Title(PF)=Main Channel Distance
X Axis Title(XS)=Station
BEGIN DESCRIPTION:
UNT036 IN NURI
END DESCRIPTION:
DSS Export Rating Curves= 0
DSS Export Rating Curve Sorted= 0
DSS Export Volume Flow Curves= 0
DXF OffsetX= 0
DXF OffsetY= 0
DXF ScaleX= 1
DXF ScaleY= 10

--- UNT036 IN NURI.p01 (plan) ---

Plan Title=Multiple Run
Short Identifier=Multiple
Geom File=g01
Flow File=f01
Subcritical Flow
K Sum by GR= 0
Std Step Tol= 0.01
Critical Tol= 0.01
Num of Std Step Trials= 20
Max Error Tol= 0.3
Flow Tol Ratio= 0.001
Split Flow NTrial= 30
Split Flow Tol= 0.02
Split Flow Ratio= 0.02
Log Output Level= 0
Friction Slope Method= 1
Unsteady Friction Slope Method= 2
Unsteady Bridges Friction Slope Method= 1
Parabolic Critical Depth
Global Vel Dist=  1 , 1 , 1
Global Log Level= 0
CheckData=True
Encroach Param= -1, 0, 0, 0
BEGIN DESCRIPTION:
Multiple Run
END DESCRIPTION:

--- UNT036 IN NURI.f01 (steady flow) ---

Flow Title=Multiple
Number of Profiles=7
Profile Names=10-year,25-year,50-year,1pct_min,100-year,1pct_plu,500-year
River Rch & RM= UNT036 IN NURI,Reach-1,18791
     578     814    1010     917    1240    1677    1875
River Rch & RM= UNT036 IN NURI,Reach-1,17371
    1176    1715    2180    2020    2731    3694    4307
River Rch & RM= UNT036 IN NURI,Reach-1,4679
    1654    2450    3146    2941    3977    5379    6388
Boundary for River Rch & Prof#=UNT036 IN NURI,Reach-1,1
Up Type=0
Dn Type=3
Dn Slope=0.005
Boundary for River Rch & Prof#=UNT036 IN NURI,Reach-1,2
Up Type=0
Dn Type=3
Dn Slope=0.005
Boundary for River Rch & Prof#=UNT036 IN NURI,Reach-1,3
Up Type=0
Dn Type=3
Dn Slope=0.005
Boundary for River Rch & Prof#=UNT036 IN NURI,Reach-1,4
Up Type=0
Dn Type=3
Dn Slope=0.005
Boundary for River Rch & Prof#=UNT036 IN NURI,Reach-1,5
Up Type=0
Dn Type=3
Dn Slope=0.005
Boundary for River Rch & Prof#=UNT036 IN NURI,Reach-1,6
Up Type=0
Dn Type=3
Dn Slope=0.005
Boundary for River Rch & Prof#=UNT036 IN NURI,Reach-1,7
Up Type=0
Dn Type=3
Dn Slope=0.005

--- UNT036 IN NURI.g01 (geometry) ---

Geom Title=Existing Conditions
Program Version=4.10

River Reach=UNT036 IN NURI  ,Reach-1
Reach XY= 30
      2313436.64     13319107.17      2313247.62     13319056.09
      2313060.43     13318809.26      2312201.86     13316754.35
      2311824.44     13316193.55      2311217.72     13315666.86
      2310314.16     13315477.82        2309537.     13315500.21
      2308949.76     13315095.26      2308515.35     13315031.19
      2308345.13     13314098.65      2307715.25     13313861.44
      2307432.62     13313624.13      2307059.35     13311988.93
      2306760.48     13311275.72      2306733.92     13310838.43
      2306502.39     13310484.58      2306255.71     13310353.19
      2306085.57      13310010.1      2306237.72     13309416.86
      2305951.51     13309025.29       2305920.6     13308406.56
      2305690.09     13307908.56      2305877.62     13307681.34
      2305688.12     13307361.46      2305801.85     13306965.64
      2305663.87     13306831.32      2305231.75      13306902.1
       2304520.3     13306282.01      2303947.72     13305986.86

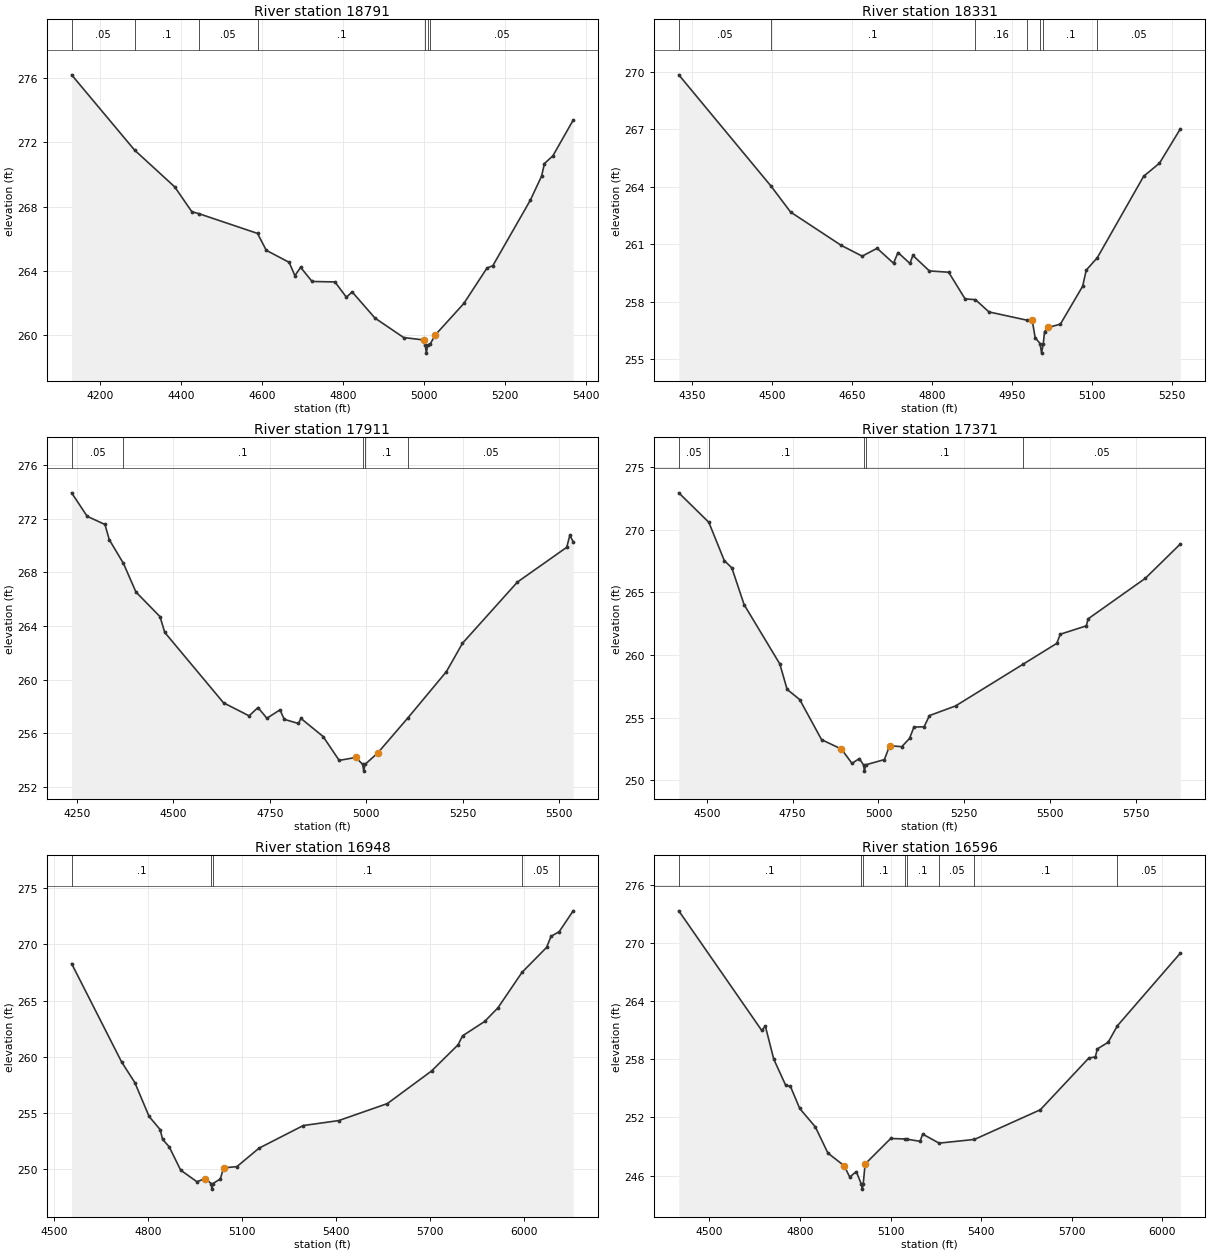
Type RM Length L Ch R = 1 ,18791   ,460,460,460
BEGIN DESCRIPTION:
UNT036 IN NURI 42.0
END DESCRIPTION:
XS GIS Cut Line= 3
      2313887.73     13318446.85      2313287.72     13319046.85
      2313037.75     13319346.82
#Sta/Elev= 30
  4129.6  276.21    4285  271.53  4384.2  269.24  4426.6  267.69  4443.9  267.57
  4588.9  266.34  4610.4  265.29    4667  264.54  4681.2  263.71  4695.3  264.23
  4723.6  263.35  4780.1  263.32  4808.4  262.37  4822.6   262.7  4879.1  261.07
  4949.9  259.86  4999.6  259.71  5003.1  259.39  5005.9  258.89  5009.1  259.39
  5015.8  259.48  5028.3  260.03  5098.5  261.98  5155.8  264.19  5170.1  264.33
  5262.6   268.4  5290.5   269.9  5297.7  270.69  5318.5  271.17  5368.6  273.39
#Mann= 7 ,-1 , 0
  4129.6     .05       0    4285      .1       0  4443.9     .05       0
  4588.9      .1       0  5003.1     .07       0  5009.1      .1       0
  5015.8     .05       0
Bank Sta=4999.6,5028.3
XS Rating Curve= 0 ,0
Exp/Cntr=0.3,0.1

Type RM Length L Ch R = 1 ,18331   ,420,420,420
BEGIN DESCRIPTION:
UNT036 IN NURI 41.0
END DESCRIPTION:
XS GIS Cut Line= 3
       2313637.7     13318396.86      2313037.72     13318696.85
      2312787.68     13318796.87
#Sta/Elev= 30
  4325.6  269.84  4498.3  264.04  4535.2  262.68  4630.2  260.94  4669.4  260.38
  4697.3  260.79  4728.1  260.01  4736.5  260.57  4758.8     260  4764.4  260.42
  4795.2  259.61  4831.5  259.54  4862.2  258.15  4881.6  258.11    4907  257.47
    4978  257.04    4988  257.04  4993.6  256.13  5002.8  255.82  5005.6  255.32
  5008.8  255.82  5011.2  256.44  5017.9  256.66  5040.8  256.83  5082.6  258.81
  5089.3  259.65  5110.1   260.3    5197  264.55  5226.6  265.23  5265.7  267.02
#Mann= 7 ,-1 , 0
  4325.6     .05       0  4498.3      .1       0  4881.6     .16       0
    4978      .1       0  5002.8     .07       0  5008.8      .1       0
  5110.1     .05       0
Bank Sta=4988,5017.9
XS Rating Curve= 0 ,0
Exp/Cntr=0.3,0.1

Type RM Length L Ch R = 1 ,17911   ,540,540,540
BEGIN DESCRIPTION:
UNT036 IN NURI 40.0
END DESCRIPTION:
XS GIS Cut Line= 3
       2313240.8     13317658.06      2313018.59     13318147.62
      2312539.43     13318741.36
#Sta/Elev= 30
  4235.9  273.93  4276.3  272.18  4322.4  271.57  4333.5  270.44  4370.3  268.67
  4402.7  266.54  4465.2   264.7  4477.4  263.53  4629.9  258.28  4696.1  257.31
  4719.2  257.93  4742.3  257.13  4776.3  257.76  4787.3  257.05    4824  256.74
  4830.5  257.12  4888.1  255.77  4929.7  253.99  4972.8  254.21  4990.7  253.69
  4993.4  253.19  4996.7  253.69  5029.6  254.54  5108.3  257.17  5207.9  260.61
  5249.5  262.72  5391.9  267.28  5519.8  269.87  5527.8  270.76  5536.5   270.3
#Mann= 5 ,-1 , 0
  4235.9     .05       0  4370.3      .1       0  4990.7     .07       0
  4996.7      .1       0  5108.3     .05       0
Bank Sta=4972.8,5029.6
XS Rating Curve= 0 ,0
Exp/Cntr=0.3,0.1

Type RM Length L Ch R = 1 ,17371   ,423,423,423
BEGIN DESCRIPTION:
UNT036 IN NURI 39.0
END DESCRIPTION:
XS GIS Cut Line= 3
      2313108.91     13317564.26      2312456.09     13317970.54
      2312334.57     13318651.05
#Sta/Elev= 30
  4418.6  272.94    4506  270.59    4551  267.54  4573.1  266.95  4608.8  264.02
  4712.7  259.29    4734  257.26  4770.6  256.45  4834.3  253.25  4892.1   252.5
  4922.8  251.36  4944.1  251.74  4956.4  251.24  4959.2  250.74  4962.4  251.24
  5017.2  251.66  5032.5  252.77  5067.8  252.69  5090.4  253.35  5103.1  254.25
  5132.9  254.28  5148.3  255.17  5224.4  255.94  5421.6  259.28    5519  260.93
  5529.2  261.66  5605.1  262.33  5610.4  262.89  5776.8  266.12  5878.8  268.86
#Mann= 5 ,-1 , 0
  4418.6     .05       0    4506      .1       0  4956.4     .07       0
  4962.4      .1       0  5421.6     .05       0
Bank Sta=4892.1,5032.5
XS Rating Curve= 0 ,0
Exp/Cntr=0.3,0.1

Type RM Length L Ch R = 1 ,16948   ,352,352,352
BEGIN DESCRIPTION:
UNT036 IN NURI 38.0
END DESCRIPTION:
XS GIS Cut Line= 3
      2312837.71     13317246.86      2312437.72     13317496.85
      2311637.69     13318296.88
#Sta/Elev= 30
  4555.1  268.28  4714.9  259.54  4757.3   257.7  4802.7   254.7  4838.1  253.53
  4845.8  252.67    4867     252  4903.6  249.93  4955.4   248.9  4982.6  249.18
  5000.8  248.74  5003.5  248.24  5006.8  248.74  5030.3  249.14  5040.9  250.13
  5083.4  250.24  5154.1  251.88  5295.5  253.89  5408.6  254.33  5564.2  255.84
  5705.6  258.74  5790.5  261.07  5804.6  261.86  5875.3  263.14  5917.7  264.35
  5994.9  267.51  6073.3  269.72  6087.5  270.71  6113.4  271.11  6158.2  272.97
#Mann= 5 ,-1 , 0
  4555.1      .1       0  5000.8     .07       0  5006.8      .1       0
  5994.9     .05       0  6113.4      .1       0
Bank Sta=4982.6,5040.9
XS Rating Curve= 0 ,0
Exp/Cntr=0.3,0.1

Type RM Length L Ch R = 1 ,16596   ,521,521,521
BEGIN DESCRIPTION:
UNT036 IN NURI 37.0
END DESCRIPTION:
XS GIS Cut Line= 3
      2312914.39     13317008.74      2312160.95     13317213.59
      2311414.83     13317682.08
#Sta/Elev= 30
  4398.4  273.29  4673.3  260.96  4685.1  261.42  4713.1     258  4752.9  255.29
    4768  255.22  4799.1  252.92  4850.9  251.02  4892.4  248.33  4946.6  247.01
  4964.9  245.85  4986.4  246.42  5003.4  245.11  5006.1  244.61  5009.4  245.11
  5015.8   247.2  5100.6  249.83  5146.4  249.78  5153.6  249.76  5197.7  249.54
  5206.6  250.28  5260.8  249.35  5377.8  249.73  5596.3  252.79  5757.3  258.13
  5778.5  258.23  5785.2  259.06  5820.9  259.74  5851.5  261.44  6060.2  268.93
#Mann= 8 ,-1 , 0
  4398.4      .1       0  5003.4     .07       0  5009.4      .1       0
  5146.4     .05       0  5153.6      .1       0  5260.8     .05       0
  5377.8      .1       0  5851.5     .05       0
Bank Sta=4946.6,5015.8
XS Rating Curve= 0 ,0
Exp/Cntr=0.3,0.1

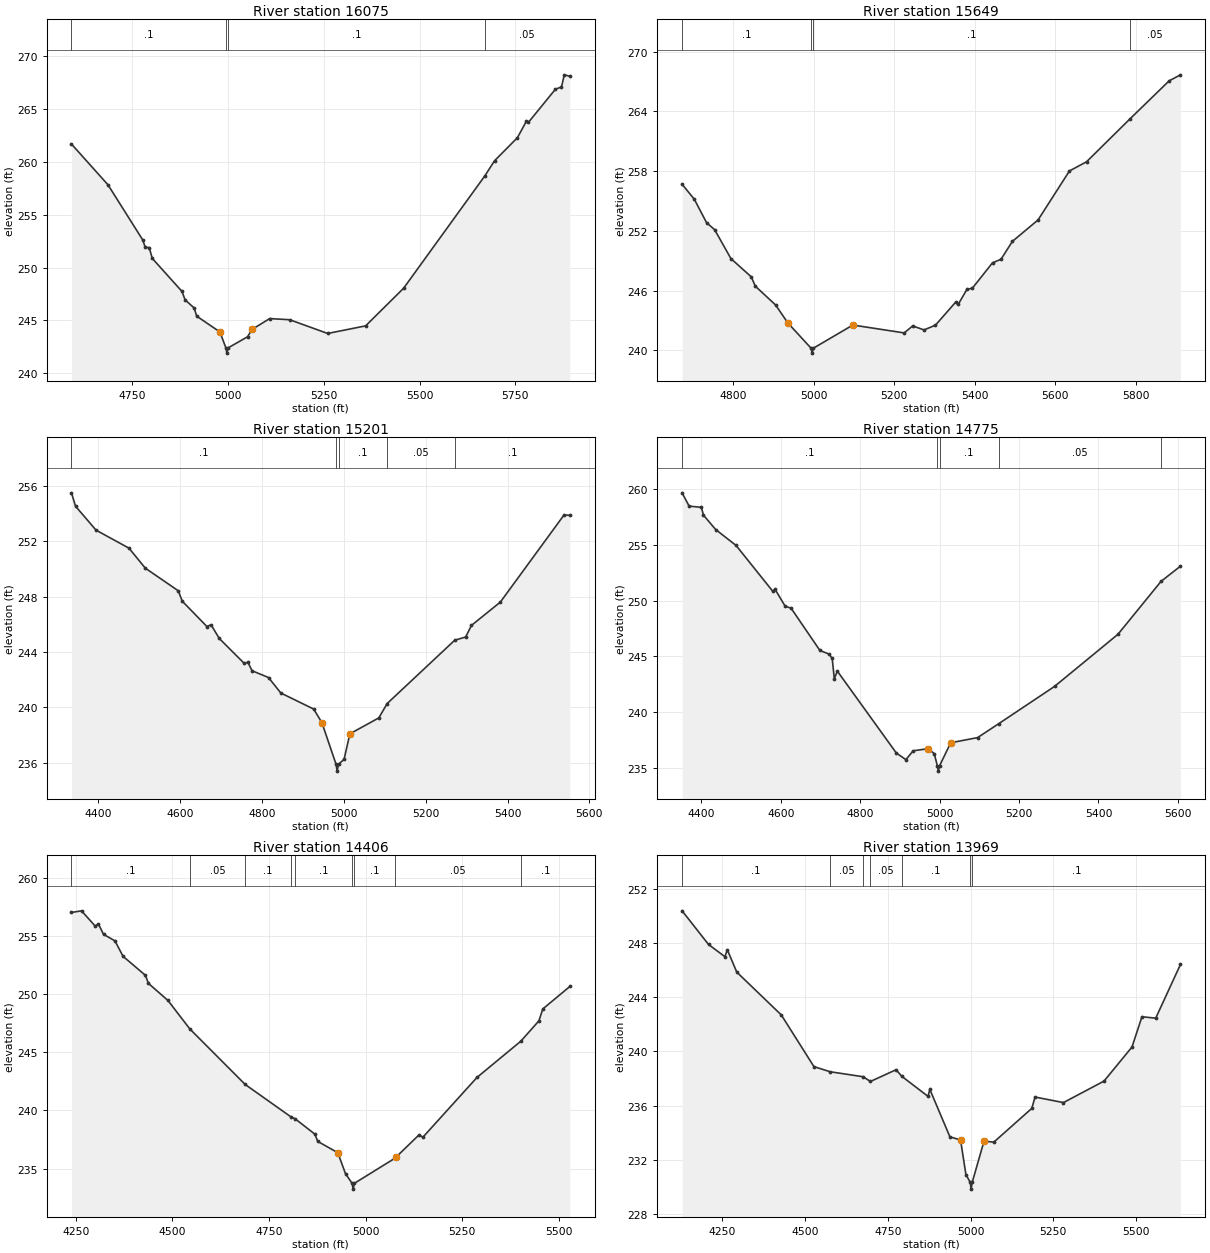
Type RM Length L Ch R = 1 ,16075   ,426,426,426
BEGIN DESCRIPTION:
UNT036 IN NURI 36.0
END DESCRIPTION:
XS GIS Cut Line= 3
      2312537.75     13316546.84      2312137.72     13316696.85
      2311337.76     13317046.84
#Sta/Elev= 30
  4591.7  261.69    4687  257.83  4777.7  252.61    4784  251.93  4794.6  251.88
  4802.7  250.86  4880.1  247.74  4888.1  246.95  4912.1  246.16  4918.4   245.4
  4978.9  243.91  4994.6   242.4  4997.3   241.9  5000.6   242.4  5051.3  243.45
  5062.6  244.14    5109  245.17  5161.2  245.06  5260.2  243.76  5359.2  244.48
  5458.3  248.04  5669.8  258.65  5695.7  260.11  5755.3  262.29  5778.7  263.85
  5784.2  263.75  5854.3  266.87  5870.3   267.1  5877.7  268.24  5892.1   268.1
#Mann= 4 ,-1 , 0
  4591.7      .1       0  4994.6     .07       0  5000.6      .1       0
  5669.8     .05       0
Bank Sta=4978.9,5062.6
XS Rating Curve= 0 ,0
Exp/Cntr=0.3,0.1

Type RM Length L Ch R = 1 ,15649   ,448,448,448
BEGIN DESCRIPTION:
UNT036 IN NURI 35.0
END DESCRIPTION:
XS GIS Cut Line= 3
      2312287.76     13316296.85      2311937.72     13316346.85
      2311287.71     13316946.86
#Sta/Elev= 30
  4673.4  256.68  4703.7  255.18  4734.1  252.83  4754.3  252.12  4794.7  249.22
  4845.2  247.39  4855.3  246.45  4905.8  244.56  4936.1  242.76  4993.7  240.23
  4996.4  239.73  4999.7  240.23  5097.6  242.55  5225.2  241.76  5246.2  242.46
  5274.5  242.06  5302.9  242.54  5352.8  244.84  5359.6  244.64  5380.8  246.12
  5394.7  246.26  5444.6   248.8  5465.6  249.15    5494  250.95  5557.7   253.1
  5635.7  258.02  5678.2  258.94  5785.9  263.24  5883.5  267.07  5911.6  267.67
#Mann= 4 ,-1 , 0
  4673.4      .1       0  4993.7     .07       0  4999.7      .1       0
  5785.9     .05       0
Bank Sta=4936.1,5097.6
XS Rating Curve= 0 ,0
Exp/Cntr=0.3,0.1

Type RM Length L Ch R = 1 ,15201   ,426,426,426
BEGIN DESCRIPTION:
UNT036 IN NURI 34.0
END DESCRIPTION:
XS GIS Cut Line= 3
      2312287.69     13315996.86      2311637.72     13316046.85
       2311237.7     13316446.87
#Sta/Elev= 30
  4334.7  255.51  4344.7  254.54  4394.8  252.81  4475.1  251.51  4515.2  250.06
  4595.4  248.43  4605.5  247.67  4665.6  245.84  4675.7  245.97  4695.7  244.98
  4755.9   243.2  4765.9  243.24    4776  242.64  4816.1  242.15  4846.2  241.03
  4926.4  239.87  4946.5  238.89  4981.1  235.88  4983.8  235.38  4987.1  235.88
  5000.7  236.23  5014.9  238.08  5085.6  239.23    5106  240.27  5271.1  244.85
  5297.7  245.08  5311.9  245.92  5382.6  247.61  5538.1  253.91  5552.3  253.88
#Mann= 5 ,-1 , 0
  4334.7      .1       0  4981.1     .07       0  4987.1      .1       0
    5106     .05       0  5271.1      .1       0
Bank Sta=4946.5,5014.9
XS Rating Curve= 0 ,0
Exp/Cntr=0.3,0.1

Type RM Length L Ch R = 1 ,14775   ,369,369,369
BEGIN DESCRIPTION:
UNT036 IN NURI 33.0
END DESCRIPTION:
XS GIS Cut Line= 3
      2311539.64     13315158.26      2311296.58     13315845.79
      2311137.71     13316346.88
#Sta/Elev= 30
  4351.6  259.64  4369.2  258.45  4400.1  258.34  4405.4  257.64  4436.3  256.35
  4487.5  254.93  4580.3  250.81  4585.6  251.01  4611.2  249.48  4625.9  249.32
  4698.6  245.53  4721.3  245.21  4729.5  244.83  4734.8     243  4742.5  243.68
    4891  236.35    4915  235.76  4933.5  236.55  4971.5  236.74  4986.5  236.29
  4994.1  235.23  4996.8  234.73  5000.1  235.23    5028  237.27  5095.6  237.73
    5149  238.98  5289.3  242.31  5449.1  246.98  5557.4  251.71  5606.5  253.08
#Mann= 5 ,-1 , 0
  4351.6      .1       0  4994.1     .07       0  5000.1      .1       0
    5149     .05       0  5557.4      .1       0
Bank Sta=4971.5,5028
XS Rating Curve= 0 ,0
Exp/Cntr=0.3,0.1

Type RM Length L Ch R = 1 ,14406   ,437,437,437
BEGIN DESCRIPTION:
UNT036 IN NURI 32.0
END DESCRIPTION:
XS GIS Cut Line= 3
      2311397.25     13315029.84      2311008.38     13315588.84
      2310987.72     13316196.84
#Sta/Elev= 30
  4238.8     257  4264.9  257.14  4300.7  255.81  4308.3  256.03  4321.7  255.12
  4351.3  254.56  4372.3  253.23  4430.1   251.6  4437.8  250.91  4488.4  249.44
  4545.1  246.99  4688.3  242.22  4806.1  239.45  4817.6  239.27  4868.6  237.95
  4875.9  237.33  4927.8  236.36  4947.8  234.55  4964.8  233.73  4967.5  233.23
  4970.8  233.73  5075.9  235.89  5077.9  235.96  5137.9  237.89  5147.9  237.69
    5288  242.83  5401.3  245.94  5448.1  247.69  5458.1  248.71  5528.1  250.64
#Mann= 9 ,-1 , 0
  4238.8      .1       0  4545.1     .05       0  4688.3      .1       0
  4806.1     .05       0  4817.6      .1       0  4964.8     .07       0
  4970.8      .1       0  5075.9     .05       0  5401.3      .1       0
Bank Sta=4927.8,5077.9
XS Rating Curve= 0 ,0
Exp/Cntr=0.3,0.1

Type RM Length L Ch R = 1 ,13969   ,455,455,455
BEGIN DESCRIPTION:
UNT036 IN NURI 31.0
END DESCRIPTION:
XS GIS Cut Line= 3
      2311181.77     13314908.05      2310657.48     13315380.26
      2310369.29     13316126.76
#Sta/Elev= 30
  4128.4   250.4  4208.3  247.91  4257.7  247.01  4265.1  247.52  4293.5  245.87
  4428.1   242.7  4526.7  238.88  4575.6   238.5  4675.6  238.13  4697.3  237.78
  4774.9  238.65  4792.3  238.16  4871.4  236.68  4876.8   237.2  4937.5  233.69
  4969.7  233.45  4985.9   230.9  4998.9  230.32  5001.6  229.82  5004.9  230.32
  5040.5  233.36  5070.4   233.3  5184.9  235.79  5194.8  236.63  5280.6  236.22
  5403.2  237.81  5487.7  240.33  5517.7  242.57  5559.3  242.46  5634.2  246.44
#Mann= 7 ,-1 , 0
  4128.4      .1       0  4575.6     .05       0  4675.6      .1       0
  4697.3     .05       0  4792.3      .1       0  4998.9     .07       0
  5004.9      .1       0
Bank Sta=4969.7,5040.5
XS Rating Curve= 0 ,0
Exp/Cntr=0.3,0.1

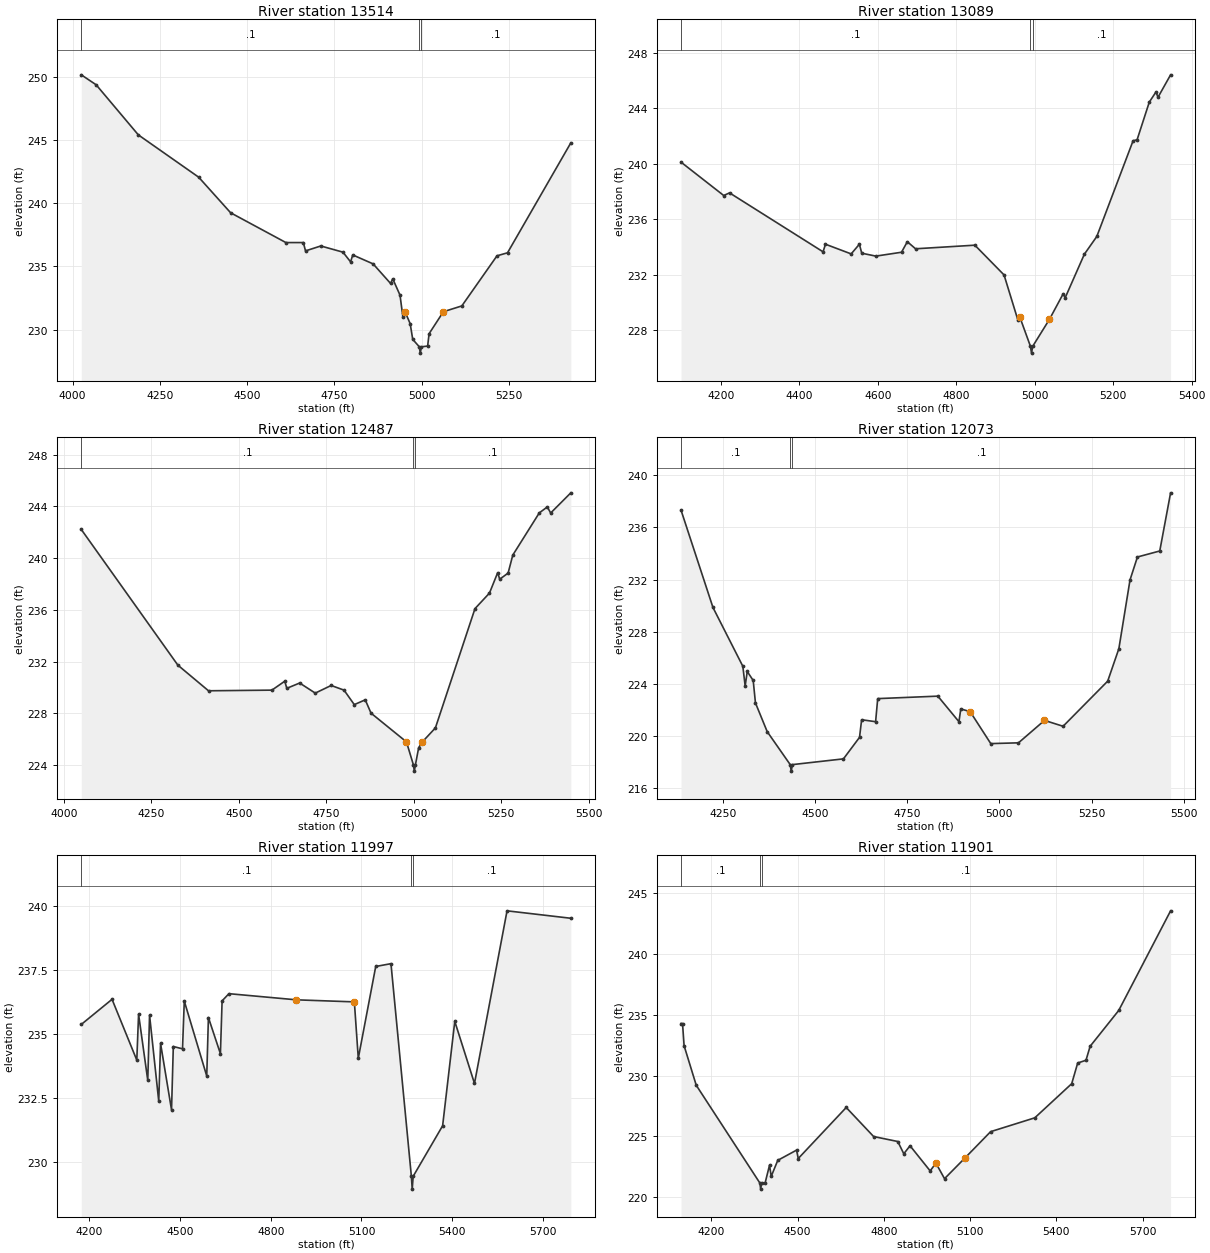
Type RM Length L Ch R = 1 ,13514   ,425,425,425
BEGIN DESCRIPTION:
UNT036 IN NURI 30.0
END DESCRIPTION:
XS GIS Cut Line= 3
      2310737.73     13314696.84      2310137.72     13315496.85
      2310087.72     13315896.82
#Sta/Elev= 30
  4024.7  250.18  4067.4  249.39  4188.3  245.42  4361.2  242.07  4452.8  239.25
  4611.2  236.89  4661.2  236.89  4667.4  236.23  4711.2  236.62  4774.7  236.13
  4796.6  235.36  4802.8  235.91  4861.2   235.2  4911.2  233.65  4917.4  234.02
  4938.3  232.72  4946.6  230.96  4952.8   231.4  4967.4  230.46  4974.7  229.22
  4993.6  228.63  4996.3  228.13  4999.6  228.63  5017.4  228.69  5021.6  229.67
  5062.5  231.41  5115.4  231.87  5216.2  235.84  5246.4  236.08  5427.8  244.79
#Mann= 3 ,-1 , 0
  4024.7      .1       0  4993.6     .07       0  4999.6      .1       0
Bank Sta=4952.8,5062.5
XS Rating Curve= 0 ,0
Exp/Cntr=0.3,0.1

Type RM Length L Ch R = 1 ,13089   ,602,602,602
BEGIN DESCRIPTION:
UNT036 IN NURI 29.0
END DESCRIPTION:
XS GIS Cut Line= 3
      2310192.18     13314758.75      2309775.53     13315359.42
       2309643.6     13315859.38
#Sta/Elev= 30
  4098.2  240.12    4207  237.71  4221.9   237.9  4460.3  233.64  4466.4  234.19
  4531.9  233.49  4552.9  234.19  4558.9  233.54  4594.9  233.33  4660.3  233.61
  4675.1  234.37  4696.1  233.86  4847.3  234.12  4921.7  231.97  4956.8  228.73
    4962  228.92  4988.9  226.82  4991.7  226.32  4994.9  226.82  5037.4  228.76
  5072.5  230.61  5077.7  230.33  5126.5  233.47  5158.2  234.75  5250.6  241.66
  5260.9  241.74    5292  244.46    5309  245.19  5314.2  244.81  5346.3  246.43
#Mann= 3 ,-1 , 0
  4098.2      .1       0  4988.9     .07       0  4994.9      .1       0
Bank Sta=4962,5037.4
XS Rating Curve= 0 ,0
Exp/Cntr=0.3,0.1

Type RM Length L Ch R = 1 ,12487   ,414,414,414
BEGIN DESCRIPTION:
UNT036 IN NURI 28.0
END DESCRIPTION:
XS GIS Cut Line= 3
      2309657.49     13314467.04      2309292.89     13315060.81
      2309025.52     13315710.15
#Sta/Elev= 30
  4049.8  242.22  4325.9  231.73  4413.4  229.75  4594.6   229.8  4631.3  230.49
  4637.2  229.94  4673.9  230.35  4718.5  229.57  4763.9  230.16  4800.7   229.8
    4830  228.68  4861.3  229.05  4877.9  228.02  4979.1   225.8  4998.8  224.04
  5001.6  223.54  5004.8  224.04  5013.9  225.34  5023.5  225.77  5061.8  226.88
  5174.9   236.1  5216.3   237.3  5239.8  238.88  5245.6  238.37  5269.6  238.85
    5283  240.24  5358.7   243.5  5381.6  243.96  5391.2  243.49  5448.8  245.05
#Mann= 3 ,-1 , 0
  4049.8      .1       0  4998.8     .07       0  5004.8      .1       0
Bank Sta=4979.1,5023.5
XS Rating Curve= 0 ,0
Exp/Cntr=0.3,0.1

Type RM Length L Ch R = 1 ,12073   ,76,76,76
BEGIN DESCRIPTION:
UNT036 IN NURI 27.0
END DESCRIPTION:
XS GIS Cut Line= 3
      2309216.51     13314289.97       2308879.7     13314904.56
      2308803.31     13315526.06
#Sta/Elev= 30
  4137.2  237.32  4223.7  229.86  4304.7  225.35    4311  223.84  4316.7  224.95
  4332.8  224.26  4338.9  222.54  4370.7  220.34  4433.1  217.81  4435.9  217.31
  4439.1  217.81  4577.4  218.25    4621   219.9  4626.7  221.25  4664.6   221.1
  4670.3  222.87  4833.3  223.06  4890.5   221.1  4895.5  222.08  4920.9  221.87
  4976.8  219.42  5051.9  219.48  5122.4   221.2  5172.8  220.75  5293.7  224.21
    5324   226.7  5354.2  231.97  5374.3  233.73  5434.8  234.19  5464.2  238.65
#Mann= 3 ,-1 , 0
  4137.2      .1       0  4433.1     .07       0  4439.1      .1       0
Bank Sta=4920.9,5122.4
XS Rating Curve= 0 ,0
Exp/Cntr=0.3,0.1

Type RM Length L Ch R = 1 ,11997   ,96,96,96
BEGIN DESCRIPTION:
UNT036 IN NURI 26.0
END DESCRIPTION:
XS GIS Cut Line= 6
      2309124.51      13314321.2      2308913.55     13314649.35
      2308811.21     13314862.07      2308736.47     13315472.27
      2308696.16     13315638.16      2308592.34      13315818.1
#Sta/Elev= 30
    4173  235.37  4274.8  236.35  4356.7  233.98  4362.6  235.77    4393  233.19
  4398.9  235.73  4429.3  232.38  4435.3  234.63  4471.6  232.04  4477.5  234.51
  4507.9  234.42  4513.8  236.28  4588.1  233.36  4593.6  235.64  4633.3  234.23
  4638.9  236.29  4661.5  236.57  4884.7  236.33  5076.4  236.25  5089.4  234.05
  5147.1  237.63  5197.5  237.74    5265  229.45  5267.8  228.95    5271  229.45
  5368.4  231.42  5408.6  235.49  5473.8  233.07  5581.5   239.8  5792.5  239.51
#Mann= 3 ,-1 , 0
    4173      .1       0    5265     .07       0    5271      .1       0
Bank Sta=4884.7,5076.4
XS Rating Curve= 0 ,0
Exp/Cntr=0.3,0.1

Type RM Length L Ch R = 1 ,11901   ,601,601,601
BEGIN DESCRIPTION:
Mapping XS 445f6ba9
END DESCRIPTION:
XS GIS Cut Line= 6
      2309068.34     13314252.89      2308844.85     13314604.41
      2308684.11      13314929.5      2308690.62     13315144.34
      2308681.94     13315255.88      2308212.34     13315624.45
#Sta/Elev= 30
  4094.5  234.28  4099.7  234.28  4105.1  232.46  4147.4   229.2  4368.8  221.15
  4371.5  220.65  4374.8  221.15    4387  221.16  4402.3  222.62  4408.2   221.7
    4431  223.02  4496.3  223.86  4502.2  223.17  4669.1  227.37  4764.4  224.98
  4848.5  224.57  4869.4  223.56  4891.1  224.22  4961.1  222.15  4981.1  222.79
  5011.1  221.51  5081.2  223.19  5171.4  225.38  5325.1  226.52  5453.5  229.33
  5474.3  231.03  5503.2  231.26  5517.6  232.41  5617.1  235.36  5797.5  243.56
#Mann= 3 ,-1 , 0
  4094.5      .1       0  4368.8     .07       0  4374.8      .1       0
Bank Sta=4981.1,5081.2
XS Rating Curve= 0 ,0
Exp/Cntr=0.3,0.1

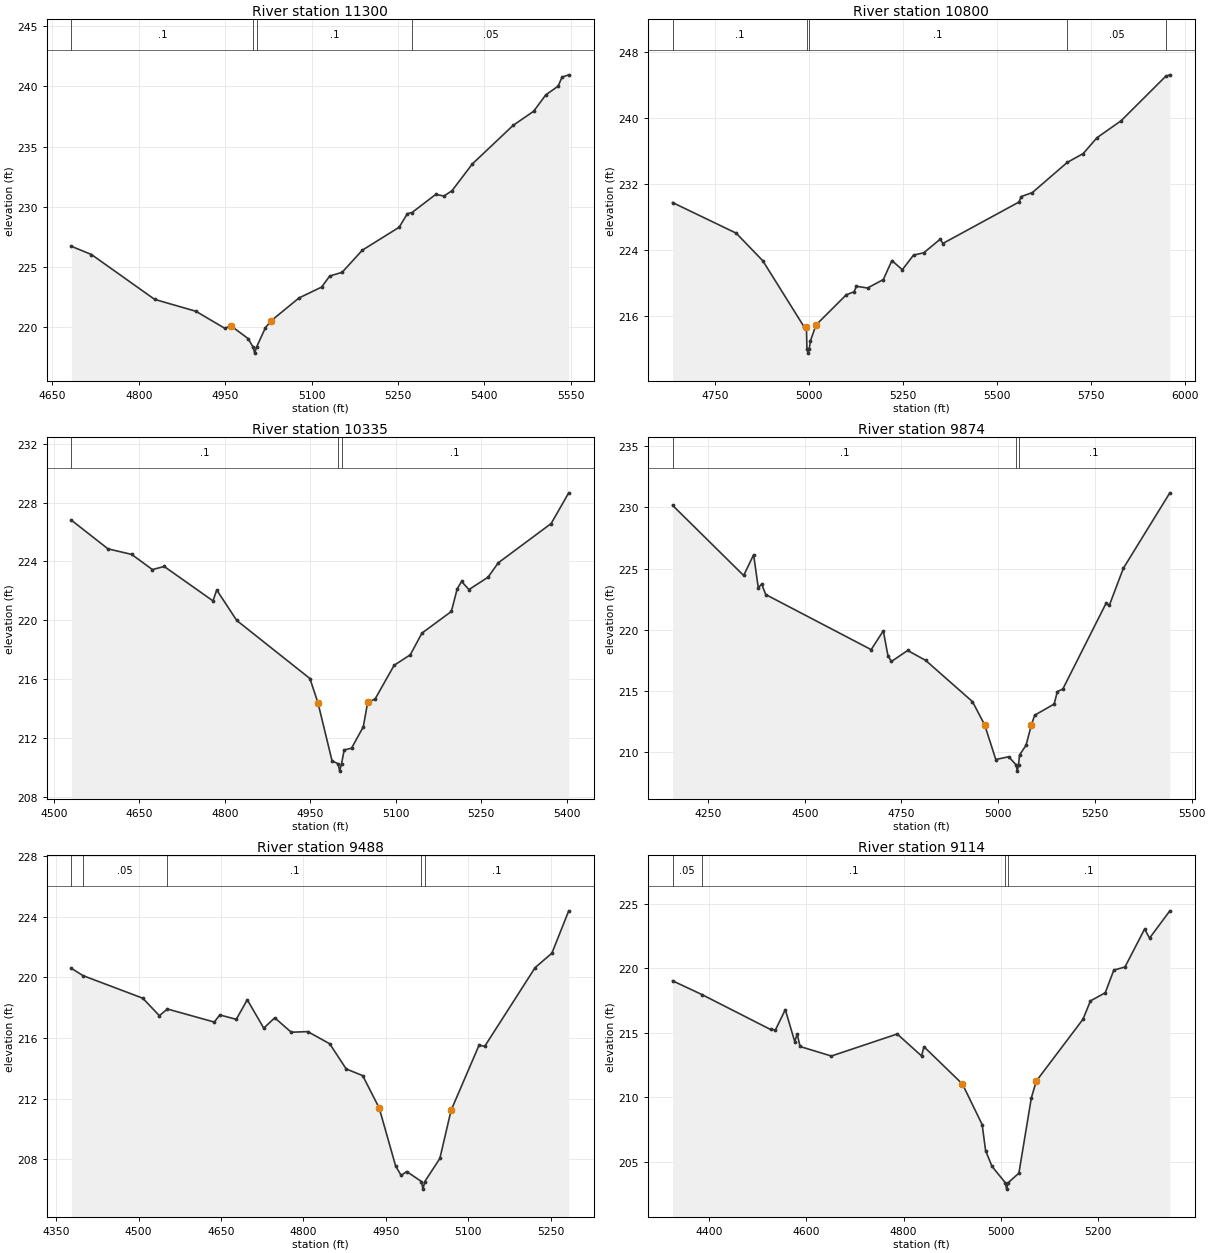
Type RM Length L Ch R = 1 ,11300   ,500,500,500
BEGIN DESCRIPTION:
UNT036 IN NURI 25.0
END DESCRIPTION:
XS GIS Cut Line= 3
      2308722.32     13314679.68      2308313.73     13314630.26
      2308004.68     13314960.14
#Sta/Elev= 30
    4683  226.71  4717.8  226.03  4827.5   222.3  4899.2  221.31  4949.5  219.89
  4959.6  220.12  4989.8  219.04  4998.5  218.33  5001.2  217.83  5004.5  218.33
    5020  219.95  5030.1  220.53  5078.3  222.42  5117.4  223.32  5131.6  224.24
  5153.1  224.55  5188.2  226.39  5252.2   228.3  5266.4  229.43  5274.5  229.52
  5315.7  231.03  5329.9  230.89    5344  231.34  5379.2  233.56  5450.1  236.77
  5485.7  237.94  5506.7   239.3  5528.2  240.03    5535  240.78  5546.6  240.97
#Mann= 4 ,-1 , 0
    4683      .1       0  4998.5     .07       0  5004.5      .1       0
  5274.5     .05       0
Bank Sta=4959.6,5030.1
XS Rating Curve= 0 ,0
Exp/Cntr=0.3,0.1

Type RM Length L Ch R = 1 ,10800   ,465,465,465
BEGIN DESCRIPTION:
UNT036 IN NURI 24.0
END DESCRIPTION:
XS GIS Cut Line= 3
      2308637.75     13313896.83      2308387.72     13314146.85
      2307837.73     13314946.84
#Sta/Elev= 30
  4636.2  229.76  4805.9  226.05  4876.7  222.71  4986.3  214.74  4992.8  214.74
  4994.2  212.04    4997  211.54  5000.2  212.04  5003.3  212.99  5018.2  214.94
  5098.7  218.59  5119.7  218.97  5125.8  219.63  5155.6  219.42  5197.5  220.44
  5220.4  222.74  5248.2  221.63    5278   223.4  5305.3  223.68  5349.7  225.35
  5355.8   224.8  5558.8  229.82  5564.8  230.48  5594.6  230.97  5687.3  234.61
    5730  235.69  5766.5   237.6  5830.7  239.65  5949.3  245.02  5960.6  245.21
#Mann= 5 ,-1 , 0
  4636.2      .1       0  4994.2     .07       0  5000.2      .1       0
  5687.3     .05       0  5949.3      .1       0
Bank Sta=4992.8,5018.2
XS Rating Curve= 0 ,0
Exp/Cntr=0.3,0.1

Type RM Length L Ch R = 1 ,10335   ,461,461,461
BEGIN DESCRIPTION:
UNT036 IN NURI 23.0
END DESCRIPTION:
XS GIS Cut Line= 3
      2308337.74     13313646.84      2307987.72     13313946.85
      2307887.72     13314346.84
#Sta/Elev= 30
  4530.6  226.81  4594.8  224.86  4636.5  224.48  4672.8  223.45  4693.6  223.66
  4779.2  221.32  4785.8  222.06  4820.9  219.99  4949.4  216.04  4963.6  214.38
  4988.3  210.44  4998.9  210.24  5001.7  209.74  5004.9  210.24  5009.6  211.18
  5022.5   211.3  5043.1  212.75  5050.9  214.43  5063.8  214.64  5097.3  216.94
  5125.6  217.65  5146.2  219.13  5197.8   220.6  5208.1  222.15  5215.8  222.64
  5228.7  222.09  5262.2  222.93  5280.2  223.91    5373  226.58  5403.9  228.67
#Mann= 3 ,-1 , 0
  4530.6      .1       0  4998.9     .07       0  5004.9      .1       0
Bank Sta=4963.6,5050.9
XS Rating Curve= 0 ,0
Exp/Cntr=0.3,0.1

Type RM Length L Ch R = 1 ,9874    ,386,386,386
BEGIN DESCRIPTION:
UNT036 IN NURI 22.0
END DESCRIPTION:
XS GIS Cut Line= 3
      2308387.75     13313496.85      2307587.72     13313746.85
      2307187.72     13313946.86
#Sta/Elev= 30
  4158.2  230.18  4342.1  224.43  4367.8  226.13  4379.8  223.44  4388.7  223.72
  4399.2  222.87  4671.6  218.36    4703   219.9  4715.1  217.85    4724  217.39
  4765.9  218.29  4812.5  217.48  4933.5   214.1    4965   212.2  4993.8  209.36
  5027.1  209.59  5046.5  208.91  5049.2  208.41  5052.5  208.91  5055.1  209.73
  5071.8  210.52  5085.8   212.2  5094.2  212.99  5144.5   213.9  5152.9  214.93
  5166.9  215.13  5278.7  222.15  5287.1  221.98  5323.4  225.02  5443.6   231.2
#Mann= 3 ,-1 , 0
  4158.2      .1       0  5046.5     .07       0  5052.5      .1       0
Bank Sta=4965,5085.8
XS Rating Curve= 0 ,0
Exp/Cntr=0.3,0.1

Type RM Length L Ch R = 1 ,9488    ,374,374,374
BEGIN DESCRIPTION:
UNT036 IN NURI 21.0
END DESCRIPTION:
XS GIS Cut Line= 3
      2307987.71     13313446.85      2307337.72     13313446.85
      2307087.76     13313496.85
#Sta/Elev= 30
  4377.8  220.59  4398.9  220.11  4507.8  218.62  4537.8  217.47  4552.5  217.91
  4637.8  217.05  4647.8  217.52  4677.8  217.23  4697.8  218.52  4727.8  216.65
  4747.8  217.33  4777.8  216.38  4807.8  216.42  4847.8  215.62  4877.8  213.96
  4907.8  213.52  4937.8  211.39  4967.8  207.56  4977.8  206.94  4987.8   207.2
  5014.8  206.54  5017.5  206.04  5020.8  206.54  5048.2  208.06  5068.6  211.23
  5119.6  215.53  5129.8  215.45  5221.6  220.64  5252.1  221.59  5282.7  224.38
#Mann= 5 ,-1 , 0
  4377.8      .1       0  4398.9     .05       0  4552.5      .1       0
  5014.8     .07       0  5020.8      .1       0
Bank Sta=4937.8,5068.6
XS Rating Curve= 0 ,0
Exp/Cntr=0.3,0.1

Type RM Length L Ch R = 1 ,9114    ,585,585,585
BEGIN DESCRIPTION:
UNT036 IN NURI 20.0
END DESCRIPTION:
XS GIS Cut Line= 3
      2307937.01     13313128.52      2307452.61     13313058.21
      2306926.55     13313138.94
#Sta/Elev= 30
  4325.2  219.03  4385.7  217.96  4526.6  215.25  4536.7  215.22  4556.9  216.79
  4576.3  214.31  4581.3  214.91  4587.2  213.93  4651.5  213.19  4786.8   214.9
  4836.8   213.2  4841.8  213.91  4920.8  211.02  4961.3  207.87  4968.4  205.85
  4981.5  204.63  5008.8  203.36  5011.6  202.86  5014.8  203.36  5036.8   204.1
  5062.4  209.95  5072.6  211.25  5168.5  216.05  5183.8  217.47  5214.2   218.1
  5231.8  219.86  5254.7   220.1  5295.1  223.05  5305.2  222.34  5346.9  224.46
#Mann= 4 ,-1 , 0
  4325.2     .05       0  4385.7      .1       0  5008.8     .07       0
  5014.8      .1       0
Bank Sta=4920.8,5072.6
XS Rating Curve= 0 ,0
Exp/Cntr=0.3,0.1

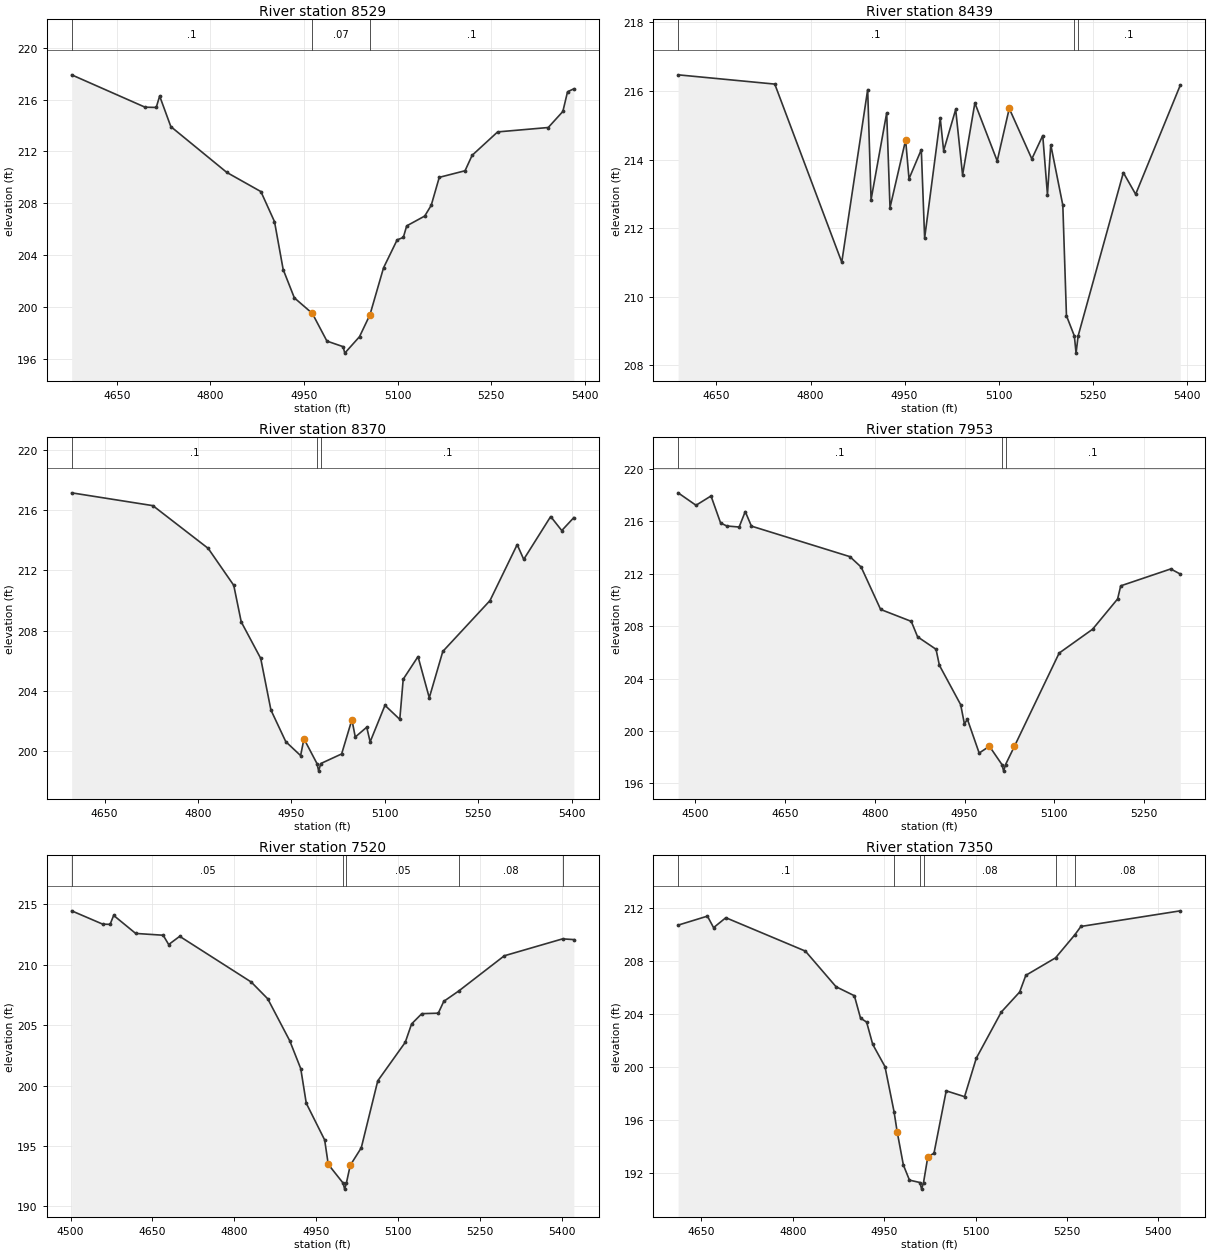
Type RM Length L Ch R = 1 ,8529    ,90,90,90
BEGIN DESCRIPTION:
UNT036 IN NURI 19.0
END DESCRIPTION:
XS GIS Cut Line= 2
      2307585.42     13312336.86      2306848.46     13312659.77
#Sta/Elev= 30
  4577.6  217.92  4695.2  215.42  4713.1   215.4  4718.6  216.28  4736.5  213.92
  4826.2  210.38  4880.8   208.9  4902.6  206.58  4916.5  202.88  4934.4  200.69
  4963.2  199.49  4986.6  197.35  5012.5  196.92  5015.2  196.42  5038.8  197.69
  5055.5  199.38  5077.3  203.01  5099.1  205.17    5109  205.36  5114.4  206.25
  5143.3  207.01  5153.7  207.84  5166.6     210  5207.9  210.51  5219.2   211.7
  5260.1  213.51  5341.2  213.85  5364.6  215.09  5372.1  216.61  5382.2  216.84
#Mann= 3 , 0 , 0
  4577.6      .1       0  4963.2     .07       0  5055.5      .1       0
Bank Sta=4963.2,5055.5
XS Rating Curve= 0 ,0
Exp/Cntr=0.3,0.1

Type RM Length L Ch R = 1 ,8439    ,69,69,69
BEGIN DESCRIPTION:
Mapping XS f274f12c
END DESCRIPTION:
XS GIS Cut Line= 2
      2307562.01     13312274.35      2306812.38     13312555.46
#Sta/Elev= 30
  4588.9  216.47    4743   216.2  4849.8  211.01  4891.1  216.04  4896.5  212.83
  4921.4  215.36  4926.7   212.6  4951.6  214.57    4957  213.44  4976.6  214.29
  4981.9  211.71  5006.8   215.2  5012.2  214.26  5031.4  215.46  5042.4  213.55
    5062  215.65  5097.6  213.96  5116.8  215.49  5152.8  214.02  5170.2   214.7
  5177.7  212.98    5183  214.43  5202.2  212.67    5208  209.45  5220.6  208.86
  5223.3  208.36  5226.6  208.86  5298.7  213.62  5318.3  212.99  5389.5  216.17
#Mann= 3 ,-1 , 0
  4588.9      .1       0  5220.6     .07       0  5226.6      .1       0
Bank Sta=4951.6,5116.8
XS Rating Curve= 0 ,0
Exp/Cntr=0.3,0.1

Type RM Length L Ch R = 1 ,8370    ,417,417,417
BEGIN DESCRIPTION:
UNT036 IN NURI 18.0
END DESCRIPTION:
XS GIS Cut Line= 2
      2307528.16     13312198.82      2306783.36     13312508.72
#Sta/Elev= 30
    4597  217.13  4727.5  216.28  4816.3  213.45  4857.4     211  4869.4  208.58
  4900.7  206.16  4917.1  202.74    4941  200.64  4964.8  199.72  4970.2  200.83
  4991.1  199.19  4993.8  198.69  4997.1  199.19  5030.7  199.83  5047.2   202.1
  5052.6  200.95    5071   201.6  5076.5  200.63  5100.3  203.05  5124.1  202.12
  5129.6  204.78  5153.4  206.28  5171.5  203.55  5193.2  206.62    5269  209.99
  5312.7   213.7  5323.2  212.72  5366.5  215.56  5384.3  214.63  5403.7  215.49
#Mann= 3 ,-1 , 0
    4597      .1       0  4991.1     .07       0  4997.1      .1       0
Bank Sta=4970.2,5047.2
XS Rating Curve= 0 ,0
Exp/Cntr=0.3,0.1

Type RM Length L Ch R = 1 ,7953    ,433,433,433
BEGIN DESCRIPTION:
Mapping XS 33cf0125
END DESCRIPTION:
XS GIS Cut Line= 2
      2307556.77     13311829.05      2306740.92     13312026.51
#Sta/Elev= 30
  4471.2  218.18  4501.1  217.23  4526.2  217.94  4542.2  215.88  4552.5  215.65
  4573.2  215.57  4583.4  216.75  4593.7  215.64  4758.3  213.31  4777.2  212.51
  4809.7  209.28  4860.9  208.37  4871.5  207.19  4902.3  206.24  4907.9  205.02
  4943.5  202.01  4949.7  200.55  4954.8  200.89  4974.4  198.32  4991.5  198.84
  5012.5  197.44  5015.3  196.94  5018.5  197.44  5033.4  198.84  5108.1  205.95
    5164  207.77  5205.8  210.08    5211  211.08  5294.6  212.37  5310.6  211.98
#Mann= 3 ,-1 , 0
  4471.2      .1       0  5012.5     .07       0  5018.5      .1       0
Bank Sta=4991.5,5033.4
XS Rating Curve= 0 ,0
Exp/Cntr=0.3,0.1

Type RM Length L Ch R = 1 ,7520    ,170,170,170
BEGIN DESCRIPTION:
UNT036 IN NURI 17.0
END DESCRIPTION:
XS GIS Cut Line= 2
      2307364.09      13311493.1      2306451.36     13311610.12
#Sta/Elev= 30
  4501.9  214.46  4558.7  213.36  4572.3  213.34  4578.9  214.08  4619.2  212.59
  4669.6  212.44  4679.7  211.67  4699.9  212.35  4830.9  208.57  4861.2  207.18
  4901.5  203.71  4921.7   201.4  4931.8  198.54  4965.5   195.5  4972.1  193.48
  4999.3  191.93  5002.1  191.43  5005.3  191.93  5012.4   193.4  5032.6  194.85
  5062.8  200.39  5113.2  203.58  5124.8   205.1  5143.5  205.95  5173.7  205.99
  5183.8  206.97    5211  207.82  5294.7  210.74  5401.5  212.14  5422.1  212.08
#Mann= 5 ,-1 , 0
  4501.9     .05       0  4999.3     .04       0  5005.3     .05       0
    5211     .08       0  5401.5     .05       0
Bank Sta=4972.1,5012.4
XS Rating Curve= 0 ,0
Exp/Cntr=0.3,0.1

Type RM Length L Ch R = 1 ,7350    ,444,444,444
BEGIN DESCRIPTION:
UNT036 IN NURI 16.0
END DESCRIPTION:
XS GIS Cut Line= 2
      2307215.63     13311355.08      2306395.34     13311433.21
#Sta/Elev= 30
  4611.9  210.69    4660  211.37  4670.1   210.5  4690.2  211.25  4820.7  208.73
    4871  206.04  4901.1  205.36  4911.2  203.67  4921.2  203.37  4931.2  201.69
  4951.3  200.01  4966.2  196.61  4971.4  195.07  4981.5  192.58  4991.5  191.44
  5008.6  191.26  5011.4  190.76  5014.6  191.26  5021.7  193.22  5031.7  193.46
  5051.8  198.18  5081.9  197.74  5101.1  200.64  5142.2  204.13  5172.3  205.64
  5182.4   206.9  5231.2  208.22    5263  209.97  5272.8  210.59  5435.9  211.77
#Mann= 6 ,-1 , 0
  4611.9      .1       0  4966.2     .08       0  5008.6     .07       0
  5014.6     .08       0  5231.2      .1       0    5263     .08       0
Bank Sta=4971.4,5021.7
XS Rating Curve= 0 ,0
Exp/Cntr=0.3,0.1