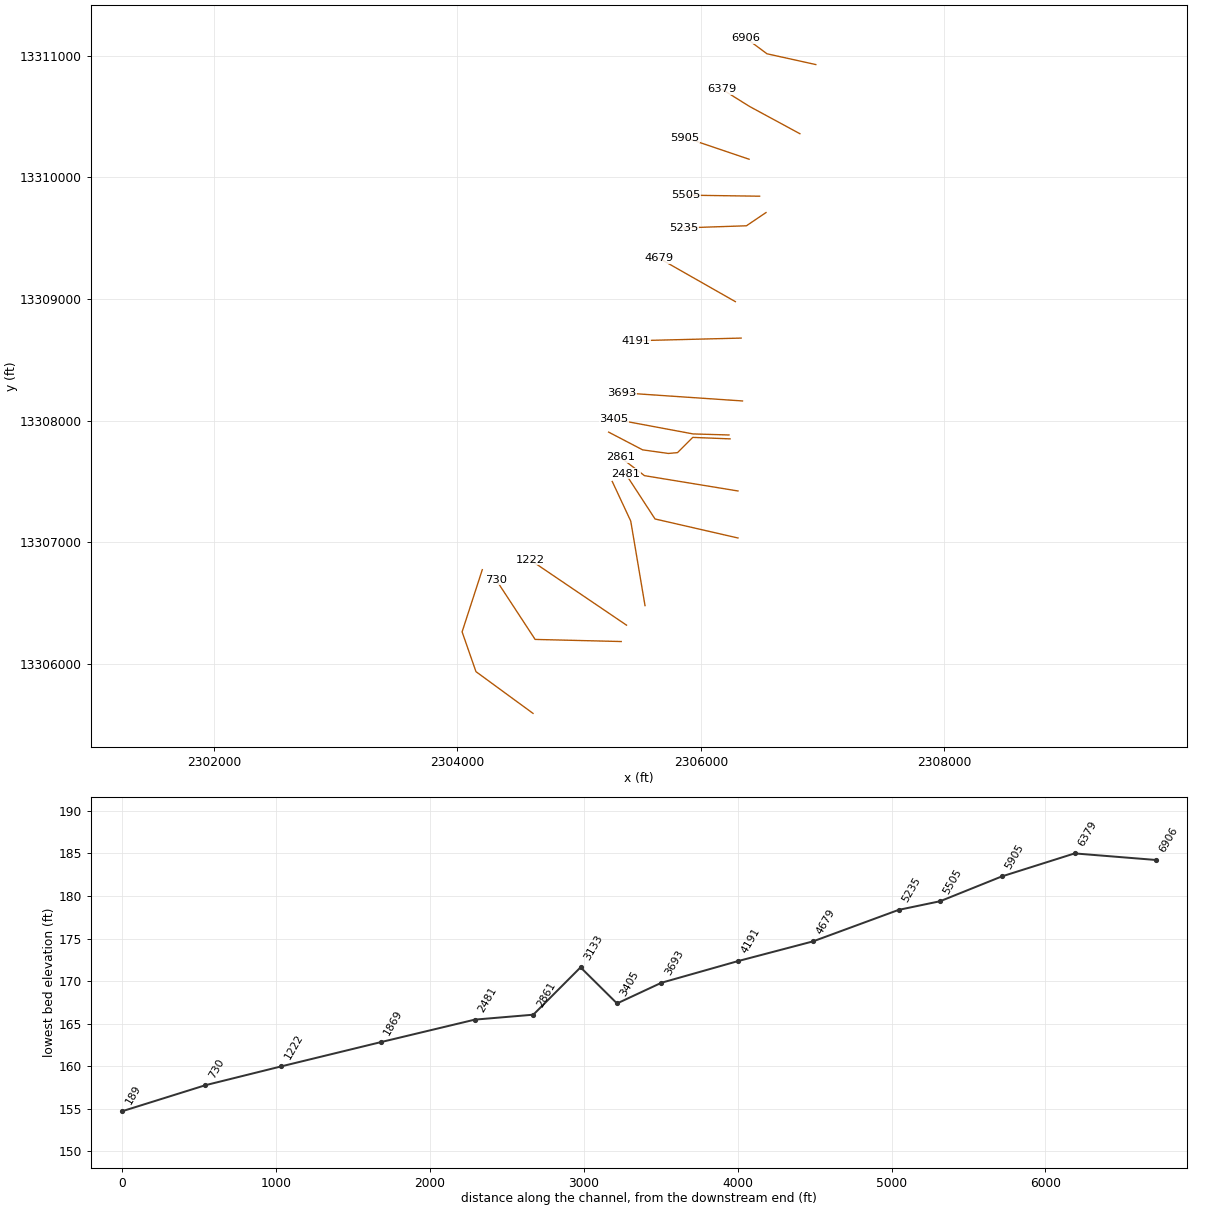
HEC-RAS study UNT036 IN NURI.prj: UNT036 IN NURI Base Level Engineering

--- UNT036 IN NURI.g01 (geometry) --- (continued)

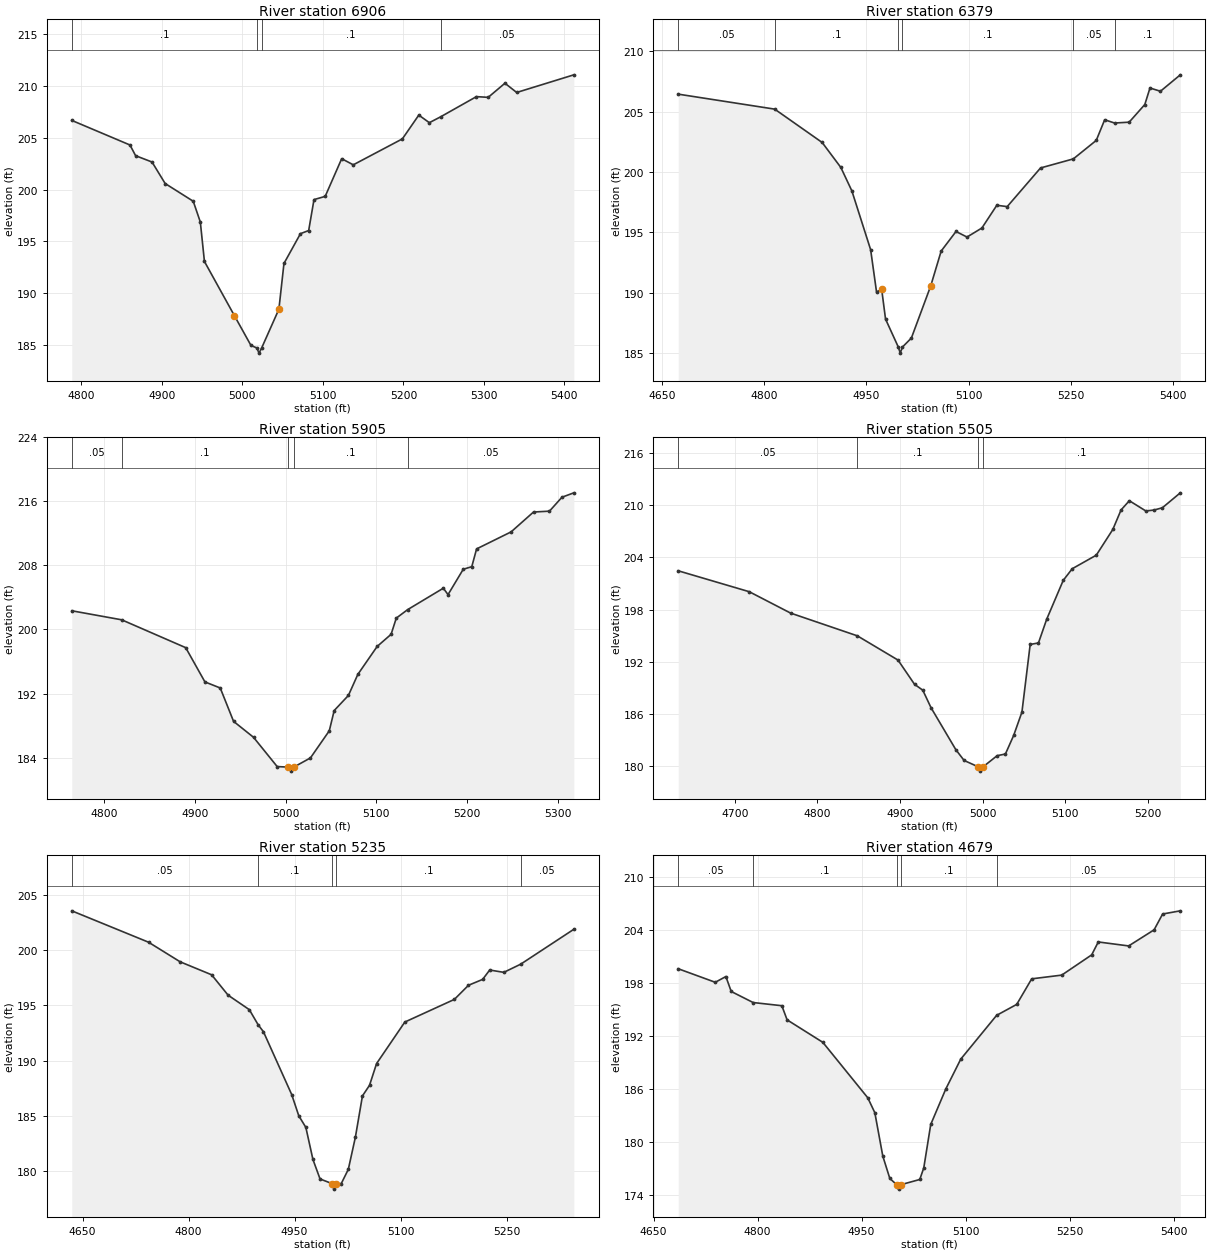
Type RM Length L Ch R = 1 ,6906    ,527,527,527
BEGIN DESCRIPTION:
UNT036 IN NURI 15.0
END DESCRIPTION:
XS GIS Cut Line= 3
      2306945.11     13310926.65      2306544.04      13311015.2
      2306373.05     13311142.15
#Sta/Elev= 30
    4788  206.66  4860.3  204.29  4867.3  203.26  4887.7  202.65    4904  200.58
  4938.9  198.87  4947.7  196.87  4952.8  193.07  4990.1  187.84  5010.6  184.98
  5017.9  184.74  5020.6  184.24  5023.9  184.74  5045.3  188.47  5051.6  192.88
  5072.1  195.75  5082.3  196.05  5088.9  199.03  5102.8  199.34  5123.3  202.97
  5137.7  202.38  5198.7  204.88  5219.1  207.17  5232.2  206.44  5246.1     207
  5290.7  208.95  5305.3  208.88  5326.1  210.24  5340.7  209.35  5411.7  211.05
#Mann= 4 ,-1 , 0
    4788      .1       0  5017.9     .07       0  5023.9      .1       0
  5246.1     .05       0
Bank Sta=4990.1,5045.3
XS Rating Curve= 0 ,0
Exp/Cntr=0.3,0.1

Type RM Length L Ch R = 1 ,6379    ,474,474,474
BEGIN DESCRIPTION:
UNT036 IN NURI 14.0
END DESCRIPTION:
XS GIS Cut Line= 3
      2306814.17     13310358.63      2306400.84      13310582.4
      2306173.43     13310724.54
#Sta/Elev= 30
  4673.2  206.45    4815  205.21  4884.8  202.45  4912.3  200.38  4928.5  198.44
  4956.1  193.57  4964.8  190.06  4972.3   190.3    4978  187.83  4996.8  185.51
  4999.6  185.01  5002.8  185.51    5016  186.26  5044.4  190.57  5059.8  193.46
  5081.6  195.08  5097.8  194.62  5119.7  195.37  5141.6  197.25  5156.9  197.14
  5205.9  200.34  5254.1  201.09  5287.8  202.62  5300.2  204.33  5314.7  204.06
  5336.2  204.13  5359.2  205.59  5366.8  206.96  5382.2  206.69  5411.4  208.05
#Mann= 6 ,-1 , 0
  4673.2     .05       0    4815      .1       0  4996.8     .07       0
  5002.8      .1       0  5254.1     .05       0  5314.7      .1       0
Bank Sta=4972.3,5044.4
XS Rating Curve= 0 ,0
Exp/Cntr=0.3,0.1

Type RM Length L Ch R = 1 ,5905    ,400,400,400
BEGIN DESCRIPTION:
UNT036 IN NURI 13.0
END DESCRIPTION:
XS GIS Cut Line= 2
      2306396.81     13310148.93       2305872.2     13310326.69
#Sta/Elev= 30
  4764.1  202.34  4819.2  201.21  4889.8  197.73    4911  193.45  4927.9  192.69
  4942.6  188.52  4964.6  186.53  4990.7  182.87    5003   182.8  5005.7   182.3
    5009   182.8  5027.4  183.95  5048.2  187.34  5053.6  189.87  5069.3  191.76
  5079.7  194.39    5101  197.88  5116.4   199.4  5122.1  201.42  5134.6  202.48
    5174  205.16  5179.2  204.36    5196  207.53  5205.4  207.85  5210.7  210.07
  5248.8   212.2  5273.5  214.68  5291.1  214.79  5304.9  216.53    5318  217.08
#Mann= 5 ,-1 , 0
  4764.1     .05       0  4819.2      .1       0    5003     .07       0
    5009      .1       0  5134.6     .05       0
Bank Sta=5003,5009
XS Rating Curve= 0 ,0
Exp/Cntr=0.3,0.1

Type RM Length L Ch R = 1 ,5505    ,270,270,270
BEGIN DESCRIPTION:
UNT036 IN NURI 12.0
END DESCRIPTION:
XS GIS Cut Line= 2
       2306483.7      13309845.1      2305876.06     13309853.78
#Sta/Elev= 30
  4631.6  202.46  4717.6  200.05  4767.6  197.59  4848.4  194.97  4897.6  192.18
  4917.6  189.39  4927.6  188.71  4937.6  186.69  4967.6  181.86  4977.6  180.62
  4994.6  179.89  4997.4  179.39  5000.6  179.89  5017.6  181.17  5027.6  181.36
  5037.6   183.5  5047.6  186.19  5057.6  193.98  5067.6  194.15  5077.6  196.89
  5097.6  201.36  5108.5   202.7  5137.6  204.26  5157.6  207.22  5167.6  209.47
  5177.6  210.53  5197.6  209.35  5207.6  209.46  5217.6  209.72  5239.3  211.44
#Mann= 4 ,-1 , 0
  4631.6     .05       0  4848.4      .1       0  4994.6     .07       0
  5000.6      .1       0
Bank Sta=4994.6,5000.6
XS Rating Curve= 0 ,0
Exp/Cntr=0.3,0.1

Type RM Length L Ch R = 1 ,5235    ,556,556,556
BEGIN DESCRIPTION:
UNT036 IN NURI 11.0
END DESCRIPTION:
XS GIS Cut Line= 3
      2306535.76     13309710.57      2306375.14     13309602.05
      2305858.68     13309584.69
#Sta/Elev= 30
  4634.6  203.57  4743.2  200.73  4788.1  198.95  4832.5  197.78  4855.9  195.93
  4885.9  194.62  4898.4  193.25  4905.9  192.62  4945.9  186.93  4955.9  185.01
  4965.9  183.96  4975.9  181.06    4986  179.29    5003  178.87  5005.7  178.37
    5009  178.87    5016  178.87    5026  180.16    5036  183.07    5046  186.81
    5056  187.77    5066  189.74    5106   193.5  5176.1  195.55  5196.1  196.83
  5216.1  197.36  5226.1  198.21  5246.1     198    5270  198.74  5345.2   201.9
#Mann= 5 ,-1 , 0
  4634.6     .05       0  4898.4      .1       0    5003     .07       0
    5009      .1       0    5270     .05       0
Bank Sta=5003,5009
XS Rating Curve= 0 ,0
Exp/Cntr=0.3,0.1

Type RM Length L Ch R = 1 ,4679    ,488,488,488
BEGIN DESCRIPTION:
UNT036 IN NURI 10.0
END DESCRIPTION:
XS GIS Cut Line= 2
      2306284.14     13308978.86      2305654.87      13309336.9
#Sta/Elev= 30
  4685.6  199.59    4739  198.06  4754.3  198.71    4762  197.02  4793.6  195.77
    4835  195.41  4842.6  193.81  4894.1  191.27  4958.9     185  4969.1  183.31
  4980.6   178.4  4990.7  175.88  5000.6  175.17  5003.4  174.67  5006.6  175.17
  5033.9  175.76  5039.7  177.08  5049.7  181.98  5071.4  185.99    5093  189.37
  5144.7  194.32  5173.7  195.56  5195.3  198.45  5238.6  198.87  5281.8  201.16
  5291.3  202.62  5335.1  202.17  5371.8  203.99  5384.1  205.78  5409.6  206.14
#Mann= 5 ,-1 , 0
  4685.6     .05       0  4793.6      .1       0  5000.6     .07       0
  5006.6      .1       0  5144.7     .05       0
Bank Sta=5000.6,5006.6
XS Rating Curve= 0 ,0
Exp/Cntr=0.3,0.1

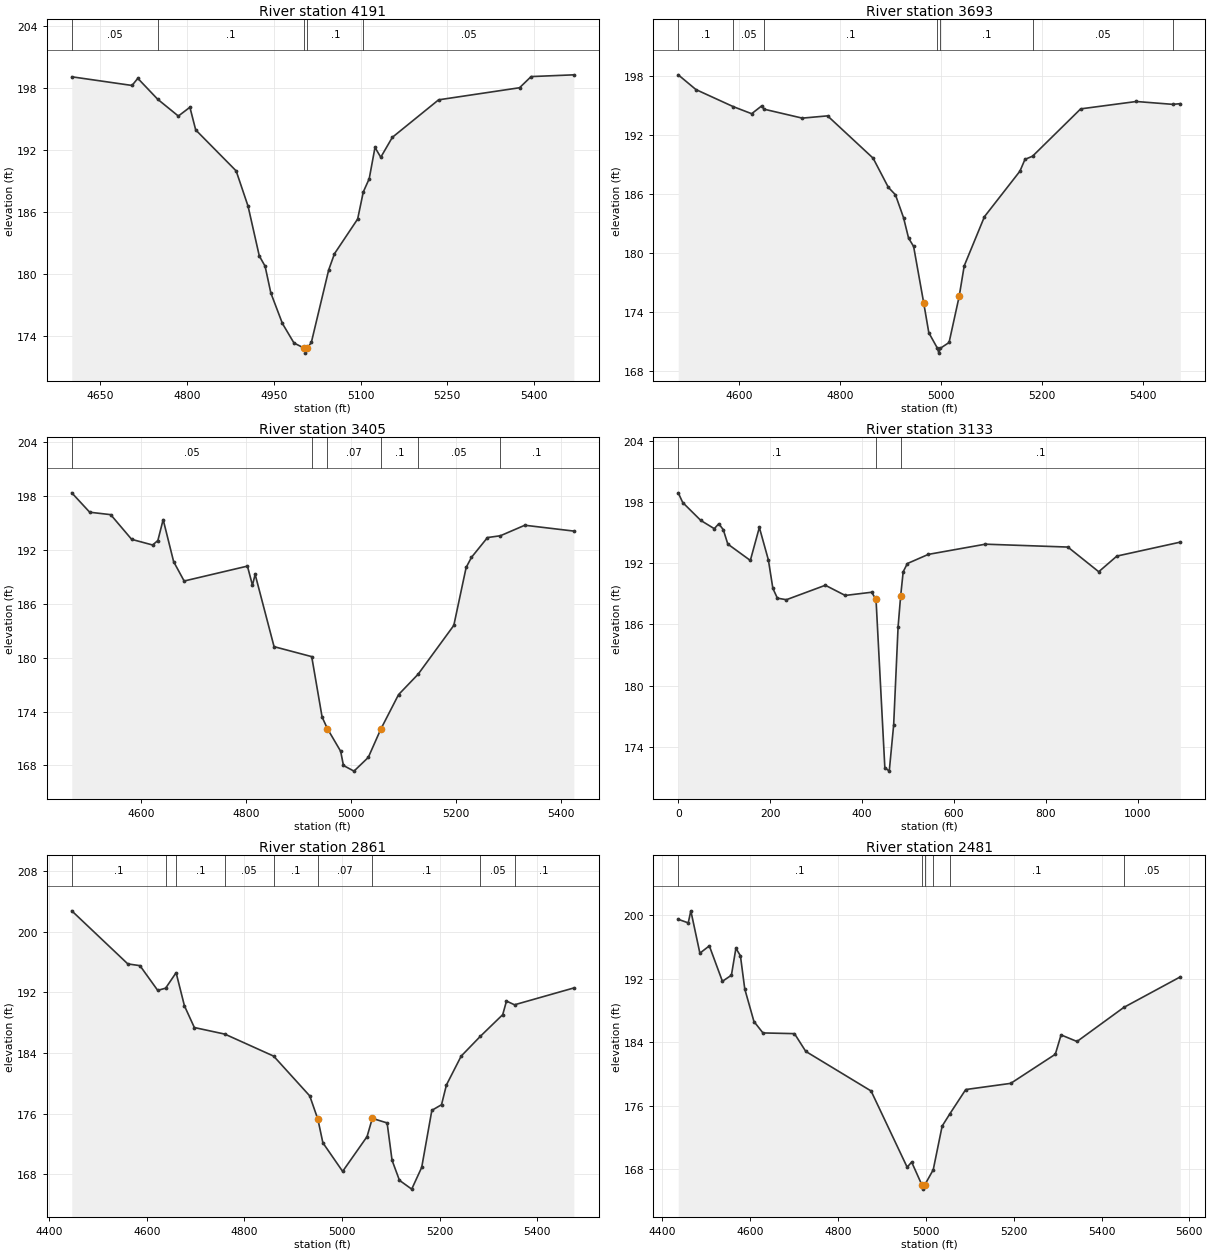
Type RM Length L Ch R = 1 ,4191    ,498,498,498
BEGIN DESCRIPTION:
UNT036 IN NURI 9.0
END DESCRIPTION:
XS GIS Cut Line= 2
      2306331.92     13308679.37      2305463.89     13308657.67
#Sta/Elev= 30
  4600.5   199.1  4704.7  198.26  4714.7  198.95  4749.2  196.92  4784.8   195.3
  4804.8  196.15  4814.8  193.96  4884.8  189.99  4905.4  186.57  4924.8  181.76
  4934.8  180.77  4944.8  178.17  4964.8  175.22  4984.8  173.33  5001.8  172.85
  5004.6  172.35  5007.8  172.85  5014.8  173.38  5044.8   180.4  5054.8  181.97
  5094.9  185.33  5104.7  187.96  5114.9  189.23  5124.9  192.26  5134.9  191.31
  5154.9  193.24  5234.9  196.87  5374.9  198.04  5394.9  199.12  5468.8  199.29
#Mann= 5 ,-1 , 0
  4600.5     .05       0  4749.2      .1       0  5001.8     .07       0
  5007.8      .1       0  5104.7     .05       0
Bank Sta=5001.8,5007.8
XS Rating Curve= 0 ,0
Exp/Cntr=0.3,0.1

Type RM Length L Ch R = 1 ,3693    ,288,288,288
BEGIN DESCRIPTION:
UNT036 IN NURI 8.0
END DESCRIPTION:
XS GIS Cut Line= 2
      2306342.76     13308162.87      2305350.83     13308230.01
#Sta/Elev= 30
  4479.1  198.08  4514.2  196.58  4588.4  194.84  4624.5  194.13  4644.5  194.93
  4648.9  194.59  4724.7  193.68  4774.8  193.91    4865  189.61  4895.1  186.65
  4909.2  185.89  4925.2  183.57  4935.2  181.49  4945.2  180.64  4965.2   174.9
  4975.3  171.87  4992.3   170.3  4995.1   169.8  4998.3   170.3  5015.4  170.88
  5035.4  175.56  5045.4  178.67  5085.5  183.67  5155.7  188.29  5165.7  189.49
  5180.7  189.81    5276  194.62  5386.2  195.37  5458.5  195.08  5473.3  195.15
#Mann= 7 ,-1 , 0
  4479.1      .1       0  4588.4     .05       0  4648.9      .1       0
  4992.3     .07       0  4998.3      .1       0  5180.7     .05       0
  5458.5      .1       0
Bank Sta=4965.2,5035.4
XS Rating Curve= 0 ,0
Exp/Cntr=0.3,0.1

Type RM Length L Ch R = 1 ,3405    ,237,237,237
BEGIN DESCRIPTION:
UNT036 IN NURI 7.0
END DESCRIPTION:
XS GIS Cut Line= 3
       2306231.9      13307883.3      2305936.77     13307891.98
      2305285.77      13308013.5
#Sta/Elev= 30
  4467.9  198.36  4502.1   196.2  4542.1  195.93  4582.1  193.18  4622.1  192.55
  4632.1  193.05  4642.2  195.38  4662.2  190.69  4682.2  188.54  4802.9   190.2
  4812.5  188.07  4817.6  189.28  4853.7  181.23  4925.5  180.12  4945.3  173.39
  4955.5  172.09  4980.7  169.58    4986     168  5006.1  167.37  5033.4   168.9
  5057.2  172.04  5091.1  175.89  5128.4  178.16  5196.5   183.6    5220  190.05
  5230.1  191.17  5260.7  193.38  5285.3  193.58  5331.9  194.75  5425.4   194.1
#Mann= 6 ,-1 , 0
  4467.9     .05       0  4925.5      .1       0  4955.5     .07       0
  5057.2      .1       0  5128.4     .05       0  5285.3      .1       0
Bank Sta=4955.5,5057.2
XS Rating Curve= 0 ,0
Exp/Cntr=0.3,0.1

Type RM Length L Ch R = 1 ,3133    ,307,307,307
BEGIN DESCRIPTION:
UNT036 IN NURI 6.1
END DESCRIPTION:
XS GIS Cut Line= 6
      2306241.18    13307851.309     2305933.888    13307863.462
     2305808.866     13307738.33     2305734.235    13307731.517
      2305522.43    13307761.031     2305242.916    13307906.865
#Sta/Elev= 30
       0198.89339.810863197.939449.05431196.1899 78.4869195.379788.29776195.8623
98.10863195.2783107.9195193.8706156.9738192.2654176.5955195.5045196.2173192.3236
206.0281 189.527 215.839188.5697235.4607188.4167320.2891189.8334363.5556188.8353
421.0083189.1491 430.612188.4486449.8194171.9614459.4231171.6158469.0268176.1516
478.6305185.7378484.1887 188.763 489.747191.1567498.8719191.9629544.4965192.8597
 668.683193.8599 848.326193.5777915.5032191.1586954.9704192.69291093.105194.0608
#Mann= 3 ,-1 , 0
       0      .1       0 430.612     .07       0484.1887      .1       0
Bank Sta=430.612,484.1887
XS Rating Curve= 0 ,0
Exp/Cntr=0.3,0.1

Type RM Length L Ch R = 1 ,2861    ,380,380,380
BEGIN DESCRIPTION:
UNT036 IN NURI 6.0
END DESCRIPTION:
XS GIS Cut Line= 3
       2306305.7     13307423.23      2305537.47     13307549.09
      2305337.85     13307700.97
#Sta/Elev= 30
  4445.9  202.75  4560.8  195.75  4585.7  195.52  4622.1  192.26  4638.3  192.55
  4659.8  194.59  4676.9  190.22  4697.2  187.36  4759.8  186.49  4859.8  183.59
  4933.8  178.34  4950.5  175.25  4960.7  172.16  5001.2  168.39  5051.3  172.98
    5062  175.38  5092.4  174.78  5102.5  169.86  5117.7  167.21  5142.8  166.05
  5163.3  168.92  5184.1  176.44  5203.9  177.18    5214  179.79  5244.2  183.59
  5283.5   186.2  5329.4  189.06  5337.1  190.85  5353.6  190.36  5475.2  192.58
#Mann= 9 ,-1 , 0
  4445.9      .1       0  4638.3     .05       0  4659.8      .1       0
  4759.8     .05       0  4859.8      .1       0  4950.5     .07       0
    5062      .1       0  5283.5     .05       0  5353.6      .1       0
Bank Sta=4950.5,5062
XS Rating Curve= 0 ,0
Exp/Cntr=0.3,0.1

Type RM Length L Ch R = 1 ,2481    ,612,612,612
BEGIN DESCRIPTION:
UNT036 IN NURI 5.0
END DESCRIPTION:
XS GIS Cut Line= 3
      2306305.73     13307036.93      2305624.27     13307193.19
      2305381.96     13307565.31
#Sta/Elev= 30
  4436.2   199.5    4459  199.05  4464.9  200.57  4485.5  195.23    4507  196.15
  4536.8  191.68  4557.3  192.45  4567.5  195.85  4577.8   194.9  4587.7  190.71
  4608.6  186.61  4629.1  185.17  4700.9  185.08  4726.6  182.84  4875.3  177.85
  4957.4  168.24  4967.7  168.88  4991.2  165.97    4994  165.47  4997.2  165.97
  5016.8  167.91  5037.1  173.42  5054.8  174.98  5090.8  178.03  5193.3  178.81
  5294.8  182.48  5307.9  184.92  5344.2  184.09  5450.8  188.39  5579.4  192.24
#Mann= 6 ,-1 , 0
  4436.2      .1       0  4991.2     .07       0  4997.2      .1       0
  5016.8     .16       0  5054.8      .1       0  5450.8     .05       0
Bank Sta=4991.2,4997.2
XS Rating Curve= 0 ,0
Exp/Cntr=0.3,0.1

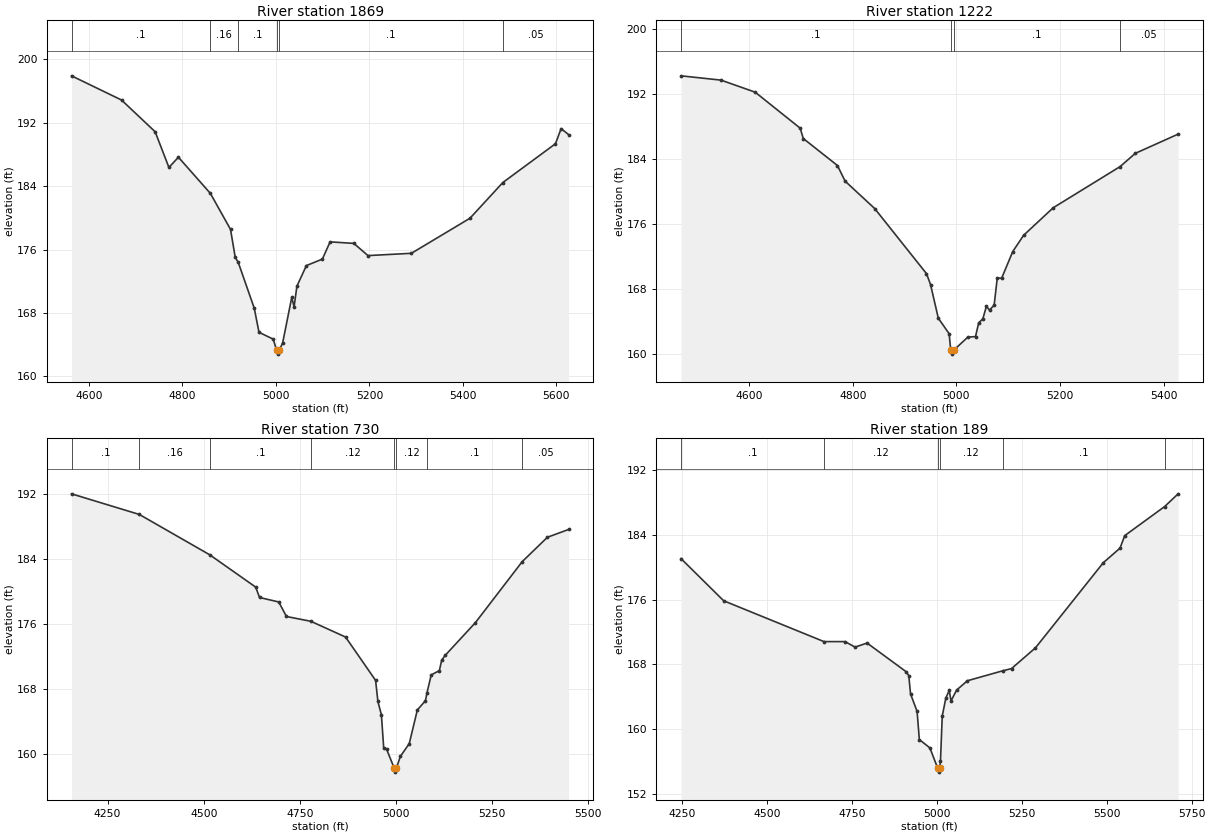
Type RM Length L Ch R = 1 ,1869    ,647,647,647
BEGIN DESCRIPTION:
UNT036 IN NURI 4.0
END DESCRIPTION:
XS GIS Cut Line= 3
      2305541.81     13306481.35      2305424.62     13307175.83
      2305272.72     13307501.33
#Sta/Elev= 30
  4562.7   197.9  4669.7  194.85  4741.6  190.85  4771.1  186.35  4791.4  187.64
  4859.8  183.08  4902.9  178.54  4912.9  175.04  4919.5  174.37  4953.7   168.6
  4963.8  165.57  4994.2  164.71  5001.4  163.32  5004.1  162.82  5007.4  163.32
  5014.5  164.26  5033.9  169.98  5038.9  168.78  5044.9  171.38  5065.2  173.98
  5099.4   174.8  5115.9  176.97  5166.6  176.78    5197  175.24  5289.9  175.53
  5415.2  179.95  5485.5  184.45  5598.1  189.34  5610.2  191.25  5626.2  190.49
#Mann= 6 ,-1 , 0
  4562.7      .1       0  4859.8     .16       0  4919.5      .1       0
  5001.4     .07       0  5007.4      .1       0  5485.5     .05       0
Bank Sta=5001.4,5007.4
XS Rating Curve= 0 ,0
Exp/Cntr=0.3,0.1

Type RM Length L Ch R = 1 ,1222    ,492,492,492
BEGIN DESCRIPTION:
UNT036 IN NURI 3.0
END DESCRIPTION:
XS GIS Cut Line= 2
       2305389.9     13306320.79      2304595.66     13306858.97
#Sta/Elev= 30
  4468.6   194.2  4545.8  193.67  4611.6  192.19  4698.5  187.76  4704.5  186.49
  4770.4  183.17  4785.3  181.24  4842.3  177.88  4942.3  169.87  4950.1  168.53
  4965.1  164.39    4986  162.48  4989.1  160.47  4991.8  159.97  4995.1  160.47
    5022  162.06  5036.9  162.13    5043   163.8  5051.1  164.33  5057.9  165.84
    5064  165.39  5072.9     166  5078.9  169.34  5087.3   169.3  5108.8  172.59
  5129.8  174.59  5186.8  177.97  5315.8  183.03  5345.5  184.67    5428  187.03
#Mann= 4 ,-1 , 0
  4468.6      .1       0  4989.1     .07       0  4995.1      .1       0
  5315.8     .05       0
Bank Sta=4989.1,4995.1
XS Rating Curve= 0 ,0
Exp/Cntr=0.3,0.1

Type RM Length L Ch R = 1 ,730     ,541,541,541
BEGIN DESCRIPTION:
UNT036 IN NURI 2.0
END DESCRIPTION:
XS GIS Cut Line= 3
      2305346.48     13306186.25      2304639.03     13306203.61
      2304318.57     13306692.96
#Sta/Elev= 30
  4156.3  192.04  4332.6   189.5  4515.7  184.53  4635.2  180.55  4645.2  179.27
  4695.2  178.72  4715.2  176.93  4778.6  176.34  4868.9   174.4    4947  169.06
    4953  166.46  4962.1  164.82  4968.1  160.73  4975.4  160.61  4995.3  158.26
  4998.1  157.76  5001.3  158.26  5011.3  159.69  5034.5  161.27  5055.6  165.42
  5076.6  166.55  5080.7  167.54  5091.7  169.74  5112.8  170.26  5118.9  171.55
  5127.9  172.14  5206.3  176.16  5328.3  183.69  5393.8  186.69  5448.9  187.65
#Mann= 8 ,-1 , 0
  4156.3      .1       0  4332.6     .16       0  4515.7      .1       0
  4778.6     .12       0  4995.3     .07       0  5001.3     .12       0
  5080.7      .1       0  5328.3     .05       0
Bank Sta=4995.3,5001.3
XS Rating Curve= 0 ,0
Exp/Cntr=0.3,0.1

Type RM Length L Ch R = 1 ,189     ,0,0,0
BEGIN DESCRIPTION:
UNT036 IN NURI 1.0
END DESCRIPTION:
XS GIS Cut Line= 4
      2304621.65     13305595.98      2304152.92     13305938.85
       2304039.1     13306265.82      2304204.99     13306776.49
#Sta/Elev= 30
  4246.4  181.05  4371.9  175.85  4667.3  170.81  4729.4  170.81  4758.8  170.13
  4794.3  170.63  4909.7  167.08    4917  166.61  4922.3  164.34  4941.5   162.2
  4948.1  158.72  4979.2  157.69    5002   155.2  5004.7   154.7    5008   155.2
  5010.3  156.02  5015.6  161.63  5026.2  163.85  5036.1  164.79  5041.4  163.49
    5058  164.83  5089.7  165.98  5193.1   167.2  5219.6  167.48  5290.1  170.04
  5489.9  180.55  5539.2  182.35    5553  183.89  5670.5  187.48  5710.3  189.05
#Mann= 6 ,-1 , 0
  4246.4      .1       0  4667.3     .12       0    5002     .07       0
    5008     .12       0  5193.1      .1       0  5670.5     .05       0
Bank Sta=5002,5008
XS Rating Curve= 0 ,0
Exp/Cntr=0.3,0.1

Chan Stop Cuts=-1
Use User Specified Reach Order=0
Composite Channel Slope=5