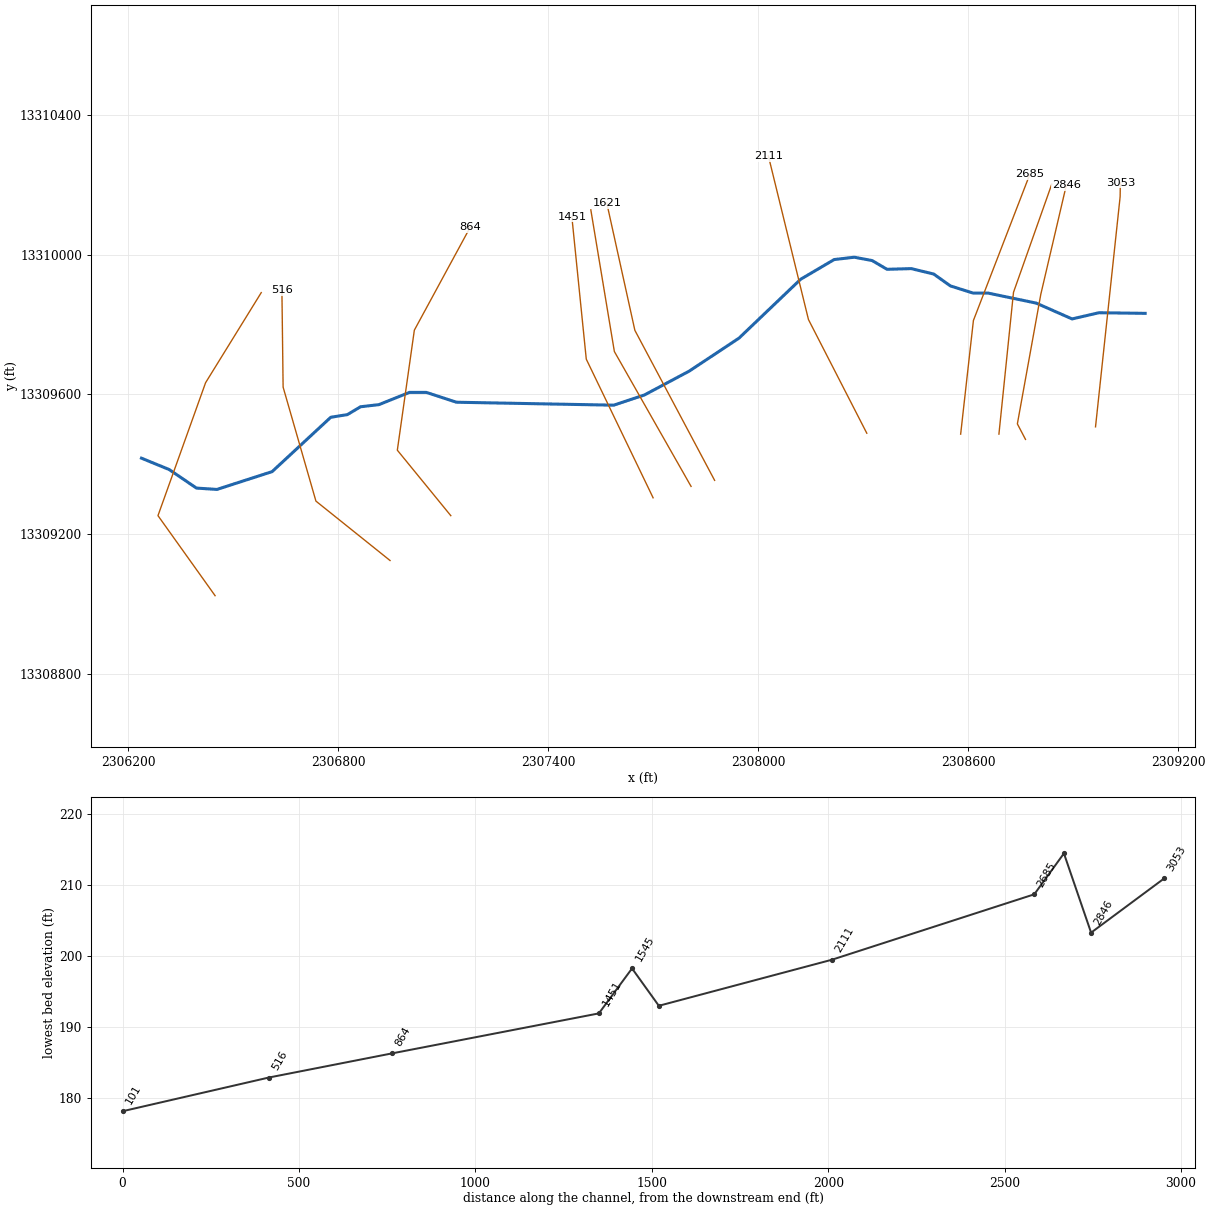
--- UNT037 IN NURI.prj (project) ---

Proj Title=UNT037 IN NURI Base Level Engineering
Current Plan=p01
Default Exp/Contr=0.3,0.1
English Units
Geom File=g01
Flow File=f01
Plan File=p01
BEGIN DESCRIPTION:
UNT037 IN NURI
END DESCRIPTION:

--- UNT037 IN NURI.p01 (plan) ---

Plan Title=Multiple Run
Short Identifier=Multiple
Geom File=g01
Flow File=f01
Subcritical Flow
K Sum by GR= 0
Std Step Tol= 0.01
Critical Tol= 0.01
Num of Std Step Trials= 20
Max Error Tol= 0.3
Flow Tol Ratio= 0.001
Split Flow NTrial= 30
Split Flow Tol= 0.02
Split Flow Ratio= 0.02
Log Output Level= 0
Friction Slope Method= 1
Unsteady Friction Slope Method= 2
Unsteady Bridges Friction Slope Method= 1
Parabolic Critical Depth
Global Vel Dist=  1 , 1 , 1
Global Log Level= 0
CheckData=True
Encroach Param= -1, 0, 0, 0
BEGIN DESCRIPTION:
Multiple Run
END DESCRIPTION:

--- UNT037 IN NURI.f01 (steady flow) ---

Flow Title=Multiple
Number of Profiles=7
Profile Names=10-year,25-year,50-year,1pct_min,100-year,1pct_plu,500-year
River Rch & RM= UNT037 IN NURI,Reach-1,3053
     778    1124    1421    1313    1776    2401    2782
Boundary for River Rch & Prof#=UNT037 IN NURI,Reach-1,1
Up Type=0
Dn Type=3
Dn Slope=0.005
Boundary for River Rch & Prof#=UNT037 IN NURI,Reach-1,2
Up Type=0
Dn Type=3
Dn Slope=0.005
Boundary for River Rch & Prof#=UNT037 IN NURI,Reach-1,3
Up Type=0
Dn Type=3
Dn Slope=0.005
Boundary for River Rch & Prof#=UNT037 IN NURI,Reach-1,4
Up Type=0
Dn Type=3
Dn Slope=0.005
Boundary for River Rch & Prof#=UNT037 IN NURI,Reach-1,5
Up Type=0
Dn Type=3
Dn Slope=0.005
Boundary for River Rch & Prof#=UNT037 IN NURI,Reach-1,6
Up Type=0
Dn Type=3
Dn Slope=0.005
Boundary for River Rch & Prof#=UNT037 IN NURI,Reach-1,7
Up Type=0
Dn Type=3
Dn Slope=0.005

--- UNT037 IN NURI.g01 (geometry) ---

Geom Title=Existing Conditions

River Reach=UNT037 IN NURI,Reach-1
Reach XY= 30
      2309106.06     13309831.66      2308973.89     13309833.48
      2308897.04     13309815.69      2308794.93     13309860.97
      2308657.09     13309889.73      2308614.24     13309889.72
      2308549.36     13309910.28      2308501.57     13309944.33
      2308437.34     13309959.84      2308368.21     13309957.84
      2308325.94     13309982.84      2308274.80     13309992.46
      2308217.43     13309985.83      2308121.37     13309929.28
      2307945.34     13309760.73      2307803.19     13309666.32
      2307675.15     13309597.96      2307587.26     13309568.67
      2307137.82     13309577.10      2307051.87     13309605.24
      2307003.54     13309605.30      2306916.32     13309570.23
      2306863.77     13309564.11      2306826.10     13309541.65
      2306778.67     13309534.02      2306611.06     13309378.32
      2306453.30     13309327.31      2306394.90     13309331.17
      2306316.70     13309384.38      2306237.72     13309416.86

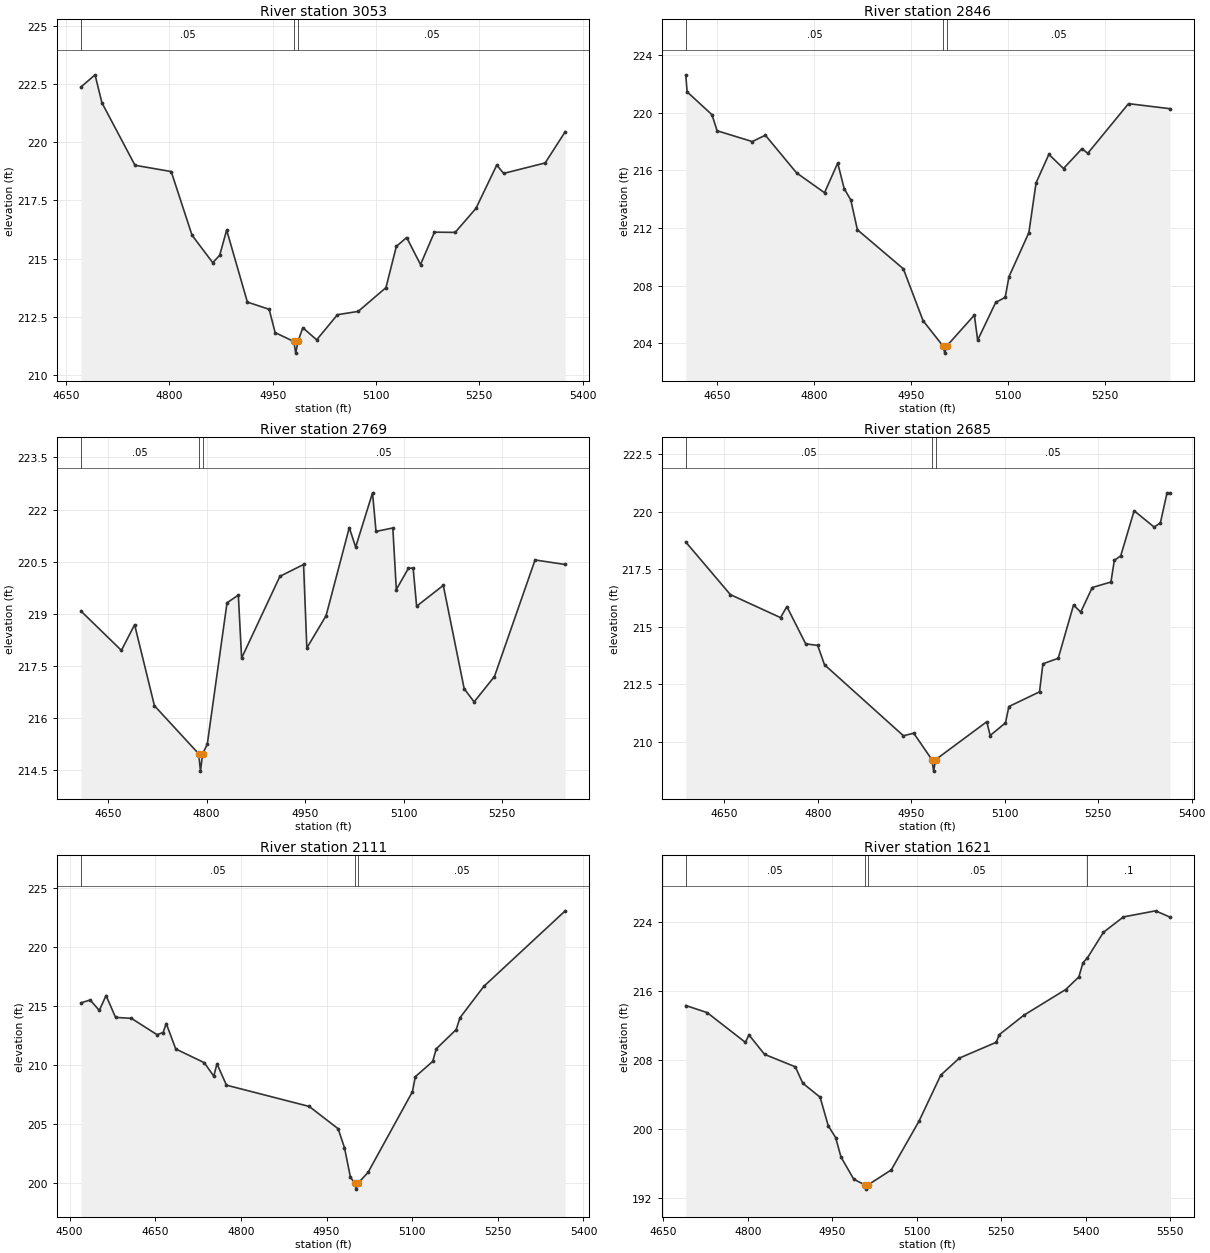
Type RM Length L Ch R = 1,3053,207,207,207
BEGIN DESCRIPTION:
UNT037 IN NURI 6.0
END DESCRIPTION:
XS GIS Cut Line= 3
      2308964.12     13309506.59      2309034.43     13310165.41
      2309035.06     13310205.95
#Sta/Elev= 30
  4671.6  222.37  4692.0  222.89  4702.0  221.69  4750.0  219.01  4802.6  218.74
  4832.8  216.01  4862.9  214.83  4873.0  215.15  4883.1  216.23  4913.2  213.14
  4944.8  212.83  4953.5  211.83  4980.6  211.45  4983.4  210.95  4986.6  211.45
  4993.7  212.04  5013.8  211.52  5044.0  212.60  5074.1  212.74  5114.4  213.76
  5129.5  215.53  5144.5  215.91  5164.6  214.75  5184.8  216.14  5214.9  216.13
  5245.1  217.16  5275.3  219.02  5285.3  218.66  5345.6  219.11  5374.7  220.45
#Mann=3,-1,0
  4671.6    0.05       0  4980.6    0.03       0  4986.6    0.05       0
Bank Sta=4980.6,4986.6
Exp/Cntr=0.3,0.1

Type RM Length L Ch R = 1,2846,77,77,77
BEGIN DESCRIPTION:
Mapping XS 73742b63
END DESCRIPTION:
XS GIS Cut Line= 4
      2308764.01     13309470.61      2308740.76     13309515.11
      2308807.87     13309886.77      2308880.79     13310199.30
#Sta/Elev= 30
  4601.8  222.63  4603.9  221.45  4642.4  219.86  4650.2  218.75  4704.6  218.00
  4724.9  218.44  4773.1  215.83  4816.4  214.45  4836.8  216.51  4846.8  214.73
  4857.0  213.95  4867.2  211.88  4938.3  209.17  4968.8  205.57  4999.5  203.82
  5002.3  203.32  5005.5  203.82  5048.1  205.96  5053.2  204.22  5081.1  206.84
  5095.8  207.19  5101.6  208.62  5132.4  211.68  5143.5  215.13  5163.3  217.11
  5186.0  216.13  5214.6  217.51  5223.4  217.18  5286.5  220.63  5350.6  220.28
#Mann=3,-1,0
  4601.8    0.05       0  4999.5    0.03       0  5005.5    0.05       0
Bank Sta=4999.5,5005.5
Exp/Cntr=0.3,0.1

Type RM Length L Ch R = 1,2769,84,84,84
BEGIN DESCRIPTION:
Mapping XS 90b83cc1
END DESCRIPTION:
XS GIS Cut Line= 3
      2308688.07     13309485.68      2308729.74     13309891.98
      2308839.13     13310201.91
#Sta/Elev= 30
  4608.7  219.08  4670.2  217.95  4690.3  218.69  4720.5  216.36  4787.8  214.98
  4790.6  214.48  4793.8  214.98  4800.9  215.25  4831.0  219.32  4848.2  219.54
  4853.2  217.73  4911.5  220.08  4947.5  220.42  4952.5  218.02  4981.8  218.95
  5017.1  221.48  5026.8  220.92  5052.5  222.48  5057.8  221.37  5083.4  221.47
  5088.7  219.70  5107.1  220.31  5114.3  220.32  5119.6  219.22  5160.2  219.82
  5192.0  216.85  5207.1  216.47  5238.1  217.20  5299.9  220.55  5345.8  220.42
#Mann=3,-1,0
  4608.7    0.05       0  4787.8    0.03       0  4793.8    0.05       0
Bank Sta=4787.8,4793.8
Exp/Cntr=0.3,0.1

Type RM Length L Ch R = 1,2685,574,574,574
BEGIN DESCRIPTION:
Mapping XS 62d8ffee
END DESCRIPTION:
XS GIS Cut Line= 3
      2308578.70     13309485.69      2308615.16     13309811.25
      2308776.62     13310230.53
#Sta/Elev= 30
  4588.3  218.69  4659.9  216.40  4740.4  215.40  4750.5  215.88  4780.7  214.26
  4800.0  214.19  4810.9  213.35  4937.5  210.26  4954.1  210.37  4983.2  209.22
  4986.0  208.72  4989.2  209.22  5071.3  210.87  5076.7  210.27  5101.3  210.82
  5106.7  211.53  5155.9  212.17  5161.3  213.39  5185.9  213.63  5210.5  215.95
  5222.0  215.64  5240.5  216.71  5270.5  216.95  5275.9  217.89  5286.2  218.09
  5307.7  220.05  5339.8  219.34  5349.8  219.52  5360.5  220.83  5365.2  220.83
#Mann=3,-1,0
  4588.3    0.05       0  4983.2    0.03       0  4989.2    0.05       0
Bank Sta=4983.2,4989.2
Exp/Cntr=0.3,0.1

Type RM Length L Ch R = 1,2111,490,490,490
BEGIN DESCRIPTION:
UNT037 IN NURI 5.0
END DESCRIPTION:
XS GIS Cut Line= 3
      2308310.46     13309488.34      2308143.80     13309813.85
      2308029.30     13310282.27
#Sta/Elev= 30
  4520.1  215.25  4536.2  215.49  4552.1  214.61  4564.0  215.87  4580.6  214.02
  4608.4  213.94  4653.2  212.56  4663.8  212.74  4669.4  213.50  4686.0  211.35
  4736.0  210.19  4752.6  209.05  4758.2  210.10  4774.8  208.29  4919.8  206.49
  4970.3  204.61  4981.5  203.00  4991.8  200.53  4999.1  200.00  5001.9  199.50
  5005.1  200.00  5022.7  200.91  5100.4  207.73  5105.6  209.01  5136.0  210.30
  5142.1  211.36  5177.1  212.99  5183.7  213.99  5225.4  216.64  5368.0  223.03
#Mann=3,-1,0
  4520.1    0.05       0  4999.1    0.03       0  5005.1    0.05       0
Bank Sta=4999.1,5005.1
Exp/Cntr=0.3,0.1

Type RM Length L Ch R = 1,1621,76,76,76
BEGIN DESCRIPTION:
UNT037 IN NURI 4.0
END DESCRIPTION:
XS GIS Cut Line= 3
      2307875.58     13309353.33      2307647.71     13309783.04
      2307567.42     13310147.61
#Sta/Elev= 30
  4689.8  214.35  4727.7  213.53  4795.7  210.07  4802.0  210.94  4829.6  208.68
  4884.3  207.23  4897.5  205.33  4928.3  203.70  4942.8  200.38  4955.9  199.01
  4965.4  196.75  4988.1  194.17  5007.6  193.52  5010.3  193.02  5013.6  193.52
  5054.6  195.25  5104.2  200.95  5142.5  206.26  5175.5  208.24  5241.1  210.08
  5246.3  210.96  5290.0  213.22  5364.4  216.21  5387.7  217.67  5395.1  219.33
  5402.8  219.87  5431.4  222.86  5466.8  224.64  5524.0  225.35  5549.5  224.62
#Mann=4,-1,0
  4689.8    0.05       0  5007.6    0.03       0  5013.6    0.05       0
  5402.8     0.1       0
Bank Sta=5007.6,5013.6
Exp/Cntr=0.3,0.1

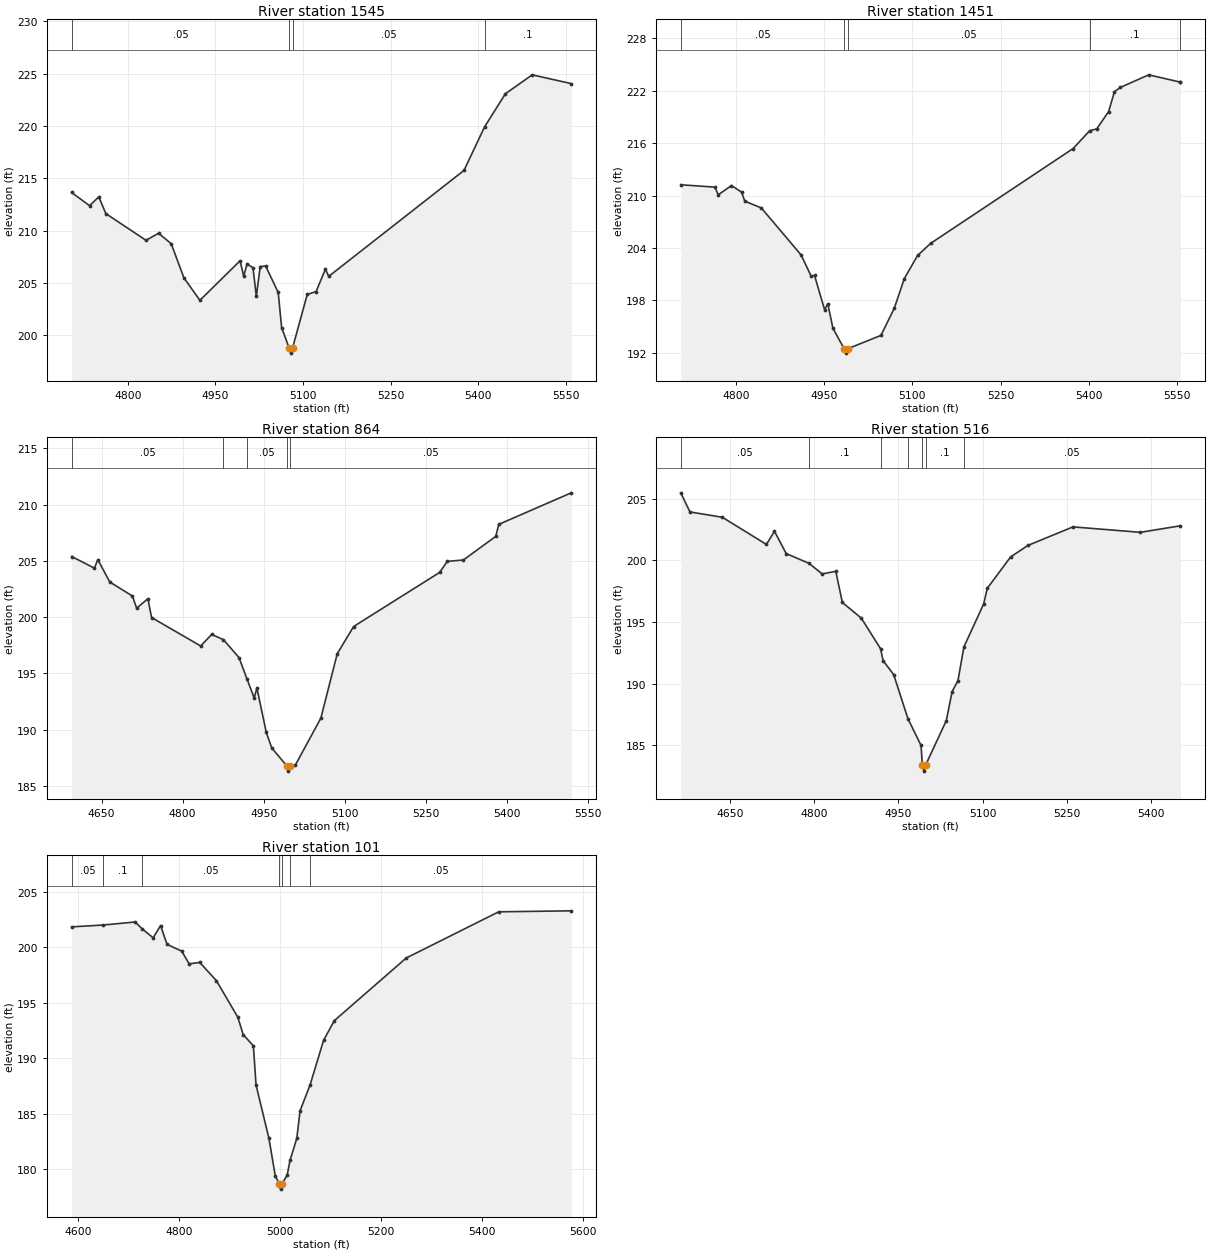
Type RM Length L Ch R = 1,1545,94,94,94
BEGIN DESCRIPTION:
Mapping XS 5556a8f0
END DESCRIPTION:
XS GIS Cut Line= 3
      2307808.29     13309336.00      2307589.12     13309722.27
      2307521.84     13310128.11
#Sta/Elev= 30
  4703.8  213.64  4734.4  212.38  4750.3  213.22  4762.3  211.62  4831.1  209.07
  4852.7  209.74  4874.3  208.74  4896.0  205.48  4923.4  203.33  4992.2  207.11
  4998.4  205.64  5004.1  206.80  5014.3  206.45  5020.0  203.71  5026.7  206.55
  5035.9  206.62  5057.5  204.08  5063.3  200.73  5076.1  198.78  5078.9  198.28
  5082.1  198.78  5107.2  203.89  5122.4  204.17  5138.3  206.31  5144.0  205.62
  5375.6  215.75  5410.8  219.91  5446.5  223.08  5492.4  224.89  5559.3  224.05
#Mann=4,-1,0
  4703.8    0.05       0  5076.1    0.03       0  5082.1    0.05       0
  5410.8     0.1       0
Bank Sta=5076.1,5082.1
Exp/Cntr=0.3,0.1

Type RM Length L Ch R = 1,1451,587,587,587
BEGIN DESCRIPTION:
UNT037 IN NURI 3.0
END DESCRIPTION:
XS GIS Cut Line= 3
      2307699.81     13309303.39      2307508.82     13309700.57
      2307467.59     13310108.58
#Sta/Elev= 30
  4705.6  211.23  4763.7  210.96  4769.3  210.08  4791.9  211.14  4809.0  210.39
  4814.6  209.35  4842.7  208.58  4910.6  203.18  4927.7  200.74  4933.3  200.85
  4950.4  196.93  4955.9  197.61  4964.7  194.78  4983.8  192.45  4986.6  191.95
  4989.8  192.45  5046.4  193.98  5069.1  197.08  5086.2  200.48  5108.8  203.13
  5131.1  204.52  5373.7  215.38  5401.6  217.40  5414.0  217.64  5434.1  219.61
  5444.1  221.90  5454.2  222.38  5502.4  223.82  5555.1  223.00  5556.4  223.00
#Mann=5,-1,0
  4705.6    0.05       0  4983.8    0.03       0  4989.8    0.05       0
  5401.6     0.1       0  5555.1    0.05       0
Bank Sta=4983.8,4989.8
Exp/Cntr=0.3,0.1

Type RM Length L Ch R = 1,864,348,348,348
BEGIN DESCRIPTION:
UNT037 IN NURI 2.0
END DESCRIPTION:
XS GIS Cut Line= 4
      2307121.67     13309252.21      2306968.89     13309439.72
      2307017.50     13309783.47      2307177.21     13310078.58
#Sta/Elev= 30
  4594.7  205.38  4636.7  204.35  4643.2  205.10  4665.2  203.12  4707.1  201.87
  4715.0  200.79  4735.8  201.63  4742.6  199.96  4833.5  197.43  4853.9  198.46
  4875.6  197.99  4904.4  196.40  4918.9  194.54  4932.5  192.81  4937.5  193.70
  4954.9  189.75  4965.0  188.37  4992.3  186.81  4995.0  186.31  4998.3  186.81
  5008.6  186.84  5055.9  191.02  5086.2  196.74  5116.5  199.16  5275.8  203.97
  5289.9  204.95  5319.6  205.07  5379.5  207.17  5385.2  208.24  5519.3  211.04
#Mann=5,-1,0
  4594.7    0.05       0  4875.6     0.1       0  4918.9    0.05       0
  4992.3    0.03       0  4998.3    0.05       0
Bank Sta=4992.3,4998.3
Exp/Cntr=0.3,0.1

Type RM Length L Ch R = 1,516,415,415,415
BEGIN DESCRIPTION:
Mapping XS 641206b9
END DESCRIPTION:
XS GIS Cut Line= 4
      2306948.04     13309123.76      2306736.25     13309293.89
      2306642.50     13309620.27      2306639.03     13309898.01
#Sta/Elev= 30
  4563.0  205.47  4579.3  203.92  4636.9  203.49  4715.3  201.29  4729.7  202.35
  4750.5  200.55  4791.3  199.75  4814.5  198.90  4838.8  199.11  4850.4  196.59
  4884.1  195.32  4918.4  192.84  4923.0  191.87  4941.8  190.74  4967.2  187.16
  4990.5  185.00  4992.7  183.42  4995.4  182.92  4998.7  183.42  5035.4  187.01
  5045.8  189.37  5056.2  190.26  5066.7  192.98  5102.0  196.48  5108.3  197.73
  5149.9  200.28  5180.8  201.21  5260.8  202.71  5380.8  202.27  5452.0  202.80
#Mann=7,-1,0
  4563.0    0.05       0  4791.3     0.1       0  4918.4    0.05       0
  4967.2     0.1       0  4992.7    0.07       0  4998.7     0.1       0
  5066.7    0.05       0
Bank Sta=4992.7,4998.7
Exp/Cntr=0.3,0.1

Type RM Length L Ch R = 1,101,0,0,0
BEGIN DESCRIPTION:
UNT037 IN NURI 1.0
END DESCRIPTION:
XS GIS Cut Line= 4
      2306448.07     13309023.03      2306284.86     13309252.22
      2306420.90     13309632.97      2306580.00     13309891.10
#Sta/Elev= 30
  4587.8  201.86  4650.5  202.03  4713.4  202.30  4728.0  201.66  4749.1  200.87
  4763.8  201.98  4776.6  200.28  4805.6  199.67  4820.4  198.52  4841.3  198.65
  4874.3  197.00  4916.6  193.71  4927.4  192.12  4947.5  191.12  4952.8  187.57
  4978.3  182.75  4990.9  179.35  4998.5  178.67  5001.3  178.17  5004.5  178.67
  5014.4  179.44  5020.1  180.78  5033.4  182.75  5039.9  185.25  5059.7  187.58
  5086.5  191.62  5107.7  193.39  5250.1  199.05  5433.0  203.22  5576.7  203.31
#Mann=7,-1,0
  4587.8    0.05       0  4650.5     0.1       0  4728.0    0.05       0
  4998.5    0.03       0  5004.5    0.05       0  5020.1     0.1       0
  5059.7    0.05       0
Bank Sta=4998.5,5004.5
Exp/Cntr=0.3,0.1

Chan Stop Cuts=-1