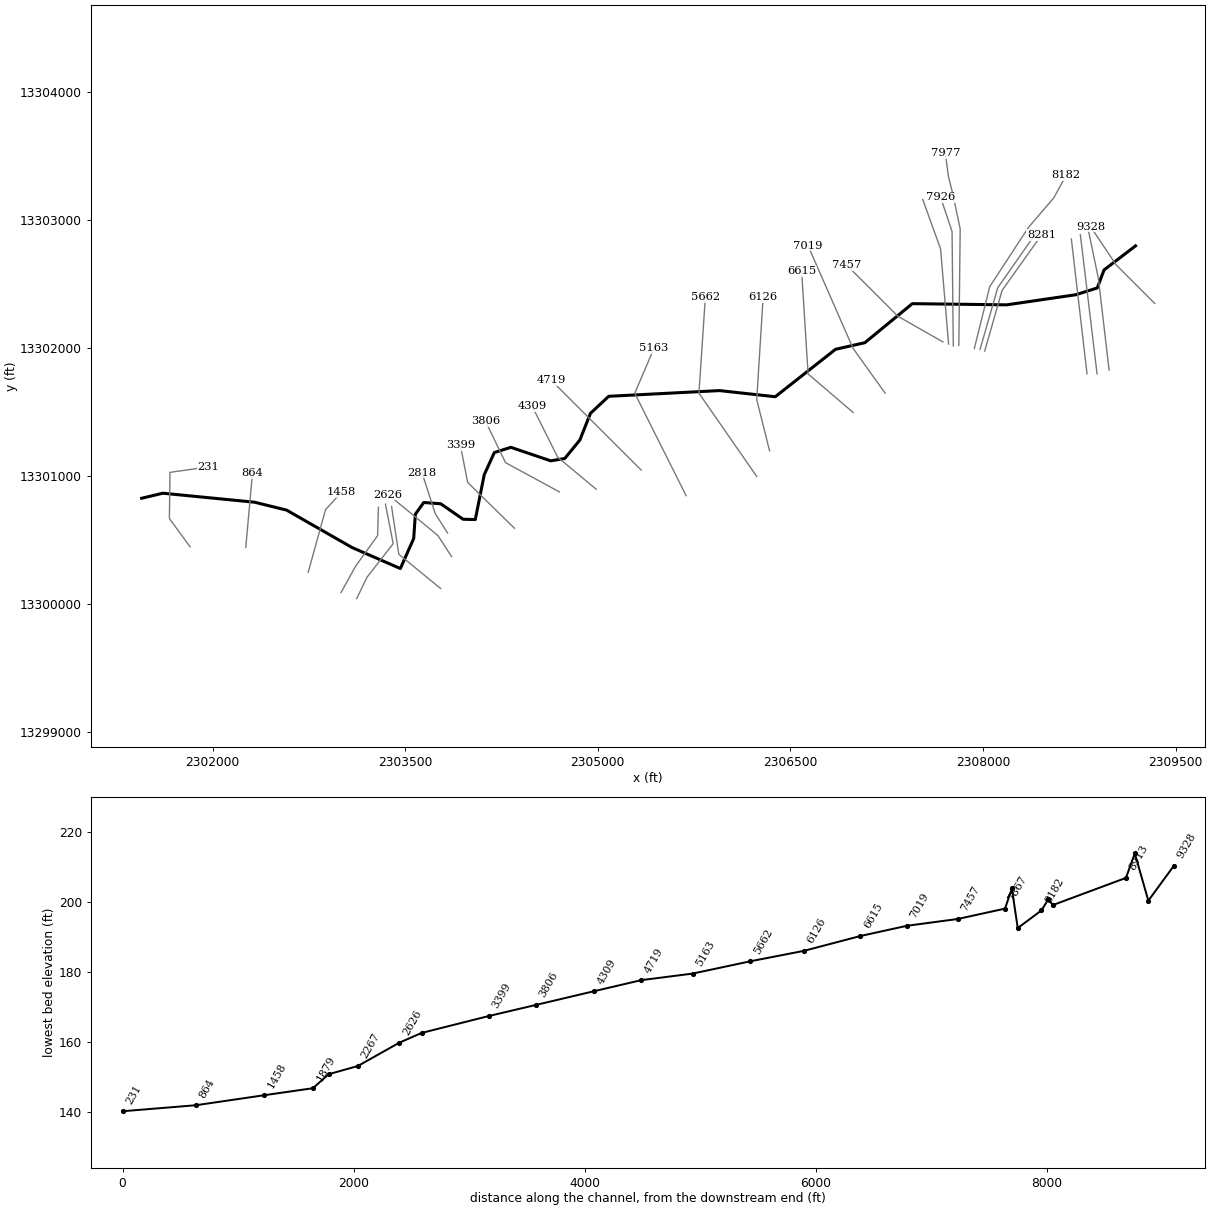
--- UNT038 IN NURI.prj (project) ---

Proj Title=UNT038 IN NURI Base Level Engineering
Current Plan=p01
Default Exp/Contr=0.3,0.1
English Units
Geom File=g01
Flow File=f01
Plan File=p01
BEGIN DESCRIPTION:
UNT038 IN NURI
END DESCRIPTION:

--- UNT038 IN NURI.p01 (plan) ---

Plan Title=Multiple Run
Short Identifier=Multiple
Geom File=g01
Flow File=f01
Subcritical Flow
K Sum by GR= 0
Std Step Tol= 0.01
Critical Tol= 0.01
Num of Std Step Trials= 20
Max Error Tol= 0.3
Flow Tol Ratio= 0.001
Split Flow NTrial= 30
Split Flow Tol= 0.02
Split Flow Ratio= 0.02
Log Output Level= 0
Friction Slope Method= 1
Unsteady Friction Slope Method= 2
Unsteady Bridges Friction Slope Method= 1
Parabolic Critical Depth
Global Vel Dist=  1 , 1 , 1
Global Log Level= 0
CheckData=True
Encroach Param= -1, 0, 0, 0
BEGIN DESCRIPTION:
Multiple Run
END DESCRIPTION:

--- UNT038 IN NURI.f01 (steady flow) ---

Flow Title=Multiple
Number of Profiles=7
Profile Names=10-year,25-year,50-year,1pct_min,100-year,1pct_plu,500-year
River Rch & RM= UNT038 IN NURI,Reach-1,9328
     686     985    1240    1141    1543    2086    2397
River Rch & RM= UNT038 IN NURI,Reach-1,7867
     846    1226    1552    1435    1940    2624    3046
River Rch & RM= UNT038 IN NURI,Reach-1,2013
    1167    1719    2201    2056    2780    3760    4456
Boundary for River Rch & Prof#=UNT038 IN NURI,Reach-1,1
Up Type=0
Dn Type=3
Dn Slope=0.005
Boundary for River Rch & Prof#=UNT038 IN NURI,Reach-1,2
Up Type=0
Dn Type=3
Dn Slope=0.005
Boundary for River Rch & Prof#=UNT038 IN NURI,Reach-1,3
Up Type=0
Dn Type=3
Dn Slope=0.005
Boundary for River Rch & Prof#=UNT038 IN NURI,Reach-1,4
Up Type=0
Dn Type=3
Dn Slope=0.005
Boundary for River Rch & Prof#=UNT038 IN NURI,Reach-1,5
Up Type=0
Dn Type=3
Dn Slope=0.005
Boundary for River Rch & Prof#=UNT038 IN NURI,Reach-1,6
Up Type=0
Dn Type=3
Dn Slope=0.005
Boundary for River Rch & Prof#=UNT038 IN NURI,Reach-1,7
Up Type=0
Dn Type=3
Dn Slope=0.005

--- UNT038 IN NURI.g01 (geometry) ---

Geom Title=Existing Conditions

River Reach=UNT038 IN NURI,Reach-1
Reach XY= 30
      2309187.99     13302796.40      2308942.48     13302608.29
      2308890.13     13302468.04      2308722.36     13302414.95
      2308184.67     13302336.16      2307449.39     13302345.39
      2307080.28     13302040.87      2306851.60     13301989.30
      2306381.91     13301618.96      2305947.78     13301666.99
      2305084.83     13301622.40      2304942.72     13301489.52
      2304859.89     13301280.66      2304742.69     13301137.04
      2304633.29     13301118.76      2304323.12     13301224.24
      2304194.19     13301183.52      2304115.37     13301010.13
      2304045.81     13300660.47      2303950.92     13300662.96
      2303776.43     13300783.77      2303644.29     13300793.69
      2303579.01     13300702.32      2303566.12     13300512.69
      2303462.34     13300278.35      2303085.30     13300442.65
      2302576.58     13300734.10      2302327.22     13300795.85
      2301612.36     13300866.12      2301447.72     13300826.85

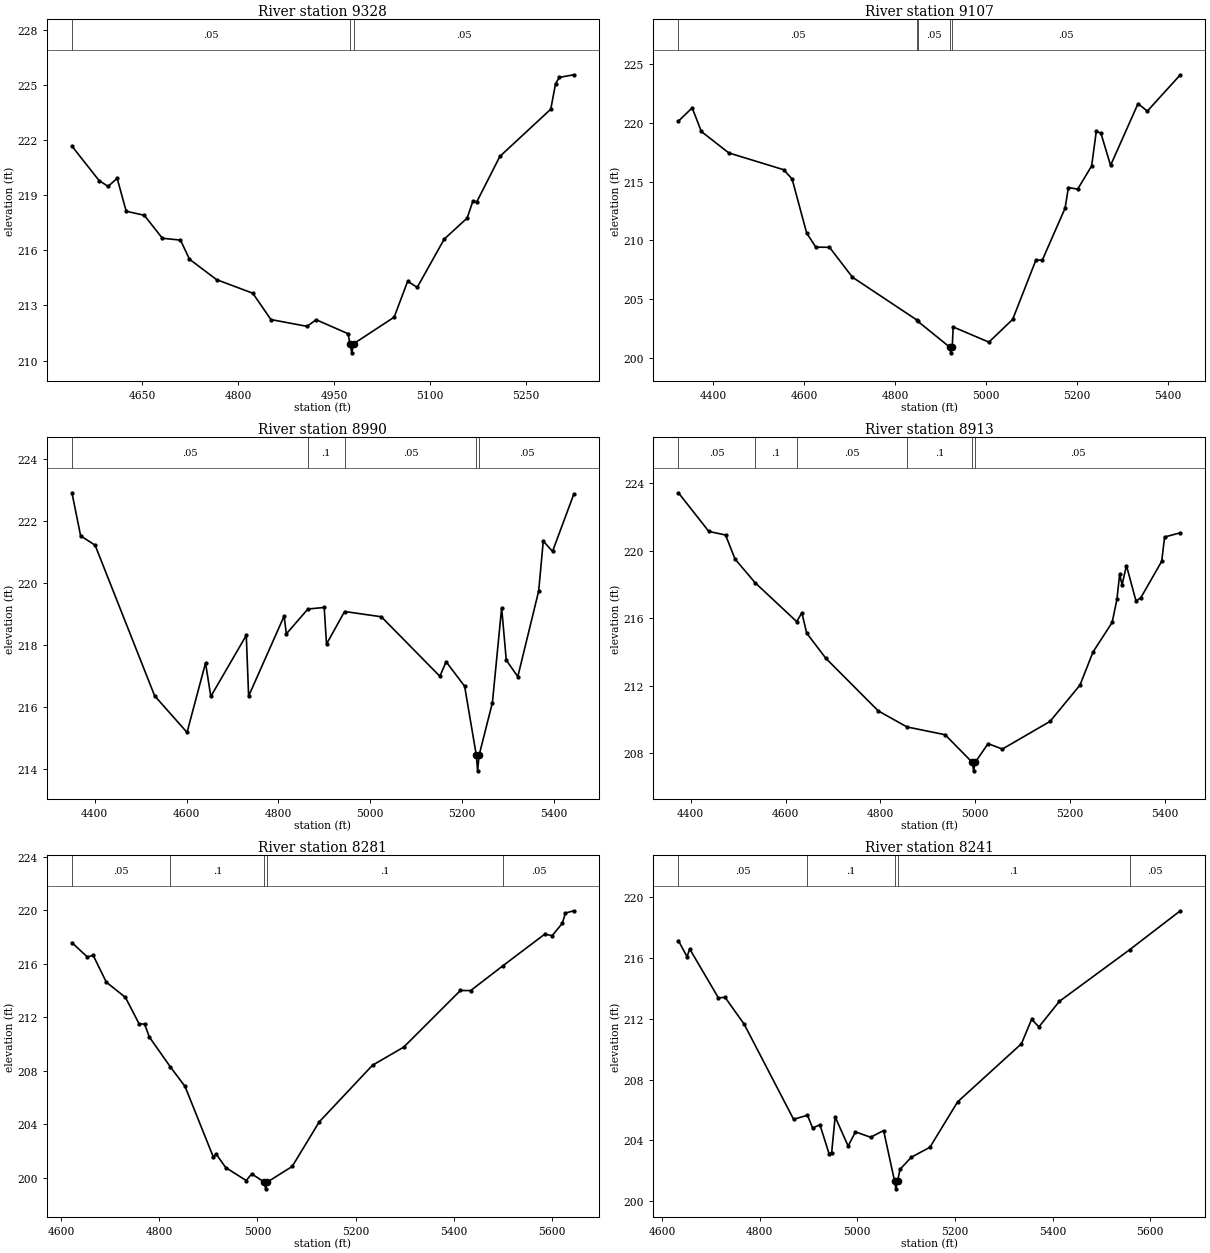
Type RM Length L Ch R = 1,9328,221,221,221
BEGIN DESCRIPTION:
UNT038 IN NURI 20.0
END DESCRIPTION:
XS GIS Cut Line= 3
      2309337.69     13302346.88      2309037.72     13302646.85
      2308837.71     13302946.87
#Sta/Elev= 30
  4540.2  221.66  4582.6  219.79  4596.7  219.47  4610.9  219.91  4625.0  218.12
  4653.3  217.90  4681.6  216.65  4709.9  216.55  4724.0  215.51  4766.4  214.40
  4823.0  213.66  4851.3  212.23  4907.9  211.86  4922.0  212.22  4971.9  211.46
  4974.9  210.92  4977.7  210.42  4980.9  210.92  5044.0  212.36  5065.1  214.31
  5080.1  213.98  5122.2  216.60  5158.2  217.75  5167.2  218.68  5173.2  218.63
  5209.3  221.10  5288.9  223.67  5296.4  225.06  5302.4  225.40  5325.0  225.54
#Mann=3,-1,0
  4540.2    0.05       0  4974.9    0.03       0  4980.9    0.05       0
Bank Sta=4974.9,4980.9
Exp/Cntr=0.3,0.1

Type RM Length L Ch R = 1,9107,117,117,117
BEGIN DESCRIPTION:
Mapping XS 401f8709
END DESCRIPTION:
XS GIS Cut Line= 3
      2308982.02     13301826.77      2308898.69     13302542.91
      2308820.57     13302917.88
#Sta/Elev= 30
  4323.4  220.13  4353.7  221.26  4373.8  219.25  4434.2  217.43  4555.0  216.00
  4573.5  215.21  4605.4  210.63  4625.5  209.42  4655.7  209.41  4706.1  206.87
  4848.7  203.21  4850.3  203.11  4919.7  200.94  4922.5  200.44  4925.7  200.94
  4927.8  202.64  5006.3  201.35  5058.6  203.28  5109.7  208.32  5123.8  208.32
  5173.9  212.73  5181.2  214.49  5201.6  214.35  5232.3  216.32  5242.5  219.25
  5252.7  219.11  5274.0  216.37  5334.4  221.62  5354.8  220.98  5427.4  224.07
#Mann=5,-1,0
  4323.4    0.05       0  4848.7     0.1       0  4850.3    0.05       0
  4919.7    0.03       0  4925.7    0.05       0
Bank Sta=4919.7,4925.7
Exp/Cntr=0.3,0.1

Type RM Length L Ch R = 1,8990,77,77,77
BEGIN DESCRIPTION:
UNT038 IN NURI 19.0
END DESCRIPTION:
XS GIS Cut Line= 2
      2308888.27     13301798.10      2308758.20     13302882.93
#Sta/Elev= 30
  4350.5  222.91  4369.4  221.52  4400.9  221.22  4530.5  216.36  4601.0  215.18
  4641.3  217.42  4652.8  216.34  4730.0  218.31  4735.1  216.35  4812.3  218.93
  4817.3  218.36  4864.2  219.16  4899.6  219.21  4904.7  218.03  4944.0  219.08
  5024.0  218.91  5151.5  216.99  5165.0  217.46  5205.3  216.67  5230.8  214.44
  5233.6  213.94  5236.8  214.44  5265.8  216.14  5285.9  219.20  5296.0  217.51
  5321.1  216.98  5366.5  219.74  5376.5  221.35  5396.7  221.02  5443.1  222.87
#Mann=5,-1,0
  4350.5    0.05       0  4864.2     0.1       0  4944.0    0.05       0
  5230.8    0.03       0  5236.8    0.05       0
Bank Sta=5230.8,5236.8
Exp/Cntr=0.3,0.1

Type RM Length L Ch R = 1,8913,632,632,632
BEGIN DESCRIPTION:
Mapping XS 9ca7ba31
END DESCRIPTION:
XS GIS Cut Line= 2
      2308810.14     13301798.16      2308688.05     13302849.69
#Sta/Elev= 30
  4374.1  223.42  4438.3  221.13  4473.5  220.92  4493.6  219.49  4536.0  218.09
  4623.5  215.79  4634.5  216.31  4644.6  215.11  4684.9  213.62  4795.6  210.50
  4856.2  209.55  4936.5  209.09  4994.0  207.45  4996.7  206.95  5000.0  207.45
  5027.2  208.56  5057.4  208.24  5158.0  209.88  5221.1  212.03  5248.6  213.99
  5288.9  215.74  5299.0  217.11  5304.7  218.59  5309.8  217.97  5319.1  219.11
  5339.2  217.01  5349.3  217.20  5393.4  219.36  5399.6  220.80  5432.7  221.05
#Mann=6,-1,0
  4374.1    0.05       0  4536.0     0.1       0  4623.5    0.05       0
  4856.2     0.1       0  4994.0    0.03       0  5000.0    0.05       0
Bank Sta=4994,5000
Exp/Cntr=0.3,0.1

Type RM Length L Ch R = 1,8281,40,40,40
BEGIN DESCRIPTION:
Mapping XS aa5398c6
END DESCRIPTION:
XS GIS Cut Line= 3
      2308013.26     13301975.18      2308148.69     13302449.16
      2308455.96     13302881.43
#Sta/Elev= 30
  4621.7  217.57  4652.8  216.51  4665.0  216.62  4691.8  214.62  4730.8  213.48
  4758.6  211.51  4769.8  211.49  4779.4  210.53  4822.6  208.28  4852.2  206.84
  4910.2  201.54  4915.4  201.80  4935.4  200.77  4977.0  199.81  4988.2  200.31
  5013.8  199.69  5016.5  199.19  5019.8  199.69  5070.7  200.86  5125.9  204.19
  5234.5  208.42  5298.1  209.77  5413.7  214.00  5434.6  213.99  5500.5  215.85
  5585.9  218.21  5600.7  218.09  5621.6  219.02  5627.7  219.78  5645.0  219.95
#Mann=5,-1,0
  4621.7    0.05       0  4822.6     0.1       0  5013.8    0.07       0
  5019.8     0.1       0  5500.5    0.05       0
Bank Sta=5013.8,5019.8
Exp/Cntr=0.3,0.1

Type RM Length L Ch R = 1,8241,59,59,59
BEGIN DESCRIPTION:
UNT038 IN NURI 18.0
END DESCRIPTION:
XS GIS Cut Line= 3
      2307976.81     13301988.21      2308114.83     13302469.99
      2308416.78     13302902.09
#Sta/Elev= 30
  4633.5  217.15  4651.3  216.09  4656.5  216.61  4715.3  213.39  4729.2  213.41
  4768.2  211.65  4869.5  205.38  4897.9  205.65  4908.4  204.81  4923.4  205.02
  4942.2  203.11  4947.4  203.16  4954.6  205.54  4981.2  203.62  4996.2  204.55
  5027.4  204.20  5053.9  204.64  5076.4  201.30  5079.1  200.80  5082.4  201.30
  5087.6  202.09  5110.6  202.88  5148.8  203.54  5205.5  206.53  5336.3  210.36
  5357.2  211.97  5372.1  211.47  5413.9  213.15  5558.2  216.56  5661.8  219.12
#Mann=5,-1,0
  4633.5    0.05       0  4897.9     0.1       0  5076.4    0.07       0
  5082.4     0.1       0  5558.2    0.05       0
Bank Sta=5076.4,5082.4
Exp/Cntr=0.3,0.1

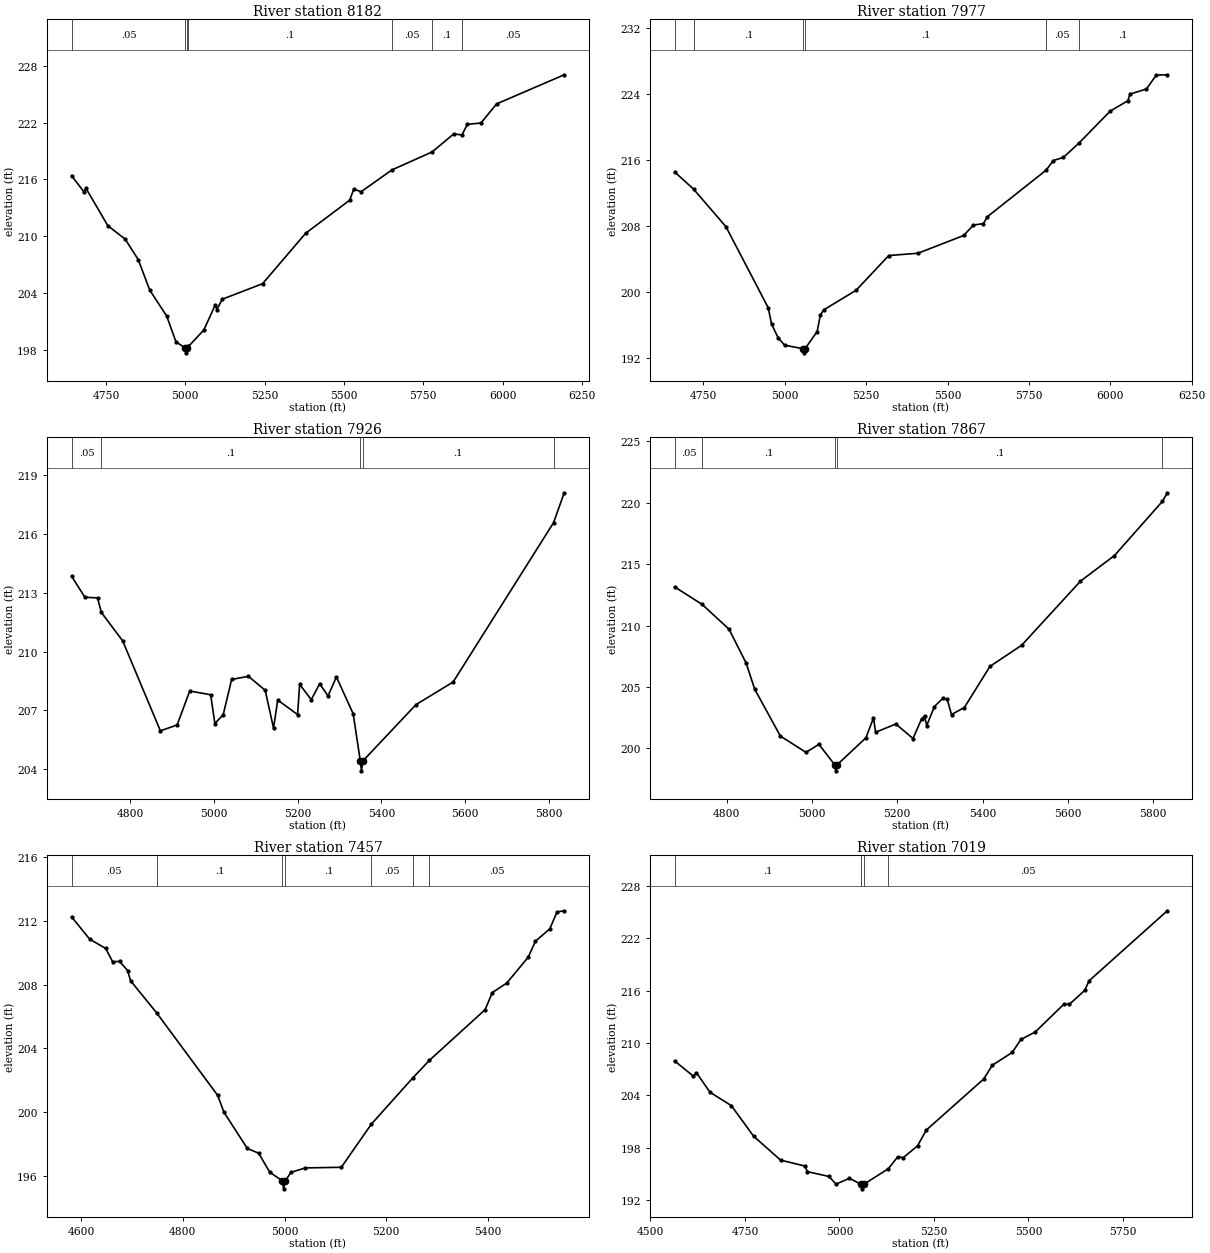
Type RM Length L Ch R = 1,8182,205,205,205
BEGIN DESCRIPTION:
Mapping XS 2d863de8
END DESCRIPTION:
XS GIS Cut Line= 5
      2307932.54     13301996.03      2308052.33     13302477.81
      2308354.42     13302941.35      2308550.42     13303169.74
      2308647.63     13303346.81
#Sta/Elev= 30
  4641.7  216.38  4681.3  214.65  4686.4  215.09  4755.9  211.10  4810.4  209.69
  4851.7  207.52  4887.9  204.30  4941.4  201.55  4970.6  198.83  5000.2  198.16
  5003.0  197.66  5006.2  198.16  5010.1  198.34  5058.4  200.07  5094.6  202.73
  5099.7  202.24  5116.6  203.33  5243.6  204.97  5379.3  210.30  5518.2  213.80
  5530.9  214.96  5554.5  214.70  5651.3  217.00  5777.9  218.90  5846.3  220.81
  5872.1  220.70  5889.1  221.82  5931.9  221.96  5981.3  223.98  6194.4  227.06
#Mann=7,-1,0
  4641.7    0.05       0  5000.2    0.03       0  5006.2    0.05       0
  5010.1     0.1       0  5651.3    0.05       0  5777.9     0.1       0
  5872.1    0.05       0
Bank Sta=5000.2,5006.2
Exp/Cntr=0.3,0.1

Type RM Length L Ch R = 1,7977,51,51,51
BEGIN DESCRIPTION:
Mapping XS 9168c1b3
END DESCRIPTION:
XS GIS Cut Line= 5
      2307811.88     13302019.43      2307822.30     13302929.19
      2307763.27     13303206.97      2307730.97     13303336.41
      2307706.67     13303520.40
#Sta/Elev= 30
  4662.1  214.56  4720.0  212.49  4819.5  207.93  4949.5  198.09  4959.5  196.13
  4979.5  194.48  4999.5  193.56  5056.5  193.13  5059.3  192.63  5062.5  193.13
  5099.6  195.21  5109.6  197.23  5119.6  197.83  5219.6  200.23  5319.6  204.43
  5409.6  204.71  5549.6  206.86  5579.8  208.13  5610.4  208.30  5621.9  209.12
  5802.4  214.77  5825.1  215.95  5855.9  216.33  5903.0  218.04  5999.8  221.95
  6053.8  223.20  6060.4  224.01  6110.8  224.62  6141.1  226.31  6174.9  226.35
#Mann=6,-1,0
  4662.1    0.05       0  4720.0     0.1       0  5056.5    0.07       0
  5062.5     0.1       0  5802.4    0.05       0  5903.0     0.1       0
Bank Sta=5056.5,5062.5
Exp/Cntr=0.3,0.1

Type RM Length L Ch R = 1,7926,59,59,59
BEGIN DESCRIPTION:
UNT038 IN NURI 17.0
END DESCRIPTION:
XS GIS Cut Line= 3
      2307768.48     13302015.09      2307758.98     13302908.35
      2307669.50     13303175.77
#Sta/Elev= 30
  4660.7  213.84  4692.5  212.77  4722.5  212.74  4731.6  212.00  4782.5  210.55
  4872.5  205.96  4912.5  206.26  4942.5  207.99  4992.5  207.80  5002.5  206.33
  5022.5  206.79  5042.5  208.58  5082.5  208.74  5122.5  208.03  5142.5  206.10
  5152.5  207.53  5199.8  206.79  5204.8  208.33  5232.5  207.55  5252.5  208.36
  5272.5  207.74  5292.5  208.71  5332.5  206.83  5349.5  204.42  5352.3  203.92
  5355.5  204.42  5482.5  207.30  5571.0  208.45  5810.7  216.58  5836.0  218.10
#Mann=5,-1,0
  4660.7    0.05       0  4731.6     0.1       0  5349.5    0.07       0
  5355.5     0.1       0  5810.7    0.05       0
Bank Sta=5349.5,5355.5
Exp/Cntr=0.3,0.1

Type RM Length L Ch R = 1,7867,410,410,410
BEGIN DESCRIPTION:
Mapping XS 3d1737f2
END DESCRIPTION:
XS GIS Cut Line= 3
      2307732.02     13302029.84      2307669.52     13302772.94
      2307530.63     13303158.36
#Sta/Elev= 30
  4677.8  213.14  4742.2  211.72  4805.3  209.70  4845.4  206.95  4865.5  204.82
  4925.7  201.01  4985.9  199.68  5016.0  200.34  5053.1  198.68  5055.9  198.18
  5059.1  198.68  5126.4  200.87  5144.1  202.48  5149.1  201.32  5196.6  201.99
  5236.8  200.81  5256.8  202.39  5263.9  202.65  5269.0  201.86  5287.0  203.41
  5307.0  204.09  5317.1  203.99  5327.1  202.76  5357.2  203.33  5417.4  206.68
  5491.5  208.39  5629.6  213.61  5709.2  215.69  5821.7  220.10  5833.2  220.80
#Mann=5,-1,0
  4677.8    0.05       0  4742.2     0.1       0  5053.1    0.07       0
  5059.1     0.1       0  5821.7    0.05       0
Bank Sta=5053.1,5059.1
Exp/Cntr=0.3,0.1

Type RM Length L Ch R = 1,7457,438,438,438
BEGIN DESCRIPTION:
UNT038 IN NURI 16.0
END DESCRIPTION:
XS GIS Cut Line= 3
      2307687.75     13302046.84      2307337.72     13302246.85
      2306937.74     13302646.83
#Sta/Elev= 30
  4581.3  212.24  4616.6  210.85  4648.3  210.26  4662.0  209.43  4675.6  209.45
  4691.5  208.88  4697.2  208.24  4748.5  206.23  4868.6  201.06  4880.8  200.01
  4926.9  197.74  4949.2  197.44  4970.8  196.26  4995.6  195.71  4998.3  195.21
  5001.6  195.71  5012.7  196.24  5041.0  196.52  5111.7  196.56  5170.8  199.26
  5252.1  202.15  5284.8  203.25  5394.6  206.43  5408.7  207.50  5437.0  208.09
  5479.4  209.72  5493.6  210.72  5521.8  211.49  5536.0  212.55  5550.1  212.62
#Mann=7,-1,0
  4581.3    0.05       0  4748.5     0.1       0  4995.6    0.07       0
  5001.6     0.1       0  5170.8    0.05       0  5252.1     0.1       0
  5284.8    0.05       0
Bank Sta=4995.6,5001.6
Exp/Cntr=0.3,0.1

Type RM Length L Ch R = 1,7019,404,404,404
BEGIN DESCRIPTION:
UNT038 IN NURI 15.0
END DESCRIPTION:
XS GIS Cut Line= 3
      2307237.70     13301646.88      2306987.72     13301996.85
      2306637.72     13302796.86
#Sta/Elev= 30
  4564.0  207.93  4613.1  206.21  4621.7  206.59  4657.4  204.35  4713.9  202.82
  4772.9  199.31  4844.2  196.57  4908.1  195.90  4915.4  195.25  4972.0  194.70
  4991.0  193.82  5026.4  194.49  5057.7  193.78  5060.5  193.28  5063.7  193.78
  5129.7  195.60  5154.3  196.96  5168.7  196.85  5206.5  198.21  5229.9  200.02
  5381.2  205.85  5404.6  207.45  5456.8  208.91  5480.2  210.40  5518.0  211.26
  5594.4  214.47  5608.1  214.42  5649.0  216.03  5660.3  217.12  5867.3  225.15
#Mann=4,-1,0
  4564.0     0.1       0  5057.7    0.07       0  5063.7     0.1       0
  5129.7    0.05       0
Bank Sta=5057.7,5063.7
Exp/Cntr=0.3,0.1

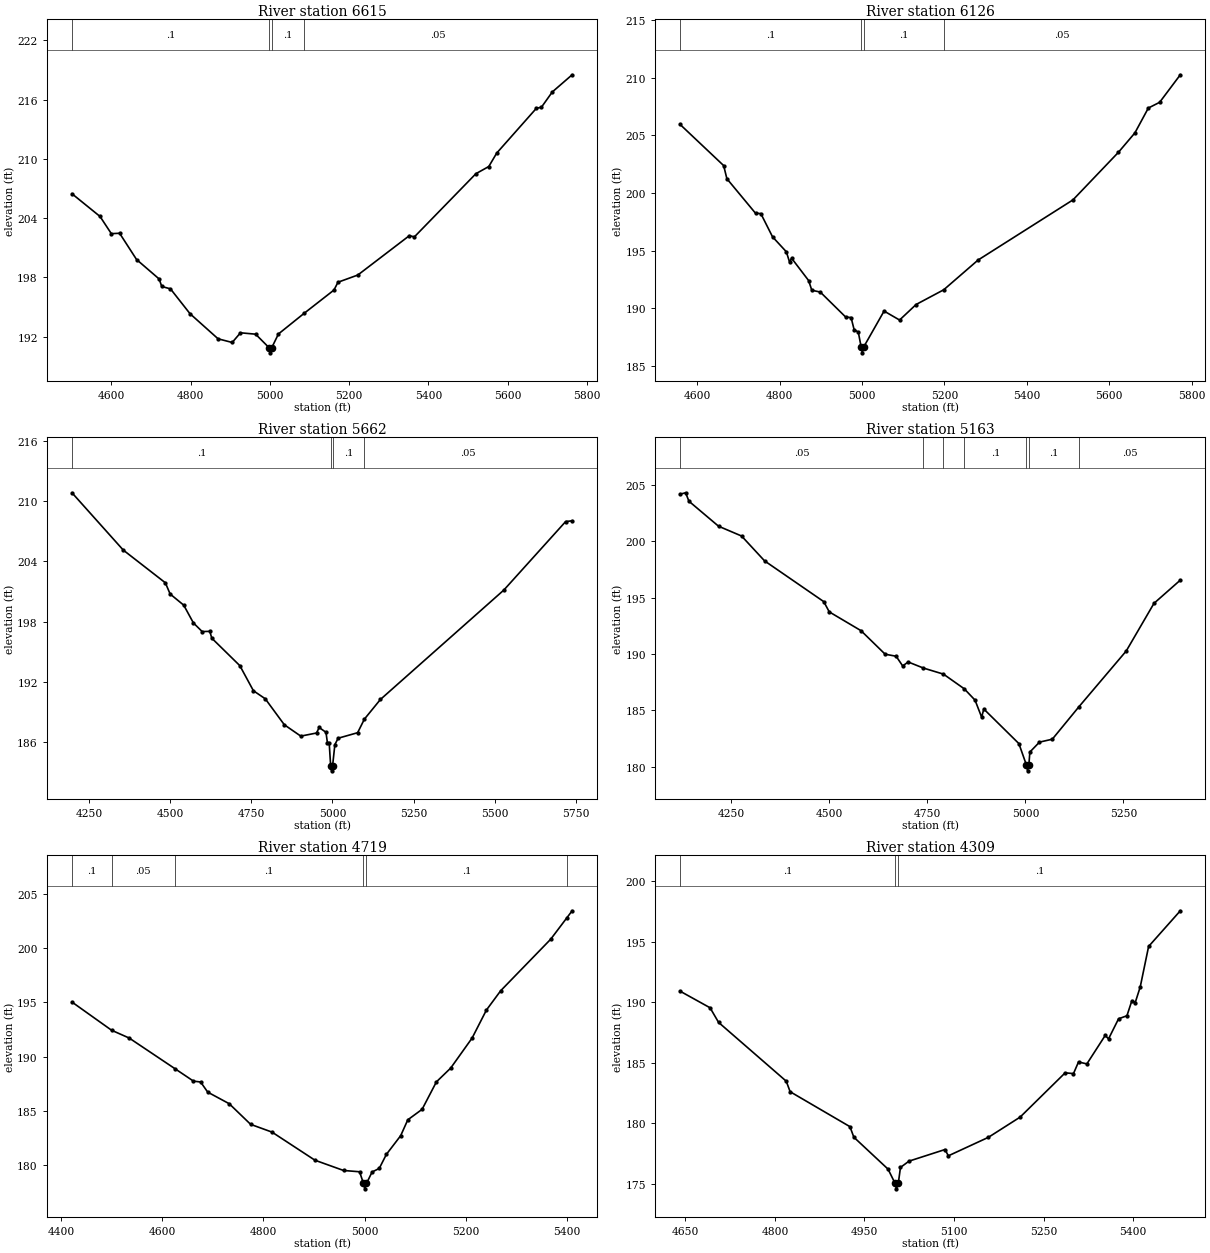
Type RM Length L Ch R = 1,6615,489,489,489
BEGIN DESCRIPTION:
UNT038 IN NURI 14.0
END DESCRIPTION:
XS GIS Cut Line= 3
      2306987.70     13301496.87      2306637.72     13301796.85
      2306587.72     13302596.85
#Sta/Elev= 30
  4500.4  206.46  4571.2  204.16  4599.7  202.42  4620.6  202.46  4663.4  199.80
  4720.4  197.83  4727.0  197.07  4749.0  196.83  4798.4  194.31  4869.2  191.77
  4904.8  191.40  4925.7  192.38  4963.9  192.24  4998.4  190.85  5001.2  190.35
  5004.4  190.85  5021.5  192.26  5086.0  194.34  5161.7  196.71  5171.8  197.50
  5221.9  198.23  5352.1  202.22  5364.6  202.09  5519.9  208.49  5552.5  209.22
  5572.5  210.58  5672.7  215.12  5685.3  215.22  5712.8  216.77  5762.9  218.51
#Mann=4,-1,0
  4500.4     0.1       0  4998.4    0.07       0  5004.4     0.1       0
  5086.0    0.05       0
Bank Sta=4998.4,5004.4
Exp/Cntr=0.3,0.1

Type RM Length L Ch R = 1,6126,464,464,464
BEGIN DESCRIPTION:
UNT038 IN NURI 13.0
END DESCRIPTION:
XS GIS Cut Line= 3
      2306337.71     13301196.88      2306237.72     13301596.85
      2306287.72     13302396.81
#Sta/Elev= 30
  4558.8  205.95  4664.4  202.38  4672.2  201.24  4741.7  198.24  4754.6  198.21
  4783.0  196.19  4816.5  194.89  4824.2  194.01  4829.3  194.33  4870.6  192.39
  4878.3  191.55  4898.9  191.39  4960.8  189.21  4973.6  189.18  4981.1  188.11
  4991.1  187.92  4998.1  186.61  5000.9  186.11  5004.1  186.61  5053.7  189.74
  5091.3  188.96  5131.4  190.31  5198.5  191.59  5281.7  194.17  5512.1  199.40
  5622.3  203.53  5662.4  205.22  5695.0  207.38  5722.5  207.88  5772.6  210.27
#Mann=4,-1,0
  4558.8     0.1       0  4998.1    0.07       0  5004.1     0.1       0
  5198.5    0.05       0
Bank Sta=4998.1,5004.1
Exp/Cntr=0.3,0.1

Type RM Length L Ch R = 1,5662,499,499,499
BEGIN DESCRIPTION:
UNT038 IN NURI 12.0
END DESCRIPTION:
XS GIS Cut Line= 3
      2306237.74     13300996.83      2305787.72     13301646.85
      2305837.72     13302396.89
#Sta/Elev= 30
  4196.8  210.84  4354.9  205.13  4484.7  201.87  4499.5  200.75  4541.4  199.64
  4571.2  197.87  4598.2  197.01  4621.8  197.03  4627.9  196.35  4714.4  193.61
  4756.3  191.11  4792.8  190.31  4851.6  187.72  4902.3  186.59  4950.9  186.90
  4959.0  187.45  4980.0  186.97  4984.4  185.94  4989.9  185.94  4994.4  183.63
  4997.2  183.13  5000.4  183.63  5007.4  185.74  5017.5  186.38  5077.6  186.93
  5098.4  188.28  5147.8  190.24  5528.6  201.15  5719.0  207.97  5739.1  208.05
#Mann=4,-1,0
  4196.8     0.1       0  4994.4    0.07       0  5000.4     0.1       0
  5098.4    0.05       0
Bank Sta=4994.4,5000.4
Exp/Cntr=0.3,0.1

Type RM Length L Ch R = 1,5163,444,444,444
BEGIN DESCRIPTION:
UNT038 IN NURI 11.0
END DESCRIPTION:
XS GIS Cut Line= 3
      2305687.74     13300846.82      2305287.72     13301646.85
      2305437.74     13301996.89
#Sta/Elev= 30
  4119.6  204.20  4133.6  204.32  4142.0  203.57  4217.5  201.35  4276.2  200.48
  4334.9  198.27  4485.8  194.65  4499.8  193.74  4580.8  192.07  4642.3  189.98
  4670.3  189.80  4687.0  188.94  4701.0  189.29  4739.9  188.75  4791.0  188.21
  4843.9  186.91  4871.5  185.90  4888.3  184.39  4893.9  185.11  4983.3  182.04
  5002.7  180.12  5005.4  179.62  5008.7  180.12  5011.3  181.29  5035.8  182.17
  5068.5  182.43  5136.1  185.30  5257.1  190.27  5327.8  194.50  5394.9  196.56
#Mann=7,-1,0
  4119.6    0.05       0  4739.9     0.1       0  4791.0    0.05       0
  4843.9     0.1       0  5002.7    0.07       0  5008.7     0.1       0
  5136.1    0.05       0
Bank Sta=5002.7,5008.7
Exp/Cntr=0.3,0.1

Type RM Length L Ch R = 1,4719,410,410,410
BEGIN DESCRIPTION:
UNT038 IN NURI 10.0
END DESCRIPTION:
XS GIS Cut Line= 3
      2305337.76     13301046.82      2304937.72     13301446.85
      2304637.72     13301746.86
#Sta/Elev= 30
  4421.0  195.04  4499.4  192.43  4534.2  191.71  4625.2  188.86  4661.5  187.72
  4675.6  187.64  4689.7  186.70  4732.2  185.63  4774.6  183.72  4817.0  183.00
  4901.9  180.40  4958.5  179.45  4990.3  179.33  4997.9  178.25  5000.6  177.75
  5003.9  178.25  5015.0  179.31  5029.2  179.64  5043.3  180.94  5071.6  182.67
  5085.7  184.14  5114.0  185.11  5142.3  187.65  5170.6  188.93  5213.0  191.71
  5241.3  194.30  5269.6  196.09  5368.6  200.86  5400.4  202.83  5411.0  203.49
#Mann=6,-1,0
  4421.0     0.1       0  4499.4    0.05       0  4625.2     0.1       0
  4997.9    0.07       0  5003.9     0.1       0  5400.4    0.05       0
Bank Sta=4997.9,5003.9
Exp/Cntr=0.3,0.1

Type RM Length L Ch R = 1,4309,503,503,503
BEGIN DESCRIPTION:
UNT038 IN NURI 9.0
END DESCRIPTION:
XS GIS Cut Line= 3
      2304987.70     13300896.87      2304687.72     13301146.85
      2304487.72     13301546.85
#Sta/Elev= 30
  4641.3  190.92  4691.4  189.55  4705.7  188.34  4819.0  183.48  4825.5  182.61
  4925.7  179.72  4932.2  178.85  4989.5  176.21  5000.8  175.08  5003.6  174.58
  5006.8  175.08  5010.3  176.35  5024.6  176.87  5084.9  177.83  5090.5  177.31
  5157.6  178.84  5210.7  180.51  5286.1  184.17  5300.1  184.11  5308.5  185.07
  5322.5  184.91  5353.2  187.26  5358.8  186.98  5375.6  188.64  5389.6  188.89
  5397.9  190.14  5403.5  189.98  5411.9  191.28  5425.9  194.62  5479.0  197.57
#Mann=3,-1,0
  4641.3     0.1       0  5000.8    0.07       0  5006.8     0.1       0
Bank Sta=5000.8,5006.8
Exp/Cntr=0.3,0.1

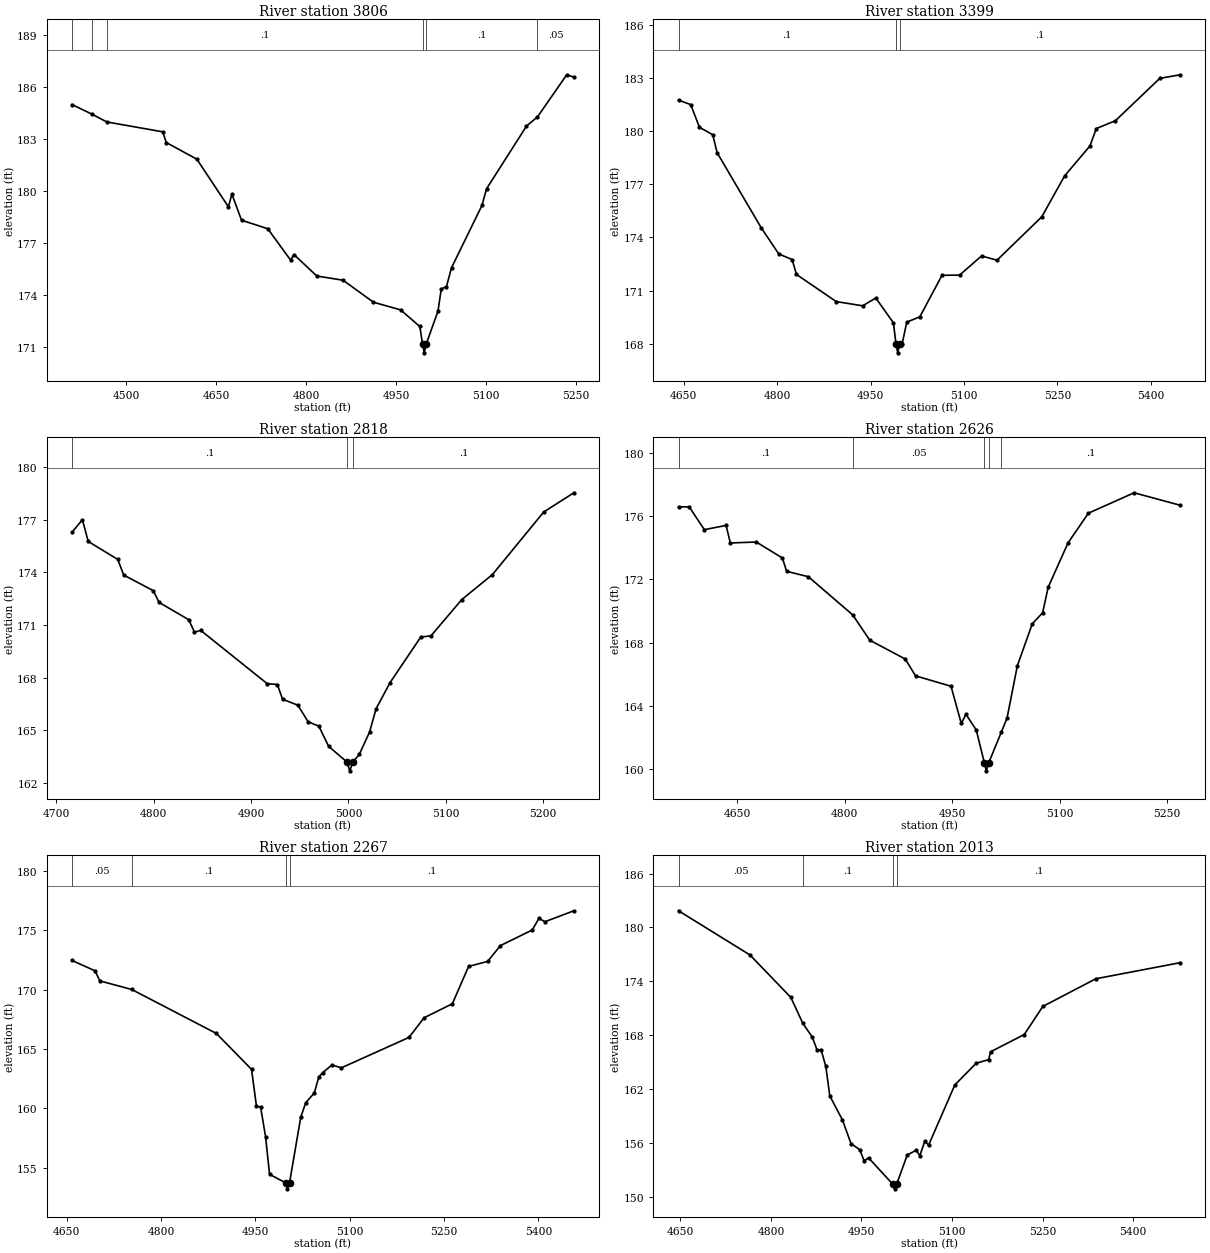
Type RM Length L Ch R = 1,3806,407,407,407
BEGIN DESCRIPTION:
UNT038 IN NURI 8.0
END DESCRIPTION:
XS GIS Cut Line= 3
      2304700.31     13300876.69      2304281.50     13301104.54
      2304125.25     13301427.89
#Sta/Elev= 30
  4410.3  184.98  4443.3  184.43  4468.1  183.98  4561.2  183.41  4567.3  182.79
  4618.2  181.83  4670.8  179.08  4676.5  179.82  4692.6  178.31  4736.3  177.82
  4774.3  176.01  4780.0  176.33  4818.0  175.09  4861.7  174.85  4912.3  173.58
  4957.5  173.14  4989.6  172.18  4994.2  171.16  4996.9  170.66  5000.2  171.16
  5019.8  173.06  5025.3  174.34  5034.0  174.48  5042.4  175.57  5093.1  179.16
  5100.7  180.12  5167.3  183.74  5185.6  184.27  5234.3  186.70  5246.2  186.57
#Mann=6,-1,0
  4410.3     0.1       0  4443.3    0.05       0  4468.1     0.1       0
  4994.2    0.07       0  5000.2     0.1       0  5185.6    0.05       0
Bank Sta=4994.2,5000.2
Exp/Cntr=0.3,0.1

Type RM Length L Ch R = 1,3399,581,581,581
BEGIN DESCRIPTION:
UNT038 IN NURI 7.0
END DESCRIPTION:
XS GIS Cut Line= 3
      2304350.92     13300592.42      2303986.36     13300950.46
      2303929.93     13301239.12
#Sta/Elev= 30
  4642.0  181.74  4661.5  181.49  4675.6  180.21  4696.9  179.79  4703.9  178.78
  4774.6  174.55  4802.9  173.07  4824.2  172.76  4831.2  171.92  4894.9  170.39
  4937.4  170.15  4958.5  170.59  4986.8  169.19  4990.9  168.00  4993.7  167.50
  4996.9  168.00  5000.9  168.01  5008.1  169.23  5029.2  169.53  5064.7  171.87
  5092.9  171.88  5128.2  172.96  5153.0  172.72  5224.9  175.17  5261.4  177.47
  5302.1  179.16  5312.3  180.14  5342.9  180.58  5414.2  182.97  5447.1  183.17
#Mann=3,-1,0
  4642.0     0.1       0  4990.9    0.07       0  4996.9     0.1       0
Bank Sta=4990.9,4996.9
Exp/Cntr=0.3,0.1

Type RM Length L Ch R = 1,2818,192,192,192
BEGIN DESCRIPTION:
UNT038 IN NURI 6.0
END DESCRIPTION:
XS GIS Cut Line= 3
      2303830.10     13300555.50      2303734.62     13300705.24
      2303630.47     13301026.38
#Sta/Elev= 30
  4716.3  176.30  4726.9  177.01  4732.9  175.77  4763.3  174.74  4769.3  173.85
  4799.7  172.96  4805.6  172.29  4836.1  171.30  4842.0  170.59  4848.4  170.69
  4916.6  167.65  4927.1  167.60  4932.4  166.76  4948.1  166.42  4958.7  165.47
  4969.7  165.22  4979.7  164.07  4998.6  163.17  5001.4  162.67  5004.6  163.17
  5011.2  163.61  5021.7  164.88  5028.4  166.21  5042.8  167.71  5074.3  170.31
  5084.8  170.38  5116.4  172.45  5147.9  173.88  5200.5  177.45  5231.5  178.55
#Mann=3,-1,0
  4716.3     0.1       0  4998.6    0.07       0  5004.6     0.1       0
Bank Sta=4998.6,5004.6
Exp/Cntr=0.3,0.1

Type RM Length L Ch R = 1,2626,359,359,359
BEGIN DESCRIPTION:
UNT038 IN NURI 5.1
END DESCRIPTION:
XS GIS Cut Line= 3
      2303861.70     13300370.79      2303754.93     13300535.71
      2303366.93     13300856.01
#Sta/Elev= 30
  4568.6  176.57  4583.5  176.57  4604.6  175.13  4634.9  175.40  4640.8  174.29
  4677.1  174.35  4713.4  173.34  4719.3  172.50  4749.6  172.16  4811.4  169.75
  4835.2  168.15  4884.7  166.96  4899.0  165.90  4948.5  165.24  4962.8  162.89
  4969.3  163.47  4983.7  162.48  4995.0  160.40  4997.7  159.90  5001.0  160.40
  5018.6  162.34  5026.7  163.25  5041.0  166.54  5061.8  169.19  5076.2  169.88
  5084.0  171.50  5111.6  174.29  5140.0  176.17  5203.8  177.46  5268.2  176.67
#Mann=5,-1,0
  4568.6     0.1       0  4811.4    0.05       0  4995.0    0.04       0
  5001.0    0.05       0  5018.6     0.1       0
Bank Sta=4995,5001
Exp/Cntr=0.3,0.1

Type RM Length L Ch R = 1,2267,254,254,254
BEGIN DESCRIPTION:
UNT038 IN NURI 5.0
END DESCRIPTION:
XS GIS Cut Line= 3
      2303775.62     13300122.64      2303450.12     13300389.55
      2303393.77     13300762.38
#Sta/Elev= 30
  4658.5  172.45  4694.9  171.58  4702.8  170.73  4753.4  170.01  4888.0  166.31
  4943.9  163.29  4951.8  160.17  4958.3  160.13  4966.2  157.63  4972.6  154.46
  4998.3  153.74  5001.1  153.24  5004.3  153.74  5022.2  159.27  5030.1  160.49
  5043.7  161.30  5050.9  162.66  5057.3  163.02  5071.7  163.66  5086.8  163.42
  5194.4  165.98  5218.3  167.63  5263.3  168.81  5289.1  171.95  5319.4  172.37
  5339.7  173.70  5390.2  175.01  5401.0  175.99  5410.5  175.71  5456.5  176.63
#Mann=4,-1,0
  4658.5    0.05       0  4753.4     0.1       0  4998.3    0.07       0
  5004.3     0.1       0
Bank Sta=4998.3,5004.3
Exp/Cntr=0.3,0.1

Type RM Length L Ch R = 1,2013,134,134,134
BEGIN DESCRIPTION:
Mapping XS f08077f9
END DESCRIPTION:
XS GIS Cut Line= 4
      2303122.13     13300043.54      2303203.37     13300211.75
      2303406.50     13300472.16      2303346.07     13300780.53
#Sta/Elev= 30
  4646.9  181.85  4765.2  176.93  4833.0  172.20  4852.6  169.34  4868.5  167.78
  4876.7  166.29  4883.0  166.39  4890.9  164.51  4897.5  161.23  4918.3  158.57
  4932.7  155.91  4947.2  155.24  4954.3  154.00  4961.7  154.33  5002.1  151.38
  5004.8  150.88  5008.1  151.38  5025.9  154.66  5040.4  155.17  5046.7  154.59
  5054.9  156.18  5061.2  155.75  5104.6  162.45  5139.9  164.86  5160.7  165.28
  5163.8  166.14  5219.7  168.07  5250.3  171.19  5338.3  174.28  5478.2  176.07
#Mann=4,-1,0
  4646.9    0.05       0  4852.6     0.1       0  5002.1    0.07       0
  5008.1     0.1       0
Bank Sta=5002.1,5008.1
Exp/Cntr=0.3,0.1

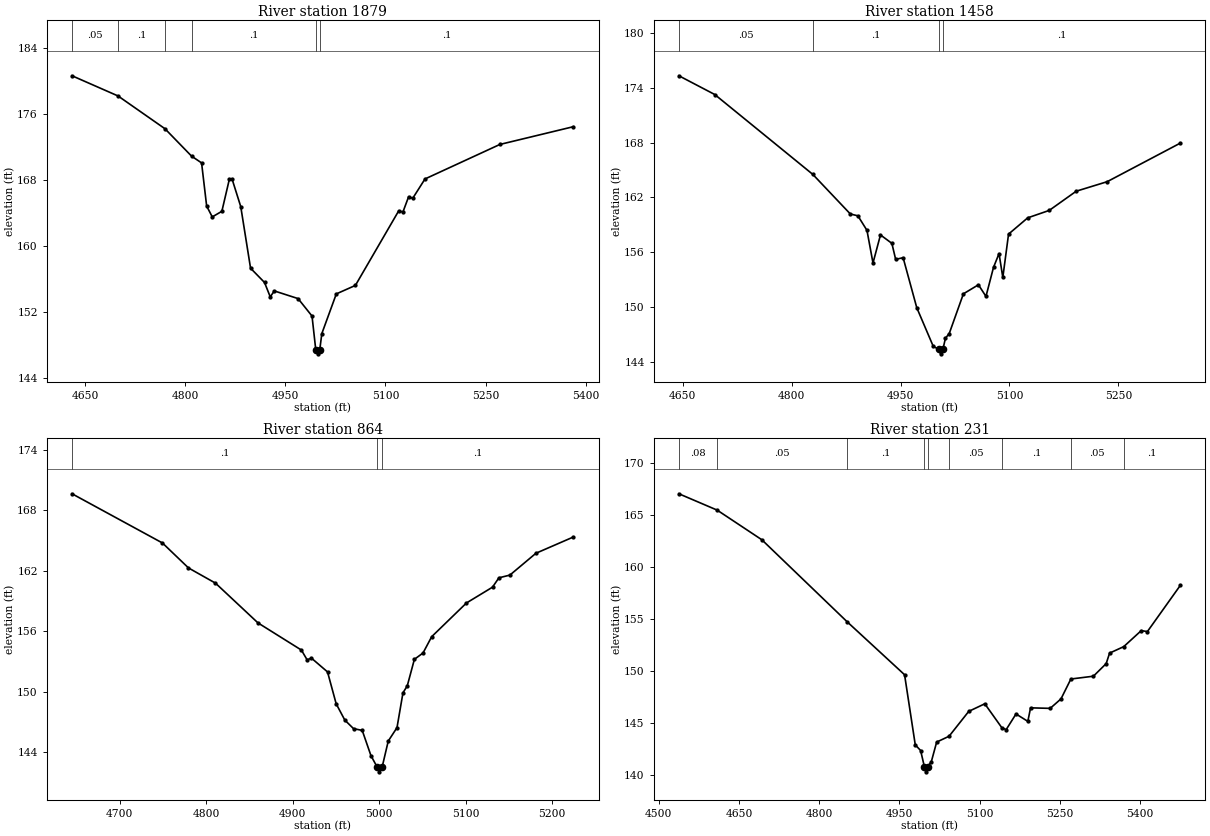
Type RM Length L Ch R = 1,1879,421,421,421
BEGIN DESCRIPTION:
UNT038 IN NURI 4.0
END DESCRIPTION:
XS GIS Cut Line= 4
      2302999.72     13300090.39      2303114.83     13300298.55
      2303284.97     13300534.66      2303291.39     13300757.07
#Sta/Elev= 30
  4630.4  180.67  4699.3  178.22  4769.6  174.24  4809.5  170.91  4824.5  170.09
  4832.1  164.85  4840.5  163.53  4854.9  164.21  4866.1  168.10  4870.3  168.10
  4883.2  164.78  4897.9  157.30  4918.8  155.57  4927.4  153.82  4933.5  154.54
  4969.1  153.61  4990.0  151.49  4995.6  147.40  4998.3  146.90  5001.6  147.40
  5004.7  149.36  5026.4  154.18  5055.0  155.21  5120.0  164.28  5126.2  164.12
  5134.8  165.99  5140.9  165.79  5159.3  168.14  5271.5  172.33  5381.8  174.49
#Mann=6,-1,0
  4630.4    0.05       0  4699.3     0.1       0  4769.6    0.05       0
  4809.5     0.1       0  4995.6    0.07       0  5001.6     0.1       0
Bank Sta=4995.6,5001.6
Exp/Cntr=0.3,0.1

Type RM Length L Ch R = 1,1458,594,594,594
BEGIN DESCRIPTION:
UNT038 IN NURI 3.0
END DESCRIPTION:
XS GIS Cut Line= 3
      2302744.52     13300249.26      2302879.93     13300738.84
      2303003.81     13300873.04
#Sta/Elev= 30
  4644.7  175.30  4694.1  173.25  4829.1  164.52  4880.8  160.19  4891.2  159.99
  4903.7  158.40  4912.0  154.83  4922.3  157.90  4938.0  156.98  4943.2  155.23
  4953.5  155.41  4972.3  149.94  4995.0  145.72  5002.3  145.40  5005.1  144.90
  5008.3  145.40  5011.8  146.61  5017.0  147.12  5036.5  151.46  5057.2  152.45
  5067.6  151.18  5078.0  154.36  5085.6  155.86  5090.8  153.25  5098.7  157.99
  5125.1  159.77  5154.7  160.58  5191.9  162.68  5234.5  163.72  5335.3  167.94
#Mann=4,-1,0
  4644.7    0.05       0  4829.1     0.1       0  5002.3    0.07       0
  5008.3     0.1       0
Bank Sta=5002.3,5008.3
Exp/Cntr=0.3,0.1

Type RM Length L Ch R = 1,864,633,633,633
BEGIN DESCRIPTION:
UNT038 IN NURI 2.0
END DESCRIPTION:
XS GIS Cut Line= 2
      2302258.17     13300442.80      2302310.26     13301020.05
#Sta/Elev= 30
  4645.0  169.66  4749.5  164.77  4779.6  162.29  4810.8  160.78  4859.9  156.83
  4910.1  154.13  4916.7  153.16  4921.7  153.33  4940.3  151.96  4950.3  148.79
  4960.3  147.17  4970.4  146.32  4980.4  146.15  4990.5  143.64  4997.5  142.53
  5000.2  142.03  5003.5  142.53  5010.5  145.09  5020.6  146.42  5027.5  149.88
  5032.5  150.58  5040.7  153.21  5050.7  153.84  5060.7  155.46  5100.9  158.81
  5131.0  160.38  5138.4  161.31  5151.1  161.58  5181.2  163.75  5224.6  165.37
#Mann=3,-1,0
  4645.0     0.1       0  4997.5    0.07       0  5003.5     0.1       0
Bank Sta=4997.5,5003.5
Exp/Cntr=0.3,0.1

Type RM Length L Ch R = 1,231,0,0,0
BEGIN DESCRIPTION:
UNT038 IN NURI 1.0
END DESCRIPTION:
XS GIS Cut Line= 4
      2301824.85     13300447.48      2301663.55     13300668.45
      2301667.89     13301028.69      2301968.69     13301071.67
#Sta/Elev= 30
  4537.7  167.04  4609.2  165.47  4692.8  162.62  4852.5  154.73  4959.7  149.65
  4979.7  142.91  4989.7  142.37  4996.7  140.82  4999.4  140.32  5002.7  140.82
  5009.7  141.29  5019.7  143.18  5042.9  143.74  5079.7  146.13  5109.7  146.86
  5141.7  144.55  5149.7  144.38  5168.1  145.88  5190.2  145.17  5195.3  146.47
  5232.0  146.42  5252.2  147.33  5270.7  149.24  5312.8  149.51  5336.7  150.72
  5343.1  151.73  5369.5  152.35  5402.3  153.89  5413.8  153.80  5475.4  158.24
#Mann=9,-1,0
  4537.7    0.08       0  4609.2    0.05       0  4852.5     0.1       0
  4996.7    0.07       0  5002.7     0.1       0  5042.9    0.05       0
  5141.7     0.1       0  5270.7    0.05       0  5369.5     0.1       0
Bank Sta=4996.7,5002.7
Exp/Cntr=0.3,0.1

Chan Stop Cuts=-1