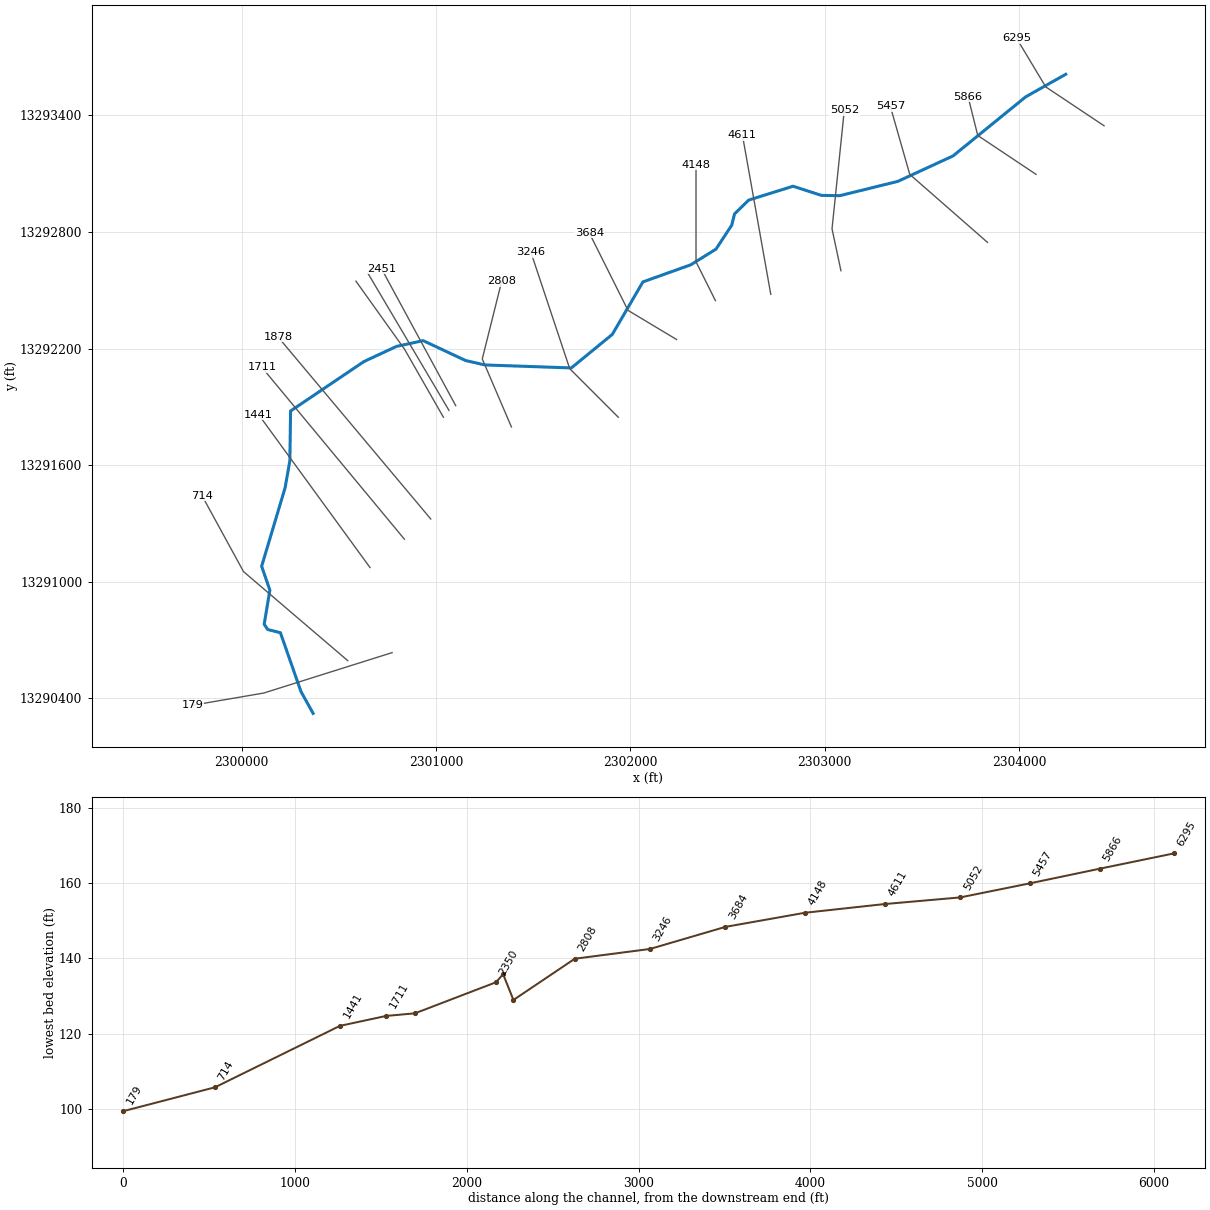
--- UNT039 IN NURI.prj (project) ---

Proj Title=UNT039 IN NURI Base Level Engineering
Current Plan=p01
Default Exp/Contr=0.3,0.1
English Units
Geom File=g01
Flow File=f01
Plan File=p01
BEGIN DESCRIPTION:
UNT039 IN NURI
END DESCRIPTION:

--- UNT039 IN NURI.p01 (plan) ---

Plan Title=Multiple Run
Short Identifier=Multiple
Geom File=g01
Flow File=f01
Subcritical Flow
K Sum by GR= 0
Std Step Tol= 0.01
Critical Tol= 0.01
Num of Std Step Trials= 20
Max Error Tol= 0.3
Flow Tol Ratio= 0.001
Split Flow NTrial= 30
Split Flow Tol= 0.02
Split Flow Ratio= 0.02
Log Output Level= 0
Friction Slope Method= 1
Unsteady Friction Slope Method= 2
Unsteady Bridges Friction Slope Method= 1
Parabolic Critical Depth
Global Vel Dist=  1 , 1 , 1
Global Log Level= 0
CheckData=True
Encroach Param= -1, 0, 0, 0
BEGIN DESCRIPTION:
Multiple Run
END DESCRIPTION:

--- UNT039 IN NURI.f01 (steady flow) ---

Flow Title=Multiple
Number of Profiles=7
Profile Names=10-year,25-year,50-year,1pct_min,100-year,1pct_plu,500-year
River Rch & RM= UNT039 IN NURI,Reach-1,6295
     633     903    1132    1037    1402    1896    2160
River Rch & RM= UNT039 IN NURI,Reach-1,5457
     944    1375    1747    1620    2191    2963    3462
River Rch & RM= UNT039 IN NURI,Reach-1,1711
    1038    1525    1948    1816    2456    3322    3921
Boundary for River Rch & Prof#=UNT039 IN NURI,Reach-1,1
Up Type=0
Dn Type=3
Dn Slope=0.005
Boundary for River Rch & Prof#=UNT039 IN NURI,Reach-1,2
Up Type=0
Dn Type=3
Dn Slope=0.005
Boundary for River Rch & Prof#=UNT039 IN NURI,Reach-1,3
Up Type=0
Dn Type=3
Dn Slope=0.005
Boundary for River Rch & Prof#=UNT039 IN NURI,Reach-1,4
Up Type=0
Dn Type=3
Dn Slope=0.005
Boundary for River Rch & Prof#=UNT039 IN NURI,Reach-1,5
Up Type=0
Dn Type=3
Dn Slope=0.005
Boundary for River Rch & Prof#=UNT039 IN NURI,Reach-1,6
Up Type=0
Dn Type=3
Dn Slope=0.005
Boundary for River Rch & Prof#=UNT039 IN NURI,Reach-1,7
Up Type=0
Dn Type=3
Dn Slope=0.005

--- UNT039 IN NURI.g01 (geometry) ---

Geom Title=Existing Conditions

River Reach=UNT039 IN NURI,Reach-1
Reach XY= 30
      2304240.43     13293611.76      2304034.54     13293495.82
      2303660.46     13293191.63      2303376.16     13293060.63
      2303078.34     13292987.21      2302983.26     13292988.60
      2302837.19     13293035.72      2302608.70     13292964.41
      2302536.04     13292893.22      2302521.69     13292835.53
      2302440.48     13292711.95      2302310.59     13292631.29
      2302064.47     13292543.34      2301907.15     13292273.39
      2301696.03     13292100.62      2301251.66     13292115.89
      2301151.83     13292138.68      2300933.40     13292241.06
      2300796.17     13292211.31      2300628.77     13292133.41
      2300251.17     13291879.07      2300247.48     13291623.50
      2300223.17     13291484.61      2300102.25     13291079.81
      2300144.57     13290957.20      2300115.27     13290781.42
      2300133.72     13290754.29      2300198.82     13290738.02
      2300304.29     13290436.02      2300366.98     13290322.78

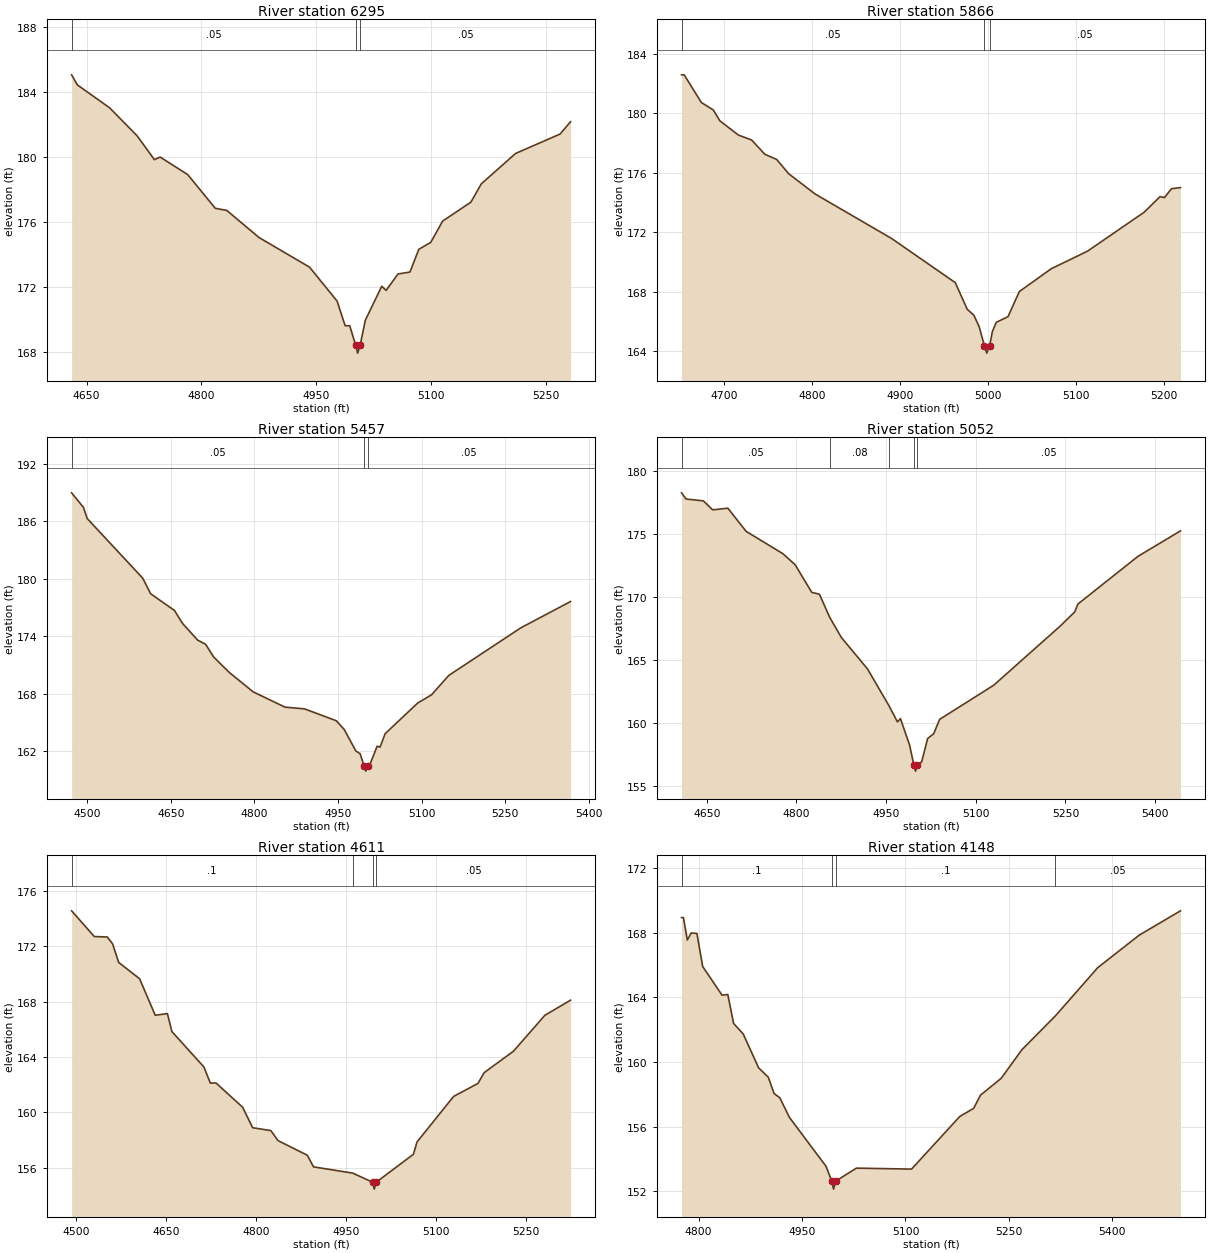
Type RM Length L Ch R = 1,6295,429,429,429
BEGIN DESCRIPTION:
UNT039 IN NURI 12.0
END DESCRIPTION:
XS GIS Cut Line= 3
      2304437.72     13293346.86      2304137.72     13293546.85
      2303987.72     13293796.86
#Sta/Elev= 30
  4630.4  185.06  4637.9  184.44  4680.0  183.03  4716.0  181.30  4738.6  179.83
  4746.1  179.99  4782.1  178.91  4818.2  176.83  4833.2  176.70  4875.3  175.03
  4941.4  173.20  4977.4  171.11  4987.9  169.59  4993.9  169.59  5001.6  168.40
  5004.3  167.90  5007.6  168.40  5014.3  169.93  5035.7  172.02  5041.5  171.77
  5057.0  172.78  5072.6  172.90  5084.2  174.30  5099.8  174.73  5115.3  176.04
  5152.3  177.21  5165.9  178.34  5210.6  180.21  5268.9  181.41  5282.5  182.17
#Mann=3,-1,0
  4630.4    0.05       0  5001.6    0.03       0  5007.6    0.05       0
Bank Sta=5001.6,5007.6
Exp/Cntr=0.3,0.1

Type RM Length L Ch R = 1,5866,409,409,409
BEGIN DESCRIPTION:
UNT039 IN NURI 11.0
END DESCRIPTION:
XS GIS Cut Line= 3
      2304087.69     13293096.87      2303787.72     13293296.85
      2303737.71     13293496.88
#Sta/Elev= 30
  4651.7  182.57  4654.7  182.57  4674.2  180.71  4687.7  180.21  4695.2  179.48
  4716.3  178.52  4731.3  178.19  4746.3  177.23  4759.8  176.88  4773.4  175.92
  4803.4  174.56  4890.5  171.56  4962.6  168.60  4976.2  166.81  4983.7  166.41
  4989.7  165.65  4995.7  164.36  4998.4  163.86  5001.7  164.36  5004.7  165.30
  5009.2  165.93  5022.5  166.31  5035.4  168.00  5071.5  169.53  5112.7  170.71
  5177.1  173.33  5195.2  174.38  5200.3  174.32  5208.1  174.91  5218.4  174.99
#Mann=3,-1,0
  4651.7    0.05       0  4995.7    0.03       0  5001.7    0.05       0
Bank Sta=4995.7,5001.7
Exp/Cntr=0.3,0.1

Type RM Length L Ch R = 1,5457,405,405,405
BEGIN DESCRIPTION:
UNT039 IN NURI 10.0
END DESCRIPTION:
XS GIS Cut Line= 3
      2303837.74     13292746.84      2303437.72     13293096.85
      2303337.73     13293446.82
#Sta/Elev= 30
  4472.0  188.96  4493.4  187.43  4500.0  186.28  4599.7  180.06  4613.9  178.44
  4656.6  176.70  4670.9  175.36  4698.4  173.60  4712.6  173.17  4726.9  171.85
  4755.3  170.22  4798.0  168.21  4855.0  166.62  4890.1  166.44  4947.1  165.20
  4961.3  164.29  4982.2  162.05  4989.8  161.77  4997.2  160.45  5000.0  159.95
  5003.2  160.45  5006.1  160.45  5020.4  162.55  5025.6  162.45  5034.7  163.85
  5093.2  167.05  5117.9  167.90  5149.1  169.93  5277.8  174.87  5367.5  177.63
#Mann=3,-1,0
  4472.0    0.05       0  4997.2    0.03       0  5003.2    0.05       0
Bank Sta=4997.2,5003.2
Exp/Cntr=0.3,0.1

Type RM Length L Ch R = 1,5052,441,441,441
BEGIN DESCRIPTION:
UNT039 IN NURI 9.0
END DESCRIPTION:
XS GIS Cut Line= 3
      2303083.58     13292601.09      2303037.72     13292816.35
      2303100.95     13293427.49
#Sta/Elev= 30
  4607.8  178.30  4615.4  177.81  4644.4  177.66  4659.8  176.95  4685.3  177.08
  4715.9  175.24  4777.3  173.47  4797.7  172.60  4825.6  170.40  4838.5  170.25
  4855.4  168.44  4875.1  166.82  4918.9  164.32  4955.0  161.38  4968.9  160.12
  4973.9  160.38  4989.3  158.27  4996.3  156.71  4999.1  156.21  5002.3  156.71
  5009.4  156.94  5019.4  158.80  5029.5  159.17  5039.5  160.32  5130.0  163.03
  5240.6  167.70  5265.5  168.85  5270.7  169.47  5371.3  173.26  5442.3  175.28
#Mann=5,-1,0
  4607.8    0.05       0  4855.4    0.08       0  4955.0    0.05       0
  4996.3    0.03       0  5002.3    0.05       0
Bank Sta=4996.3,5002.3
Exp/Cntr=0.3,0.1

Type RM Length L Ch R = 1,4611,463,463,463
BEGIN DESCRIPTION:
UNT039 IN NURI 8.0
END DESCRIPTION:
XS GIS Cut Line= 2
      2302722.47     13292479.56      2302576.64     13293298.98
#Sta/Elev= 30
  4492.8  174.56  4530.7  172.70  4552.3  172.67  4561.2  172.17  4571.3  170.83
  4606.2  169.65  4632.3  167.01  4652.6  167.13  4660.1  165.83  4713.5  163.27
  4724.2  162.11  4733.8  162.11  4778.1  160.36  4794.8  158.88  4825.2  158.67
  4837.1  157.95  4886.0  156.89  4896.3  156.05  4961.5  155.60  4994.9  154.94
  4997.7  154.44  5000.9  154.94  5063.0  156.96  5069.0  157.85  5130.0  161.14
  5170.6  162.08  5181.0  162.86  5229.9  164.41  5282.3  167.01  5325.1  168.10
#Mann=4,-1,0
  4492.8     0.1       0  4961.5    0.05       0  4994.9    0.04       0
  5000.9    0.05       0
Bank Sta=4994.9,5000.9
Exp/Cntr=0.3,0.1

Type RM Length L Ch R = 1,4148,464,464,464
BEGIN DESCRIPTION:
UNT039 IN NURI 7.0
END DESCRIPTION:
XS GIS Cut Line= 3
      2302437.71     13292446.87      2302337.72     13292646.85
      2302337.72     13293146.86
#Sta/Elev= 30
  4775.2  168.94  4778.0  168.94  4783.6  167.55  4789.2  167.99  4797.5  167.96
  4805.9  165.91  4833.9  164.14  4842.3  164.18  4850.7  162.39  4864.6  161.74
  4887.0  159.64  4901.0  159.06  4909.4  158.05  4917.7  157.79  4931.7  156.57
  4984.8  153.54  4993.0  152.63  4995.7  152.13  4999.0  152.63  5028.8  153.43
  5108.8  153.37  5178.8  156.63  5198.8  157.13  5208.8  157.95  5238.8  158.99
  5268.8  160.76  5317.3  162.85  5378.8  165.84  5438.8  167.85  5498.8  169.36
#Mann=4,-1,0
  4775.2     0.1       0  4993.0    0.07       0  4999.0     0.1       0
  5317.3    0.05       0
Bank Sta=4993,4999
Exp/Cntr=0.3,0.1

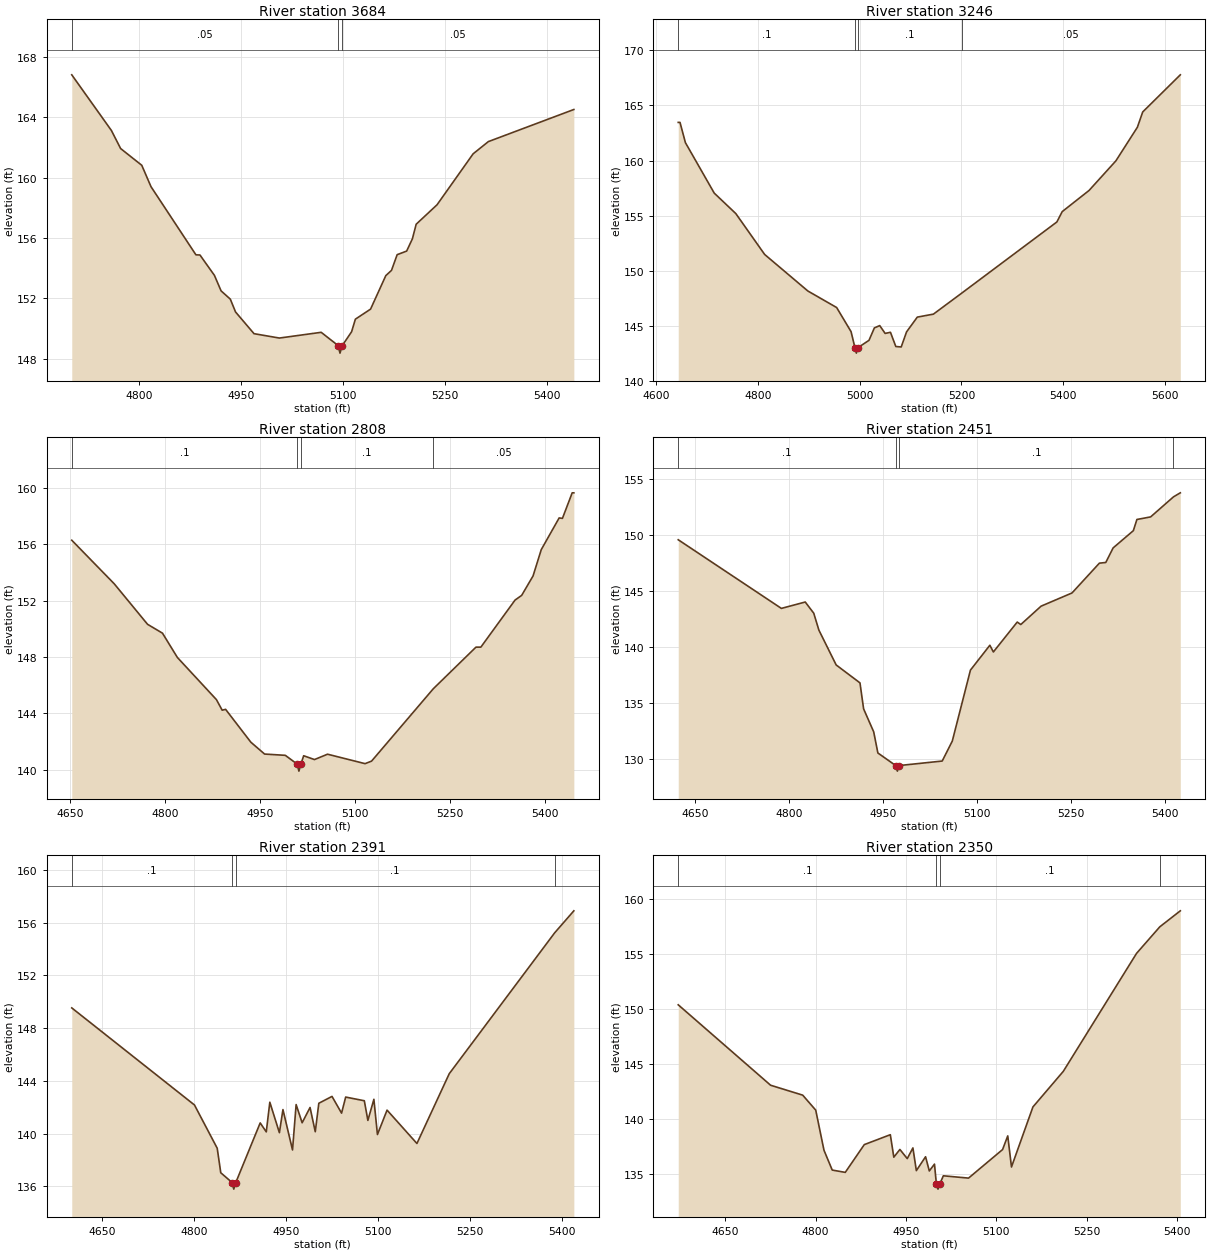
Type RM Length L Ch R = 1,3684,438,438,438
BEGIN DESCRIPTION:
UNT039 IN NURI 6.0
END DESCRIPTION:
XS GIS Cut Line= 3
      2302237.74     13292246.84      2301987.72     13292396.85
      2301787.71     13292796.87
#Sta/Elev= 30
  4701.2  166.83  4759.5  163.14  4773.1  161.94  4804.2  160.83  4817.8  159.41
  4883.9  154.89  4889.8  154.88  4911.1  153.53  4920.9  152.50  4934.5  151.95
  4942.2  151.10  4969.4  149.66  5006.7  149.37  5068.2  149.75  5093.2  148.87
  5095.9  148.37  5099.2  148.87  5113.0  149.79  5118.5  150.62  5140.9  151.29
  5163.3  153.51  5171.7  153.86  5180.0  154.90  5194.0  155.14  5202.4  155.95
  5208.0  156.92  5238.7  158.21  5291.8  161.59  5314.2  162.40  5440.0  164.53
#Mann=3,-1,0
  4701.2    0.05       0  5093.2    0.03       0  5099.2    0.05       0
Bank Sta=5093.2,5099.2
Exp/Cntr=0.3,0.1

Type RM Length L Ch R = 1,3246,438,438,438
BEGIN DESCRIPTION:
UNT039 IN NURI 5.0
END DESCRIPTION:
XS GIS Cut Line= 3
      2301937.72     13291846.86      2301687.72     13292096.85
      2301487.72     13292696.85
#Sta/Elev= 30
  4643.9  163.46  4647.4  163.46  4658.0  161.62  4714.6  157.04  4757.0  155.18
  4813.6  151.47  4898.5  148.15  4955.0  146.65  4983.3  144.46  4990.9  143.01
  4993.7  142.51  4996.9  143.01  5018.5  143.67  5029.1  144.80  5039.6  145.01
  5050.2  144.30  5060.7  144.40  5071.2  143.11  5081.8  143.07  5092.3  144.44
  5113.4  145.78  5145.0  146.05  5200.7  147.96  5387.5  154.42  5398.0  155.36
  5450.7  157.28  5503.4  159.97  5545.6  163.02  5556.1  164.41  5629.9  167.78
#Mann=4,-1,0
  4643.9     0.1       0  4990.9    0.07       0  4996.9     0.1       0
  5200.7    0.05       0
Bank Sta=4990.9,4996.9
Exp/Cntr=0.3,0.1

Type RM Length L Ch R = 1,2808,357,357,357
BEGIN DESCRIPTION:
UNT039 IN NURI 4.0
END DESCRIPTION:
XS GIS Cut Line= 3
      2301387.73     13291796.84      2301237.72     13292146.85
      2301337.72     13292546.84
#Sta/Elev= 30
  4652.7  156.28  4719.8  153.19  4772.4  150.32  4796.0  149.69  4819.5  147.97
  4881.2  144.98  4890.3  144.23  4895.7  144.29  4935.6  141.96  4957.3  141.12
  4990.0  141.03  5008.7  140.41  5011.5  139.91  5014.7  140.41  5019.0  141.00
  5036.1  140.73  5056.7  141.11  5116.0  140.44  5126.3  140.62  5223.8  145.75
  5291.2  148.70  5298.9  148.70  5353.0  152.04  5363.4  152.37  5381.4  153.75
  5394.3  155.61  5422.6  157.86  5427.8  157.83  5443.2  159.64  5445.8  159.64
#Mann=4,-1,0
  4652.7     0.1       0  5008.7    0.07       0  5014.7     0.1       0
  5223.8    0.05       0
Bank Sta=5008.7,5014.7
Exp/Cntr=0.3,0.1

Type RM Length L Ch R = 1,2451,60,60,60
BEGIN DESCRIPTION:
Mapping XS 816368a4
END DESCRIPTION:
XS GIS Cut Line= 2
      2301100.96     13291906.59      2300719.01     13292611.46
#Sta/Elev= 30
  4622.6  149.61  4787.3  143.48  4825.4  144.05  4839.0  143.05  4847.2  141.54
  4874.8  138.43  4912.8  136.83  4918.6  134.51  4934.7  132.46  4941.4  130.57
  4969.8  129.45  4972.5  128.95  4975.8  129.45  5044.1  129.85  5060.2  131.63
  5089.2  137.97  5120.2  140.19  5125.8  139.59  5163.9  142.26  5169.6  142.04
  5202.0  143.68  5251.4  144.86  5295.1  147.52  5305.3  147.58  5317.0  148.88
  5349.3  150.42  5355.0  151.42  5376.9  151.65  5413.4  153.44  5424.3  153.80
#Mann=4,-1,0
  4622.6     0.1       0  4969.8    0.07       0  4975.8     0.1       0
  5413.4    0.05       0
Bank Sta=4969.8,4975.8
Exp/Cntr=0.3,0.1

Type RM Length L Ch R = 1,2391,41,41,41
BEGIN DESCRIPTION:
Mapping XS 58d5b95f
END DESCRIPTION:
XS GIS Cut Line= 2
      2301066.20     13291882.36      2300649.54     13292587.21
#Sta/Elev= 30
  4601.0  149.54  4801.1  142.18  4838.2  138.90  4844.0  137.04  4862.5  136.30
  4865.2  135.80  4868.5  136.30  4908.3  140.82  4918.2  140.14  4924.0  142.39
  4939.6  140.08  4945.4  141.83  4961.0  138.77  4966.9  142.21  4976.7  140.83
  4989.6  141.99  4998.1  140.15  5003.9  142.31  5025.4  142.83  5041.0  141.56
  5047.7  142.78  5078.1  142.50  5083.9  141.01  5093.7  142.61  5099.5  139.94
  5115.2  141.79  5163.9  139.26  5216.6  144.55  5388.5  155.23  5419.8  156.90
#Mann=4,-1,0
  4601.0     0.1       0  4862.5    0.07       0  4868.5     0.1       0
  5388.5    0.05       0
Bank Sta=4862.5,4868.5
Exp/Cntr=0.3,0.1

Type RM Length L Ch R = 1,2350,472,472,472
BEGIN DESCRIPTION:
UNT039 IN NURI 3.0
END DESCRIPTION:
XS GIS Cut Line= 3
      2301037.73     13291846.84      2300837.72     13292196.85
      2300587.69     13292546.90
#Sta/Elev= 30
  4571.9  150.40  4725.2  143.10  4778.5  142.20  4800.1  140.84  4813.8  137.20
  4827.5  135.40  4849.1  135.19  4880.7  137.71  4923.9  138.61  4929.7  136.57
  4939.8  137.27  4952.0  136.44  4961.4  137.41  4967.1  135.35  4982.4  136.61
  4988.6  135.32  4997.2  135.94  5000.3  134.17  5003.0  133.67  5006.3  134.17
  5011.9  134.88  5053.7  134.67  5110.2  137.26  5118.8  138.50  5125.0  135.68
  5160.6  141.13  5211.0  144.36  5332.6  155.07  5371.2  157.48  5405.2  158.93
#Mann=4,-1,0
  4571.9     0.1       0  5000.3    0.07       0  5006.3     0.1       0
  5371.2    0.05       0
Bank Sta=5000.3,5006.3
Exp/Cntr=0.3,0.1

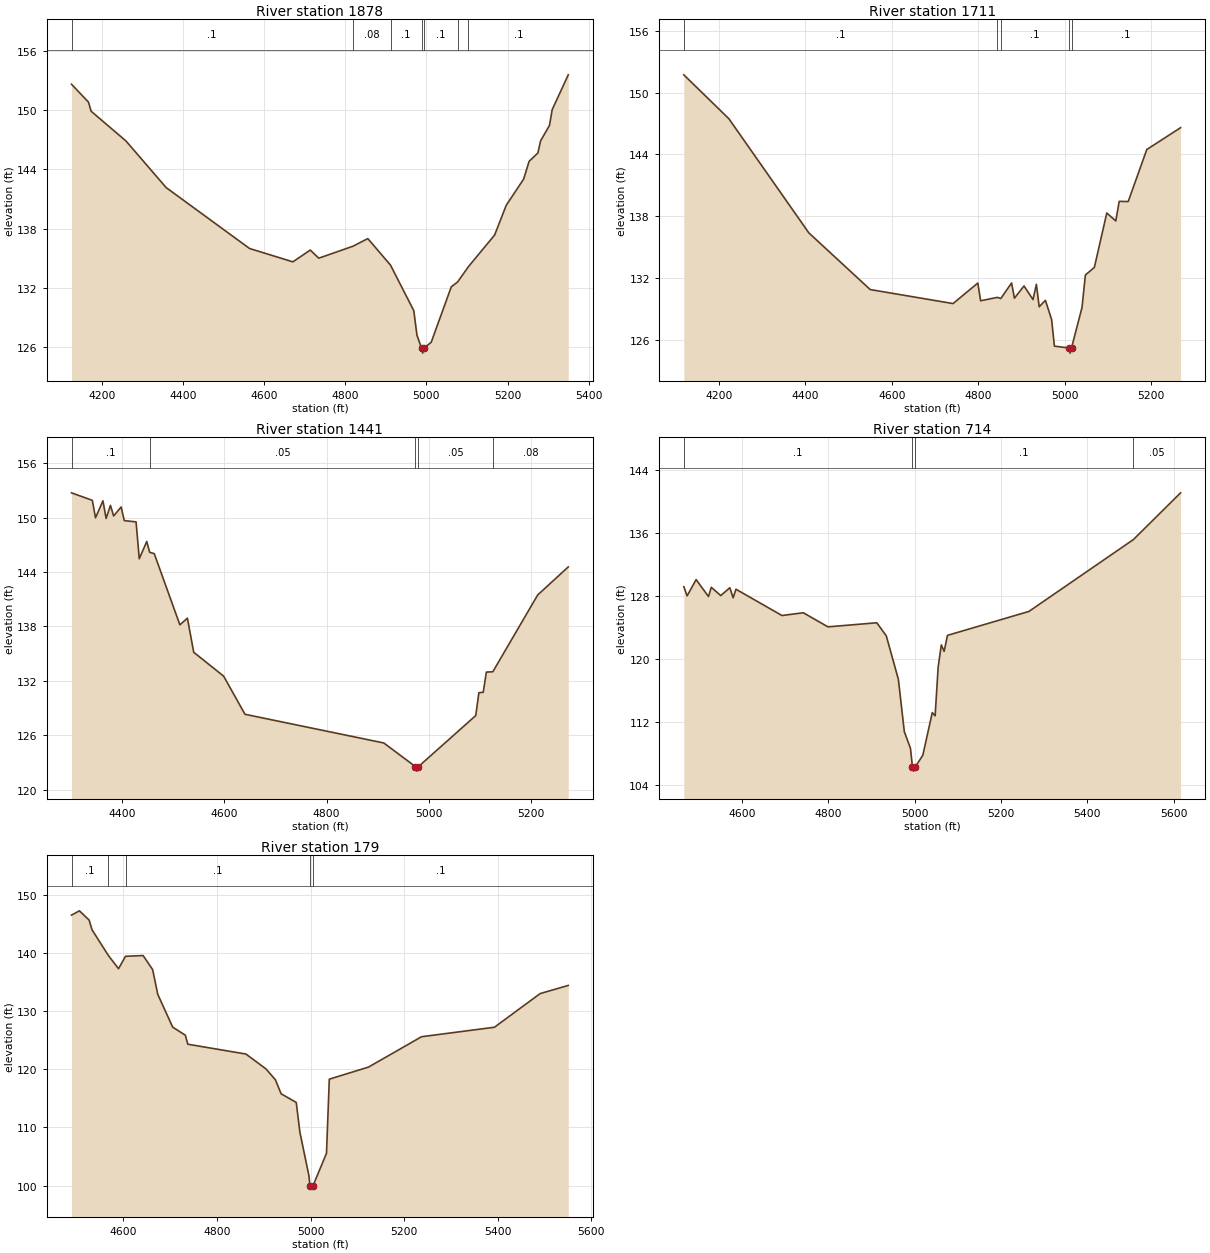
Type RM Length L Ch R = 1,1878,167,167,167
BEGIN DESCRIPTION:
UNT039 IN NURI 2.0
END DESCRIPTION:
XS GIS Cut Line= 2
      2300972.49     13291323.27      2300186.03     13292260.77
#Sta/Elev= 30
  4125.7  152.60  4167.5  150.79  4174.0  149.87  4259.9  146.86  4358.8  142.15
  4564.3  135.99  4671.0  134.64  4713.9  135.83  4734.8  135.01  4819.1  136.22
  4855.7  136.99  4911.5  134.31  4968.9  129.70  4976.7  127.22  4988.0  125.91
  4990.8  125.41  4994.0  125.91  5011.8  126.51  5061.3  132.12  5076.7  132.60
  5103.6  134.16  5168.0  137.35  5196.6  140.36  5239.5  143.01  5252.9  144.80
  5274.6  145.65  5281.2  146.87  5303.2  148.44  5309.8  150.03  5349.4  153.55
#Mann=7,-1,0
  4125.7     0.1       0  4819.1    0.08       0  4911.5     0.1       0
  4988.0    0.07       0  4994.0     0.1       0  5076.7    0.08       0
  5103.6     0.1       0
Bank Sta=4988,4994
Exp/Cntr=0.3,0.1

Type RM Length L Ch R = 1,1711,270,270,270
BEGIN DESCRIPTION:
Mapping XS d84bc7ff
END DESCRIPTION:
XS GIS Cut Line= 2
      2300837.08     13291219.09      2300103.82     13292103.17
#Sta/Elev= 30
  4119.1  151.73  4223.3  147.47  4408.2  136.39  4550.1  130.89  4741.6  129.53
  4798.9  131.52  4805.4  129.80  4844.1  130.13  4852.0  130.02  4877.0  131.53
  4883.5  130.05  4905.7  131.24  4926.5  129.92  4934.3  131.40  4940.8  129.22
  4955.2  129.84  4969.5  127.98  4976.0  125.40  5009.5  125.22  5012.2  124.72
  5015.5  125.22  5039.8  129.15  5047.6  132.30  5068.4  133.04  5097.1  138.32
  5117.9  137.55  5125.8  139.45  5146.6  139.43  5189.6  144.48  5267.7  146.60
#Mann=5,-1,0
  4119.1     0.1       0  4844.1    0.08       0  4852.0     0.1       0
  5009.5    0.07       0  5015.5     0.1       0
Bank Sta=5009.5,5015.5
Exp/Cntr=0.3,0.1

Type RM Length L Ch R = 1,1441,727,727,727
BEGIN DESCRIPTION:
Mapping XS f5515d1a
END DESCRIPTION:
XS GIS Cut Line= 2
      2300659.95     13291073.33      2300087.04     13291859.78
#Sta/Elev= 30
  4300.5  152.72  4341.3  151.89  4347.5  149.97  4362.1  151.84  4368.3  149.90
  4376.8  151.34  4383.0  150.17  4397.7  151.16  4403.9  149.66  4427.0  149.52
  4433.2  145.46  4447.9  147.36  4453.6  146.17  4462.6  146.02  4512.8  138.18
  4527.5  138.92  4539.9  135.16  4598.5  132.53  4640.3  128.33  4912.2  125.17
  4974.1  122.57  4976.9  122.07  4980.1  122.57  5092.3  128.19  5098.4  130.71
  5106.9  130.75  5113.1  132.98  5125.7  133.01  5213.6  141.47  5273.5  144.56
#Mann=5,-1,0
  4300.5     0.1       0  4453.6    0.05       0  4974.1    0.04       0
  4980.1    0.05       0  5125.7    0.08       0
Bank Sta=4974.1,4980.1
Exp/Cntr=0.3,0.1

Type RM Length L Ch R = 1,714,535,535,535
BEGIN DESCRIPTION:
Mapping XS 8a2e1cdb
END DESCRIPTION:
XS GIS Cut Line= 3
      2300545.35     13290594.15      2300008.93     13291052.46
      2299795.74     13291442.44
#Sta/Elev= 30
  4465.9  129.17  4473.6  128.01  4494.4  130.07  4523.0  127.92  4529.5  129.09
  4551.5  128.04  4572.4  129.04  4580.1  127.76  4586.6  128.85  4693.1  125.51
  4742.5  125.86  4799.6  124.07  4912.7  124.59  4934.7  122.92  4962.6  117.41
  4976.4  110.76  4990.6  108.65  4995.3  106.25  4998.1  105.75  5001.3  106.25
  5019.2  107.77  5041.1  113.18  5047.7  112.78  5054.7  118.95  5062.0  121.78
  5068.6  120.96  5076.3  122.99  5264.9  126.03  5506.6  135.15  5615.9  141.09
#Mann=4,-1,0
  4465.9     0.1       0  4995.3    0.07       0  5001.3     0.1       0
  5506.6    0.05       0
Bank Sta=4995.3,5001.3
Exp/Cntr=0.3,0.1

Type RM Length L Ch R = 1,179,0,0,0
BEGIN DESCRIPTION:
UNT039 IN NURI 1.0
END DESCRIPTION:
XS GIS Cut Line= 3
      2300773.71     13290635.39      2300113.10     13290427.46
      2299748.48     13290364.95
#Sta/Elev= 30
  4488.8  146.51  4505.7  147.25  4526.5  145.66  4532.8  143.98  4567.9  139.54
  4589.4  137.30  4604.3  139.43  4641.9  139.56  4662.3  137.15  4673.3  132.89
  4705.2  127.25  4732.3  125.86  4737.6  124.31  4861.9  122.62  4904.7  120.07
  4924.9  118.20  4937.1  115.79  4969.5  114.30  4977.3  109.18  4996.6  101.71
  4998.9   99.89  5001.6   99.39  5004.9   99.89  5034.2  105.56  5040.2  118.30
  5124.1  120.38  5237.5  125.60  5393.4  127.23  5491.2  133.02  5551.3  134.42
#Mann=5,-1,0
  4488.8     0.1       0  4567.9    0.08       0  4604.3     0.1       0
  4998.9    0.07       0  5004.9     0.1       0
Bank Sta=4998.9,5004.9
Exp/Cntr=0.3,0.1

Chan Stop Cuts=-1