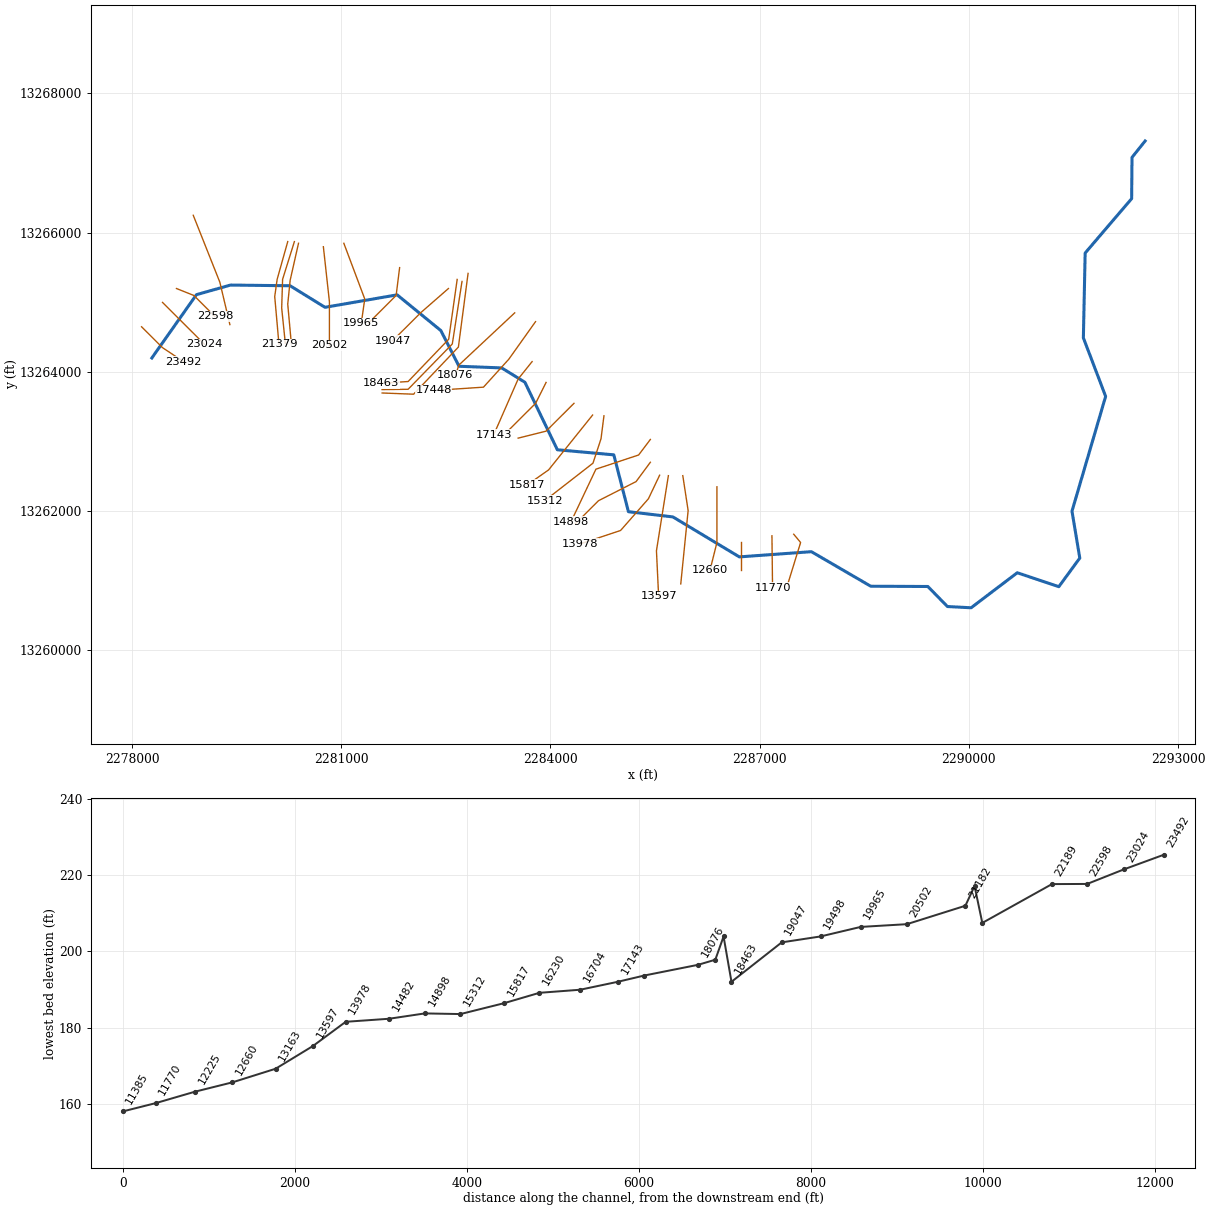
--- UNT040 IN NURI.prj (project) ---

Proj Title=UNT040 IN NURI Base Level Engineering
Current Plan=p01
Default Exp/Contr=0.3,0.1
English Units
Geom File=g01
Flow File=f01
Plan File=p01
BEGIN DESCRIPTION:
UNT040 IN NURI
END DESCRIPTION:

--- UNT040 IN NURI.p01 (plan) ---

Plan Title=Multiple Run
Short Identifier=Multiple
Geom File=g01
Flow File=f01
Subcritical Flow
K Sum by GR= 0
Std Step Tol= 0.01
Critical Tol= 0.01
Num of Std Step Trials= 20
Max Error Tol= 0.3
Flow Tol Ratio= 0.001
Split Flow NTrial= 30
Split Flow Tol= 0.02
Split Flow Ratio= 0.02
Log Output Level= 0
Friction Slope Method= 1
Unsteady Friction Slope Method= 2
Unsteady Bridges Friction Slope Method= 1
Parabolic Critical Depth
Global Vel Dist=  1 , 1 , 1
Global Log Level= 0
CheckData=True
Encroach Param= -1, 0, 0, 0
BEGIN DESCRIPTION:
Multiple Run
END DESCRIPTION:

--- UNT040 IN NURI.f01 (steady flow) ---

Flow Title=Multiple
Number of Profiles=7
Profile Names=10-year,25-year,50-year,1pct_min,100-year,1pct_plu,500-year
River Rch & RM= UNT040 IN NURI,Reach-1,23492
     216     298     366     331     448     606     680
River Rch & RM= UNT040 IN NURI,Reach-1,21379
     445     636     799     738     998    1350    1580
River Rch & RM= UNT040 IN NURI,Reach-1,13163
     612     883    1117    1036    1401    1895    2239
River Rch & RM= UNT040 IN NURI,Reach-1,2848
     864    1261    1608    1501    2030    2745    3280
Boundary for River Rch & Prof#=UNT040 IN NURI,Reach-1,1
Up Type=0
Dn Type=3
Dn Slope=0.005
Boundary for River Rch & Prof#=UNT040 IN NURI,Reach-1,2
Up Type=0
Dn Type=3
Dn Slope=0.005
Boundary for River Rch & Prof#=UNT040 IN NURI,Reach-1,3
Up Type=0
Dn Type=3
Dn Slope=0.005
Boundary for River Rch & Prof#=UNT040 IN NURI,Reach-1,4
Up Type=0
Dn Type=3
Dn Slope=0.005
Boundary for River Rch & Prof#=UNT040 IN NURI,Reach-1,5
Up Type=0
Dn Type=3
Dn Slope=0.005
Boundary for River Rch & Prof#=UNT040 IN NURI,Reach-1,6
Up Type=0
Dn Type=3
Dn Slope=0.005
Boundary for River Rch & Prof#=UNT040 IN NURI,Reach-1,7
Up Type=0
Dn Type=3
Dn Slope=0.005

--- UNT040 IN NURI.g01 (geometry) ---

Geom Title=Existing Conditions

River Reach=UNT040 IN NURI,Reach-1
Reach XY= 30
      2278284.70     13264198.72      2278924.22     13265108.43
      2279412.17     13265246.39      2280267.29     13265236.41
      2280767.96     13264926.69      2281802.23     13265105.80
      2282429.31     13264592.14      2282689.32     13264079.57
      2283301.97     13264055.56      2283634.20     13263849.44
      2284099.31     13262879.51      2284908.88     13262806.45
      2285118.73     13261989.43      2285756.73     13261914.38
      2286708.88     13261340.03      2287742.31     13261414.76
      2288593.38     13260918.44      2289412.05     13260914.61
      2289692.88     13260626.83      2290032.19     13260608.70
      2290694.41     13261112.09      2291290.22     13260911.93
      2291590.85     13261323.37      2291479.02     13261996.97
      2291961.54     13263646.86      2291642.17     13264487.42
      2291667.72     13265706.85      2292334.35     13266488.25
      2292339.60     13267081.17      2292527.72     13267316.85

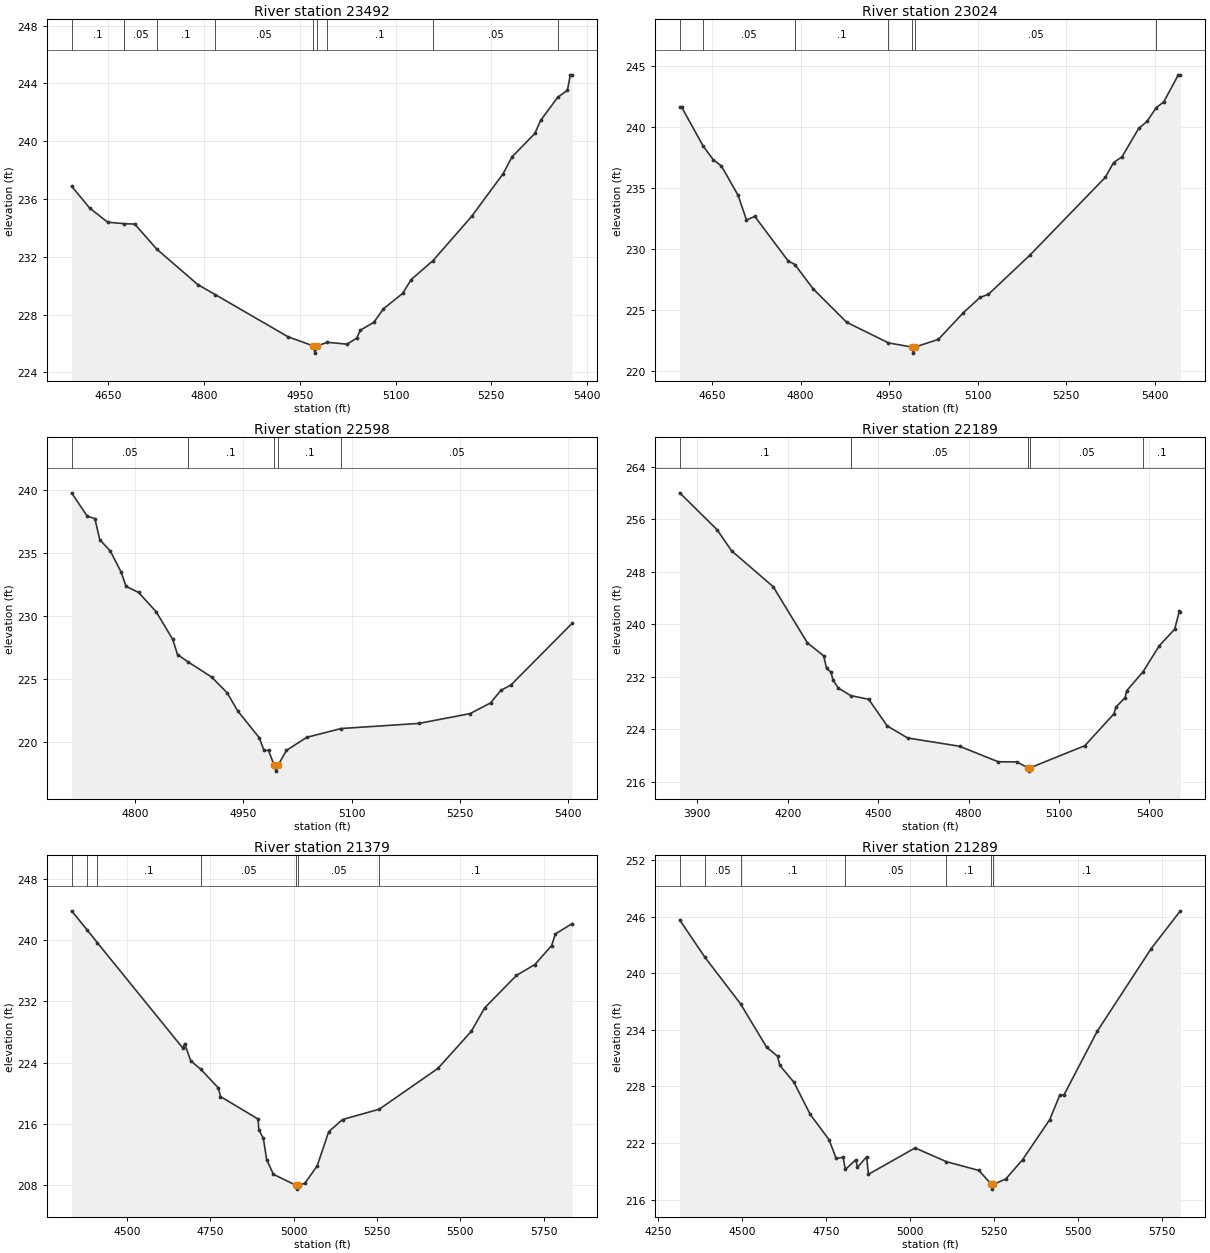
Type RM Length L Ch R = 1,23492,468,468,468
BEGIN DESCRIPTION:
UNT040 IN NURI 52.0
END DESCRIPTION:
XS GIS Cut Line= 3
      2278137.72     13264646.86      2278437.72     13264346.85
      2278737.70     13264146.87
#Sta/Elev= 30
  4592.2  236.90  4620.5  235.38  4648.8  234.40  4674.4  234.30  4691.2  234.27
  4725.9  232.53  4790.2  230.08  4817.5  229.39  4931.6  226.47  4971.0  225.84
  4973.8  225.34  4977.0  225.84  4993.2  226.09  5024.0  225.96  5039.0  226.37
  5045.0  226.93  5066.0  227.47  5081.1  228.41  5111.1  229.47  5124.6  230.43
  5158.9  231.75  5219.3  234.80  5268.9  237.77  5282.4  238.91  5318.4  240.54
  5327.4  241.44  5354.4  243.05  5369.5  243.53  5374.0  244.60  5377.0  244.60
#Mann=9,-1,0
  4592.2     0.1       0  4674.4    0.05       0  4725.9     0.1       0
  4817.5    0.05       0  4971.0    0.07       0  4977.0    0.05       0
  4993.2     0.1       0  5158.9    0.05       0  5354.4     0.1       0
Bank Sta=4971,4977
Exp/Cntr=0.3,0.1

Type RM Length L Ch R = 1,23024,426,426,426
BEGIN DESCRIPTION:
UNT040 IN NURI 51.0
END DESCRIPTION:
XS GIS Cut Line= 3
      2278437.75     13264996.83      2278737.72     13264696.85
      2279037.73     13264396.85
#Sta/Elev= 30
  4595.2  241.60  4598.7  241.60  4634.7  238.45  4651.7  237.33  4665.9  236.80
  4694.2  234.39  4708.3  232.38  4722.4  232.67  4779.0  229.02  4790.3  228.73
  4821.4  226.73  4878.0  224.00  4949.0  222.31  4988.1  221.97  4990.9  221.47
  4994.1  221.97  5033.6  222.60  5076.0  224.79  5104.3  226.04  5118.4  226.29
  5189.1  229.52  5316.4  235.87  5330.5  237.08  5344.7  237.55  5373.0  239.88
  5387.1  240.45  5402.9  241.59  5415.4  242.04  5440.2  244.27  5443.7  244.27
#Mann=7,-1,0
  4595.2     0.1       0  4634.7    0.05       0  4790.3     0.1       0
  4949.0    0.05       0  4988.1    0.03       0  4994.1    0.05       0
  5402.9     0.1       0
Bank Sta=4988.1,4994.1
Exp/Cntr=0.3,0.1

Type RM Length L Ch R = 1,22598,409,409,409
BEGIN DESCRIPTION:
UNT040 IN NURI 50.0
END DESCRIPTION:
XS GIS Cut Line= 3
      2278637.71     13265196.86      2278887.72     13265096.85
      2279187.70     13264796.88
#Sta/Elev= 30
  4711.9  239.81  4733.4  237.97  4744.2  237.75  4751.0  236.08  4765.8  235.16
  4780.6  233.49  4787.3  232.37  4804.8  231.88  4829.0  230.35  4851.9  228.16
  4858.7  226.94  4872.9  226.37  4905.8  225.15  4927.3  223.90  4942.1  222.45
  4971.7  220.33  4978.5  219.31  4984.7  219.31  4992.3  218.16  4995.1  217.66
  4998.3  218.16  5009.5  219.31  5037.7  220.35  5085.3  221.05  5193.3  221.46
  5264.0  222.24  5292.3  223.09  5306.4  224.08  5320.6  224.52  5405.4  229.43
#Mann=5,-1,0
  4711.9    0.05       0  4872.9     0.1       0  4992.3    0.07       0
  4998.3     0.1       0  5085.3    0.05       0
Bank Sta=4992.3,4998.3
Exp/Cntr=0.3,0.1

Type RM Length L Ch R = 1,22189,810,810,810
BEGIN DESCRIPTION:
UNT040 IN NURI 49.0
END DESCRIPTION:
XS GIS Cut Line= 3
      2278878.35     13266249.55      2279260.28     13265286.05
      2279403.50     13264678.44
#Sta/Elev= 30
  3841.8  260.01  3965.3  254.41  4014.0  251.17  4151.7  245.72  4265.2  237.16
  4319.2  235.18  4328.8  233.27  4343.5  232.70  4350.3  231.47  4367.8  230.27
  4408.7  229.13  4468.6  228.56  4529.9  224.51  4597.7  222.67  4769.8  221.41
  4898.0  219.05  4959.6  219.02  4997.7  218.12  5000.4  217.62  5003.7  218.12
  5185.6  221.50  5282.2  226.36  5288.4  227.36  5319.2  228.83  5324.5  229.87
  5379.0  232.78  5432.2  236.70  5483.6  239.25  5499.0  241.97  5502.5  241.87
#Mann=5,-1,0
  3841.8     0.1       0  4408.7    0.05       0  4997.7    0.03       0
  5003.7    0.05       0  5379.0     0.1       0
Bank Sta=4997.7,5003.7
Exp/Cntr=0.3,0.1

Type RM Length L Ch R = 1,21379,90,90,90
BEGIN DESCRIPTION:
UNT040 IN NURI 48.0
END DESCRIPTION:
XS GIS Cut Line= 4
      2280233.37     13265871.12      2280081.46     13265328.58
      2280046.74     13265081.19      2280107.50     13264395.40
#Sta/Elev= 30
  4334.2  243.86  4380.1  241.41  4411.6  239.68  4668.1  225.89  4673.3  226.48
  4691.7  224.23  4721.9  223.12  4774.8  220.67  4780.8  219.56  4893.6  216.61
  4895.9  215.22  4909.4  214.09  4919.5  211.28  4939.7  209.38  5007.4  207.94
  5010.2  207.44  5013.4  207.94  5034.0  208.20  5071.0  210.49  5105.4  214.95
  5147.1  216.55  5257.1  217.90  5432.9  223.23  5533.3  228.10  5573.4  231.16
  5668.6  235.41  5724.0  236.83  5774.2  239.32  5785.5  240.84  5835.9  242.19
#Mann=7,-1,0
  4334.2     0.1       0  4380.1    0.05       0  4411.6     0.1       0
  4721.9    0.05       0  5007.4    0.03       0  5013.4    0.05       0
  5257.1     0.1       0
Bank Sta=5007.4,5013.4
Exp/Cntr=0.3,0.1

Type RM Length L Ch R = 1,21289,107,107,107
BEGIN DESCRIPTION:
UNT040 IN NURI 47.0
END DESCRIPTION:
XS GIS Cut Line= 4
      2280328.87     13265871.16      2280159.58     13265328.58
      2280146.56     13264916.25      2280198.47     13264410.11
#Sta/Elev= 30
  4315.6  245.66  4390.8  241.69  4496.4  236.77  4574.0  232.17  4606.5  231.21
  4613.4  230.23  4655.3  228.45  4704.0  225.03  4760.1  222.34  4781.0  220.36
  4801.5  220.49  4808.5  219.20  4839.3  220.22  4844.5  219.43  4871.8  220.54
  4877.0  218.68  5015.8  221.48  5109.2  220.02  5205.9  219.09  5242.9  217.61
  5245.6  217.11  5248.9  217.61  5285.9  218.19  5336.1  220.25  5416.5  224.48
  5446.7  227.11  5458.3  227.06  5557.6  233.84  5718.1  242.61  5805.3  246.63
#Mann=7,-1,0
  4315.6     0.1       0  4390.8    0.05       0  4496.4     0.1       0
  4808.5    0.05       0  5109.2     0.1       0  5242.9    0.03       0
  5248.9     0.1       0
Bank Sta=5242.9,5248.9
Exp/Cntr=0.3,0.1

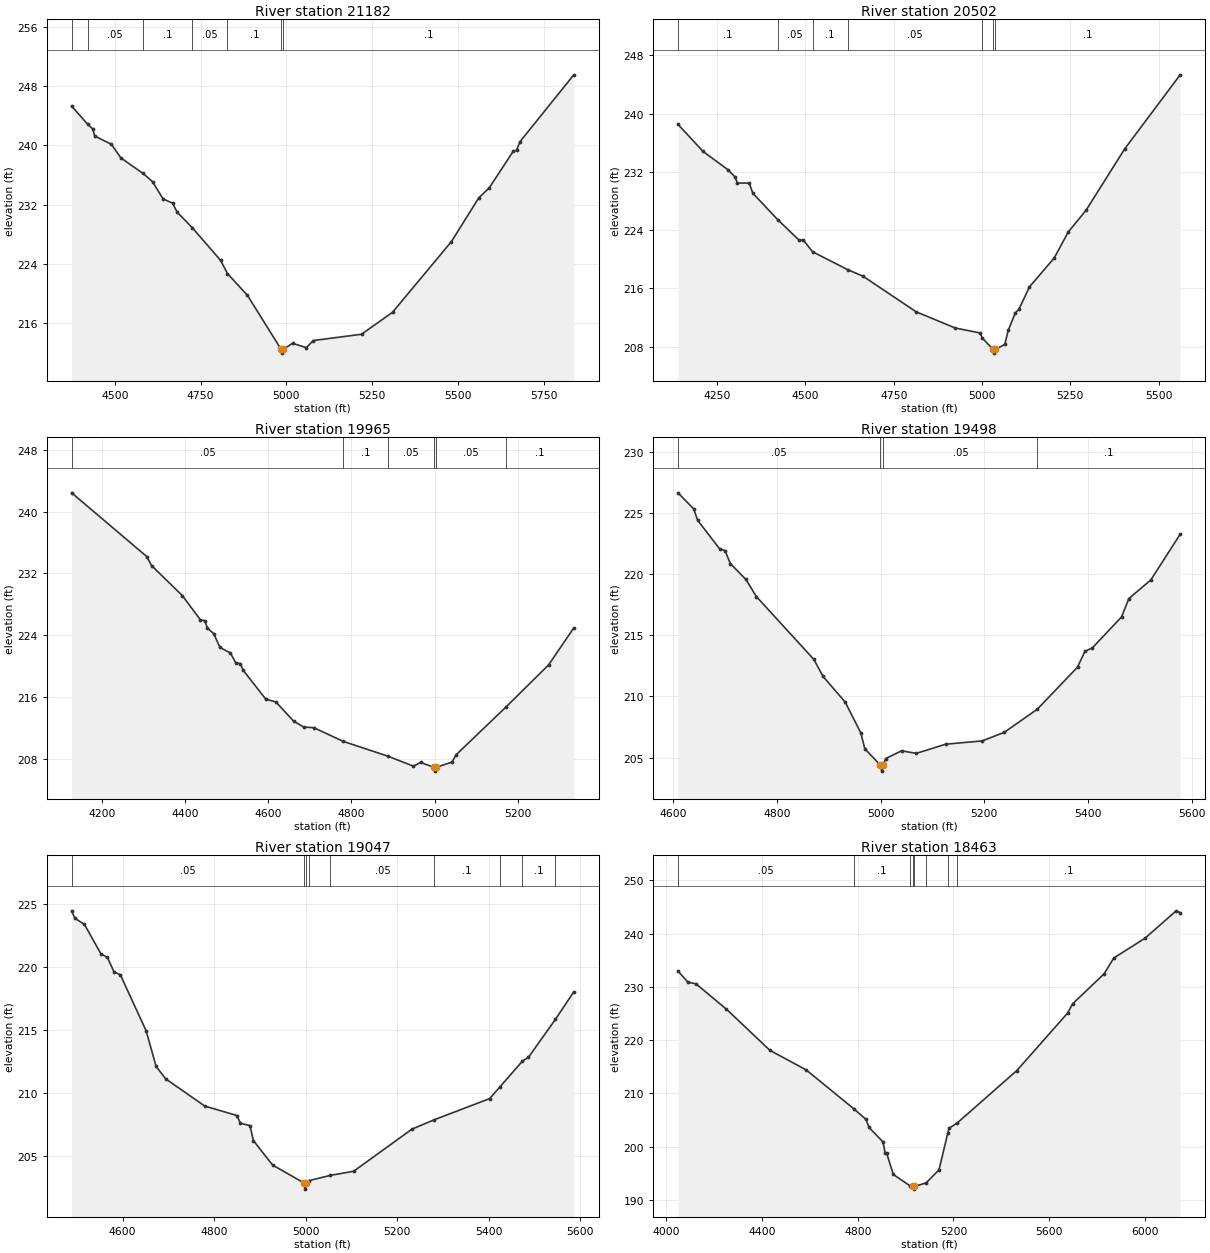
Type RM Length L Ch R = 1,21182,680,680,680
BEGIN DESCRIPTION:
UNT040 IN NURI 46.0
END DESCRIPTION:
XS GIS Cut Line= 4
      2280387.71     13265846.83      2280268.09     13265315.56
      2280233.37     13264972.68      2280285.35     13264400.84
#Sta/Elev= 30
  4374.3  245.32  4420.7  242.89  4435.8  242.23  4441.7  241.28  4490.1  240.16
  4517.8  238.32  4582.2  236.23  4610.0  235.11  4640.8  232.78  4668.3  232.21
  4681.8  230.99  4726.5  228.86  4808.3  224.48  4828.5  222.69  4886.8  219.74
  4984.9  212.44  4987.7  211.94  4990.9  212.44  5018.1  213.27  5058.3  212.68
  5078.4  213.64  5219.1  214.49  5309.5  217.46  5481.2  227.02  5560.5  232.90
  5591.7  234.30  5661.0  239.20  5671.0  239.36  5681.0  240.52  5837.7  249.55
#Mann=7,-1,0
  4374.3     0.1       0  4420.7    0.05       0  4582.2     0.1       0
  4726.5    0.05       0  4828.5     0.1       0  4984.9    0.07       0
  4990.9     0.1       0
Bank Sta=4984.9,4990.9
Exp/Cntr=0.3,0.1

Type RM Length L Ch R = 1,20502,537,537,537
BEGIN DESCRIPTION:
UNT040 IN NURI 45.0
END DESCRIPTION:
XS GIS Cut Line= 3
      2280744.22     13265797.35      2280831.02     13265007.40
      2280831.02     13264379.91
#Sta/Elev= 30
  4139.1  238.51  4210.0  234.80  4280.4  232.29  4300.6  231.30  4307.0  230.46
  4340.8  230.46  4350.9  229.06  4421.1  225.45  4481.6  222.63  4494.2  222.62
  4520.1  221.03  4619.2  218.58  4662.7  217.68  4813.6  212.78  4924.3  210.56
  4994.4  209.88  5000.7  209.20  5031.4  207.61  5034.1  207.11  5037.4  207.61
  5064.4  208.30  5074.4  210.24  5094.4  212.64  5104.4  213.11  5134.4  216.21
  5204.4  220.16  5244.4  223.75  5294.4  226.70  5404.4  235.17  5561.3  245.32
#Mann=7,-1,0
  4139.1     0.1       0  4421.1    0.05       0  4520.1     0.1       0
  4619.2    0.05       0  5000.7     0.1       0  5031.4    0.03       0
  5037.4     0.1       0
Bank Sta=5031.4,5037.4
Exp/Cntr=0.3,0.1

Type RM Length L Ch R = 1,19965,467,467,467
BEGIN DESCRIPTION:
UNT040 IN NURI 44.0
END DESCRIPTION:
XS GIS Cut Line= 3
      2281037.73     13265846.82      2281337.72     13265046.85
      2281287.72     13264696.87
#Sta/Elev= 30
  4126.8  242.44  4307.4  234.19  4319.0  233.02  4392.9  229.14  4436.5  225.99
  4447.2  225.88  4453.4  224.92  4468.5  224.20  4483.6  222.41  4508.6  221.70
  4521.9  220.40  4532.6  220.33  4538.8  219.50  4594.0  215.70  4618.0  215.36
  4660.8  212.86  4684.8  212.11  4709.7  212.01  4779.8  210.25  4887.3  208.33
  4949.1  207.03  4966.0  207.52  4998.4  206.89  5001.1  206.39  5004.4  206.89
  5041.8  207.56  5051.9  208.52  5170.9  214.66  5274.1  220.15  5334.7  224.94
#Mann=6,-1,0
  4126.8    0.05       0  4779.8     0.1       0  4887.3    0.05       0
  4998.4    0.03       0  5004.4    0.05       0  5170.9     0.1       0
Bank Sta=4998.4,5004.4
Exp/Cntr=0.3,0.1

Type RM Length L Ch R = 1,19498,451,451,451
BEGIN DESCRIPTION:
UNT040 IN NURI 43.0
END DESCRIPTION:
XS GIS Cut Line= 3
      2281837.72     13265496.88      2281787.72     13265096.85
      2281387.74     13264696.87
#Sta/Elev= 30
  4609.1  226.63  4639.4  225.31  4646.9  224.39  4689.7  222.03  4699.8  221.91
  4709.9  220.85  4740.1  219.55  4760.3  218.15  4871.1  213.02  4888.8  211.63
  4931.6  209.53  4961.8  207.01  4969.4  205.72  4999.2  204.39  5001.9  203.89
  5005.2  204.39  5009.7  204.92  5040.5  205.55  5068.8  205.34  5125.4  206.09
  5196.1  206.36  5238.5  207.06  5302.3  208.95  5379.9  212.39  5394.1  213.68
  5408.2  213.95  5464.8  216.49  5478.9  217.99  5521.4  219.52  5577.9  223.25
#Mann=4,-1,0
  4609.1    0.05       0  4999.2    0.03       0  5005.2    0.05       0
  5302.3     0.1       0
Bank Sta=4999.2,5005.2
Exp/Cntr=0.3,0.1

Type RM Length L Ch R = 1,19047,584,584,584
BEGIN DESCRIPTION:
UNT040 IN NURI 42.0
END DESCRIPTION:
XS GIS Cut Line= 3
      2282537.70     13265196.84      2282137.72     13264846.85
      2281737.69     13264446.83
#Sta/Elev= 30
  4488.5  224.42  4495.6  223.83  4516.5  223.34  4552.5  221.01  4566.8  220.72
  4581.0  219.58  4594.8  219.35  4651.2  214.91  4673.1  212.07  4694.0  211.09
  4779.4  208.93  4849.6  208.18  4857.2  207.57  4878.1  207.38  4885.7  206.19
  4927.4  204.26  4995.6  202.84  4998.4  202.34  5001.6  202.84  5007.7  203.02
  5053.7  203.43  5104.8  203.76  5232.1  207.10  5281.2  207.85  5401.8  209.52
  5423.6  210.42  5473.6  212.50  5486.7  212.80  5545.6  215.81  5585.7  217.99
#Mann=9,-1,0
  4488.5    0.05       0  4995.6    0.03       0  5001.6    0.05       0
  5007.7     0.1       0  5053.7    0.05       0  5281.2     0.1       0
  5423.6    0.05       0  5473.6     0.1       0  5545.6    0.05       0
Bank Sta=4995.6,5001.6
Exp/Cntr=0.3,0.1

Type RM Length L Ch R = 1,18463,92,92,92
BEGIN DESCRIPTION:
Mapping XS 9233d883
END DESCRIPTION:
XS GIS Cut Line= 4
      2282663.00     13265327.40      2282541.46     13264467.98
      2281959.87     13263860.34      2281571.02     13263834.42
#Sta/Elev= 30
  4048.7  232.97  4089.7  230.90  4123.6  230.59  4251.2  225.80  4433.0  218.07
  4584.5  214.40  4782.4  207.13  4834.1  205.11  4847.1  203.59  4905.2  200.87
  4914.7  198.73  4920.9  198.73  4948.3  194.76  5018.0  192.63  5030.2  192.50
  5033.0  192.00  5036.2  192.50  5085.6  193.17  5139.5  195.64  5176.5  202.59
  5181.7  203.44  5215.6  204.43  5464.7  214.28  5677.0  225.09  5698.1  226.83
  5830.1  232.49  5870.2  235.44  6000.5  239.15  6130.8  244.30  6147.5  243.97
#Mann=8,-1,0
  4048.7    0.05       0  4782.4     0.1       0  5018.0    0.05       0
  5030.2    0.07       0  5036.2    0.05       0  5085.6     0.1       0
  5176.5    0.05       0  5215.6     0.1       0
Bank Sta=5030.2,5036.2
Exp/Cntr=0.3,0.1

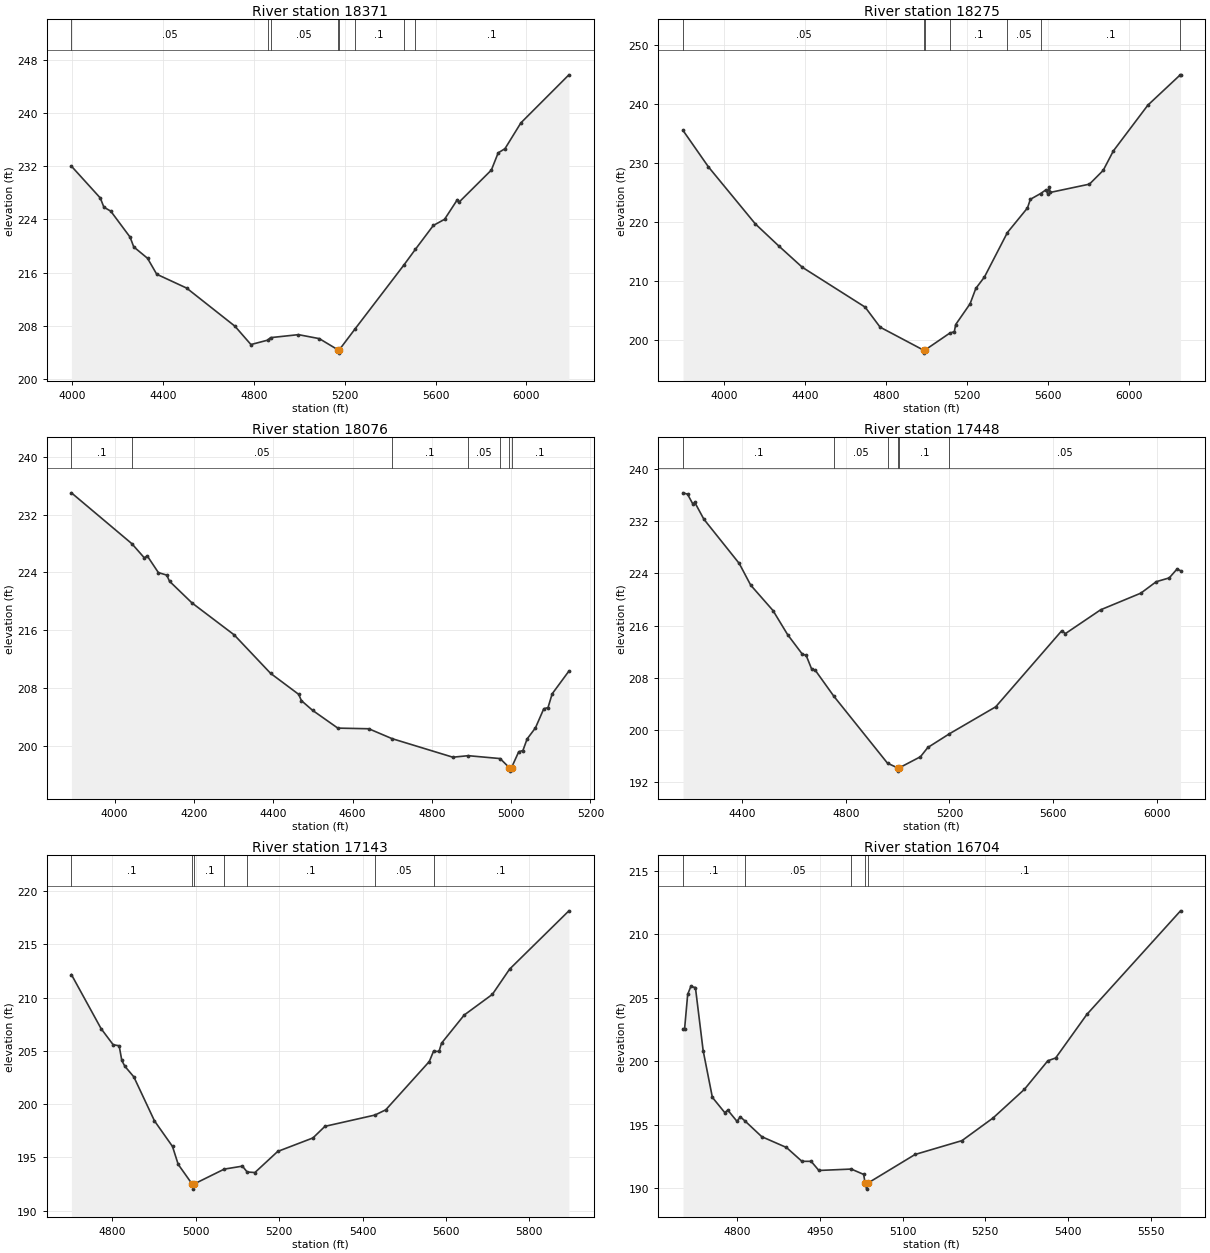
Type RM Length L Ch R = 1,18371,96,96,96
BEGIN DESCRIPTION:
UNT040 IN NURI 41.0
END DESCRIPTION:
XS GIS Cut Line= 4
      2282732.06     13265298.15      2282593.18     13264399.76
      2281959.50     13263748.72      2281586.20     13263744.38
#Sta/Elev= 30
  3996.0  232.01  4123.2  227.22  4139.0  225.84  4169.3  225.24  4254.4  221.33
  4270.5  219.86  4331.2  218.15  4371.7  215.75  4503.3  213.67  4716.2  207.93
  4786.6  205.17  4860.0  205.83  4872.9  206.21  4995.8  206.66  5087.8  206.06
  5169.7  204.38  5172.5  203.88  5175.7  204.38  5244.0  207.47  5459.2  217.09
  5511.3  219.52  5589.9  223.09  5639.3  224.01  5695.9  226.98  5703.1  226.59
  5845.4  231.42  5875.4  234.01  5905.4  234.64  5975.4  238.52  6186.9  245.75
#Mann=8,-1,0
  3996.0    0.05       0  4860.0     0.1       0  4872.9    0.05       0
  5169.7    0.03       0  5175.7    0.05       0  5244.0     0.1       0
  5459.2    0.05       0  5511.3     0.1       0
Bank Sta=5169.7,5175.7
Exp/Cntr=0.3,0.1

Type RM Length L Ch R = 1,18275,199,199,199
BEGIN DESCRIPTION:
Mapping XS ab239b4e
END DESCRIPTION:
XS GIS Cut Line= 4
      2282819.24     13265414.12      2282680.35     13264355.14
      2282037.99     13263678.05      2281586.59     13263695.41
#Sta/Elev= 30
  3798.8  235.51  3924.0  229.34  4155.3  219.68  4270.1  215.97  4386.6  212.34
  4696.8  205.58  4770.5  202.19  4984.9  198.29  4987.7  197.79  4990.9  198.29
  5113.1  201.16  5136.4  201.43  5143.3  202.64  5214.1  206.15  5242.4  208.75
  5284.8  210.68  5398.2  218.22  5497.2  222.39  5511.3  223.85  5562.0  224.83
  5589.0  225.48  5595.9  224.83  5603.2  225.91  5610.1  225.02  5802.8  226.42
  5870.5  228.75  5920.5  232.04  6090.7  239.80  6250.6  244.94  6251.9  244.94
#Mann=7,-1,0
  3798.8    0.05       0  4984.9    0.03       0  4990.9    0.05       0
  5113.1     0.1       0  5398.2    0.05       0  5562.0     0.1       0
  6250.6    0.05       0
Bank Sta=4984.9,4990.9
Exp/Cntr=0.3,0.1

Type RM Length L Ch R = 1,18076,628,628,628
BEGIN DESCRIPTION:
UNT040 IN NURI 40.0
END DESCRIPTION:
XS GIS Cut Line= 3
      2283487.70     13264846.83      2282687.72     13264096.85
      2282637.71     13263946.83
#Sta/Elev= 30
  3891.0  235.02  4043.5  227.97  4074.9  226.01  4082.2  226.29  4110.3  223.97
  4131.5  223.62  4138.4  222.77  4195.0  219.77  4301.5  215.34  4393.3  210.01
  4464.2  207.10  4471.0  206.23  4499.3  204.88  4562.9  202.42  4641.0  202.33
  4699.7  200.96  4853.0  198.39  4891.9  198.60  4972.2  198.20  4995.1  196.96
  4997.8  196.46  5001.1  196.96  5019.2  199.15  5029.7  199.31  5040.3  200.92
  5061.3  202.45  5082.4  205.11  5093.0  205.26  5103.5  207.17  5145.7  210.32
#Mann=7,-1,0
  3891.0     0.1       0  4043.5    0.05       0  4699.7     0.1       0
  4891.9    0.05       0  4972.2     0.1       0  4995.1    0.07       0
  5001.1     0.1       0
Bank Sta=4995.1,5001.1
Exp/Cntr=0.3,0.1

Type RM Length L Ch R = 1,17448,305,305,305
BEGIN DESCRIPTION:
UNT040 IN NURI 39.0
END DESCRIPTION:
XS GIS Cut Line= 4
      2283786.77     13264720.97      2283404.81     13264182.75
      2283040.23     13263779.10      2282324.12     13263731.36
#Sta/Elev= 30
  4171.1  236.39  4188.4  236.18  4209.7  234.62  4215.9  234.95  4251.5  232.34
  4388.1  225.54  4432.4  222.21  4518.5  218.31  4575.1  214.60  4631.7  211.61
  4646.4  211.44  4667.3  209.37  4682.1  209.12  4753.5  205.15  4960.8  194.86
  4999.9  194.14  5002.6  193.64  5005.9  194.14  5088.1  195.85  5116.5  197.27
  5200.1  199.38  5378.8  203.52  5633.7  215.20  5648.1  214.77  5784.0  218.42
  5939.4  220.98  5998.9  222.74  6049.0  223.32  6079.1  224.68  6092.7  224.43
#Mann=6,-1,0
  4171.1     0.1       0  4753.5    0.05       0  4960.8     0.1       0
  4999.9    0.07       0  5005.9     0.1       0  5200.1    0.05       0
Bank Sta=4999.9,5005.9
Exp/Cntr=0.3,0.1

Type RM Length L Ch R = 1,17143,439,439,439
BEGIN DESCRIPTION:
UNT040 IN NURI 38.0
END DESCRIPTION:
XS GIS Cut Line= 3
      2283737.73     13264146.86      2283537.72     13263896.85
      2283187.71     13263096.83
#Sta/Elev= 30
  4701.6  212.17  4772.8  207.09  4801.7  205.58  4816.1  205.48  4822.5  204.10
  4829.7  203.56  4851.3  202.56  4900.9  198.42  4944.1  196.02  4957.7  194.34
  4990.8  192.51  4993.5  192.01  4996.8  192.51  5068.2  193.89  5111.8  194.17
  5123.2  193.62  5141.8  193.57  5196.4  195.55  5281.0  196.82  5309.8  197.91
  5429.7  198.97  5455.6  199.46  5560.1  204.00  5570.2  204.96  5583.5  204.95
  5589.4  205.72  5643.9  208.37  5711.4  210.31  5752.7  212.68  5895.0  218.16
#Mann=7,-1,0
  4701.6     0.1       0  4990.8    0.07       0  4996.8     0.1       0
  5068.2    0.05       0  5123.2     0.1       0  5429.7    0.05       0
  5570.2     0.1       0
Bank Sta=4990.8,4996.8
Exp/Cntr=0.3,0.1

Type RM Length L Ch R = 1,16704,474,474,474
BEGIN DESCRIPTION:
UNT040 IN NURI 37.0
END DESCRIPTION:
XS GIS Cut Line= 3
      2283937.74     13263846.89      2283787.72     13263546.85
      2283387.75     13263146.88
#Sta/Elev= 30
  4702.5  202.55  4705.3  202.55  4710.9  205.26  4716.5  205.88  4724.9  205.80
  4738.9  200.83  4755.6  197.15  4778.0  195.95  4783.6  196.14  4800.4  195.25
  4806.0  195.62  4813.9  195.32  4845.1  194.05  4889.8  193.20  4917.8  192.11
  4934.5  192.11  4948.5  191.39  5007.2  191.50  5029.6  191.08  5032.2  190.42
  5034.9  189.92  5038.2  190.42  5122.8  192.65  5207.7  193.74  5264.2  195.53
  5320.8  197.78  5363.2  200.03  5377.4  200.25  5433.9  203.68  5603.6  211.84
#Mann=5,-1,0
  4702.5     0.1       0  4813.9    0.05       0  5007.2     0.1       0
  5032.2    0.03       0  5038.2     0.1       0
Bank Sta=5032.2,5038.2
Exp/Cntr=0.3,0.1

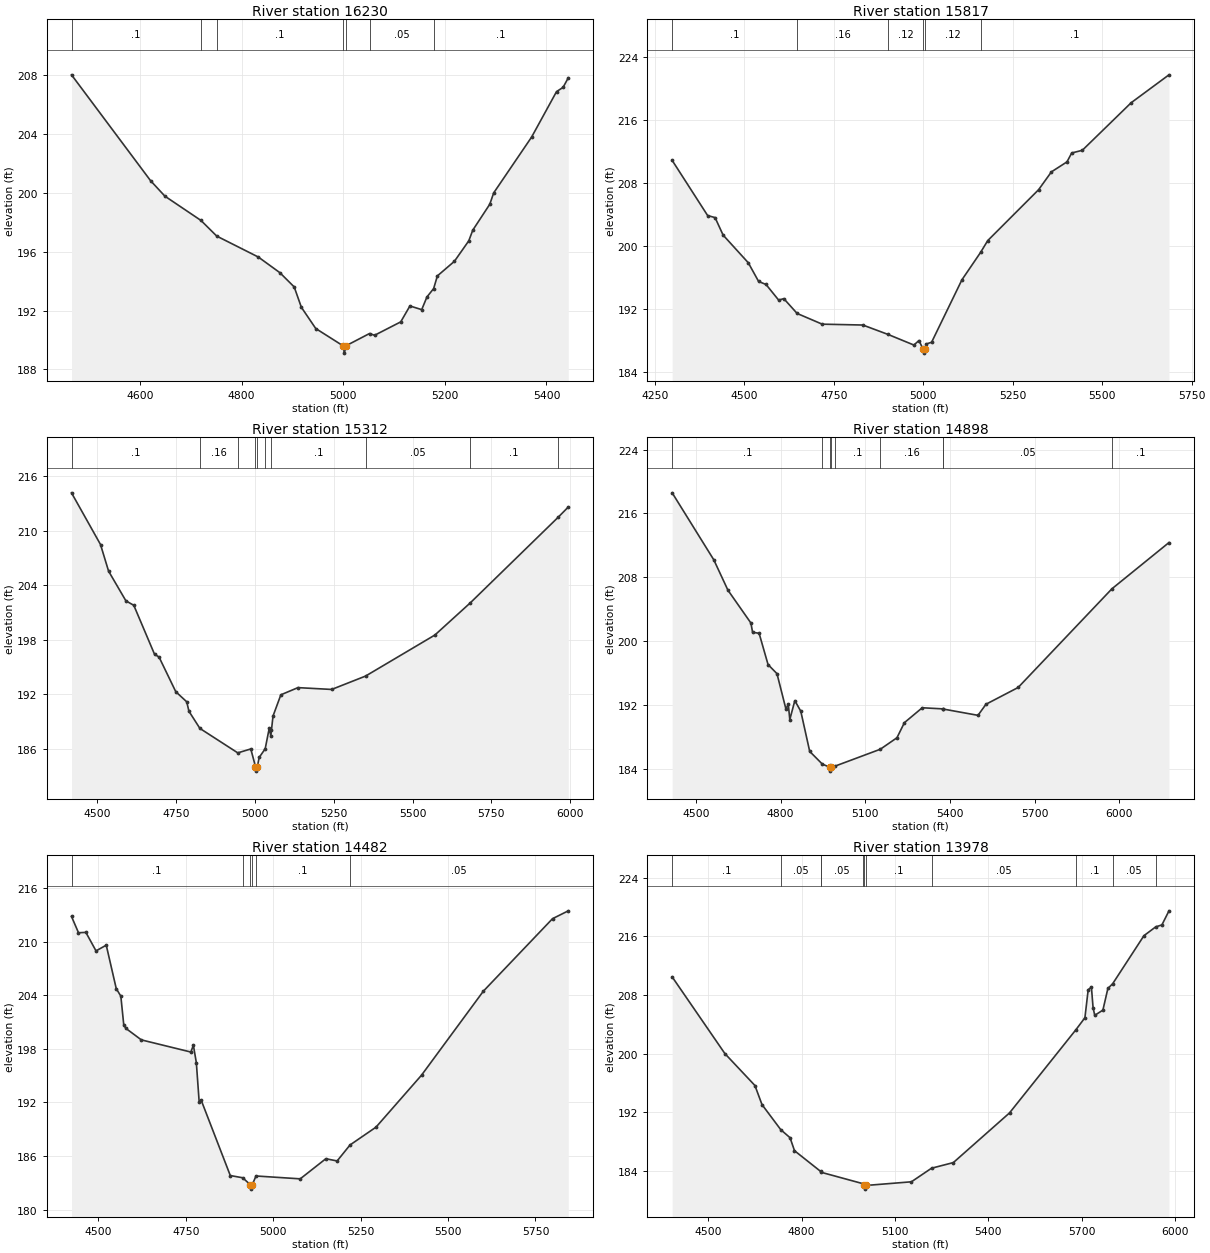
Type RM Length L Ch R = 1,16230,413,413,413
BEGIN DESCRIPTION:
UNT040 IN NURI 36.0
END DESCRIPTION:
XS GIS Cut Line= 3
      2284337.72     13263546.85      2283937.72     13263146.85
      2283537.71     13263046.85
#Sta/Elev= 30
  4465.0  207.99  4620.6  200.81  4648.8  199.76  4719.9  198.11  4750.9  197.05
  4832.7  195.63  4875.1  194.57  4903.4  193.60  4917.5  192.22  4945.8  190.78
  4999.4  189.61  5002.1  189.11  5005.4  189.61  5051.7  190.44  5061.6  190.32
  5113.1  191.23  5131.2  192.31  5154.4  192.06  5164.7  192.92  5177.9  193.49
  5185.3  194.35  5218.8  195.34  5247.1  196.73  5254.9  197.45  5288.4  199.21
  5296.1  199.98  5370.8  203.77  5419.8  206.85  5432.7  207.14  5443.0  207.79
#Mann=7,-1,0
  4465.0     0.1       0  4719.9    0.05       0  4750.9     0.1       0
  4999.4    0.07       0  5005.4     0.1       0  5051.7    0.05       0
  5177.9     0.1       0
Bank Sta=4999.4,5005.4
Exp/Cntr=0.3,0.1

Type RM Length L Ch R = 1,15817,505,505,505
BEGIN DESCRIPTION:
UNT040 IN NURI 35.0
END DESCRIPTION:
XS GIS Cut Line= 3
      2284605.13     13263378.57      2283973.73     13262589.97
      2283664.58     13262372.51
#Sta/Elev= 30
  4298.4  210.87  4397.5  203.86  4418.3  203.60  4440.7  201.38  4511.1  197.86
  4539.9  195.49  4560.7  195.10  4595.9  193.12  4610.4  193.30  4647.6  191.42
  4717.6  190.06  4831.2  189.95  4901.9  188.75  4973.7  187.41  4988.1  187.98
  4999.5  186.88  5002.3  186.38  5005.5  186.88  5008.9  187.55  5023.3  187.76
  5108.1  195.70  5160.2  199.18  5180.2  200.68  5322.4  207.15  5358.1  209.41
  5401.6  210.68  5414.8  211.81  5444.4  212.15  5581.1  218.20  5686.6  221.74
#Mann=6,-1,0
  4298.4     0.1       0  4647.6    0.16       0  4901.9    0.12       0
  4999.5    0.07       0  5005.5    0.12       0  5160.2     0.1       0
Bank Sta=4999.5,5005.5
Exp/Cntr=0.3,0.1

Type RM Length L Ch R = 1,15312,414,414,414
BEGIN DESCRIPTION:
UNT040 IN NURI 34.0
END DESCRIPTION:
XS GIS Cut Line= 4
      2284767.58     13263368.11      2284725.66     13263037.98
      2284610.38     13262686.91      2283921.36     13262149.84
#Sta/Elev= 30
  4418.0  214.17  4510.0  208.48  4535.6  205.55  4590.6  202.28  4615.6  201.79
  4681.4  196.40  4695.6  196.10  4748.8  192.28  4783.5  191.17  4790.5  190.13
  4825.3  188.24  4945.4  185.55  4986.7  185.98  5001.6  184.04  5004.3  183.54
  5007.6  184.04  5013.2  185.04  5032.4  186.00  5045.1  188.24  5050.3  187.43
  5052.3  188.06  5057.2  189.60  5082.1  191.94  5136.3  192.73  5243.2  192.53
  5350.7  194.00  5570.7  198.52  5683.0  202.06  5961.1  211.46  5993.9  212.61
#Mann=10,-1,0
  4418.0     0.1       0  4825.3    0.16       0  4945.4     0.1       0
  5001.6    0.07       0  5007.6     0.1       0  5032.4    0.16       0
  5052.3     0.1       0  5350.7    0.05       0  5683.0     0.1       0
  5961.1    0.16       0
Bank Sta=5001.6,5007.6
Exp/Cntr=0.3,0.1

Type RM Length L Ch R = 1,14898,416,416,416
BEGIN DESCRIPTION:
UNT040 IN NURI 33.0
END DESCRIPTION:
XS GIS Cut Line= 4
      2285433.06     13263027.52      2285265.37     13262804.81
      2284652.30     13262600.45      2284295.97     13261845.87
#Sta/Elev= 30
  4415.9  218.58  4563.4  210.18  4613.4  206.38  4694.7  202.27  4700.7  201.11
  4723.8  200.98  4755.5  197.06  4787.1  195.92  4818.7  191.50  4827.2  192.08
  4832.5  190.17  4850.3  192.54  4871.4  191.22  4903.0  186.18  4948.0  184.58
  4973.8  184.21  4976.6  183.71  4979.8  184.21  4993.1  184.34  5152.9  186.45
  5212.0  187.89  5238.3  189.78  5301.6  191.65  5374.4  191.51  5375.6  191.49
  5499.0  190.70  5527.3  192.09  5641.2  194.19  5973.5  206.56  6175.4  212.35
#Mann=9,-1,0
  4415.9     0.1       0  4948.0    0.16       0  4973.8    0.07       0
  4979.8    0.16       0  4993.1     0.1       0  5152.9    0.16       0
  5374.4     0.1       0  5375.6    0.05       0  5973.5     0.1       0
Bank Sta=4973.8,4979.8
Exp/Cntr=0.3,0.1

Type RM Length L Ch R = 1,14482,504,504,504
BEGIN DESCRIPTION:
UNT040 IN NURI 32.0
END DESCRIPTION:
XS GIS Cut Line= 4
      2285433.03     13262699.98      2285228.69     13262422.29
      2284688.98     13262147.20      2284356.25     13261814.47
#Sta/Elev= 30
  4422.8  212.80  4442.8  210.98  4463.9  211.02  4492.9  208.95  4522.2  209.59
  4550.8  204.73  4563.9  203.89  4572.3  200.67  4578.5  200.28  4622.5  199.00
  4764.2  197.64  4771.4  198.40  4779.9  196.45  4788.0  192.05  4793.6  192.27
  4877.0  183.83  4912.5  183.58  4934.0  182.81  4936.8  182.31  4940.0  182.81
  4950.5  183.78  5077.1  183.46  5150.3  185.71  5182.6  185.46  5219.6  187.25
  5293.8  189.24  5424.0  195.05  5600.8  204.44  5798.7  212.55  5843.9  213.43
#Mann=6,-1,0
  4422.8     0.1       0  4912.5    0.16       0  4934.0    0.07       0
  4940.0    0.16       0  4950.5     0.1       0  5219.6    0.05       0
Bank Sta=4934,4940
Exp/Cntr=0.3,0.1

Type RM Length L Ch R = 1,13978,381,381,381
BEGIN DESCRIPTION:
UNT040 IN NURI 31.0
END DESCRIPTION:
XS GIS Cut Line= 4
      2285565.93     13262513.80      2285405.33     13262175.24
      2285006.03     13261719.52      2284421.38     13261524.63
#Sta/Elev= 30
  4384.2  210.45  4553.7  199.99  4650.2  195.64  4672.9  193.04  4733.4  189.61
  4763.1  188.52  4777.4  186.75  4861.0  183.94  4862.8  183.81  4997.6  182.25
  5001.2  182.01  5004.0  181.51  5007.2  182.01  5153.2  182.51  5217.8  184.36
  5288.0  185.13  5468.5  191.90  5682.4  203.27  5710.9  204.88  5721.4  208.69
  5731.8  209.06  5737.1  206.27  5742.5  205.21  5768.7  205.92  5784.7  208.87
  5800.3  209.53  5900.6  216.07  5938.4  217.27  5958.4  217.54  5981.1  219.46
#Mann=11,-1,0
  4384.2     0.1       0  4733.4    0.05       0  4861.0     0.1       0
  4862.8    0.05       0  4997.6     0.1       0  5001.2    0.07       0
  5007.2     0.1       0  5217.8    0.05       0  5682.4     0.1       0
  5800.3    0.05       0  5938.4     0.1       0
Bank Sta=5001.2,5007.2
Exp/Cntr=0.3,0.1

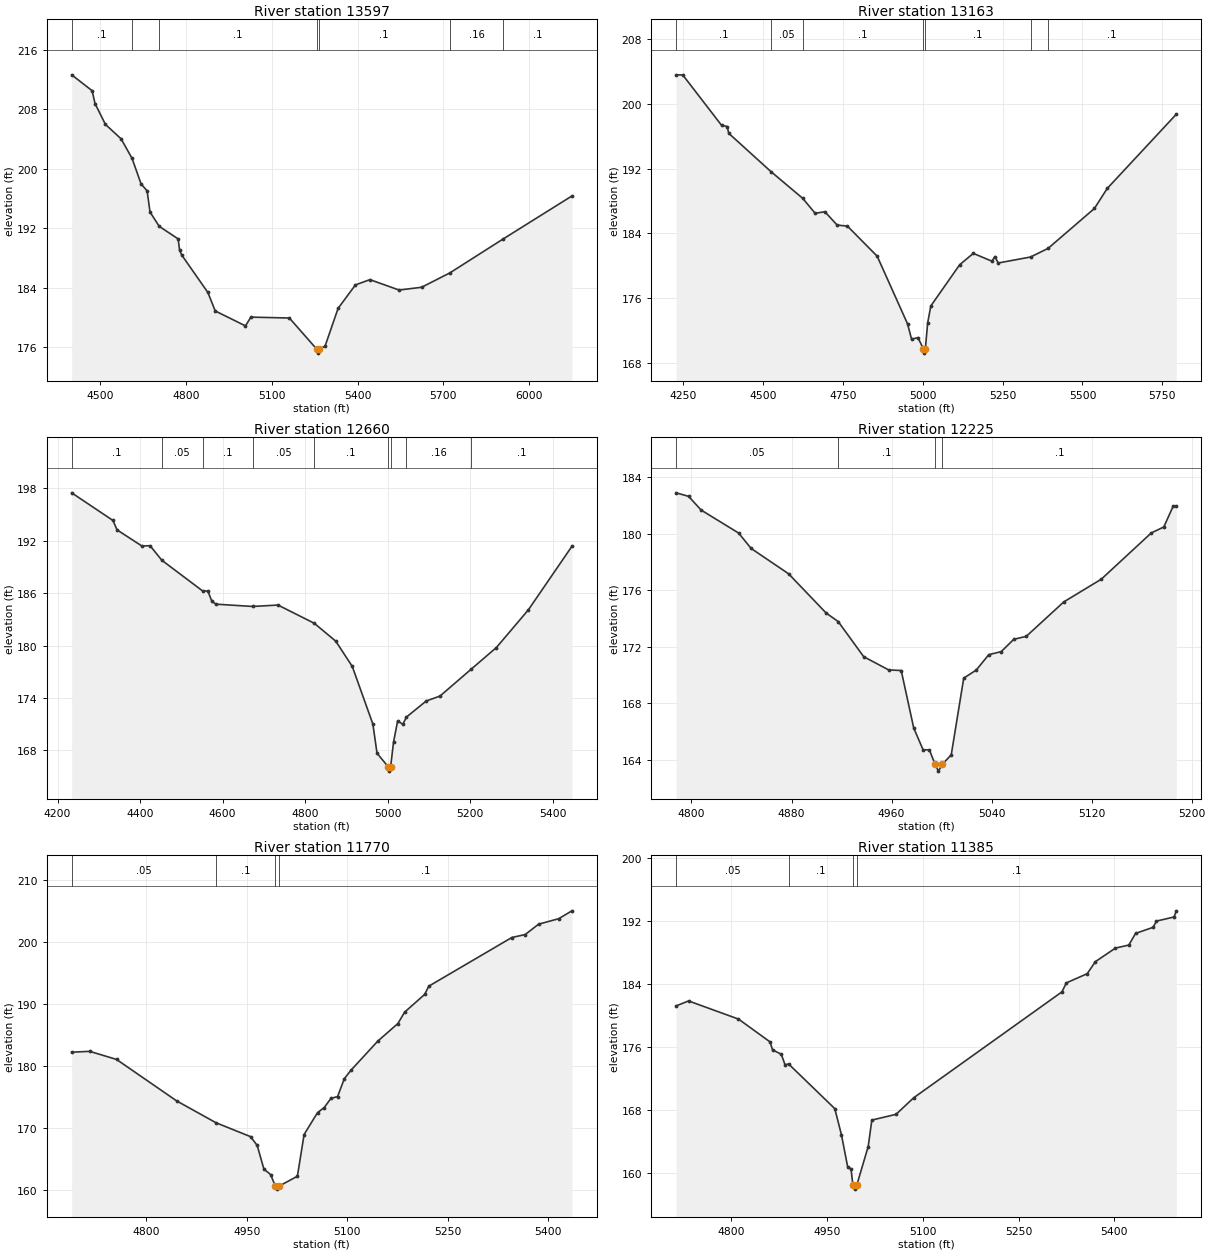
Type RM Length L Ch R = 1,13597,434,434,434
BEGIN DESCRIPTION:
UNT040 IN NURI 30.0
END DESCRIPTION:
XS GIS Cut Line= 3
      2285691.32     13262507.58      2285520.39     13261427.98
      2285551.86     13260771.49
#Sta/Elev= 30
  4399.3  212.65  4470.9  210.51  4481.0  208.78  4517.4  205.97  4572.2  204.03
  4610.5  201.40  4642.1  197.96  4663.3  197.02  4673.4  194.17  4705.6  192.24
  4771.8  190.55  4776.9  189.01  4784.8  188.35  4875.9  183.33  4901.6  180.84
  5007.5  178.83  5026.3  180.01  5161.1  179.89  5257.6  175.66  5260.4  175.16
  5263.6  175.66  5285.8  176.09  5331.5  181.19  5392.2  184.35  5442.9  185.06
  5544.8  183.66  5623.6  184.03  5722.3  185.96  5909.1  190.54  6149.6  196.33
#Mann=7,-1,0
  4399.3     0.1       0  4610.5    0.05       0  4705.6     0.1       0
  5257.6    0.07       0  5263.6     0.1       0  5722.3    0.16       0
  5909.1     0.1       0
Bank Sta=5257.6,5263.6
Exp/Cntr=0.3,0.1

Type RM Length L Ch R = 1,13163,503,503,503
BEGIN DESCRIPTION:
UNT040 IN NURI 29.0
END DESCRIPTION:
XS GIS Cut Line= 3
      2285898.24     13262507.62      2285974.72     13262006.02
      2285869.04     13260951.50
#Sta/Elev= 30
  4226.9  203.60  4247.9  203.58  4369.3  197.36  4386.9  197.21  4391.9  196.37
  4524.0  191.64  4623.4  188.34  4662.6  186.48  4693.0  186.68  4731.4  185.03
  4763.6  184.90  4856.9  181.18  4952.2  172.80  4964.6  170.92  4984.7  171.12
  5001.8  169.70  5004.6  169.20  5007.8  169.70  5014.9  172.90  5024.9  175.03
  5115.4  180.13  5158.1  181.53  5215.9  180.57  5225.9  181.13  5236.0  180.34
  5337.3  181.08  5392.1  182.14  5537.5  187.08  5577.7  189.56  5794.1  198.73
#Mann=7,-1,0
  4226.9     0.1       0  4524.0    0.05       0  4623.4     0.1       0
  5001.8    0.07       0  5007.8     0.1       0  5337.3    0.16       0
  5392.1     0.1       0
Bank Sta=5001.8,5007.8
Exp/Cntr=0.3,0.1

Type RM Length L Ch R = 1,12660,435,435,435
BEGIN DESCRIPTION:
UNT040 IN NURI 28.0
END DESCRIPTION:
XS GIS Cut Line= 3
      2286387.72     13262346.81      2286387.72     13261546.85
      2286287.71     13261146.82
#Sta/Elev= 30
  4234.3  197.47  4334.3  194.31  4344.3  193.23  4404.3  191.39  4424.3  191.42
  4452.7  189.76  4551.5  186.25  4564.3  186.23  4574.3  185.04  4584.3  184.73
  4672.9  184.47  4734.3  184.63  4822.1  182.55  4874.3  180.50  4914.3  177.61
  4964.3  171.01  4974.3  167.68  5001.3  166.13  5004.0  165.63  5007.3  166.13
  5014.3  168.94  5024.3  171.38  5036.8  170.99  5045.7  171.82  5093.5  173.65
  5127.0  174.22  5202.4  177.29  5263.6  179.77  5340.9  184.07  5446.6  191.35
#Mann=9,-1,0
  4234.3     0.1       0  4452.7    0.05       0  4551.5     0.1       0
  4672.9    0.05       0  4822.1     0.1       0  5001.3    0.07       0
  5007.3     0.1       0  5045.7    0.16       0  5202.4     0.1       0
Bank Sta=5001.3,5007.3
Exp/Cntr=0.3,0.1

Type RM Length L Ch R = 1,12225,455,455,455
BEGIN DESCRIPTION:
UNT040 IN NURI 27.0
END DESCRIPTION:
XS GIS Cut Line= 3
      2286737.72     13261546.86      2286737.72     13261346.85
      2286737.72     13261146.86
#Sta/Elev= 30
  4787.7  182.90  4797.7  182.65  4807.7  181.68  4837.7  180.05  4847.7  178.96
  4877.7  177.16  4907.7  174.38  4917.3  173.78  4937.7  171.29  4957.7  170.35
  4967.7  170.31  4977.7  166.24  4985.2  164.69  4990.2  164.69  4994.7  163.68
  4997.5  163.18  5000.7  163.68  5007.7  164.33  5017.7  169.77  5027.7  170.34
  5037.7  171.43  5047.7  171.65  5057.7  172.52  5067.7  172.73  5097.7  175.17
  5127.7  176.78  5167.7  180.06  5177.7  180.48  5185.2  181.96  5187.7  181.96
#Mann=4,-1,0
  4787.7    0.05       0  4917.3     0.1       0  4994.7    0.07       0
  5000.7     0.1       0
Bank Sta=4994.7,5000.7
Exp/Cntr=0.3,0.1

Type RM Length L Ch R = 1,11770,385,385,385
BEGIN DESCRIPTION:
UNT040 IN NURI 26.0
END DESCRIPTION:
XS GIS Cut Line= 2
      2287176.51     13261643.71      2287185.19     13260897.16
#Sta/Elev= 30
  4688.8  182.25  4715.7  182.39  4755.7  181.09  4845.7  174.39  4904.5  170.87
  4955.7  168.65  4965.7  167.23  4975.7  163.42  4985.7  162.54  4992.7  160.69
  4995.4  160.19  4998.7  160.69  5025.7  162.27  5035.7  168.99  5055.7  172.51
  5065.7  173.33  5075.7  174.80  5085.7  175.11  5095.7  177.98  5105.7  179.35
  5145.7  184.04  5175.7  186.87  5185.7  188.70  5215.7  191.57  5221.8  192.89
  5345.7  200.73  5365.7  201.21  5385.7  202.88  5415.7  203.76  5435.4  205.03
#Mann=4,-1,0
  4688.8    0.05       0  4904.5     0.1       0  4992.7    0.07       0
  4998.7     0.1       0
Bank Sta=4992.7,4998.7
Exp/Cntr=0.3,0.1

Type RM Length L Ch R = 1,11385,520,520,520
BEGIN DESCRIPTION:
UNT040 IN NURI 25.0
END DESCRIPTION:
XS GIS Cut Line= 3
      2287488.99     13261665.41      2287587.72     13261546.85
      2287402.46     13260945.74
#Sta/Elev= 30
  4713.7  181.22  4733.2  181.85  4811.4  179.55  4860.8  176.66  4864.7  175.65
  4878.4  175.09  4884.3  173.76  4889.9  173.86  4962.2  168.20  4972.6  164.89
  4982.3  160.85  4987.6  160.56  4990.6  158.50  4993.3  158.00  4996.6  158.50
  5014.5  163.40  5020.2  166.75  5058.1  167.48  5085.6  169.57  5317.9  183.00
  5324.8  184.14  5357.4  185.30  5370.3  186.83  5401.7  188.55  5422.6  188.93
  5433.2  190.41  5460.7  191.18  5465.9  191.97  5493.4  192.49  5497.0  193.27
#Mann=4,-1,0
  4713.7    0.05       0  4889.9     0.1       0  4990.6    0.07       0
  4996.6     0.1       0
Bank Sta=4990.6,4996.6
Exp/Cntr=0.3,0.1