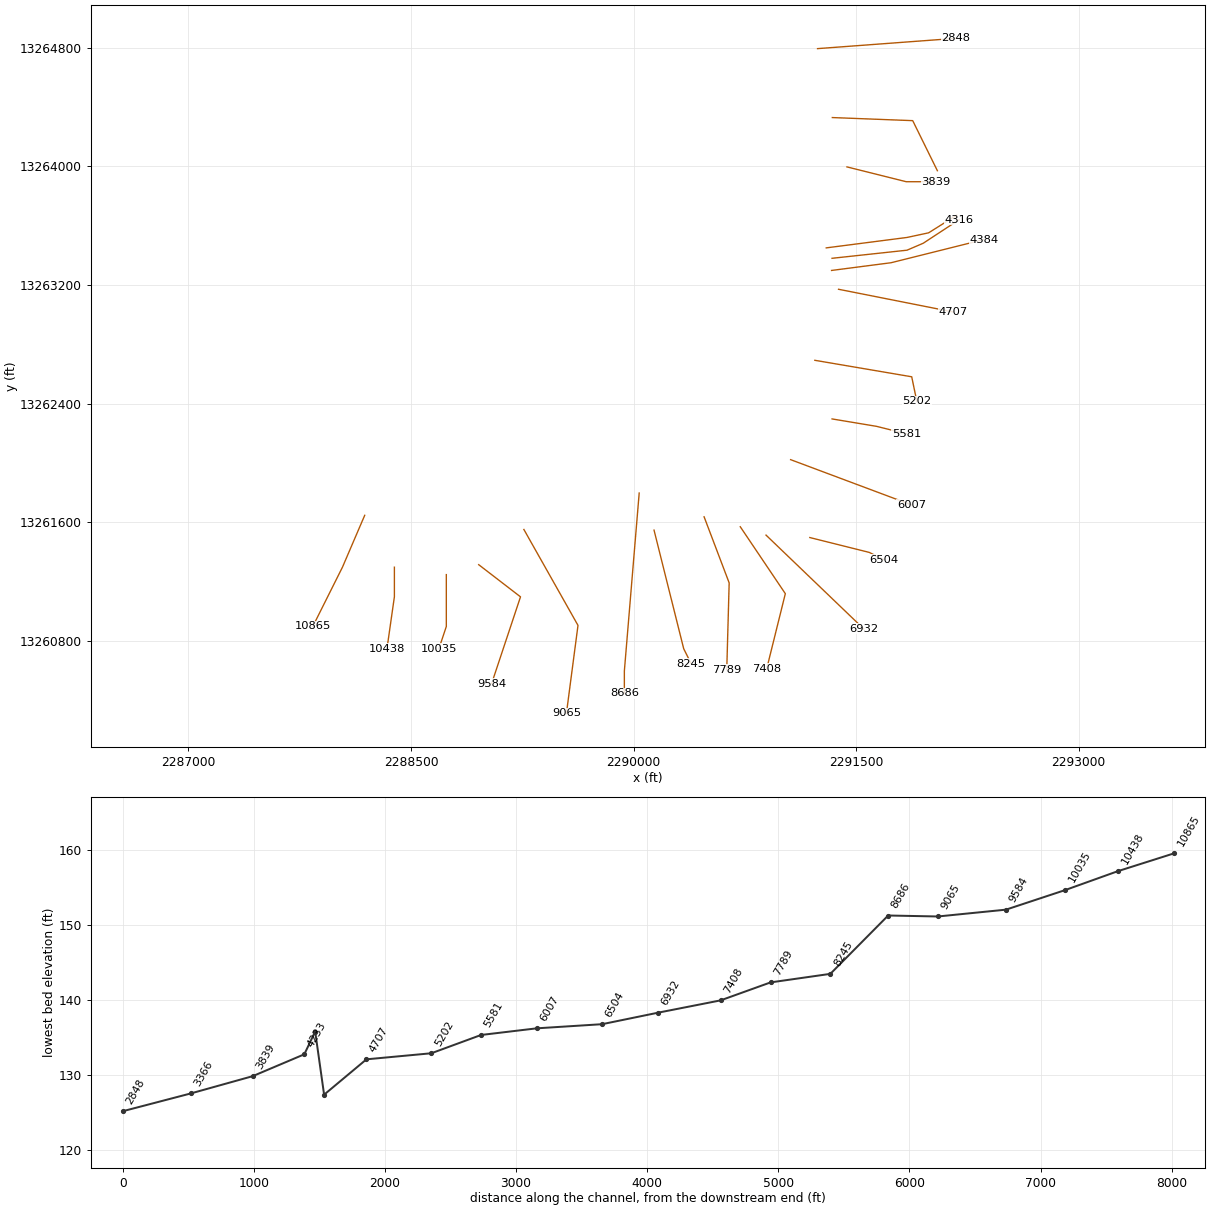
HEC-RAS study UNT040 IN NURI.prj: UNT040 IN NURI Base Level Engineering

--- UNT040 IN NURI.g01 (geometry) --- (continued)

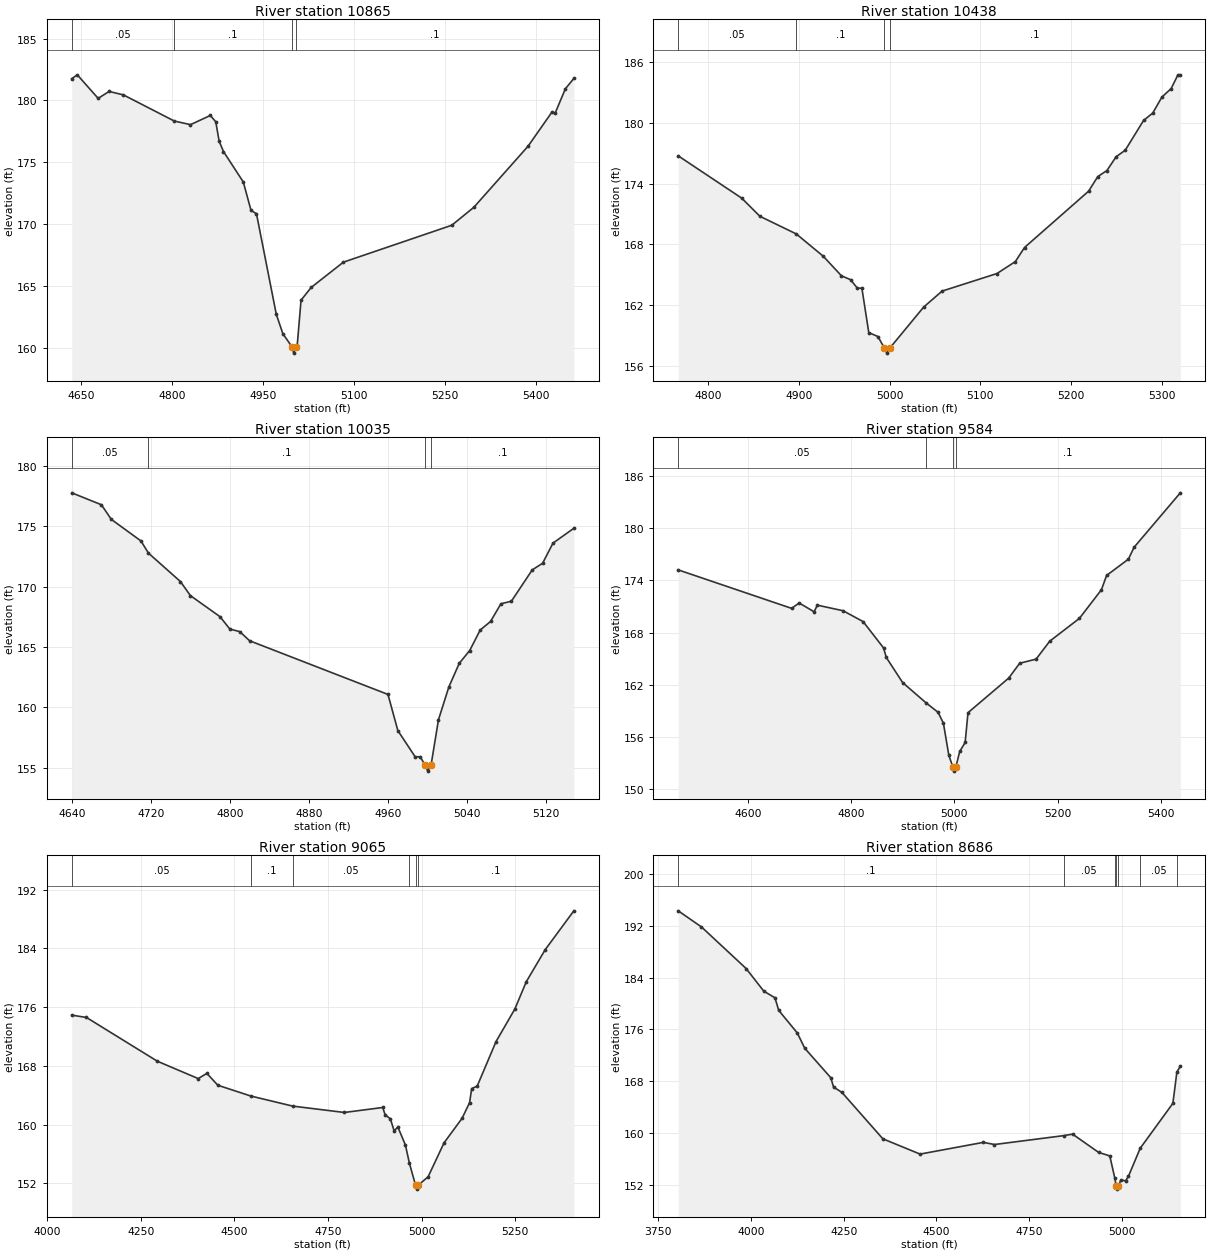
Type RM Length L Ch R = 1,10865,427,427,427
BEGIN DESCRIPTION:
UNT040 IN NURI 24.0
END DESCRIPTION:
XS GIS Cut Line= 3
      2288187.72     13261646.84      2288037.72     13261296.85
      2287837.72     13260896.84
#Sta/Elev= 30
  4634.1  181.76  4643.2  182.07  4677.6  180.17  4695.7  180.73  4719.3  180.45
  4803.2  178.34  4829.9  178.05  4862.6  178.79  4871.6  178.28  4877.1  176.72
  4884.3  175.88  4917.0  173.42  4929.7  171.13  4938.7  170.86  4971.4  162.74
  4982.2  161.18  4997.4  160.11  5000.1  159.61  5003.4  160.11  5005.8  160.17
  5012.2  163.88  5028.9  164.91  5082.0  166.95  5260.8  169.93  5297.2  171.38
  5386.6  176.31  5425.8  179.05  5431.3  178.98  5448.1  180.94  5462.1  181.78
#Mann=4,-1,0
  4634.1    0.05       0  4803.2     0.1       0  4997.4    0.07       0
  5003.4     0.1       0
Bank Sta=4997.4,5003.4
Exp/Cntr=0.3,0.1

Type RM Length L Ch R = 1,10438,403,403,403
BEGIN DESCRIPTION:
UNT040 IN NURI 23.0
END DESCRIPTION:
XS GIS Cut Line= 3
      2288387.72     13261296.85      2288387.72     13261096.85
      2288337.71     13260746.81
#Sta/Elev= 30
  4767.0  176.74  4837.0  172.56  4857.0  170.77  4897.2  169.02  4927.0  166.81
  4947.0  164.88  4957.0  164.50  4964.5  163.66  4969.5  163.66  4977.1  159.27
  4987.2  158.88  4994.3  157.74  4997.1  157.24  5000.3  157.74  5037.7  161.80
  5057.9  163.37  5118.5  165.11  5138.7  166.29  5148.8  167.68  5219.5  173.25
  5229.6  174.69  5239.7  175.29  5249.8  176.65  5259.9  177.30  5280.1  180.24
  5290.2  180.97  5300.3  182.55  5310.5  183.39  5318.0  184.75  5320.6  184.75
#Mann=4,-1,0
  4767.0    0.05       0  4897.2     0.1       0  4994.3    0.07       0
  5000.3     0.1       0
Bank Sta=4994.3,5000.3
Exp/Cntr=0.3,0.1

Type RM Length L Ch R = 1,10035,451,451,451
BEGIN DESCRIPTION:
UNT040 IN NURI 22.0
END DESCRIPTION:
XS GIS Cut Line= 3
      2288737.72     13261246.87      2288737.72     13260896.85
      2288687.73     13260746.88
#Sta/Elev= 30
  4640.0  177.79  4670.0  176.80  4680.0  175.59  4710.0  173.80  4717.6  172.79
  4750.0  170.43  4760.0  169.27  4790.0  167.52  4800.0  166.49  4810.0  166.28
  4820.0  165.52  4960.0  161.07  4970.0  158.07  4987.5  155.90  4992.6  155.90
  4997.6  155.21  5000.3  154.71  5003.6  155.21  5011.1  158.97  5021.6  161.69
  5032.2  163.66  5042.7  164.71  5053.3  166.41  5063.8  167.12  5074.3  168.59
  5084.9  168.80  5106.0  171.40  5116.5  171.95  5127.0  173.62  5148.1  174.85
#Mann=4,-1,0
  4640.0    0.05       0  4717.6     0.1       0  4997.6    0.07       0
  5003.6     0.1       0
Bank Sta=4997.6,5003.6
Exp/Cntr=0.3,0.1

Type RM Length L Ch R = 1,9584,519,519,519
BEGIN DESCRIPTION:
UNT040 IN NURI 21.0
END DESCRIPTION:
XS GIS Cut Line= 3
      2288956.02     13261313.83      2289237.72     13261096.85
      2289042.99     13260511.36
#Sta/Elev= 30
  4465.2  175.21  4684.9  170.79  4699.4  171.41  4728.4  170.40  4734.7  171.16
  4784.5  170.52  4823.4  169.27  4862.9  166.25  4868.3  165.15  4899.9  162.27
  4945.5  159.93  4968.5  158.86  4978.9  157.60  4989.4  153.91  4997.1  152.60
  4999.9  152.10  5003.1  152.60  5010.5  154.36  5021.0  155.39  5026.5  158.81
  5105.3  162.78  5126.7  164.49  5158.4  164.96  5184.8  167.02  5242.3  169.64
  5285.0  172.93  5295.0  174.57  5337.2  176.44  5348.3  177.81  5437.8  184.06
#Mann=4,-1,0
  4465.2    0.05       0  4945.5     0.1       0  4997.1    0.07       0
  5003.1     0.1       0
Bank Sta=4997.1,5003.1
Exp/Cntr=0.3,0.1

Type RM Length L Ch R = 1,9065,379,379,379
BEGIN DESCRIPTION:
UNT040 IN NURI 20.0
END DESCRIPTION:
XS GIS Cut Line= 3
      2289260.60     13261551.14      2289625.21     13260904.40
      2289547.22     13260310.83
#Sta/Elev= 30
  4065.7  174.91  4105.0  174.59  4294.2  168.63  4403.5  166.26  4426.5  166.97
  4456.0  165.35  4544.1  163.88  4655.6  162.51  4793.8  161.64  4896.4  162.32
  4902.7  161.31  4916.6  160.79  4926.7  159.14  4936.8  159.65  4956.9  157.20
  4967.7  154.70  4984.2  151.69  4987.0  151.19  4990.2  151.69  5017.5  152.87
  5060.2  157.51  5108.2  160.84  5128.4  162.99  5133.9  164.90  5148.6  165.23
  5199.0  171.31  5249.4  175.76  5279.7  179.46  5330.1  183.82  5406.8  189.13
#Mann=6,-1,0
  4065.7    0.05       0  4544.1     0.1       0  4655.6    0.05       0
  4967.7     0.1       0  4984.2    0.07       0  4990.2     0.1       0
Bank Sta=4984.2,4990.2
Exp/Cntr=0.3,0.1

Type RM Length L Ch R = 1,8686,441,441,441
BEGIN DESCRIPTION:
UNT040 IN NURI 19.0
END DESCRIPTION:
XS GIS Cut Line= 3
      2290037.72     13261796.87      2289937.72     13260596.85
      2289937.72     13260446.83
#Sta/Elev= 30
  3803.7  194.30  3866.4  191.81  3986.8  185.39  4034.5  181.89  4064.6  180.87
  4074.7  178.93  4124.8  175.44  4144.9  173.08  4215.1  168.53  4222.7  167.08
  4245.2  166.26  4355.6  159.09  4456.0  156.73  4626.6  158.54  4656.7  158.21
  4843.1  159.58  4867.4  159.81  4937.6  156.99  4967.7  156.45  4981.4  152.98
  4984.8  151.82  4987.6  151.32  4990.8  151.82  4997.8  152.76  5010.4  152.59
  5017.9  153.29  5049.8  157.64  5137.9  164.57  5148.6  169.39  5157.9  170.31
#Mann=7,-1,0
  3803.7     0.1       0  4843.1    0.05       0  4981.4     0.1       0
  4984.8    0.07       0  4990.8     0.1       0  5049.8    0.05       0
  5148.6     0.1       0
Bank Sta=4984.8,4990.8
Exp/Cntr=0.3,0.1

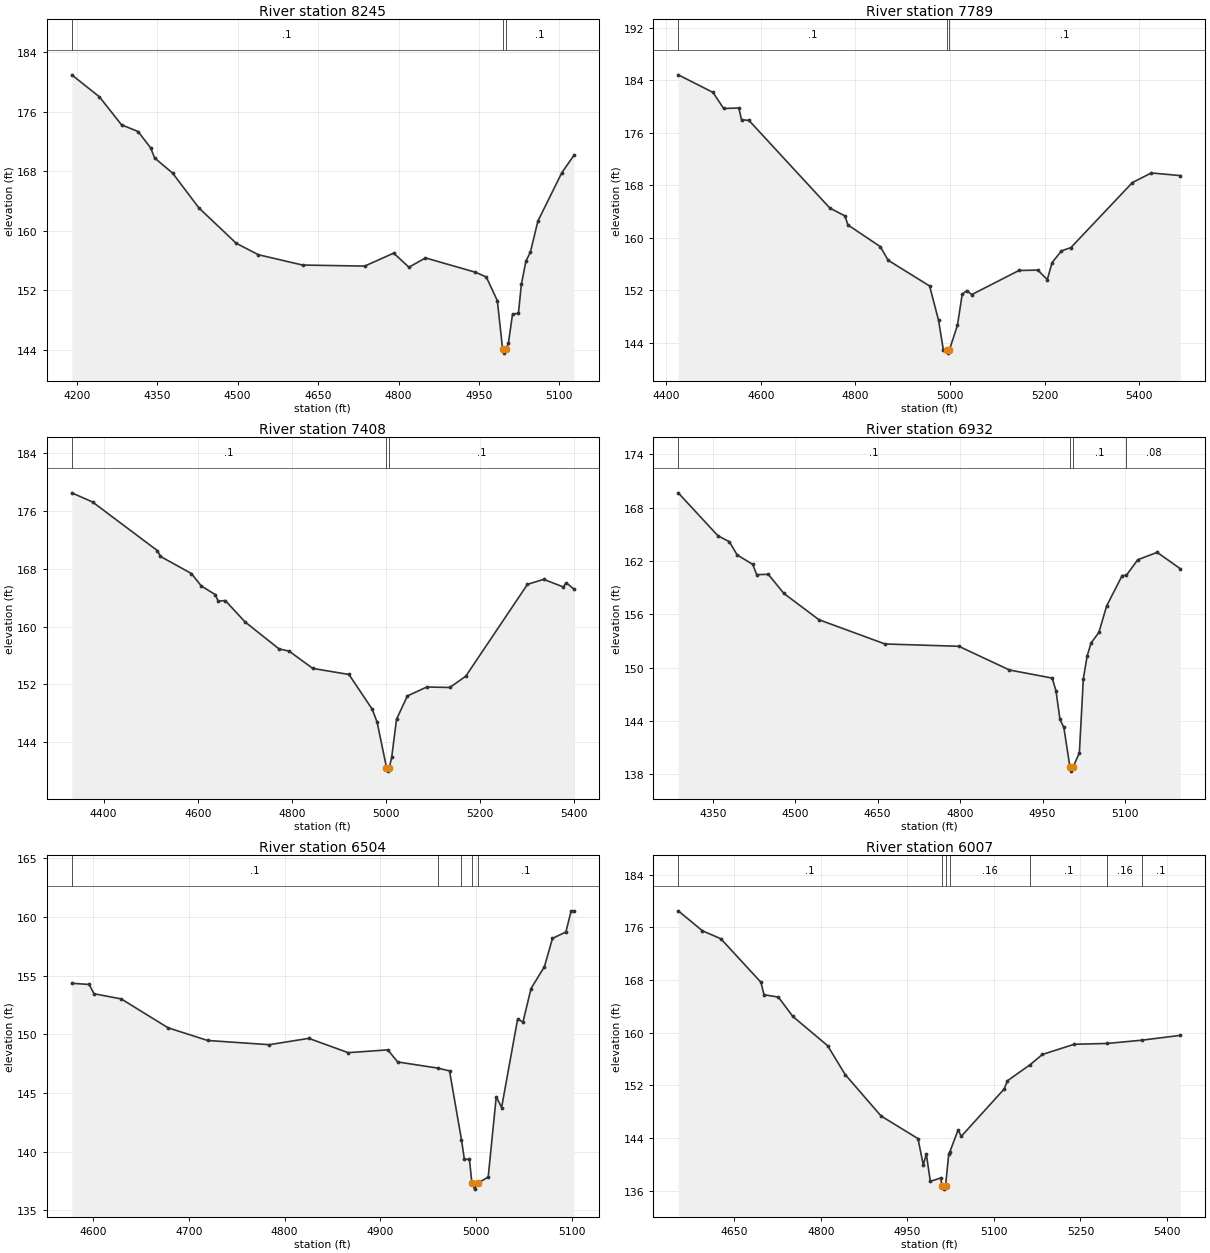
Type RM Length L Ch R = 1,8245,456,456,456
BEGIN DESCRIPTION:
UNT040 IN NURI 18.0
END DESCRIPTION:
XS GIS Cut Line= 3
      2290137.72     13261546.87      2290337.72     13260746.85
      2290387.70     13260646.89
#Sta/Elev= 30
  4190.6  180.94  4242.2  177.98  4283.4  174.22  4314.3  173.32  4337.5  171.14
  4345.2  169.76  4378.7  167.73  4427.7  163.05  4497.3  158.30  4538.5  156.76
  4621.0  155.37  4736.9  155.23  4791.0  156.97  4819.4  155.08  4850.3  156.33
  4943.1  154.41  4963.7  153.77  4984.3  150.58  4994.2  144.03  4997.0  143.53
  5000.2  144.03  5004.9  144.86  5012.7  148.78  5023.6  148.88  5029.2  152.79
  5037.6  155.89  5046.0  157.12  5060.0  161.29  5104.7  167.80  5127.0  170.10
#Mann=3,-1,0
  4190.6     0.1       0  4994.2    0.07       0  5000.2     0.1       0
Bank Sta=4994.2,5000.2
Exp/Cntr=0.3,0.1

Type RM Length L Ch R = 1,7789,381,381,381
BEGIN DESCRIPTION:
UNT040 IN NURI 17.0
END DESCRIPTION:
XS GIS Cut Line= 3
      2290475.12     13261636.75      2290644.14     13261190.89
      2290627.90     13260605.44
#Sta/Elev= 30
  4424.9  184.79  4498.5  182.11  4521.0  179.66  4553.1  179.74  4558.8  177.95
  4574.5  177.85  4745.6  164.50  4777.7  163.29  4784.0  161.92  4852.6  158.61
  4869.1  156.54  4956.8  152.62  4975.8  147.39  4985.8  142.93  4992.8  142.89
  4995.5  142.39  4998.8  142.89  5015.8  146.64  5025.8  151.35  5035.8  151.93
  5045.8  151.30  5145.9  154.98  5185.9  155.04  5205.9  153.59  5215.9  156.17
  5235.9  157.97  5255.9  158.47  5385.9  168.37  5426.0  169.84  5487.4  169.44
#Mann=3,-1,0
  4424.9     0.1       0  4992.8    0.07       0  4998.8     0.1       0
Bank Sta=4992.8,4998.8
Exp/Cntr=0.3,0.1

Type RM Length L Ch R = 1,7408,476,476,476
BEGIN DESCRIPTION:
UNT040 IN NURI 16.0
END DESCRIPTION:
XS GIS Cut Line= 3
      2290718.85     13261569.75      2291022.69     13261118.34
      2290896.99     13260611.22
#Sta/Elev= 30
  4332.2  178.52  4376.4  177.25  4514.3  170.51  4520.4  169.72  4586.3  167.35
  4607.3  165.63  4637.0  164.43  4643.3  163.51  4658.3  163.61  4700.3  160.65
  4772.3  156.92  4793.7  156.61  4844.3  154.21  4921.0  153.37  4970.6  148.55
  4980.9  146.76  5000.8  140.49  5003.5  139.99  5006.8  140.49  5011.8  141.88
  5022.1  147.17  5045.2  150.40  5086.5  151.64  5135.4  151.57  5169.3  153.14
  5300.3  165.85  5334.9  166.54  5376.3  165.49  5382.7  166.07  5398.8  165.20
#Mann=3,-1,0
  4332.2     0.1       0  5000.8    0.07       0  5006.8     0.1       0
Bank Sta=5000.8,5006.8
Exp/Cntr=0.3,0.1

Type RM Length L Ch R = 1,6932,428,428,428
BEGIN DESCRIPTION:
UNT040 IN NURI 15.0
END DESCRIPTION:
XS GIS Cut Line= 2
      2290892.47     13261513.30      2291551.07     13260880.70
#Sta/Elev= 30
  4287.3  169.67  4359.3  164.85  4380.4  164.16  4394.5  162.68  4422.8  161.62
  4430.0  160.46  4451.1  160.50  4479.4  158.35  4543.2  155.39  4663.4  152.66
  4797.7  152.40  4889.8  149.73  4967.5  148.82  4974.4  147.38  4981.6  144.17
  4988.6  143.28  4999.7  138.85  5002.5  138.35  5005.7  138.85  5016.9  140.40
  5024.1  148.73  5031.0  151.30  5038.2  152.77  5052.4  153.96  5066.5  156.94
  5094.8  160.36  5102.4  160.39  5123.1  162.14  5158.4  162.97  5200.5  161.13
#Mann=4,-1,0
  4287.3     0.1       0  4999.7    0.07       0  5005.7     0.1       0
  5102.4    0.08       0
Bank Sta=4999.7,5005.7
Exp/Cntr=0.3,0.1

Type RM Length L Ch R = 1,6504,497,497,497
BEGIN DESCRIPTION:
UNT040 IN NURI 14.0
END DESCRIPTION:
XS GIS Cut Line= 3
      2291187.70     13261496.86      2291587.72     13261396.85
      2291687.69     13261346.87
#Sta/Elev= 30
  4577.8  154.34  4595.9  154.24  4601.0  153.45  4629.4  153.01  4678.3  150.55
  4719.6  149.47  4784.0  149.11  4825.2  149.65  4866.4  148.43  4907.7  148.67
  4918.0  147.64  4959.6  147.12  4972.1  146.88  4984.6  141.02  4987.6  139.35
  4992.9  139.35  4995.5  137.31  4998.3  136.81  5001.5  137.31  5012.5  137.84
  5020.9  144.68  5026.5  143.76  5043.2  151.29  5048.8  151.04  5057.2  153.89
  5071.2  155.76  5079.6  158.16  5093.6  158.71  5099.1  160.51  5101.9  160.51
#Mann=5,-1,0
  4577.8     0.1       0  4959.6    0.16       0  4984.6     0.1       0
  4995.5    0.07       0  5001.5     0.1       0
Bank Sta=4995.5,5001.5
Exp/Cntr=0.3,0.1

Type RM Length L Ch R = 1,6007,426,426,426
BEGIN DESCRIPTION:
UNT040 IN NURI 13.0
END DESCRIPTION:
XS GIS Cut Line= 2
      2291058.49     13262022.14      2291873.61     13261716.91
#Sta/Elev= 30
  4552.7  178.52  4594.6  175.49  4626.6  174.28  4696.1  167.67  4701.4  165.78
  4726.3  165.42  4751.3  162.49  4811.8  158.03  4842.1  153.66  4904.3  147.37
  4968.3  143.93  4977.5  139.94  4982.8  141.60  4989.7  137.43  5007.7  137.96
  5010.1  136.76  5012.8  136.26  5016.1  136.76  5021.7  141.61  5023.4  141.89
  5038.0  145.27  5043.3  144.27  5117.8  151.47  5123.5  152.72  5162.8  155.16
  5184.0  156.71  5239.3  158.26  5296.5  158.38  5356.8  158.88  5423.1  159.61
#Mann=7,-1,0
  4552.7     0.1       0  5010.1    0.07       0  5016.1     0.1       0
  5023.4    0.16       0  5162.8     0.1       0  5296.5    0.16       0
  5356.8     0.1       0
Bank Sta=5010.1,5016.1
Exp/Cntr=0.3,0.1

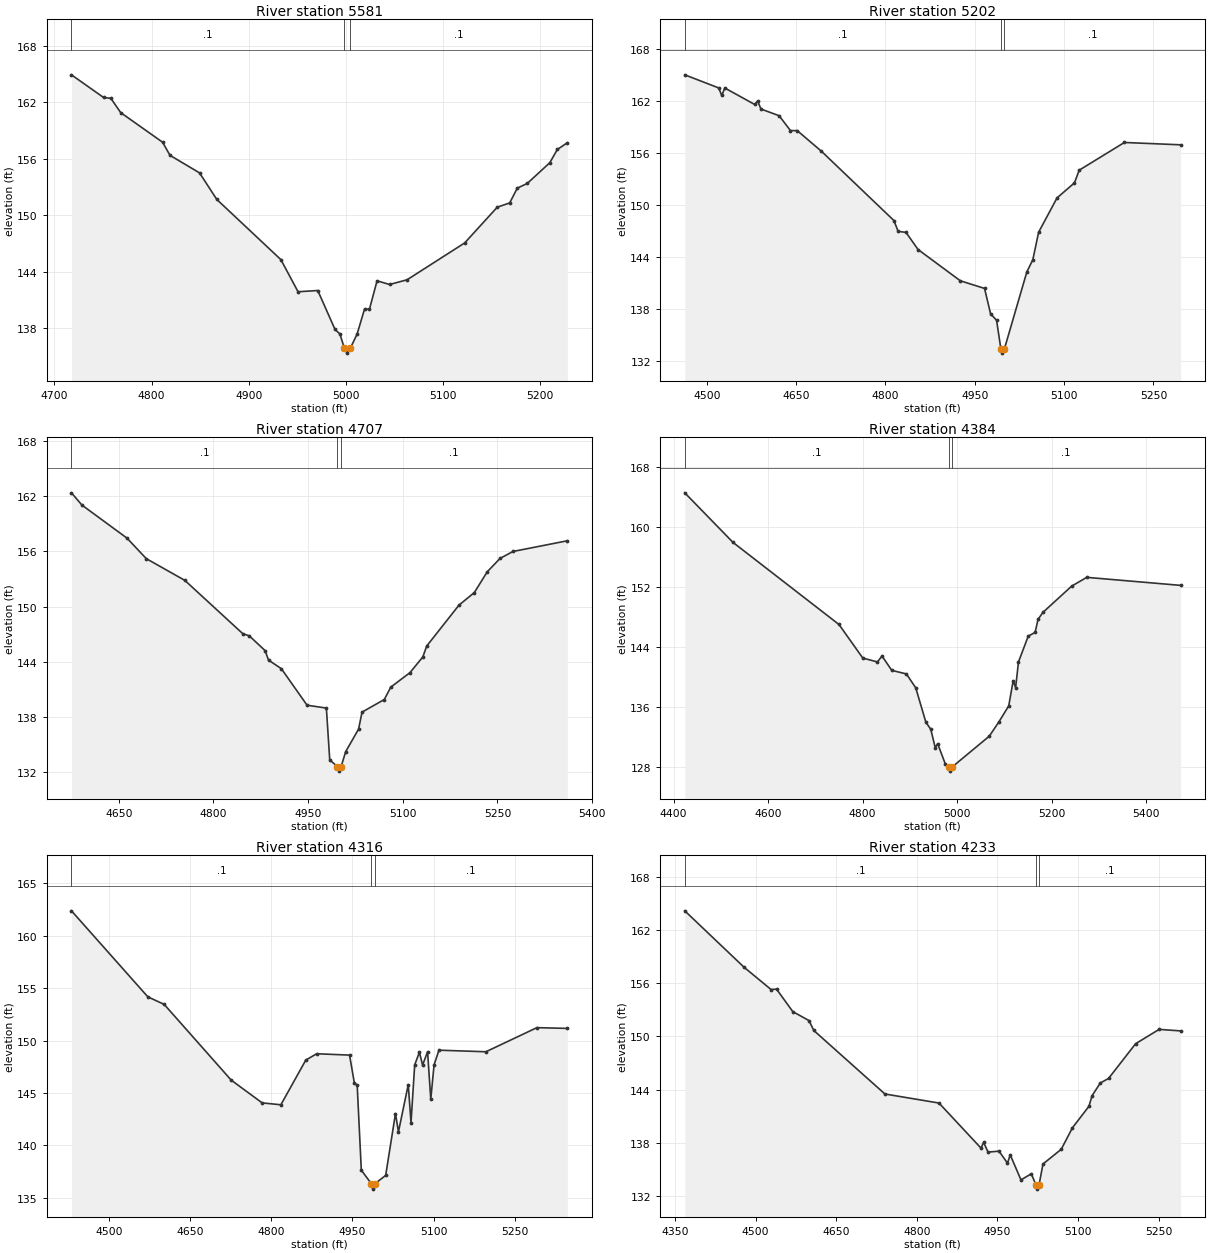
Type RM Length L Ch R = 1,5581,379,379,379
BEGIN DESCRIPTION:
UNT040 IN NURI 12.0
END DESCRIPTION:
XS GIS Cut Line= 3
      2291337.70     13262296.86      2291637.72     13262246.85
      2291837.71     13262196.86
#Sta/Elev= 30
  4717.5  164.89  4750.5  162.49  4758.1  162.39  4768.2  160.88  4811.3  157.74
  4818.9  156.35  4849.3  154.49  4867.1  151.67  4933.0  145.29  4950.7  141.88
  4971.0  142.01  4988.7  137.89  4993.8  137.40  4998.4  135.87  5001.1  135.37
  5004.4  135.87  5011.5  137.40  5019.1  140.04  5024.2  140.04  5032.0  143.04
  5044.9  142.65  5062.9  143.15  5122.2  147.06  5155.7  150.85  5168.5  151.30
  5176.3  152.87  5186.6  153.37  5209.8  155.57  5217.5  156.97  5227.8  157.68
#Mann=3,-1,0
  4717.5     0.1       0  4998.4    0.07       0  5004.4     0.1       0
Bank Sta=4998.4,5004.4
Exp/Cntr=0.3,0.1

Type RM Length L Ch R = 1,5202,495,495,495
BEGIN DESCRIPTION:
UNT040 IN NURI 11.0
END DESCRIPTION:
XS GIS Cut Line= 3
      2291221.60     13262692.30      2291874.43     13262581.19
      2291909.16     13262414.48
#Sta/Elev= 30
  4463.2  165.06  4520.1  163.55  4525.3  162.68  4530.4  163.54  4580.5  161.64
  4585.6  162.04  4591.1  161.11  4621.6  160.34  4640.7  158.62  4652.0  158.62
  4692.6  156.24  4814.3  148.24  4821.4  146.99  4834.6  146.87  4854.9  144.89
  4925.9  141.28  4966.5  140.40  4976.6  137.48  4986.7  136.72  4993.9  133.43
  4996.6  132.93  4999.9  133.43  5037.5  142.30  5047.6  143.72  5057.3  146.89
  5088.2  150.85  5117.5  152.59  5125.4  154.05  5201.3  157.25  5295.7  156.98
#Mann=3,-1,0
  4463.2     0.1       0  4993.9    0.07       0  4999.9     0.1       0
Bank Sta=4993.9,4999.9
Exp/Cntr=0.3,0.1

Type RM Length L Ch R = 1,4707,323,323,323
BEGIN DESCRIPTION:
UNT040 IN NURI 10.0
END DESCRIPTION:
XS GIS Cut Line= 2
      2291381.42     13263171.45      2292152.22     13263018.68
#Sta/Elev= 30
  4575.0  162.35  4591.6  161.02  4663.0  157.43  4693.6  155.20  4754.7  152.84
  4846.5  147.05  4856.7  146.82  4881.9  145.21  4887.3  144.18  4907.6  143.25
  4948.4  139.28  4979.0  138.97  4984.3  133.34  4996.4  132.62  4999.1  132.12
  5002.4  132.62  5009.6  134.24  5030.0  136.68  5035.5  138.53  5070.8  139.90
  5081.0  141.24  5111.5  142.82  5131.9  144.53  5137.9  145.70  5189.1  150.15
  5213.5  151.52  5233.9  153.77  5254.3  155.23  5274.7  155.98  5360.8  157.14
#Mann=3,-1,0
  4575.0     0.1       0  4996.4    0.07       0  5002.4     0.1       0
Bank Sta=4996.4,5002.4
Exp/Cntr=0.3,0.1

Type RM Length L Ch R = 1,4384,68,68,68
BEGIN DESCRIPTION:
UNT040 IN NURI 9.0
END DESCRIPTION:
XS GIS Cut Line= 3
      2291334.34     13263298.38      2291735.36     13263350.46
      2292360.34     13263506.70
#Sta/Elev= 30
  4423.8  164.54  4525.7  157.93  4749.9  146.97  4800.3  142.49  4831.1  141.97
  4840.9  142.76  4861.5  140.85  4892.5  140.37  4912.2  138.52  4933.7  133.92
  4944.0  132.99  4953.4  130.54  4958.6  131.06  4974.9  128.34  4982.2  127.90
  4985.0  127.40  4988.2  127.90  5067.7  132.06  5088.3  133.99  5108.9  136.11
  5118.3  139.46  5123.5  138.55  5129.5  141.97  5150.2  145.42  5164.7  145.91
  5170.8  147.64  5181.1  148.58  5242.0  152.09  5273.9  153.26  5472.4  152.19
#Mann=3,-1,0
  4423.8     0.1       0  4982.2    0.07       0  4988.2     0.1       0
Bank Sta=4982.2,4988.2
Exp/Cntr=0.3,0.1

Type RM Length L Ch R = 1,4316,83,83,83
BEGIN DESCRIPTION:
Mapping XS 50e1eefd
END DESCRIPTION:
XS GIS Cut Line= 4
      2291337.44     13263380.31      2291842.68     13263435.00
      2291952.05     13263481.87      2292193.47     13263640.22
#Sta/Elev= 30
  4430.9  162.39  4572.0  154.18  4602.2  153.46  4726.0  146.23  4783.2  144.06
  4817.7  143.88  4863.7  148.14  4883.8  148.75  4944.6  148.62  4953.3  146.00
  4958.7  145.73  4966.3  137.64  4985.1  136.33  4987.8  135.83  4991.1  136.33
  5011.3  137.14  5029.4  143.04  5034.9  141.30  5053.0  145.80  5058.1  142.18
  5064.9  147.69  5073.6  148.89  5079.5  147.67  5088.7  148.94  5094.6  144.41
  5100.7  147.69  5109.7  149.09  5196.4  148.94  5290.6  151.24  5346.8  151.17
#Mann=3,-1,0
  4430.9     0.1       0  4985.1    0.07       0  4991.1     0.1       0
Bank Sta=4985.1,4991.1
Exp/Cntr=0.3,0.1

Type RM Length L Ch R = 1,4233,394,394,394
BEGIN DESCRIPTION:
Mapping XS 6b3f1590
END DESCRIPTION:
XS GIS Cut Line= 4
      2291298.42     13263450.62      2291842.68     13263520.94
      2291988.51     13263552.19      2292178.51     13263671.91
#Sta/Elev= 30
  4368.3  164.15  4478.5  157.80  4528.9  155.28  4539.0  155.33  4569.3  152.79
  4599.5  151.78  4608.3  150.67  4740.7  143.51  4841.3  142.49  4919.3  137.42
  4924.4  138.06  4932.5  136.96  4952.9  137.07  4968.7  135.72  4973.8  136.65
  4993.8  133.83  5013.0  134.52  5021.5  133.29  5024.3  132.79  5027.5  133.29
  5034.7  135.62  5068.7  137.28  5089.6  139.71  5120.2  142.12  5126.1  143.32
  5141.4  144.75  5156.7  145.26  5207.1  149.18  5250.8  150.79  5290.8  150.62
#Mann=3,-1,0
  4368.3     0.1       0  5021.5    0.07       0  5027.5     0.1       0
Bank Sta=5021.5,5027.5
Exp/Cntr=0.3,0.1

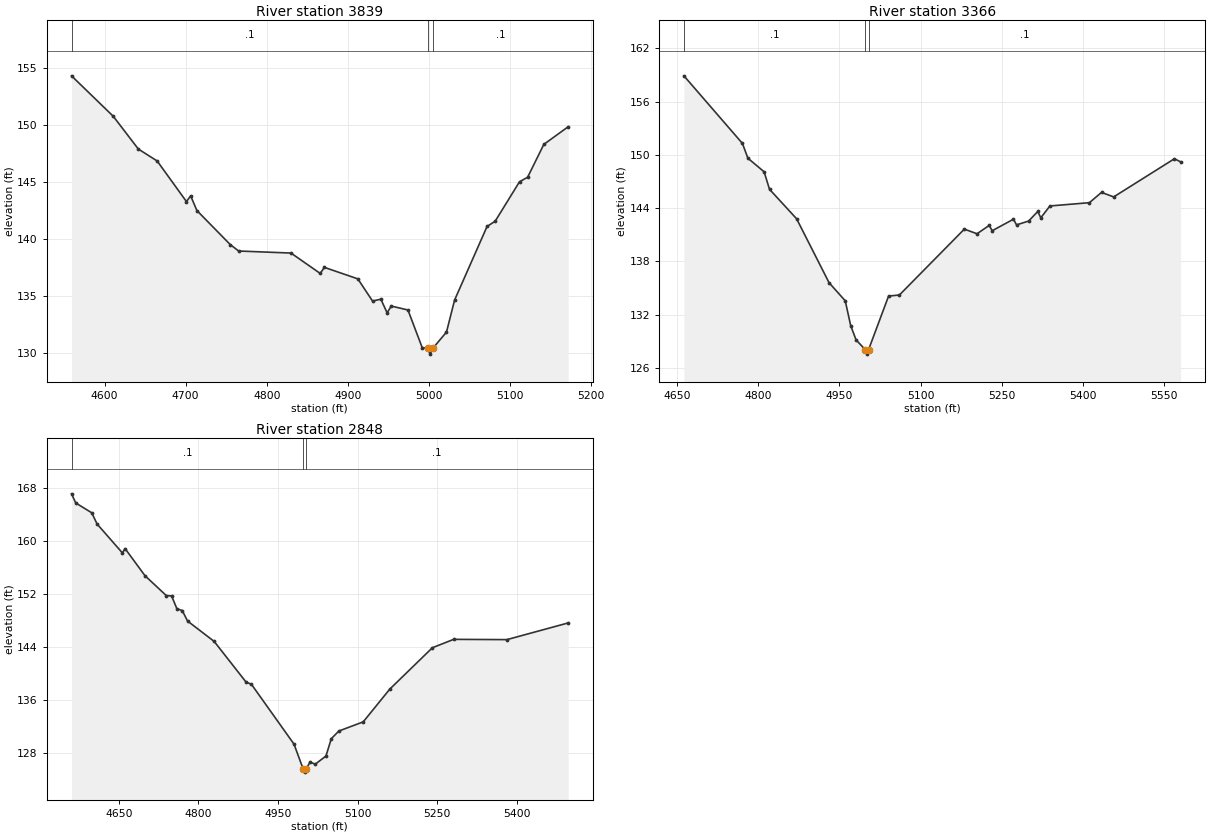
Type RM Length L Ch R = 1,3839,473,473,473
BEGIN DESCRIPTION:
UNT040 IN NURI 8.0
END DESCRIPTION:
XS GIS Cut Line= 3
      2291437.75     13263996.85      2291837.72     13263896.85
      2292037.74     13263896.85
#Sta/Elev= 30
  4559.3  154.35  4610.8  150.79  4641.7  147.91  4664.9  146.86  4701.0  143.29
  4706.2  143.79  4713.9  142.50  4755.1  139.50  4765.4  138.94  4829.9  138.76
  4865.9  136.97  4871.1  137.50  4912.3  136.49  4930.4  134.54  4940.7  134.70
  4948.4  133.50  4953.5  134.10  4974.1  133.75  4991.6  130.45  4998.6  130.37
  5001.3  129.87  5004.6  130.37  5021.6  131.81  5031.6  134.63  5071.6  141.10
  5081.6  141.56  5111.6  145.03  5121.6  145.43  5141.6  148.32  5171.6  149.87
#Mann=3,-1,0
  4559.3     0.1       0  4998.6    0.07       0  5004.6     0.1       0
Bank Sta=4998.6,5004.6
Exp/Cntr=0.3,0.1

Type RM Length L Ch R = 1,3366,518,518,518
BEGIN DESCRIPTION:
UNT040 IN NURI 7.0
END DESCRIPTION:
XS GIS Cut Line= 3
      2291339.51     13264329.62      2291881.20     13264308.79
      2292047.45     13263971.09
#Sta/Elev= 30
  4662.4  158.91  4770.7  151.29  4780.7  149.63  4810.7  148.10  4820.7  146.13
  4870.8  142.81  4930.8  135.61  4960.8  133.56  4970.8  130.78  4980.8  129.16
  4997.9  128.06  5000.6  127.56  5003.9  128.06  5040.9  134.10  5060.9  134.22
  5181.0  141.64  5204.5  141.12  5227.0  142.06  5232.5  141.46  5271.9  142.76
  5277.5  142.12  5299.9  142.55  5316.8  143.63  5322.4  142.92  5339.3  144.25
  5412.3  144.62  5434.7  145.78  5457.2  145.27  5569.5  149.57  5580.9  149.22
#Mann=3,-1,0
  4662.4     0.1       0  4997.9    0.07       0  5003.9     0.1       0
Bank Sta=4997.9,5003.9
Exp/Cntr=0.3,0.1

Type RM Length L Ch R = 1,2848,283,283,283
BEGIN DESCRIPTION:
UNT040 IN NURI 6.0
END DESCRIPTION:
XS GIS Cut Line= 2
      2291239.68     13264794.55      2292172.80     13264863.99
#Sta/Elev= 30
  4560.9  167.05  4569.0  165.67  4599.0  164.20  4609.1  162.51  4656.8  158.16
  4661.8  158.82  4699.3  154.74  4739.4  151.75  4749.5  151.69  4759.5  149.76
  4769.5  149.50  4779.5  147.92  4829.7  144.85  4889.8  138.73  4899.9  138.40
  4980.1  129.40  4997.2  125.69  4999.9  125.19  5003.2  125.69  5010.2  126.69
  5020.2  126.39  5040.3  127.61  5050.3  130.21  5064.5  131.37  5110.5  132.75
  5160.6  137.68  5240.8  143.90  5280.9  145.16  5381.2  145.12  5496.6  147.63
#Mann=3,-1,0
  4560.9     0.1       0  4997.2    0.07       0  5003.2     0.1       0
Bank Sta=4997.2,5003.2
Exp/Cntr=0.3,0.1