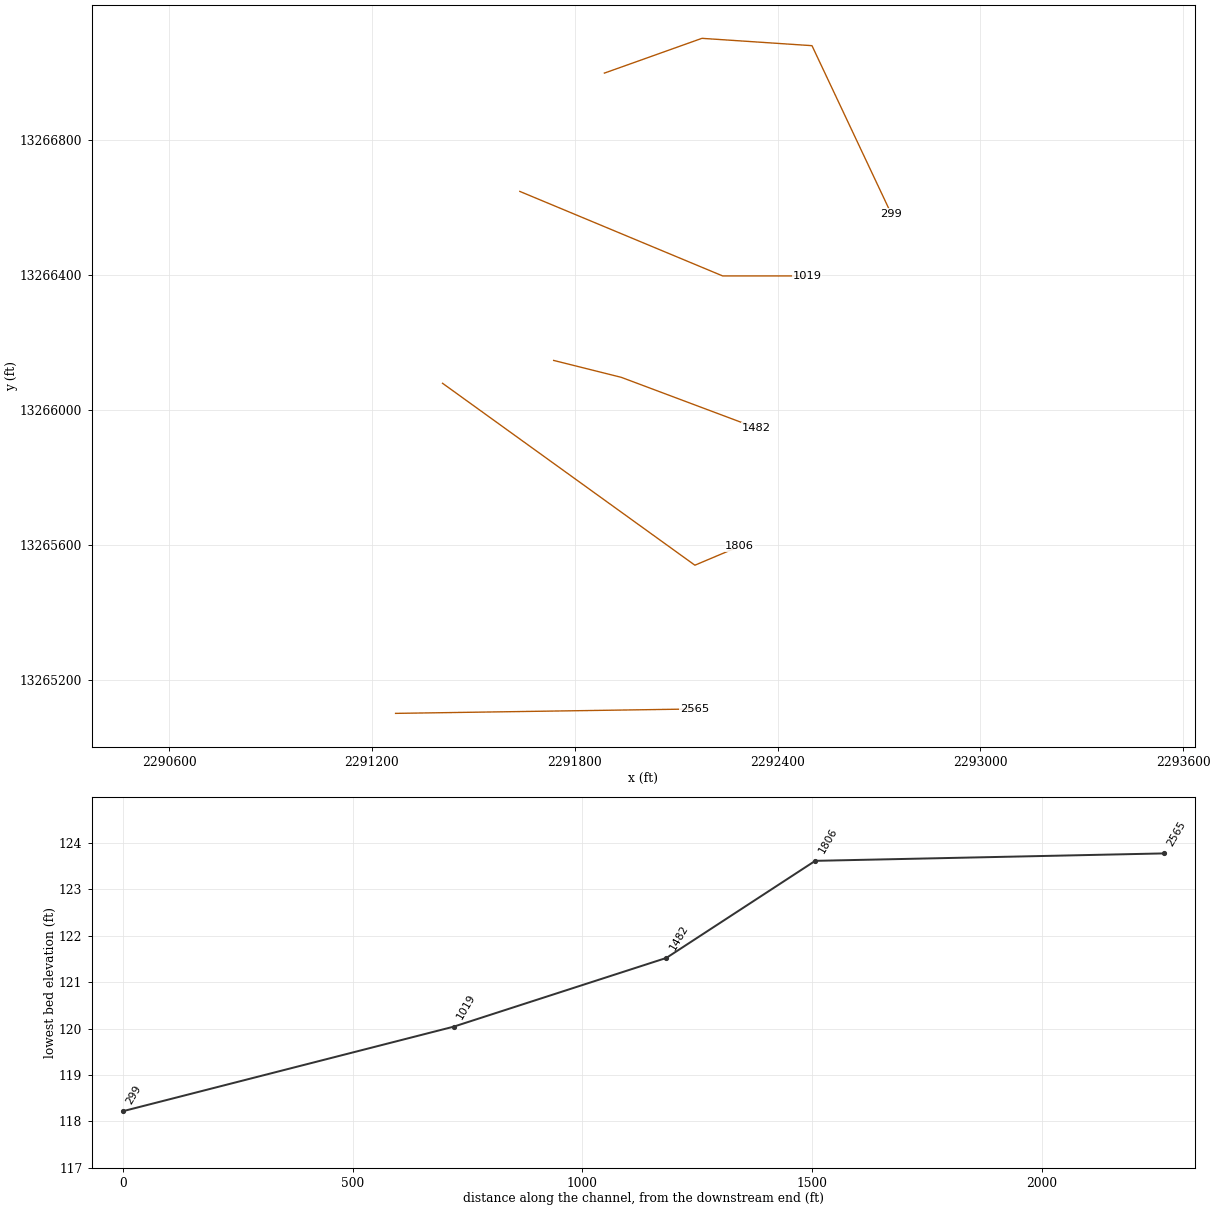
HEC-RAS study UNT040 IN NURI.prj: UNT040 IN NURI Base Level Engineering

--- UNT040 IN NURI.g01 (geometry) --- (continued)

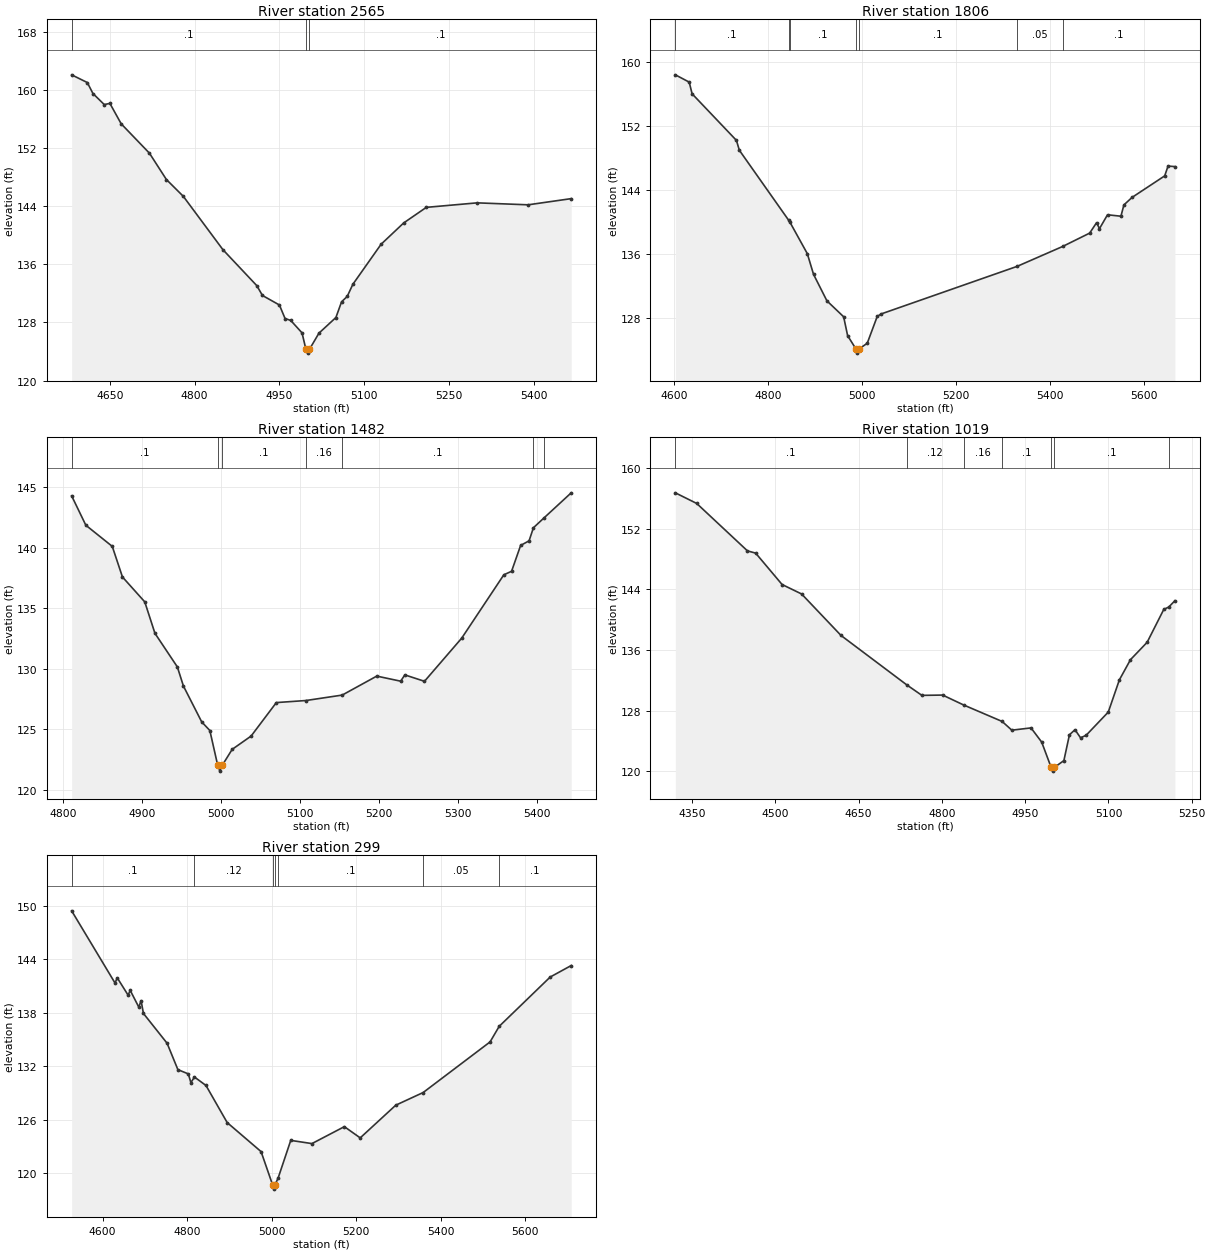
Type RM Length L Ch R = 1,2565,759,759,759
BEGIN DESCRIPTION:
UNT040 IN NURI 5.0
END DESCRIPTION:
XS GIS Cut Line= 2
      2291270.06     13265102.71      2292154.06     13265115.71
#Sta/Elev= 30
  4582.5  162.05  4610.2  160.99  4620.2  159.48  4640.2  157.96  4650.2  158.12
  4670.2  155.31  4720.2  151.27  4750.2  147.65  4780.2  145.33  4850.2  138.00
  4910.2  133.05  4920.2  131.70  4950.2  130.39  4960.2  128.53  4970.2  128.27
  4990.2  126.56  4997.2  124.27  5000.0  123.77  5003.2  124.27  5020.2  126.52
  5050.2  128.67  5060.2  130.83  5070.2  131.57  5080.2  133.24  5130.2  138.75
  5170.2  141.68  5210.2  143.82  5300.2  144.44  5390.3  144.17  5466.6  145.02
#Mann=3,-1,0
  4582.5     0.1       0  4997.2    0.07       0  5003.2     0.1       0
Bank Sta=4997.2,5003.2
Exp/Cntr=0.3,0.1

Type RM Length L Ch R = 1,1806,324,324,324
BEGIN DESCRIPTION:
UNT040 IN NURI 4.0
END DESCRIPTION:
XS GIS Cut Line= 3
      2291409.00     13266079.25      2292155.50     13265541.08
      2292287.75     13265596.87
#Sta/Elev= 30
  4602.8  158.37  4632.3  157.46  4638.5  156.00  4732.9  150.18  4739.1  148.95
  4844.2  140.20  4846.1  140.04  4883.8  136.04  4897.1  133.45  4925.6  130.14
  4961.2  128.15  4969.7  125.79  4987.6  124.11  4990.3  123.61  4993.6  124.11
  5011.5  124.85  5032.7  128.19  5040.9  128.50  5330.8  134.45  5427.5  136.93
  5485.1  138.60  5499.8  139.90  5506.0  139.16  5523.1  140.89  5551.7  140.71
  5558.0  142.12  5575.4  143.06  5644.9  145.75  5652.0  146.97  5666.6  146.91
#Mann=7,-1,0
  4602.8     0.1       0  4844.2    0.05       0  4846.1     0.1       0
  4987.6    0.07       0  4993.6     0.1       0  5330.8    0.05       0
  5427.5     0.1       0
Bank Sta=4987.6,4993.6
Exp/Cntr=0.3,0.1

Type RM Length L Ch R = 1,1482,463,463,463
BEGIN DESCRIPTION:
UNT040 IN NURI 3.0
END DESCRIPTION:
XS GIS Cut Line= 3
      2291737.75     13266146.85      2291937.72     13266096.85
      2292337.70     13265946.86
#Sta/Elev= 30
  4810.6  144.29  4828.6  141.86  4862.1  140.11  4875.0  137.58  4903.3  135.52
  4916.2  132.92  4944.6  130.14  4952.3  128.56  4975.5  125.59  4985.8  124.88
  4995.7  122.02  4998.4  121.52  5001.7  122.02  5014.1  123.32  5038.1  124.42
  5070.1  127.19  5107.6  127.36  5153.6  127.81  5197.4  129.38  5227.7  128.96
  5233.0  129.48  5257.9  128.95  5305.1  132.52  5358.5  137.76  5368.3  138.05
  5379.8  140.19  5390.5  140.57  5396.0  141.65  5409.5  142.47  5443.9  144.54
#Mann=7,-1,0
  4810.6     0.1       0  4995.7    0.07       0  5001.7     0.1       0
  5107.6    0.16       0  5153.6     0.1       0  5396.0    0.05       0
  5409.5     0.1       0
Bank Sta=4995.7,5001.7
Exp/Cntr=0.3,0.1

Type RM Length L Ch R = 1,1019,720,720,720
BEGIN DESCRIPTION:
UNT040 IN NURI 2.0
END DESCRIPTION:
XS GIS Cut Line= 3
      2291637.68     13266646.87      2292237.72     13266396.85
      2292487.67     13266396.85
#Sta/Elev= 30
  4319.7  156.74  4358.2  155.34  4449.7  149.08  4464.4  148.79  4512.0  144.65
  4547.2  143.40  4618.2  137.93  4736.9  131.40  4763.9  130.03  4801.3  130.07
  4838.9  128.77  4908.5  126.59  4925.9  125.44  4960.5  125.74  4979.7  123.87
  4996.7  120.54  4999.5  120.04  5002.7  120.54  5019.7  121.43  5029.7  124.83
  5039.7  125.50  5049.7  124.44  5059.7  124.76  5099.7  127.83  5119.7  132.08
  5139.7  134.74  5169.7  137.03  5199.7  141.37  5208.5  141.67  5219.7  142.51
#Mann=7,-1,0
  4319.7     0.1       0  4736.9    0.12       0  4838.9    0.16       0
  4908.5     0.1       0  4996.7    0.07       0  5002.7     0.1       0
  5208.5    0.05       0
Bank Sta=4996.7,5002.7
Exp/Cntr=0.3,0.1

Type RM Length L Ch R = 1,299,0,0,0
BEGIN DESCRIPTION:
UNT040 IN NURI 1.0
END DESCRIPTION:
XS GIS Cut Line= 4
      2291887.72     13266996.85      2292176.40     13267099.75
      2292501.92     13267078.05      2292736.09     13266581.51
#Sta/Elev= 30
  4526.8  149.45  4629.4  141.35  4634.7  141.93  4660.2  140.00  4665.5  140.51
  4685.7  138.64  4691.0  139.37  4696.7  137.93  4752.6  134.59  4778.1  131.63
  4802.8  131.15  4808.9  130.17  4817.3  130.80  4844.6  129.85  4894.7  125.69
  4974.9  122.43  5002.0  118.72  5004.7  118.22  5008.0  118.72  5015.2  119.46
  5045.1  123.69  5095.2  123.33  5171.9  125.23  5209.4  123.97  5293.5  127.64
  5358.3  129.06  5516.6  134.74  5538.2  136.49  5658.8  142.02  5708.5  143.31
#Mann=7,-1,0
  4526.8     0.1       0  4817.3    0.12       0  5002.0    0.07       0
  5008.0    0.12       0  5015.2     0.1       0  5358.3    0.05       0
  5538.2     0.1       0
Bank Sta=5002,5008
Exp/Cntr=0.3,0.1

Chan Stop Cuts=-1