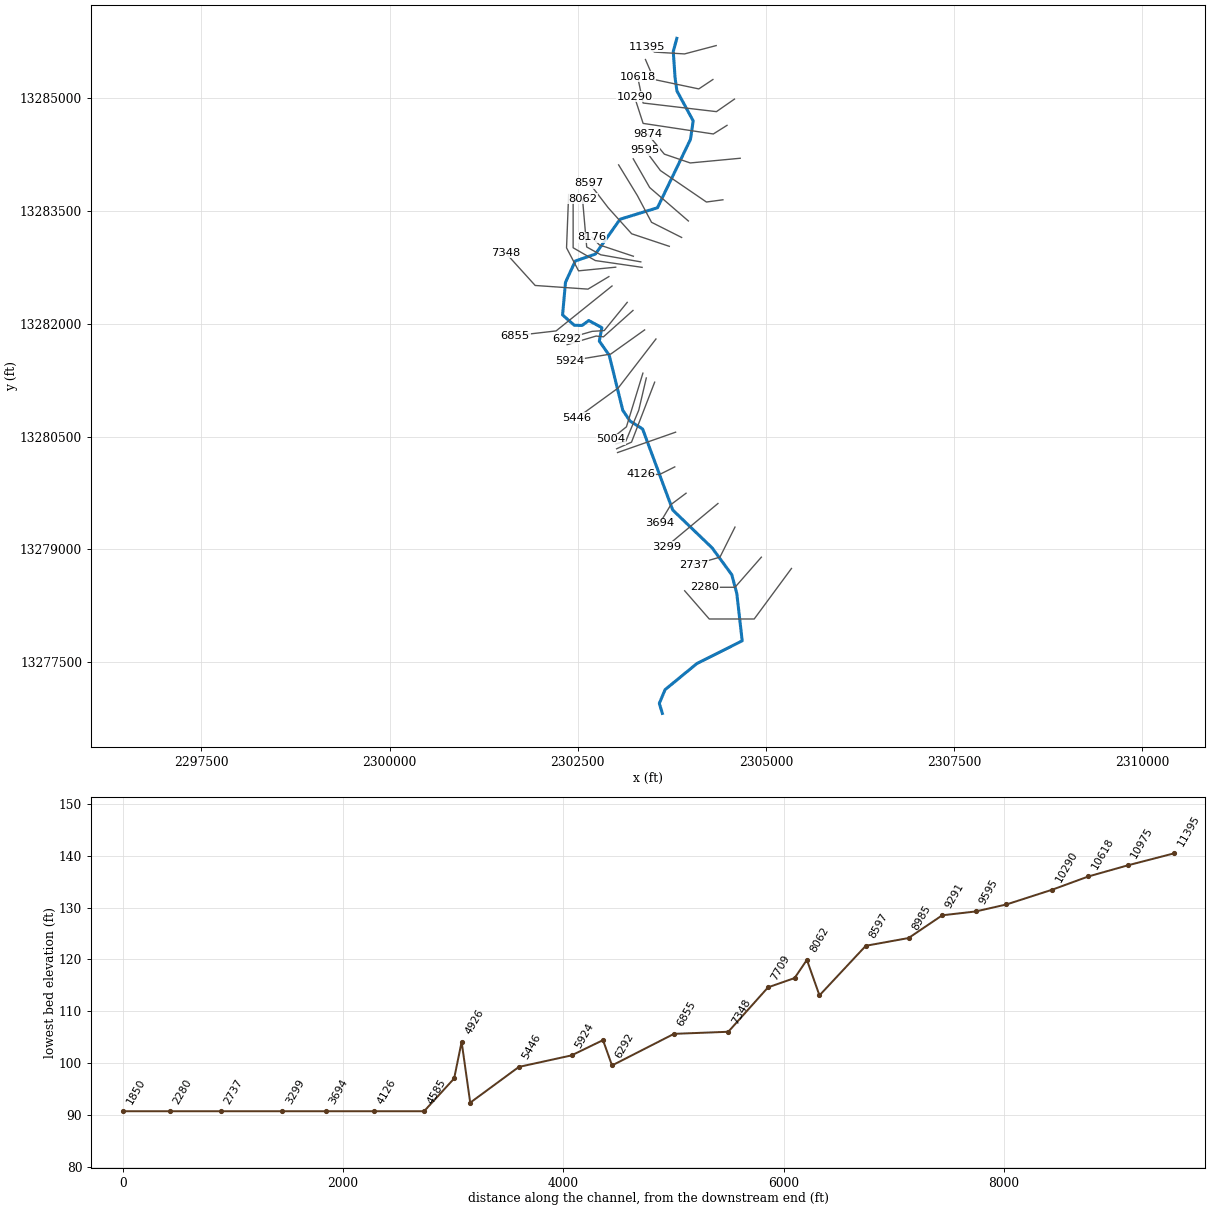
--- UNT042 IN NURI.prj (project) ---

Proj Title=UNT042 IN NURI Base Level Engineering
Current Plan=p01
Default Exp/Contr=0.3,0.1
English Units
Geom File=g01
Flow File=f01
Plan File=p01
BEGIN DESCRIPTION:
UNT042 IN NURI
END DESCRIPTION:

--- UNT042 IN NURI.p01 (plan) ---

Plan Title=Multiple Run
Short Identifier=Multiple
Geom File=g01
Flow File=f01
Subcritical Flow
K Sum by GR= 0
Std Step Tol= 0.01
Critical Tol= 0.01
Num of Std Step Trials= 20
Max Error Tol= 0.3
Flow Tol Ratio= 0.001
Split Flow NTrial= 30
Split Flow Tol= 0.02
Split Flow Ratio= 0.02
Log Output Level= 0
Friction Slope Method= 1
Unsteady Friction Slope Method= 2
Unsteady Bridges Friction Slope Method= 1
Parabolic Critical Depth
Global Vel Dist=  1 , 1 , 1
Global Log Level= 0
CheckData=True
Encroach Param= -1, 0, 0, 0
BEGIN DESCRIPTION:
Multiple Run
END DESCRIPTION:

--- UNT042 IN NURI.f01 (steady flow) ---

Flow Title=Multiple
Number of Profiles=7
Profile Names=10-year,25-year,50-year,1pct_min,100-year,1pct_plu,500-year
River Rch & RM= UNT042 IN NURI,Reach-1,11395
     587     832    1037     945    1279    1729    1950
River Rch & RM= UNT042 IN NURI,Reach-1,9291
     634     902    1129    1032    1395    1887    2139
River Rch & RM= UNT042 IN NURI,Reach-1,6855
    1223    1800    2303    2146    2902    3925    4635
Boundary for River Rch & Prof#=UNT042 IN NURI,Reach-1,1
Up Type=0
Dn Type=3
Dn Slope=0.005
Boundary for River Rch & Prof#=UNT042 IN NURI,Reach-1,2
Up Type=0
Dn Type=3
Dn Slope=0.005
Boundary for River Rch & Prof#=UNT042 IN NURI,Reach-1,3
Up Type=0
Dn Type=3
Dn Slope=0.005
Boundary for River Rch & Prof#=UNT042 IN NURI,Reach-1,4
Up Type=0
Dn Type=3
Dn Slope=0.005
Boundary for River Rch & Prof#=UNT042 IN NURI,Reach-1,5
Up Type=0
Dn Type=3
Dn Slope=0.005
Boundary for River Rch & Prof#=UNT042 IN NURI,Reach-1,6
Up Type=0
Dn Type=3
Dn Slope=0.005
Boundary for River Rch & Prof#=UNT042 IN NURI,Reach-1,7
Up Type=0
Dn Type=3
Dn Slope=0.005

--- UNT042 IN NURI.g01 (geometry) ---

Geom Title=Existing Conditions

River Reach=UNT042 IN NURI,Reach-1
Reach XY= 30
      2303815.24     13285793.14      2303767.74     13285618.40
      2303791.98     13285267.53      2303816.16     13285094.85
      2304032.58     13284695.74      2303995.98     13284449.31
      2303557.61     13283541.11      2303061.44     13283388.77
      2302733.27     13282925.32      2302466.98     13282833.66
      2302336.14     13282550.24      2302297.72     13282115.91
      2302453.65     13281979.11      2302556.79     13281977.14
      2302645.36     13282042.13      2302819.84     13281947.51
      2302785.23     13281769.21      2302917.02     13281580.49
      2303097.30     13280848.53      2303192.79     13280707.04
      2303360.32     13280601.13      2303760.50     13279523.88
      2304283.06     13279021.27      2304545.22     13278663.63
      2304611.92     13278412.63      2304683.25     13277785.06
      2304081.69     13277482.98      2303658.87     13277135.68
      2303582.57     13276953.56      2303622.93     13276820.75

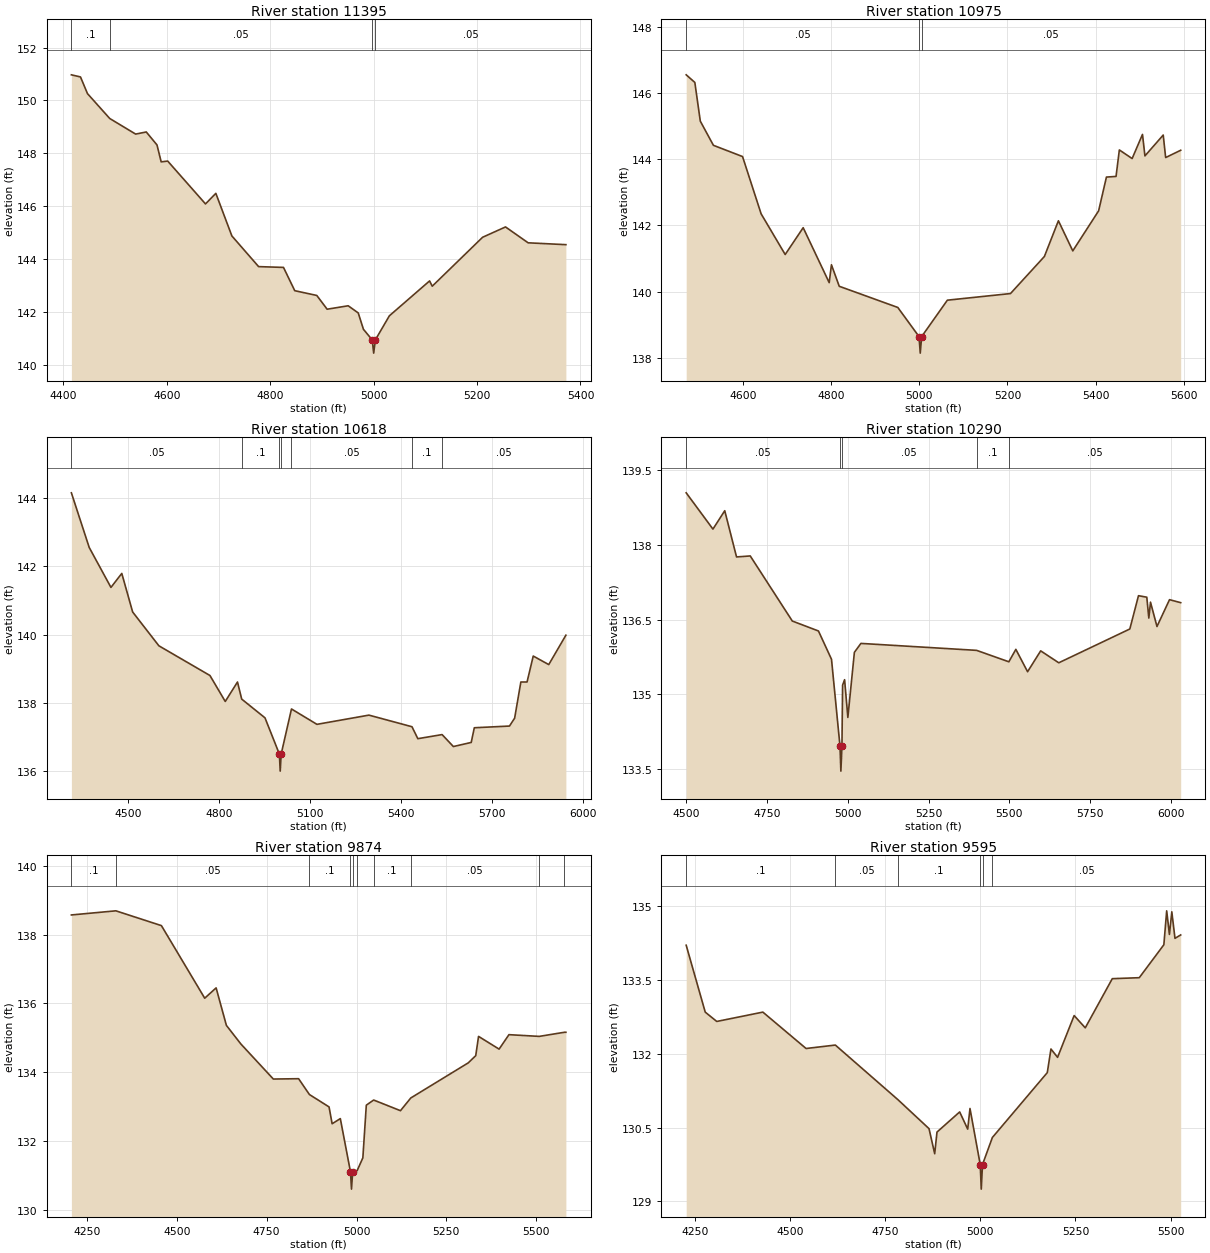
Type RM Length L Ch R = 1,11395,420,420,420
BEGIN DESCRIPTION:
UNT042 IN NURI 19.0
END DESCRIPTION:
XS GIS Cut Line= 4
      2304337.76     13285696.87      2303917.58     13285586.01
      2303518.27     13285610.31      2303421.08     13285683.21
#Sta/Elev= 30
  4415.7  150.97  4433.3  150.89  4446.8  150.26  4489.8  149.32  4539.9  148.73
  4560.5  148.81  4581.2  148.32  4589.3  147.68  4601.9  147.71  4675.0  146.09
  4695.0  146.49  4726.0  144.88  4777.7  143.72  4825.8  143.69  4847.6  142.81
  4890.2  142.63  4910.2  142.11  4950.9  142.24  4970.3  141.97  4980.4  141.35
  4997.4  140.95  5000.2  140.45  5003.4  140.95  5030.5  141.86  5108.3  143.18
  5113.4  142.98  5210.8  144.83  5255.1  145.22  5298.8  144.62  5371.8  144.55
#Mann=4,-1,0
  4415.7     0.1       0  4489.8    0.05       0  4997.4    0.03       0
  5003.4    0.05       0
Bank Sta=4997.4,5003.4
Exp/Cntr=0.3,0.1

Type RM Length L Ch R = 1,10975,357,357,357
BEGIN DESCRIPTION:
UNT042 IN NURI 18.0
END DESCRIPTION:
XS GIS Cut Line= 4
      2304294.33     13285245.90      2304106.82     13285120.89
      2303513.07     13285245.89      2303398.49     13285511.51
#Sta/Elev= 30
  4471.4  146.55  4491.0  146.32  4503.4  145.15  4533.1  144.42  4599.2  144.08
  4641.3  142.35  4695.9  141.12  4736.7  141.93  4795.7  140.27  4800.8  140.81
  4818.5  140.16  4951.3  139.52  4999.4  138.64  5002.2  138.14  5005.4  138.64
  5063.7  139.74  5206.8  139.94  5283.7  141.06  5315.5  142.14  5348.1  141.23
  5406.7  142.44  5424.4  143.46  5446.2  143.48  5453.7  144.28  5482.7  144.02
  5506.2  144.75  5511.7  144.10  5553.2  144.73  5558.7  144.05  5592.8  144.27
#Mann=3,-1,0
  4471.4    0.05       0  4999.4   0.035       0  5005.4    0.05       0
Bank Sta=4999.4,5005.4
Exp/Cntr=0.3,0.1

Type RM Length L Ch R = 1,10618,328,328,328
BEGIN DESCRIPTION:
Mapping XS 27aee4f3
END DESCRIPTION:
XS GIS Cut Line= 4
      2304580.76     13284985.46      2304341.19     13284818.81
      2303367.23     13284933.39      2303294.38     13285282.05
#Sta/Elev= 30
  4314.0  144.15  4372.7  142.55  4444.3  141.38  4480.0  141.79  4515.8  140.66
  4602.2  139.67  4770.4  138.80  4820.8  138.04  4861.1  138.61  4874.9  138.11
  4951.7  137.56  4999.0  136.50  5001.8  136.00  5005.0  136.50  5038.9  137.82
  5122.8  137.37  5294.0  137.64  5435.8  137.30  5455.1  136.95  5535.0  137.07
  5572.1  136.72  5630.9  136.84  5641.1  137.27  5756.9  137.32  5773.9  137.55
  5794.4  138.61  5814.8  138.61  5835.2  139.37  5886.3  139.12  5942.7  139.98
#Mann=7,-1,0
  4314.0    0.05       0  4874.9     0.1       0  4999.0    0.07       0
  5005.0     0.1       0  5038.9    0.05       0  5435.8     0.1       0
  5535.0    0.05       0
Bank Sta=4999,5005
Exp/Cntr=0.3,0.1

Type RM Length L Ch R = 1,10290,416,416,416
BEGIN DESCRIPTION:
Mapping XS 985ee380
END DESCRIPTION:
XS GIS Cut Line= 4
      2304481.81     13284636.51      2304299.53     13284521.93
      2303367.23     13284662.56      2303252.68     13285016.65
#Sta/Elev= 30
  4500.1  139.05  4582.9  138.32  4619.4  138.69  4655.9  137.76  4698.3  137.78
  4828.5  136.47  4909.4  136.27  4949.8  135.70  4976.1  133.95  4978.8  133.45
  4982.1  133.95  4984.1  135.18  4990.3  135.29  5000.4  134.53  5020.6  135.84
  5040.8  136.02  5398.9  135.88  5498.6  135.65  5520.3  135.90  5556.6  135.45
  5597.1  135.87  5653.1  135.63  5873.0  136.31  5899.8  136.98  5925.5  136.95
  5931.8  136.53  5937.0  136.85  5957.0  136.36  5995.8  136.90  6030.4  136.84
#Mann=5,-1,0
  4500.1    0.05       0  4976.1   0.035       0  4982.1    0.05       0
  5398.9     0.1       0  5498.6    0.05       0
Bank Sta=4976.1,4982.1
Exp/Cntr=0.3,0.1

Type RM Length L Ch R = 1,9874,279,279,279
BEGIN DESCRIPTION:
Mapping XS 8ca1ee19
END DESCRIPTION:
XS GIS Cut Line= 4
      2304657.12     13284199.27      2303993.09     13284136.77
      2303649.34     13284253.96      2303427.99     13284519.58
#Sta/Elev= 30
  4206.7  138.57  4330.4  138.69  4457.2  138.26  4577.7  136.15  4609.4  136.45
  4638.0  135.36  4678.2  134.82  4768.6  133.80  4838.9  133.81  4869.0  133.35
  4923.6  132.99  4932.2  132.50  4955.0  132.65  4983.3  131.10  4986.1  130.60
  4989.3  131.10  5001.9  131.14  5017.7  131.51  5027.3  133.04  5047.8  133.19
  5122.3  132.88  5151.1  133.25  5310.9  134.27  5331.8  134.48  5339.6  135.04
  5396.8  134.67  5424.2  135.09  5508.5  135.04  5578.7  135.16  5582.6  135.16
#Mann=10,-1,0
  4206.7     0.1       0  4330.4    0.05       0  4869.0     0.1       0
  4983.3    0.07       0  4989.3     0.1       0  5001.9    0.05       0
  5047.8     0.1       0  5151.1    0.05       0  5508.5     0.1       0
  5578.7    0.05       0
Bank Sta=4983.3,4989.3
Exp/Cntr=0.3,0.1

Type RM Length L Ch R = 1,9595,304,304,304
BEGIN DESCRIPTION:
Mapping XS c92da5a1
END DESCRIPTION:
XS GIS Cut Line= 4
      2304427.31     13283647.10      2304208.19     13283617.56
      2303597.08     13284035.56      2303395.69     13284306.40
#Sta/Elev= 30
  4227.6  134.21  4277.6  132.85  4307.9  132.66  4429.0  132.85  4542.5  132.11
  4619.4  132.18  4783.7  131.07  4865.5  130.48  4880.4  129.97  4886.4  130.41
  4946.0  130.82  4967.1  130.47  4973.1  130.89  5000.0  129.75  5002.7  129.25
  5006.0  129.75  5031.9  130.30  5176.2  131.62  5185.8  132.10  5203.2  131.93
  5246.7  132.78  5275.9  132.53  5346.9  133.53  5417.8  133.55  5482.4  134.22
  5489.8  134.91  5497.0  134.43  5503.3  134.89  5511.6  134.35  5526.6  134.42
#Mann=6,-1,0
  4227.6     0.1       0  4619.4    0.05       0  4783.7     0.1       0
  5000.0    0.07       0  5006.0     0.1       0  5031.9    0.05       0
Bank Sta=5000,5006
Exp/Cntr=0.3,0.1

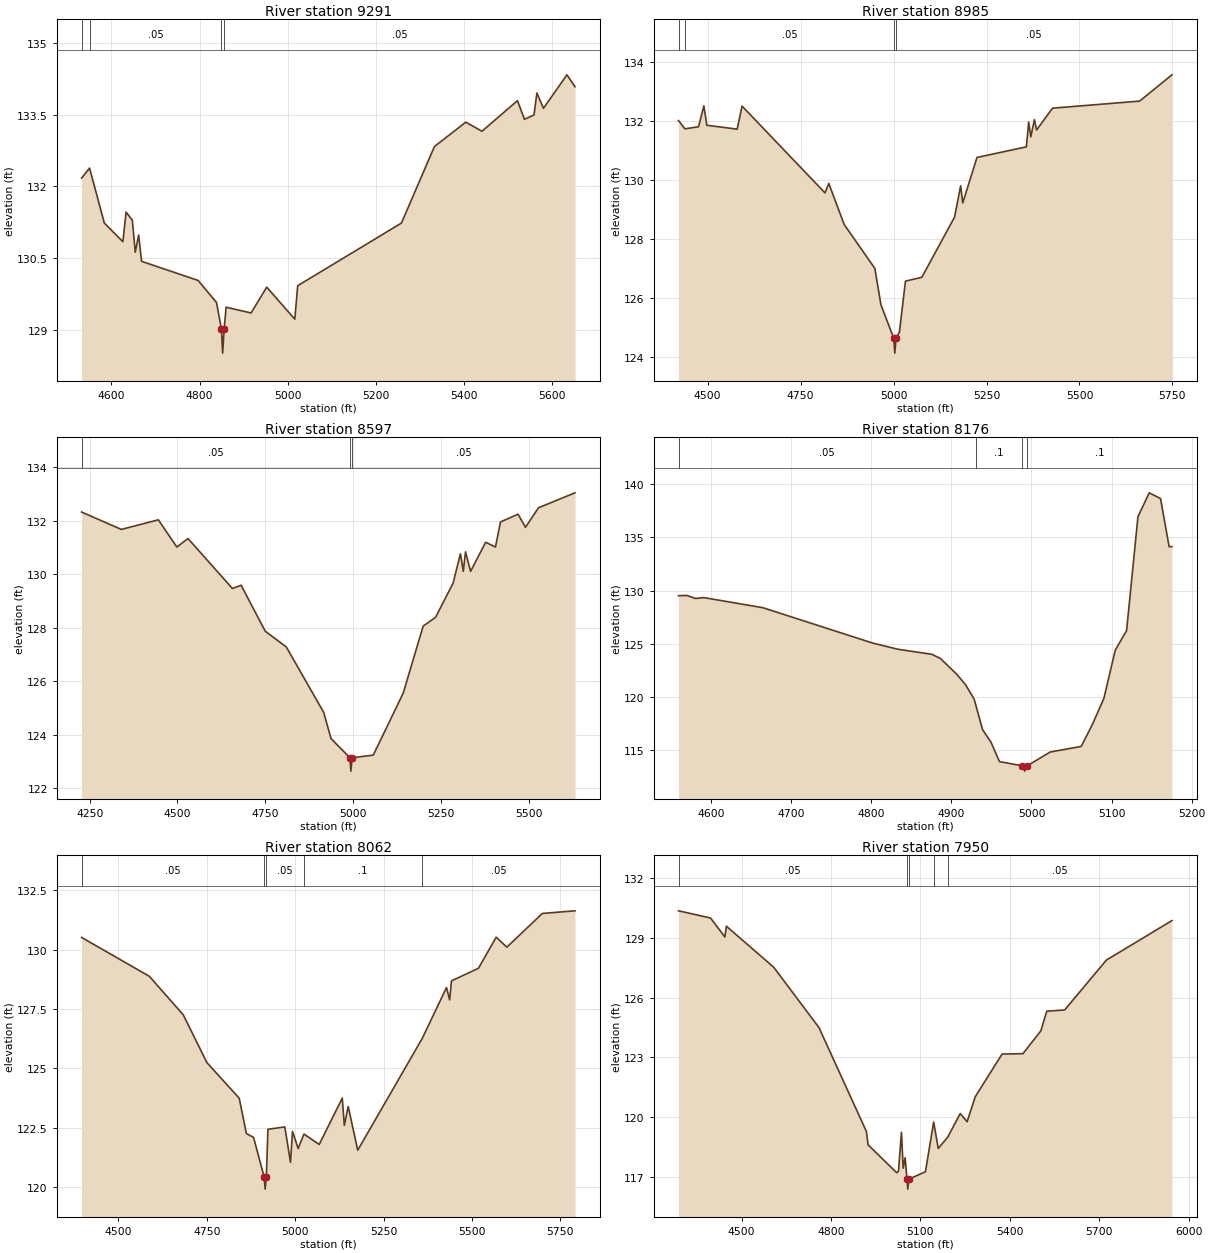
Type RM Length L Ch R = 1,9291,306,306,306
BEGIN DESCRIPTION:
Mapping XS 7b15e3df
END DESCRIPTION:
XS GIS Cut Line= 3
      2303968.63     13283365.40      2303454.72     13283809.86
      2303235.97     13284191.81
#Sta/Elev= 30
  4532.3  132.17  4550.4  132.38  4583.9  131.23  4626.0  130.84  4633.3  131.46
  4647.5  131.29  4654.1  130.62  4661.8  130.98  4668.4  130.43  4796.7  130.03
  4838.4  129.57  4849.7  129.01  4852.4  128.51  4855.7  129.01  4860.3  129.47
  4916.9  129.35  4952.4  129.89  5016.1  129.22  5022.7  129.92  5258.1  131.23
  5332.9  132.83  5404.2  133.34  5440.8  133.15  5521.4  133.79  5537.2  133.40
  5558.8  133.49  5565.5  133.95  5580.4  133.63  5633.6  134.33  5651.9  134.08
#Mann=4,-1,0
  4532.3    0.08       0  4550.4    0.05       0  4849.7   0.035       0
  4855.7    0.05       0
Bank Sta=4849.7,4855.7
Exp/Cntr=0.3,0.1

Type RM Length L Ch R = 1,8985,388,388,388
BEGIN DESCRIPTION:
UNT042 IN NURI 17.0
END DESCRIPTION:
XS GIS Cut Line= 4
      2303878.65     13283146.56      2303479.03     13283348.06
      2303291.53     13283702.22      2303042.13     13284110.96
#Sta/Elev= 30
  4421.6  132.00  4438.8  131.72  4475.4  131.79  4489.8  132.50  4497.7  131.84
  4579.4  131.71  4592.5  132.49  4815.6  129.55  4825.8  129.87  4867.1  128.48
  4949.7  126.99  4966.0  125.76  5000.6  124.62  5003.3  124.12  5006.6  124.62
  5015.7  124.83  5032.0  126.56  5076.0  126.69  5164.1  128.73  5180.4  129.79
  5186.1  129.21  5224.4  130.75  5357.3  131.11  5363.4  131.95  5369.2  131.45
  5378.8  132.03  5384.7  131.68  5427.6  132.42  5661.9  132.66  5748.7  133.55
#Mann=4,-1,0
  4421.6    0.08       0  4438.8    0.05       0  5000.6   0.035       0
  5006.6    0.05       0
Bank Sta=5000.6,5006.6
Exp/Cntr=0.3,0.1

Type RM Length L Ch R = 1,8597,421,421,421
BEGIN DESCRIPTION:
Mapping XS 35ab0fea
END DESCRIPTION:
XS GIS Cut Line= 4
      2303715.13     13283028.62      2303215.14     13283195.28
      2302902.64     13283542.50      2302652.71     13283868.80
#Sta/Elev= 30
  4227.0  132.33  4340.2  131.68  4445.6  132.04  4498.3  131.02  4530.0  131.34
  4656.5  129.47  4681.4  129.59  4750.0  127.87  4810.0  127.28  4916.5  124.83
  4937.4  123.85  4991.2  123.13  4994.0  122.63  4997.2  123.13  5057.7  123.23
  5143.0  125.55  5199.8  128.06  5235.2  128.39  5285.1  129.67  5305.9  130.77
  5314.1  130.11  5320.4  130.84  5334.9  130.11  5377.8  131.20  5405.6  131.02
  5420.1  131.96  5470.0  132.25  5491.2  131.76  5528.1  132.49  5632.2  133.05
#Mann=3,-1,0
  4227.0    0.05       0  4991.2   0.035       0  4997.2    0.05       0
Bank Sta=4991.2,4997.2
Exp/Cntr=0.3,0.1

Type RM Length L Ch R = 1,8176,114,114,114
BEGIN DESCRIPTION:
UNT042 IN NURI 16.0
END DESCRIPTION:
XS GIS Cut Line= 3
      2303237.74     13282896.85      2302787.72     13283046.85
      2302687.71     13283146.86
#Sta/Elev= 30
  4559.5  129.52  4570.1  129.54  4580.6  129.26  4591.1  129.34  4664.9  128.39
  4802.0  125.07  4833.6  124.49  4875.8  124.02  4886.3  123.63  4907.4  122.10
  4917.9  121.15  4928.5  119.81  4930.8  119.18  4939.0  116.95  4949.5  115.77
  4960.1  113.95  4988.7  113.56  4991.5  113.06  4994.7  113.56  5023.3  114.85
  5062.1  115.38  5076.3  117.48  5090.4  119.89  5104.6  124.42  5118.7  126.24
  5132.9  136.93  5147.0  139.17  5161.1  138.63  5171.8  134.12  5175.3  134.12
#Mann=4,-1,0
  4559.5    0.05       0  4930.8     0.1       0  4988.7    0.07       0
  4994.7     0.1       0
Bank Sta=4988.7,4994.7
Exp/Cntr=0.3,0.1

Type RM Length L Ch R = 1,8062,112,112,112
BEGIN DESCRIPTION:
Mapping XS 962f7104
END DESCRIPTION:
XS GIS Cut Line= 4
      2303336.64     13282822.02      2302805.42     13282915.77
      2302617.92     13283019.93      2302562.36     13283658.80
#Sta/Elev= 30
  4396.0  130.51  4587.8  128.87  4683.5  127.25  4750.3  125.24  4841.7  123.74
  4862.0  122.25  4882.3  122.09  4912.4  120.41  4915.1  119.91  4918.4  120.41
  4922.9  122.43  4970.7  122.53  4986.7  121.04  4992.4  122.34  5008.4  121.62
  5024.8  122.23  5067.9  121.79  5133.1  123.74  5138.9  122.60  5149.9  123.39
  5176.9  121.55  5359.4  126.26  5427.9  128.40  5436.8  127.88  5441.9  128.68
  5518.2  129.21  5568.4  130.52  5598.5  130.10  5698.9  131.52  5791.2  131.63
#Mann=5,-1,0
  4396.0    0.05       0  4912.4   0.035       0  4918.4    0.05       0
  5024.8     0.1       0  5359.4    0.05       0
Bank Sta=4912.4,4918.4
Exp/Cntr=0.3,0.1

Type RM Length L Ch R = 1,7950,241,241,241
BEGIN DESCRIPTION:
UNT042 IN NURI 15.0
END DESCRIPTION:
XS GIS Cut Line= 4
      2303353.98     13282749.11      2302732.50     13282839.38
      2302437.72     13283009.52      2302437.72     13283696.86
#Sta/Elev= 30
  4288.5  130.35  4395.9  129.99  4444.1  129.04  4449.1  129.58  4608.1  127.52
  4759.7  124.50  4919.0  119.29  4924.6  118.62  5020.8  117.22  5026.6  117.30
  5036.6  119.25  5042.4  117.45  5049.0  117.97  5055.1  116.90  5057.9  116.40
  5061.1  116.90  5117.0  117.27  5144.7  119.76  5160.1  118.44  5192.0  119.01
  5233.8  120.19  5256.9  119.78  5284.2  121.03  5374.2  123.17  5444.2  123.19
  5504.2  124.33  5524.2  125.32  5584.2  125.38  5724.2  127.88  5944.2  129.86
#Mann=5,-1,0
  4288.5    0.05       0  5055.1   0.035       0  5061.1    0.05       0
  5144.7     0.1       0  5192.0    0.05       0
Bank Sta=5055.1,5061.1
Exp/Cntr=0.3,0.1

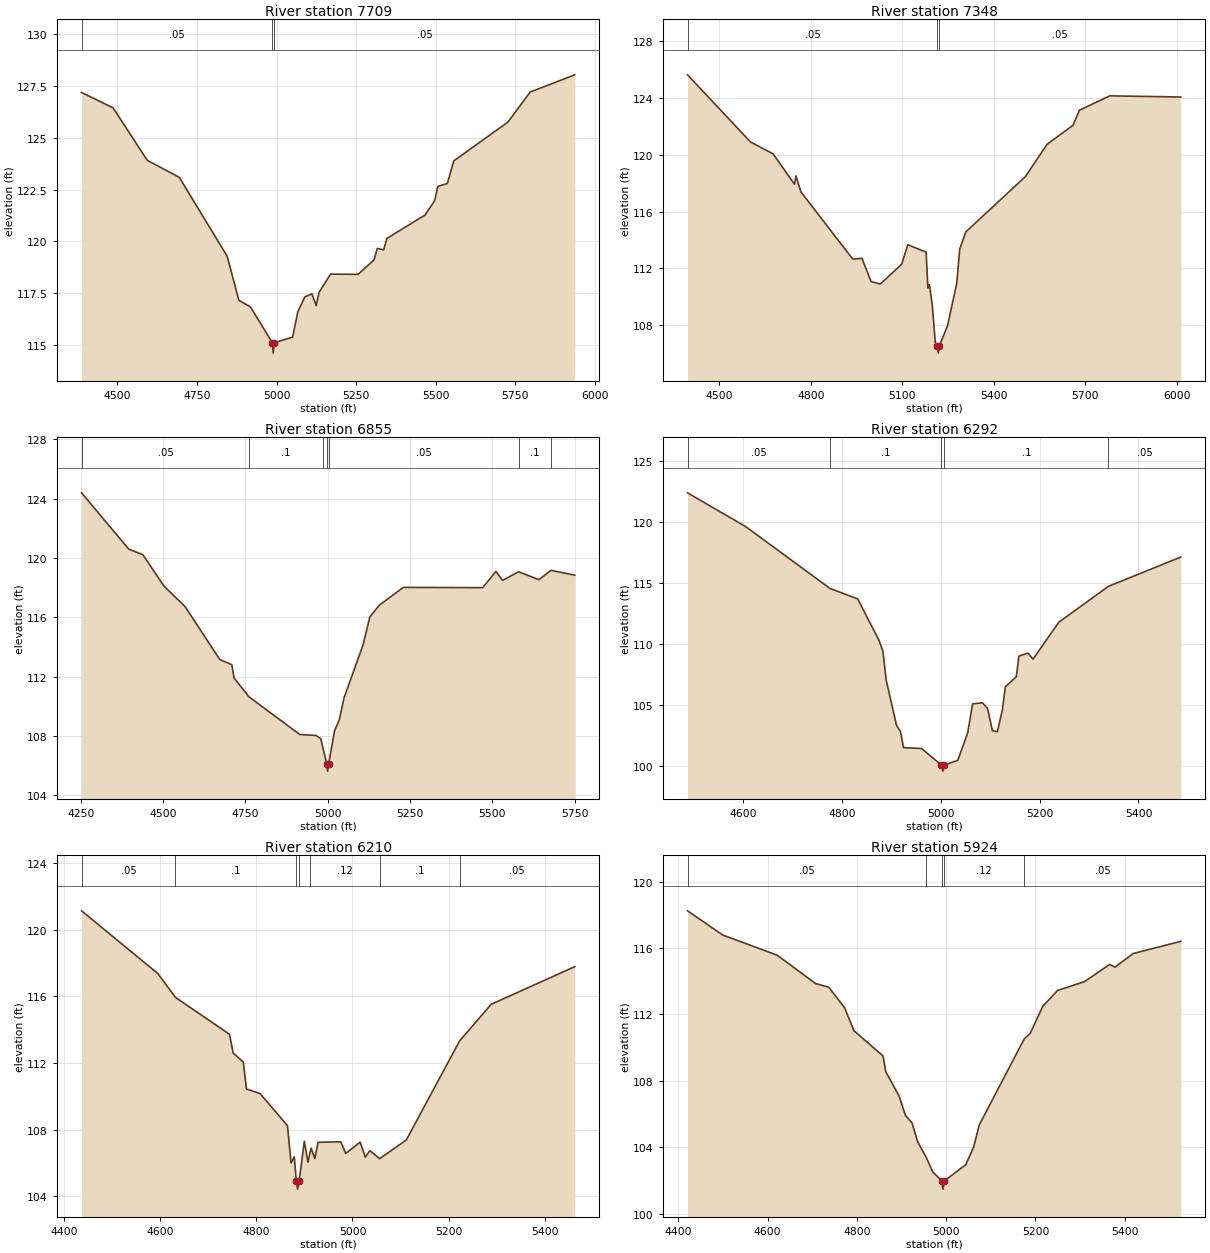
Type RM Length L Ch R = 1,7709,361,361,361
BEGIN DESCRIPTION:
Mapping XS e383f9ad
END DESCRIPTION:
XS GIS Cut Line= 4
      2303002.94     13282751.38      2302509.93     13282702.77
      2302350.21     13283008.33      2302377.99     13283716.70
#Sta/Elev= 30
  4387.5  127.18  4486.4  126.44  4593.7  123.91  4694.2  123.09  4844.9  119.28
  4881.5  117.16  4917.9  116.84  4986.8  115.11  4989.5  114.61  4992.8  115.11
  5050.3  115.38  5066.8  116.61  5088.9  117.32  5110.9  117.47  5124.5  116.90
  5133.0  117.53  5169.6  118.42  5256.2  118.41  5306.3  119.11  5316.3  119.66
  5336.3  119.59  5346.3  120.14  5466.4  121.27  5496.4  121.96  5506.4  122.65
  5536.4  122.79  5556.5  123.88  5726.6  125.75  5796.6  127.20  5936.6  128.03
#Mann=3,-1,0
  4387.5    0.05       0  4986.8   0.035       0  4992.8    0.05       0
Bank Sta=4986.8,4992.8
Exp/Cntr=0.3,0.1

Type RM Length L Ch R = 1,7348,493,493,493
BEGIN DESCRIPTION:
UNT042 IN NURI 14.0
END DESCRIPTION:
XS GIS Cut Line= 4
      2302912.70     13282626.38      2302634.93     13282459.72
      2301933.54     13282508.33      2301537.71     13282945.83
#Sta/Elev= 30
  4396.1  125.63  4602.6  120.90  4676.5  120.07  4746.6  117.93  4751.6  118.52
  4767.4  117.40  4937.8  112.66  4967.8  112.71  4997.9  111.08  5028.0  110.90
  5098.1  112.30  5118.2  113.67  5178.3  113.15  5184.1  110.62  5189.1  110.86
  5198.4  109.43  5208.4  106.79  5215.4  106.54  5218.2  106.04  5221.4  106.54
  5248.5  107.97  5278.6  110.95  5288.6  113.38  5308.7  114.58  5503.8  118.47
  5574.8  120.74  5660.0  122.08  5680.9  123.14  5780.3  124.15  6013.1  124.07
#Mann=3,-1,0
  4396.1    0.05       0  5215.4   0.035       0  5221.4    0.05       0
Bank Sta=5215.4,5221.4
Exp/Cntr=0.3,0.1

Type RM Length L Ch R = 1,6855,563,563,563
BEGIN DESCRIPTION:
UNT042 IN NURI 13.0
END DESCRIPTION:
XS GIS Cut Line= 3
      2302954.41     13282501.41      2302211.32     13281904.16
      2301669.67     13281841.66
#Sta/Elev= 30
  4252.2  124.39  4395.3  120.60  4438.5  120.22  4502.5  118.11  4566.5  116.73
  4672.1  113.16  4708.9  112.81  4715.3  111.92  4761.2  110.64  4915.1  108.11
  4964.9  108.04  4979.2  107.82  4985.7  107.19  4997.1  106.14  4999.9  105.64
  5003.1  106.14  5020.9  108.36  5035.3  109.09  5049.7  110.58  5107.3  114.13
  5128.1  116.02  5156.9  116.82  5230.0  118.02  5470.9  118.00  5511.2  119.09
  5531.3  118.49  5580.0  119.07  5642.0  118.54  5678.5  119.17  5750.8  118.84
#Mann=7,-1,0
  4252.2    0.05       0  4761.2     0.1       0  4985.7    0.05       0
  4997.1    0.03       0  5003.1    0.05       0  5580.0     0.1       0
  5678.5    0.16       0
Bank Sta=4997.1,5003.1
Exp/Cntr=0.3,0.1

Type RM Length L Ch R = 1,6292,82,82,82
BEGIN DESCRIPTION:
Mapping XS 5abaf345
END DESCRIPTION:
XS GIS Cut Line= 4
      2303156.10     13282283.81      2302850.56     13281908.82
      2302690.83     13281898.41      2302350.52     13281801.17
#Sta/Elev= 30
  4487.9  122.40  4605.3  119.63  4775.9  114.55  4832.2  113.68  4875.3  110.28
  4883.2  109.36  4889.7  107.02  4910.5  103.32  4918.4  102.81  4924.8  101.47
  4961.2  101.40  5001.5  100.04  5004.3   99.54  5007.5  100.04  5034.6  100.43
  5054.6  102.69  5064.6  105.07  5084.7  105.15  5094.7  104.69  5104.7  102.86
  5114.7  102.78  5124.8  104.58  5130.7  106.46  5153.0  107.30  5158.2  108.99
  5176.5  109.24  5186.8  108.74  5238.9  111.77  5339.4  114.72  5485.6  117.12
#Mann=5,-1,0
  4487.9    0.05       0  4775.9     0.1       0  5001.5    0.07       0
  5007.5     0.1       0  5339.4    0.05       0
Bank Sta=5001.5,5007.5
Exp/Cntr=0.3,0.1

Type RM Length L Ch R = 1,6210,286,286,286
BEGIN DESCRIPTION:
UNT042 IN NURI 12.0
END DESCRIPTION:
XS GIS Cut Line= 4
      2303232.76     13282176.27      2302840.40     13281825.57
      2302743.18     13281835.99      2302358.54     13281721.64
#Sta/Elev= 30
  4436.9  121.13  4595.7  117.36  4631.9  115.94  4744.5  113.72  4752.0  112.60
  4773.0  112.06  4779.7  110.44  4808.1  110.16  4864.9  108.24  4872.4  106.00
  4879.1  106.37  4883.3  104.93  4886.0  104.43  4889.3  104.93  4900.0  107.31
  4907.5  106.04  4911.8  106.59  4914.2  106.89  4921.8  106.26  4928.5  107.24
  4975.9  107.27  4986.0  106.57  5016.1  107.25  5026.7  106.35  5036.2  106.74
  5056.7  106.26  5112.0  107.38  5222.9  113.33  5288.4  115.52  5462.2  117.78
#Mann=7,-1,0
  4436.9    0.05       0  4631.9     0.1       0  4883.3    0.07       0
  4889.3     0.1       0  4911.8    0.12       0  5056.7     0.1       0
  5222.9    0.05       0
Bank Sta=4883.3,4889.3
Exp/Cntr=0.3,0.1

Type RM Length L Ch R = 1,5924,478,478,478
BEGIN DESCRIPTION:
UNT042 IN NURI 11.0
END DESCRIPTION:
XS GIS Cut Line= 3
      2303387.29     13281917.60      2302937.72     13281596.85
      2302392.57     13281506.14
#Sta/Elev= 30
  4420.6  118.24  4499.6  116.78  4621.3  115.57  4707.4  113.86  4736.9  113.64
  4772.5  112.40  4793.4  111.02  4858.5  109.50  4864.7  108.55  4894.2  107.11
  4908.9  105.91  4923.7  105.46  4936.0  104.34  4955.3  103.39  4969.8  102.52
  4990.1  101.98  4992.9  101.48  4996.1  101.98  5043.8  102.95  5061.6  104.02
  5074.2  105.35  5174.9  110.53  5188.4  110.87  5216.2  112.48  5249.3  113.44
  5310.2  113.98  5366.0  115.01  5378.4  114.85  5418.9  115.67  5525.5  116.40
#Mann=5,-1,0
  4420.6    0.05       0  4955.3    0.12       0  4990.1    0.07       0
  4996.1    0.12       0  5174.9    0.05       0
Bank Sta=4990.1,4996.1
Exp/Cntr=0.3,0.1

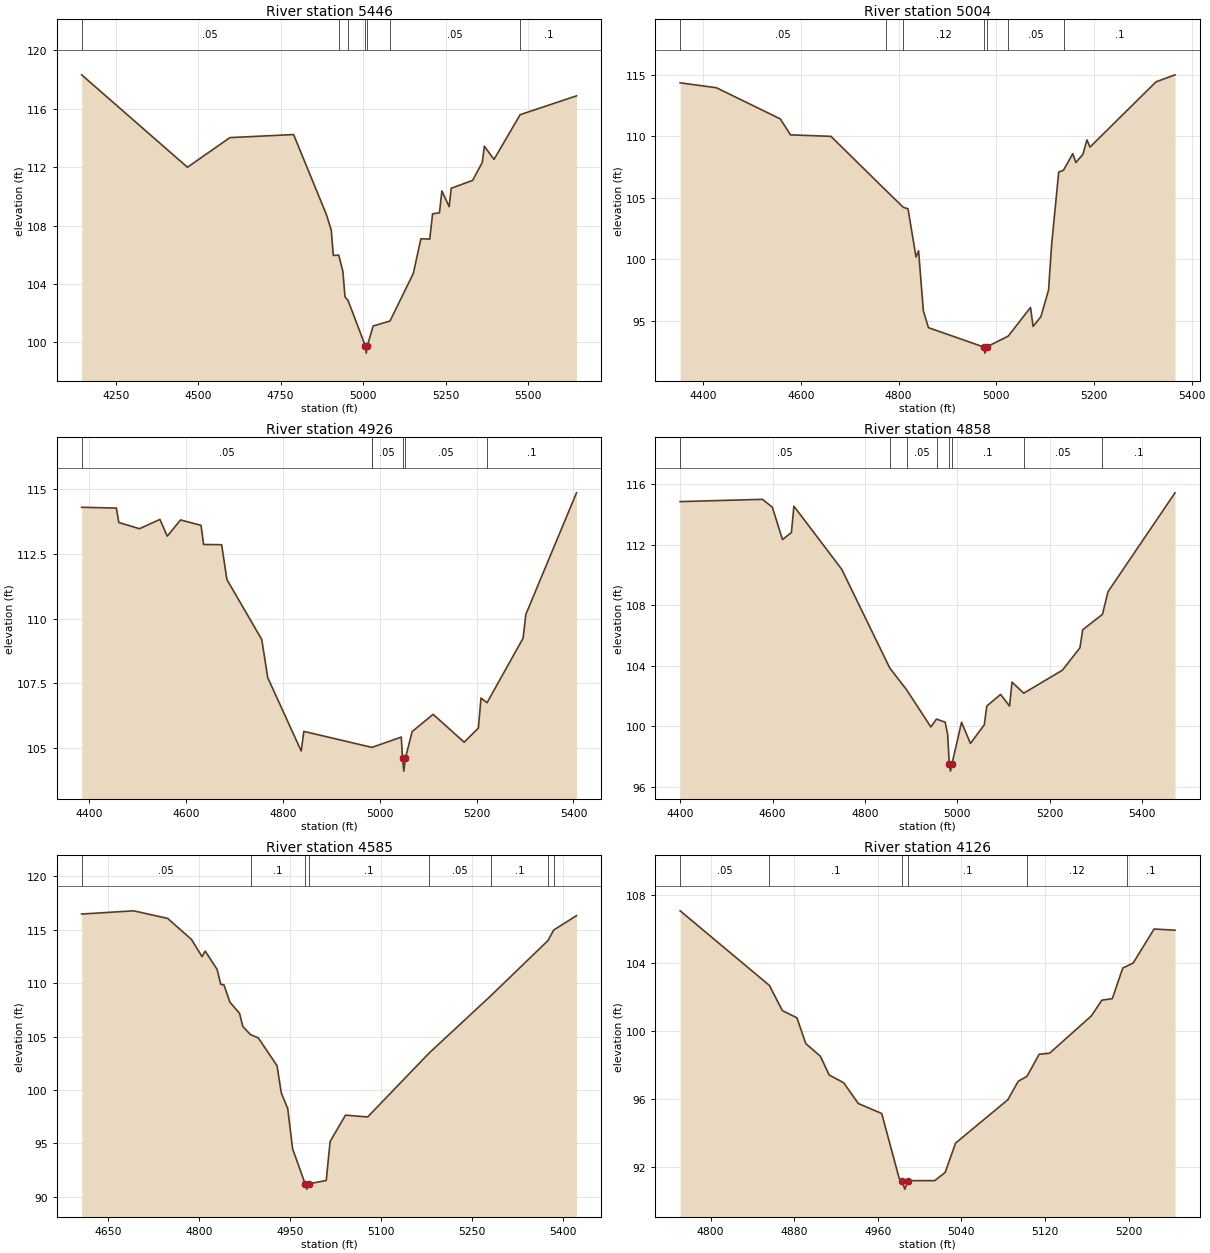
Type RM Length L Ch R = 1,5446,442,442,442
BEGIN DESCRIPTION:
UNT042 IN NURI 10.0
END DESCRIPTION:
XS GIS Cut Line= 3
      2303537.70     13281796.83      2303037.72     13281146.85
      2302487.72     13280746.86
#Sta/Elev= 30
  4147.0  118.32  4467.7  111.99  4596.4  114.02  4789.5  114.23  4889.1  108.74
  4903.6  107.70  4909.9  105.95  4926.4  105.97  4939.0  104.85  4945.3  103.12
  4954.7  102.86  5006.9   99.76  5009.7   99.26  5012.9   99.76  5030.8  101.12
  5081.7  101.46  5152.5  104.72  5175.3  107.09  5202.3  107.07  5210.8  108.80
  5231.7  108.87  5239.1  110.37  5261.1  109.29  5267.3  110.55  5332.2  111.09
  5361.5  112.32  5367.7  113.43  5397.1  112.53  5476.3  115.59  5647.1  116.88
#Mann=7,-1,0
  4147.0    0.05       0  4926.4    0.07       0  4954.7    0.12       0
  5006.9    0.07       0  5012.9    0.12       0  5081.7    0.05       0
  5476.3     0.1       0
Bank Sta=5006.9,5012.9
Exp/Cntr=0.3,0.1

Type RM Length L Ch R = 1,5004,78,78,78
BEGIN DESCRIPTION:
Mapping XS b1d762a0
END DESCRIPTION:
XS GIS Cut Line= 3
      2303364.45     13281342.88      2303145.70     13280629.31
      2302937.40     13280462.67
#Sta/Elev= 30
  4352.8  114.33  4427.0  113.93  4557.8  111.40  4578.7  110.10  4661.5  109.98
  4773.7  105.60  4809.7  104.21  4819.3  104.09  4835.7  100.17  4840.9  100.68
  4850.7   95.81  4861.1   94.43  4974.1   92.86  4976.9   92.36  4980.1   92.86
  5024.4   93.74  5070.1   96.07  5075.4   94.53  5091.3   95.32  5107.0   97.48
  5113.4  101.22  5127.8  107.07  5137.7  107.23  5156.6  108.57  5163.0  107.85
  5177.5  108.53  5185.5  109.69  5191.9  109.11  5327.1  114.41  5365.9  114.98
#Mann=7,-1,0
  4352.8    0.05       0  4773.7    0.07       0  4809.7    0.12       0
  4974.1    0.07       0  4980.1    0.12       0  5024.4    0.05       0
  5137.7     0.1       0
Bank Sta=4974.1,4980.1
Exp/Cntr=0.3,0.1

Type RM Length L Ch R = 1,4926,68,68,68
BEGIN DESCRIPTION:
UNT042 IN NURI 9.0
END DESCRIPTION:
XS GIS Cut Line= 4
      2303409.69     13281278.98      2303309.15     13280849.88
      2303137.27     13280438.42      2303007.02     13280401.95
#Sta/Elev= 30
  4384.3  114.31  4456.0  114.28  4461.1  113.72  4503.6  113.48  4546.0  113.84
  4561.1  113.19  4588.5  113.82  4630.9  113.61  4636.1  112.87  4673.4  112.86
  4684.3  111.51  4756.2  109.19  4768.6  107.71  4837.7  104.87  4843.1  105.63
  4983.6  105.01  4984.0  105.01  5044.4  105.41  5046.9  104.59  5049.6  104.09
  5052.9  104.59  5066.7  105.62  5110.1  106.29  5174.3  105.21  5203.6  105.76
  5209.0  106.92  5221.5  106.74  5295.9  109.24  5301.6  110.16  5406.2  114.87
#Mann=6,-1,0
  4384.3    0.05       0  4983.6    0.12       0  4984.0    0.05       0
  5046.9    0.04       0  5052.9    0.05       0  5221.5     0.1       0
Bank Sta=5046.9,5052.9
Exp/Cntr=0.3,0.1

Type RM Length L Ch R = 1,4858,273,273,273
BEGIN DESCRIPTION:
Mapping XS 2ff048b3
END DESCRIPTION:
XS GIS Cut Line= 3
      2303520.68     13281223.03      2303213.40     13280426.18
      2303015.45     13280337.62
#Sta/Elev= 30
  4400.0  114.84  4578.1  114.99  4599.5  114.47  4621.5  112.33  4640.8  112.80
  4646.1  114.54  4749.6  110.37  4853.7  103.84  4890.0  102.41  4942.5   99.95
  4954.8  100.47  4973.7  100.26  4979.0   99.43  4982.4   97.53  4985.1   97.03
  4988.4   97.53  5009.0  100.26  5028.2   98.86  5058.2  100.09  5063.6  101.33
  5093.5  102.10  5112.8  101.33  5118.2  102.91  5143.5  102.18  5227.3  103.70
  5265.2  105.18  5271.2  106.37  5313.9  107.39  5326.0  108.89  5470.9  115.42
#Mann=8,-1,0
  4400.0    0.05       0  4853.7     0.1       0  4890.0    0.05       0
  4954.8     0.1       0  4982.4    0.07       0  4988.4     0.1       0
  5143.5    0.05       0  5313.9     0.1       0
Bank Sta=4982.4,4988.4
Exp/Cntr=0.3,0.1

Type RM Length L Ch R = 1,4585,459,459,459
BEGIN DESCRIPTION:
UNT042 IN NURI 8.0
END DESCRIPTION:
XS GIS Cut Line= 2
      2303798.73     13280558.21      2303027.92     13280287.39
#Sta/Elev= 30
  4605.8  116.48  4691.7  116.78  4747.8  116.07  4787.1  114.10  4804.5  112.49
  4809.8  113.01  4829.5  111.29  4835.4  109.90  4840.7  109.85  4850.7  108.21
  4866.4  107.19  4871.9  105.94  4884.6  105.18  4897.4  104.88  4928.4  102.27
  4935.4   99.72  4946.0   98.27  4954.1   94.48  4974.8   91.21  4977.6   90.71
  4980.8   91.21  5009.6   91.52  5016.0   95.17  5041.4   97.64  5078.0   97.47
  5179.0  103.43  5282.0  108.86  5375.8  114.00  5385.1  114.98  5422.8  116.33
#Mann=8,-1,0
  4605.8    0.05       0  4884.6     0.1       0  4974.8    0.07       0
  4980.8     0.1       0  5179.0    0.05       0  5282.0     0.1       0
  5375.8    0.08       0  5385.1     0.1       0
Bank Sta=4974.8,4980.8
Exp/Cntr=0.3,0.1

Type RM Length L Ch R = 1,4126,432,432,432
BEGIN DESCRIPTION:
UNT042 IN NURI 7.0
END DESCRIPTION:
XS GIS Cut Line= 3
      2303787.72     13280096.86      2303587.72     13279996.85
      2303337.73     13279996.85
#Sta/Elev= 30
  4770.8  107.09  4856.2  102.70  4868.6  101.22  4882.6  100.79  4891.0   99.28
  4905.0   98.53  4913.4   97.43  4927.3   96.97  4941.3   95.75  4963.7   95.16
  4980.4   91.35  4983.0   91.21  4985.8   90.71  4989.0   91.21  5014.4   91.21
  5024.4   91.69  5034.4   93.42  5084.4   95.97  5094.4   97.06  5102.8   97.35
  5114.4   98.65  5124.4   98.71  5164.4  100.91  5174.4  101.83  5184.4  101.92
  5194.4  103.72  5198.5  103.84  5204.4  104.02  5224.4  106.02  5244.4  105.95
#Mann=6,-1,0
  4770.8    0.05       0  4856.2     0.1       0  4983.0    0.07       0
  4989.0     0.1       0  5102.8    0.12       0  5198.5     0.1       0
Bank Sta=4983,4989
Exp/Cntr=0.3,0.1

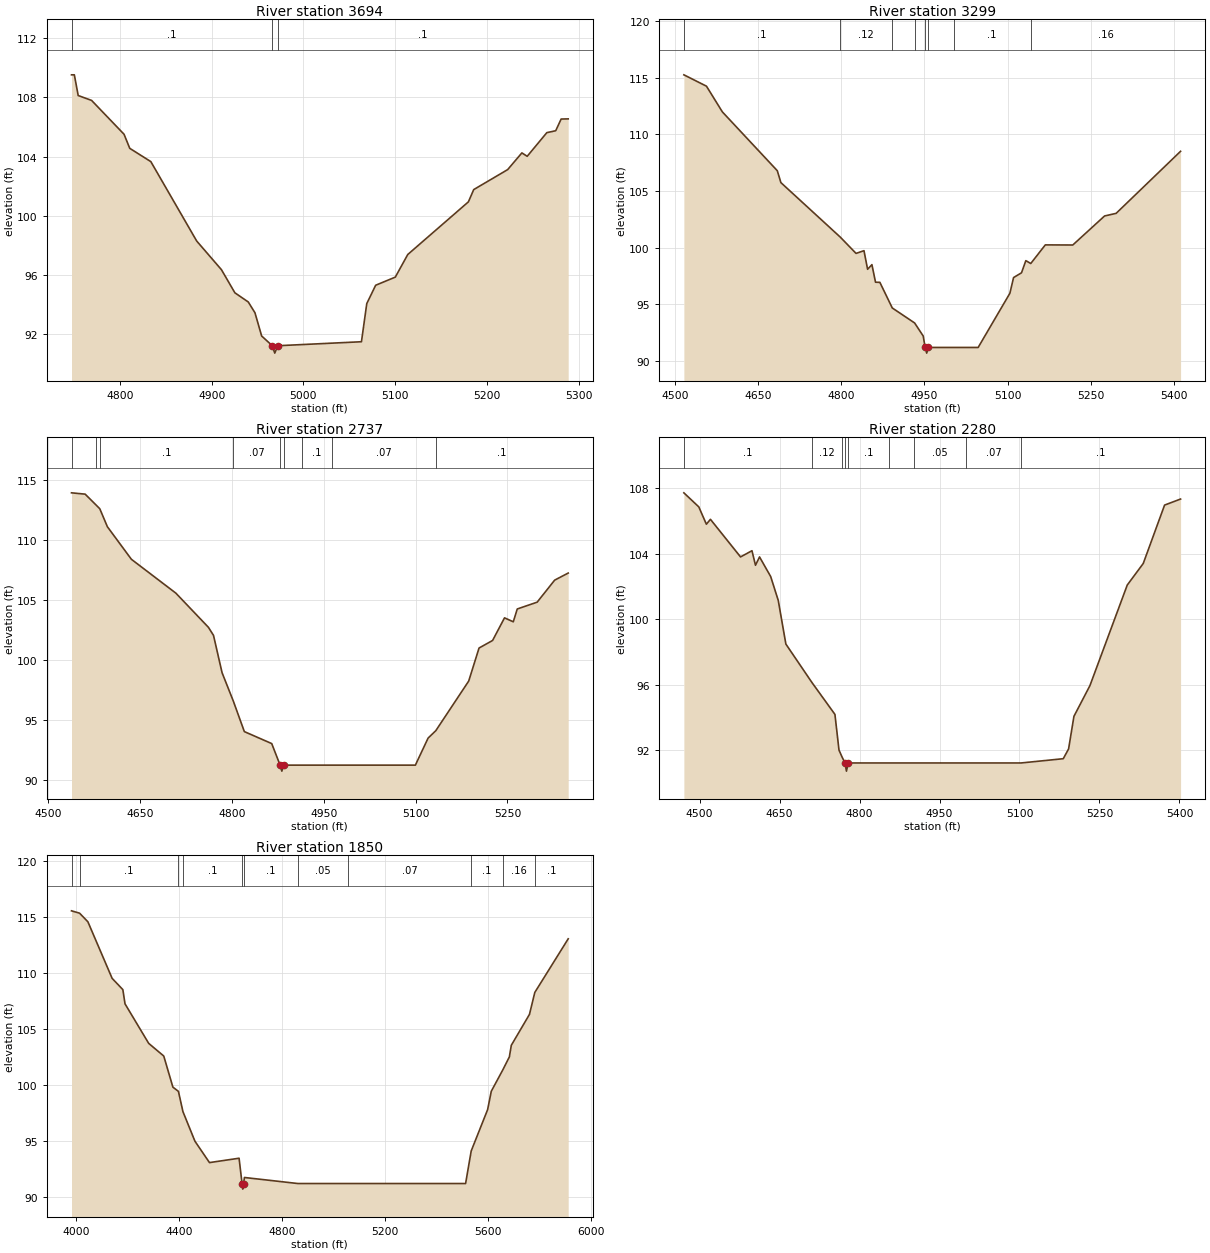
Type RM Length L Ch R = 1,3694,395,395,395
BEGIN DESCRIPTION:
UNT042 IN NURI 6.0
END DESCRIPTION:
XS GIS Cut Line= 3
      2303937.72     13279746.85      2303737.72     13279596.85
      2303587.74     13279346.89
#Sta/Elev= 30
  4747.2  109.53  4750.3  109.53  4754.5  108.13  4769.1  107.80  4804.5  105.51
  4810.7  104.56  4833.7  103.66  4883.7   98.29  4910.7   96.35  4925.3   94.79
  4939.9   94.17  4947.2   93.44  4954.5   91.87  4966.1   91.21  4968.8   90.71
  4972.1   91.21  5063.3   91.48  5069.1   94.06  5078.8   95.30  5100.2   95.85
  5113.8   97.38  5179.9  100.94  5185.7  101.77  5222.7  103.12  5238.2  104.25
  5244.0  104.02  5265.4  105.62  5275.1  105.75  5281.0  106.54  5288.7  106.55
#Mann=3,-1,0
  4747.2     0.1       0  4966.1    0.07       0  4972.1     0.1       0
Bank Sta=4966.1,4972.1
Exp/Cntr=0.3,0.1

Type RM Length L Ch R = 1,3299,562,562,562
BEGIN DESCRIPTION:
UNT042 IN NURI 5.0
END DESCRIPTION:
XS GIS Cut Line= 2
      2304361.20     13279610.27      2303673.72     13279037.37
#Sta/Elev= 30
  4516.5  115.24  4557.2  114.24  4585.9  111.97  4684.8  106.79  4691.3  105.74
  4798.2  100.94  4826.7   99.50  4841.0   99.74  4847.5   98.10  4855.3   98.51
  4861.8   96.96  4869.6   96.95  4892.0   94.69  4932.2   93.37  4947.7   92.22
  4951.2   91.21  4954.0   90.71  4957.2   91.21  5002.6   91.21  5046.7   91.21
  5103.9   95.99  5110.5   97.37  5124.8   97.79  5132.6   98.86  5141.5   98.61
  5167.7  100.25  5217.2  100.24  5274.5  102.80  5295.3  103.03  5411.4  108.50
#Mann=8,-1,0
  4516.5     0.1       0  4798.2    0.12       0  4892.0     0.1       0
  4932.2    0.12       0  4951.2    0.07       0  4957.2    0.12       0
  5002.6     0.1       0  5141.5    0.16       0
Bank Sta=4951.2,4957.2
Exp/Cntr=0.3,0.1

Type RM Length L Ch R = 1,2737,457,457,457
BEGIN DESCRIPTION:
UNT042 IN NURI 4.0
END DESCRIPTION:
XS GIS Cut Line= 3
      2304587.70     13279296.81      2304387.72     13278896.85
      2304037.69     13278796.85
#Sta/Elev= 30
  4538.1  113.95  4560.4  113.84  4578.1  112.94  4584.3  112.62  4596.7  111.12
  4635.9  108.40  4708.6  105.57  4761.7  102.72  4770.0  102.05  4784.0   98.93
  4802.3   96.57  4820.4   94.01  4865.1   93.01  4878.8   91.21  4881.6   90.71
  4884.8   91.21  4914.4   91.21  4963.5   91.21  5099.7   91.21  5120.5   93.47
  5133.1   94.09  5186.8   98.23  5203.7  100.99  5225.8  101.62  5245.3  103.51
  5259.6  103.18  5266.1  104.25  5298.6  104.82  5327.2  106.66  5349.3  107.25
#Mann=9,-1,0
  4538.1     0.1       0  4578.1    0.16       0  4584.3     0.1       0
  4802.3    0.07       0  4878.8    0.07       0  4884.8    0.07       0
  4914.4     0.1       0  4963.5    0.07       0  5133.1     0.1       0
Bank Sta=4878.8,4884.8
Exp/Cntr=0.3,0.1

Type RM Length L Ch R = 1,2280,430,430,430
BEGIN DESCRIPTION:
UNT042 IN NURI 3.0
END DESCRIPTION:
XS GIS Cut Line= 3
      2304937.73     13278896.86      2304587.72     13278496.85
      2304187.74     13278496.85
#Sta/Elev= 30
  4470.6  107.73  4498.6  106.87  4512.8  105.81  4520.4  106.11  4576.9  103.81
  4598.3  104.19  4604.9  103.30  4612.5  103.81  4633.4  102.61  4647.6  101.15
  4661.9   98.48  4711.2   96.11  4753.9   94.18  4761.5   92.00  4767.3   91.57
  4772.8   91.21  4775.5   90.71  4778.8   91.21  4855.5   91.21  4902.0   91.21
  4999.7   91.21  5103.3   91.21  5182.1   91.47  5192.1   92.07  5202.1   94.06
  5232.1   95.94  5302.1  102.09  5332.1  103.41  5372.1  106.98  5402.1  107.35
#Mann=9,-1,0
  4470.6     0.1       0  4711.2    0.12       0  4767.3     0.1       0
  4772.8    0.07       0  4778.8     0.1       0  4855.5    0.07       0
  4902.0    0.05       0  4999.7    0.07       0  5103.3     0.1       0
Bank Sta=4772.8,4778.8
Exp/Cntr=0.3,0.1

Type RM Length L Ch R = 1,1850,0,0,0
BEGIN DESCRIPTION:
UNT042 IN NURI 1.0
END DESCRIPTION:
XS GIS Cut Line= 4
      2305337.72     13278746.85      2304842.93     13278075.30
      2304245.70     13278075.30      2303919.33     13278450.29
#Sta/Elev= 30
  3982.6  115.57  4014.0  115.36  4046.3  114.59  4140.3  109.54  4182.0  108.53
  4190.4  107.26  4282.3  103.73  4340.8  102.60  4376.3   99.82  4397.8   99.44
  4415.3   97.63  4461.9   94.99  4518.3   93.08  4633.2   93.47  4644.8   91.21
  4647.6   90.71  4650.8   91.21  4654.0   91.75  4861.6   91.21  5058.0   91.21
  5512.7   91.21  5534.5   94.12  5598.2   97.81  5612.4   99.45  5657.6  101.38
  5682.6  102.52  5690.2  103.56  5760.7  106.32  5781.4  108.28  5911.1  113.07
#Mann=11,-1,0
  3982.6    0.16       0  4014.0     0.1       0  4397.8    0.12       0
  4415.3     0.1       0  4644.8   0.033       0  4650.8     0.1       0
  4861.6    0.05       0  5058.0    0.07       0  5534.5     0.1       0
  5657.6    0.16       0  5781.4     0.1       0
Bank Sta=4644.8,4650.8
Exp/Cntr=0.3,0.1

Chan Stop Cuts=-1