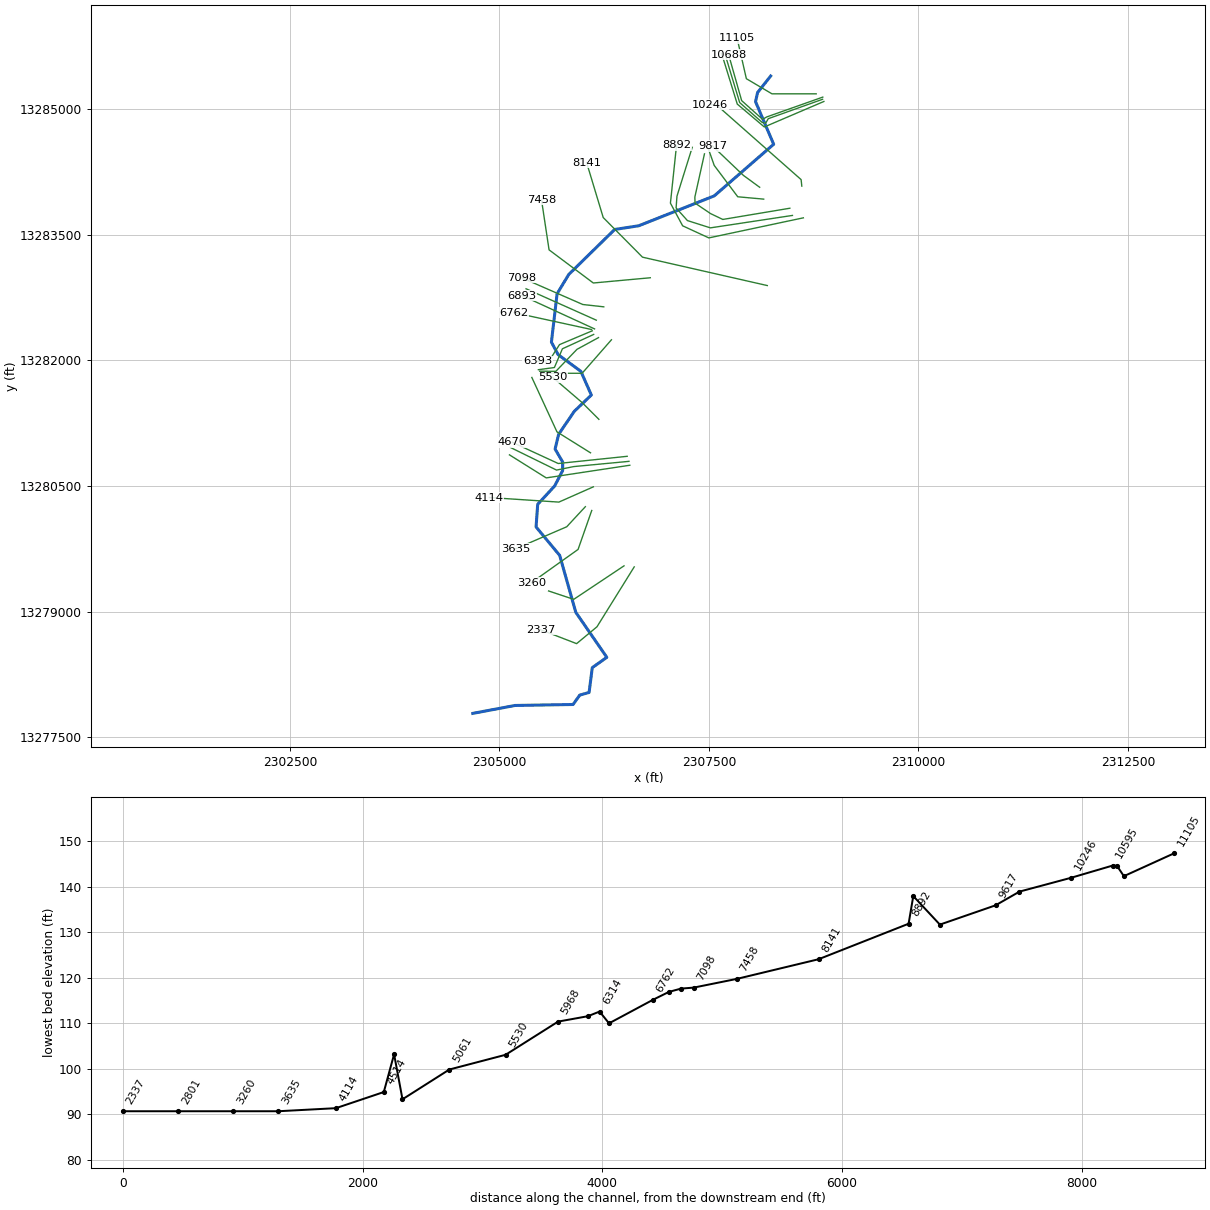
--- UNT043 IN NURI.prj (project) ---

Proj Title=UNT043 IN NURI Base Level Engineering
Current Plan=p01
Default Exp/Contr=0.3,0.1
English Units
Geom File=g01
Flow File=f01
Plan File=p01
Y Axis Title=Elevation
X Axis Title(PF)=Main Channel Distance
X Axis Title(XS)=Station
BEGIN DESCRIPTION:
UNT043 IN NURI
END DESCRIPTION:
DSS Export Rating Curves= 0
DSS Export Rating Curve Sorted= 0
DSS Export Volume Flow Curves= 0
DXF OffsetX= 0
DXF OffsetY= 0
DXF ScaleX= 1
DXF ScaleY= 10

--- UNT043 IN NURI.p01 (plan) ---

Plan Title=Multiple Run
Short Identifier=Multiple
Geom File=g01
Flow File=f01
Subcritical Flow
K Sum by GR= 0
Std Step Tol= 0.01
Critical Tol= 0.01
Num of Std Step Trials= 20
Max Error Tol= 0.3
Flow Tol Ratio= 0.001
Split Flow NTrial= 30
Split Flow Tol= 0.02
Split Flow Ratio= 0.02
Log Output Level= 0
Friction Slope Method= 1
Unsteady Friction Slope Method= 2
Unsteady Bridges Friction Slope Method= 1
Parabolic Critical Depth
Global Vel Dist=  1 , 1 , 1
Global Log Level= 0
CheckData=True
Encroach Param= -1, 0, 0, 0
BEGIN DESCRIPTION:
Multiple Run
END DESCRIPTION:

--- UNT043 IN NURI.f01 (steady flow) ---

Flow Title=Multiple
Number of Profiles=7
Profile Names=10-year,25-year,50-year,1pct_min,100-year,1pct_plu,500-year
River Rch & RM= UNT043 IN NURI,Reach-1,11105
     581     821    1022     931    1259    1702    1914
River Rch & RM= UNT043 IN NURI,Reach-1,10246
    1200    1758    2242    2084    2818    3811    4473
Boundary for River Rch & Prof#=UNT043 IN NURI,Reach-1,1
Up Type=0
Dn Type=3
Dn Slope=0.005
Boundary for River Rch & Prof#=UNT043 IN NURI,Reach-1,2
Up Type=0
Dn Type=3
Dn Slope=0.005
Boundary for River Rch & Prof#=UNT043 IN NURI,Reach-1,3
Up Type=0
Dn Type=3
Dn Slope=0.005
Boundary for River Rch & Prof#=UNT043 IN NURI,Reach-1,4
Up Type=0
Dn Type=3
Dn Slope=0.005
Boundary for River Rch & Prof#=UNT043 IN NURI,Reach-1,5
Up Type=0
Dn Type=3
Dn Slope=0.005
Boundary for River Rch & Prof#=UNT043 IN NURI,Reach-1,6
Up Type=0
Dn Type=3
Dn Slope=0.005
Boundary for River Rch & Prof#=UNT043 IN NURI,Reach-1,7
Up Type=0
Dn Type=3
Dn Slope=0.005

--- UNT043 IN NURI.g01 (geometry) ---

Geom Title=Existing Conditions
Program Version=4.10

River Reach=UNT043 IN NURI  ,Reach-1
Reach XY= 30
      2308237.77     13285396.81      2308081.58     13285199.69
      2308057.28     13285090.52       2308273.6     13284581.89
      2307564.81     13283965.31      2306663.77     13283608.54
      2306376.09     13283564.13      2305828.14     13283026.75
      2305688.79     13282795.62      2305621.31     13282218.43
      2305700.94     13282069.93      2305973.03     13281869.68
      2306097.72     13281586.85      2305895.05     13281393.36
      2305707.53     13281117.96      2305665.16     13280941.57
      2305756.14     13280786.71      2305754.75     13280683.93
      2305659.97     13280500.78      2305457.65     13280281.75
      2305438.13     13280011.35      2305720.03     13279672.13
      2305912.04     13278992.27      2306282.61     13278454.51
        2306109.     13278331.25      2306070.88     13278035.01
      2305959.58     13278003.47      2305879.83     13277891.22
      2305187.12      13277879.5      2304683.25     13277785.06

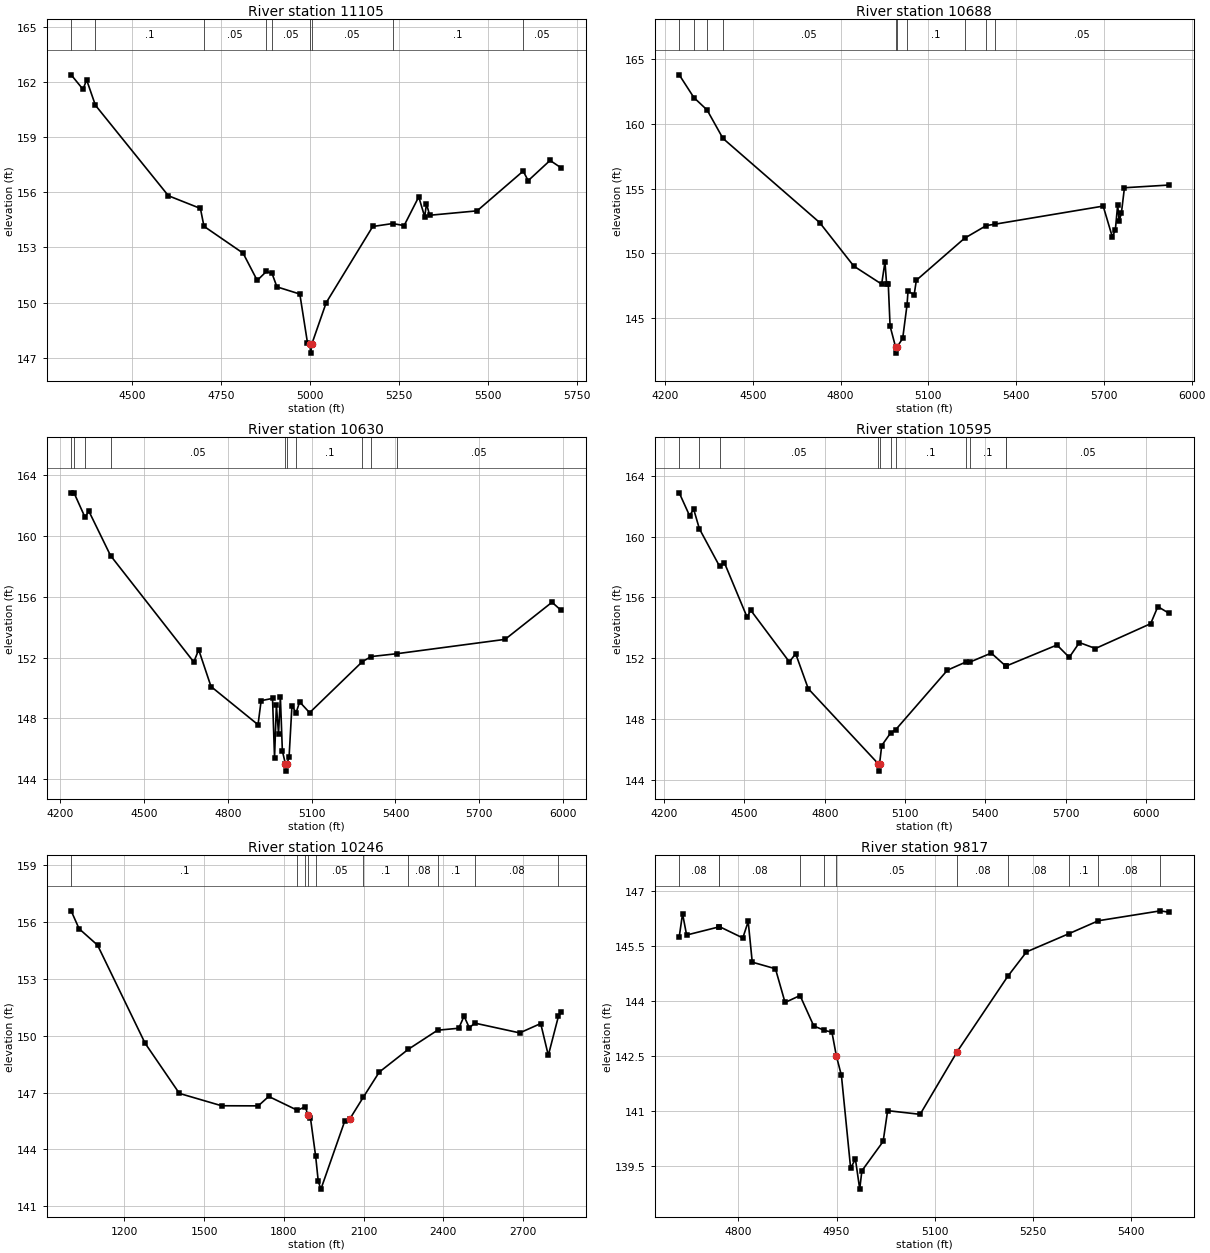
Type RM Length L Ch R = 1 ,11105   ,417,417,417
BEGIN DESCRIPTION:
UNT043 IN NURI 19.0
END DESCRIPTION:
XS GIS Cut Line= 4
      2308781.13     13285184.22      2308253.33     13285184.22
      2307947.78     13285364.78      2307837.72     13285846.86
#Sta/Elev= 30
  4329.2  162.38  4362.6  161.59  4372.6  162.11  4397.3  160.73  4602.6  155.81
  4692.6  155.12  4702.6  154.15  4812.6  152.69  4852.3  151.21  4878.2   151.7
  4893.9  151.59  4907.7  150.86  4972.1  150.47  4993.5  147.83  4999.9  147.76
  5002.7  147.26  5005.9  147.76  5046.2     150  5177.1  154.14  5232.8   154.3
  5265.3  154.19  5306.4  155.75  5323.1  154.67  5328.2  155.37  5337.1  154.75
  5470.5  154.99    5600  157.15  5614.1  156.63  5675.6  157.73  5706.4  157.33
#Mann= 9 ,-1 , 0
  4329.2     .05       0  4397.3      .1       0  4702.6     .05       0
  4878.2      .1       0  4893.9     .05       0  4999.9    .035       0
  5005.9     .05       0  5232.8      .1       0    5600     .05       0
Bank Sta=4999.9,5005.9
XS Rating Curve= 0 ,0
Exp/Cntr=0.3,0.1

Type RM Length L Ch R = 1 ,10688   ,58,58,58
BEGIN DESCRIPTION:
Mapping XS e4f2f436
END DESCRIPTION:
XS GIS Cut Line= 5
      2308860.09     13285145.09      2308190.81     13284908.11
      2308141.33     13284879.46      2307891.33     13285103.42
      2307735.59     13285653.68
#Sta/Elev= 30
  4248.1  163.81  4298.2  162.05  4343.3  161.09  4397.6  158.89    4728  152.38
  4844.7  149.01  4940.2  147.61  4951.5  149.34  4957.1  147.62  4962.8  147.62
    4969  144.36  4987.5  142.77  4990.3  142.27  4993.5  142.77  5012.1  143.41
    5027  146.02  5030.3  147.07  5051.3  146.79  5058.8  147.91  5223.5  151.16
  5297.7  152.14  5327.5  152.25  5697.5  153.65  5728.6  151.28    5739  151.78
    5747  153.74  5752.2  152.49  5759.8  153.12  5770.2  155.07  5922.8  155.28
#Mann= 10 ,-1 , 0
  4248.1      .1       0  4298.2     .05       0  4343.3      .1       0
  4397.6     .05       0  4987.5    .035       0  4993.5     .05       0
    5027      .1       0  5223.5     .05       0  5297.7      .1       0
  5327.5     .05       0
Bank Sta=4987.5,4993.5
XS Rating Curve= 0 ,0
Exp/Cntr=0.3,0.1

Type RM Length L Ch R = 1 ,10630   ,35,35,35
BEGIN DESCRIPTION:
Mapping XS fdc23efa
END DESCRIPTION:
XS GIS Cut Line= 6
      2308857.51     13285119.06      2308209.03     13284887.27
      2308177.78     13284832.59      2308136.12       13284843.
      2307867.89     13285079.98      2307696.01      13285647.7
#Sta/Elev= 30
  4239.2   162.8  4249.4  162.83  4288.6  161.23  4302.7  161.62    4380  158.71
  4678.1  151.71  4695.6  152.52  4739.7   150.1    4908  147.59  4919.1  149.17
  4959.9  149.32  4967.1  145.42  4973.7  148.87  4981.4     147    4988  149.41
  4995.1  145.87  5005.7  145.04  5008.5  144.54  5011.7  145.04  5019.1  145.46
  5029.4  148.84  5044.3  148.38  5056.9  149.09  5092.6  148.38  5281.6  151.74
  5313.4  152.07  5406.1  152.26  5792.2   153.2  5960.2  155.64  5992.4  155.11
#Mann= 10 ,-1 , 0
  4239.2      .1       0  4249.4     .05       0  4288.6      .1       0
    4380     .05       0  5005.7    .035       0  5011.7     .05       0
  5044.3      .1       0  5281.6     .05       0  5313.4      .1       0
  5406.1     .05       0
Bank Sta=5005.7,5011.7
XS Rating Curve= 0 ,0
Exp/Cntr=0.3,0.1

Type RM Length L Ch R = 1 ,10595   ,349,349,349
BEGIN DESCRIPTION:
Mapping XS c5f074dc
END DESCRIPTION:
XS GIS Cut Line= 4
      2308873.06     13285092.99      2308162.16     13284788.31
      2307839.24     13285061.75      2307652.23     13285666.94
#Sta/Elev= 30
  4256.2  162.87  4294.6  161.38  4310.4  161.78  4331.5  160.51  4407.2  158.04
  4425.2  158.27  4509.9   154.7  4523.1  155.17  4667.6  151.77  4691.2  152.31
  4738.3  150.01  4998.8   145.1  5001.6   144.6  5004.8   145.1  5012.7  146.28
  5045.7   147.1  5065.4  147.33  5258.3  151.23  5329.3  151.78    5341  151.75
    5422  152.35  5476.4  151.49  5477.7   151.5  5667.4  152.88  5713.3  152.07
  5751.2  153.04  5811.2  152.65  6017.4  154.28  6044.2   155.4  6086.2  154.96
#Mann= 11 ,-1 , 0
  4256.2     .05       0  4331.5      .1       0  4407.2     .05       0
  4998.8    .035       0  5004.8     .05       0  5045.7     .05       0
  5065.4      .1       0  5329.3     .08       0    5341      .1       0
  5476.4     .08       0  5477.7     .05       0
Bank Sta=4998.8,5004.8
XS Rating Curve= 0 ,0
Exp/Cntr=0.3,0.1

Type RM Length L Ch R = 1 ,10246   ,429,429,429
BEGIN DESCRIPTION:
Mapping XS 689f95e4
END DESCRIPTION:
XS GIS Cut Line= 4
      2308609.37     13284081.72      2308601.25     13284159.48
      2307591.85     13285051.34       2307513.8     13285055.55
#Sta/Elev= 30
    1000156.5952 1029.78155.6502 1099.26154.7836 1277.94149.6085 1406.98146.9576
  1565.8146.3057 1703.74146.2994 1742.98 146.798 1850.91146.0659 1880.35146.2519
 1890.16145.8327 1899.97145.6679 1919.59143.6372 1929.41142.3095 1939.38141.9045
  2029.1145.5017 2049.04145.6326 2098.89146.7604  2158.7148.0818 2268.37149.2894
 2378.03150.2928 2457.79150.3973 2477.73151.0344 2497.66150.4176  2517.6150.6694
 2687.08150.1515    2766 150.645 2794.64148.9652 2832.84151.0396 2842.39151.2293
#Mann= 10 ,-1 , 0
    1000      .1       0 1850.91     .07       0 1880.35      .1       0
 1890.16     .05       0 1919.59     .05       0 2098.89      .1       0
 2268.37     .08       0 2378.03      .1       0  2517.6     .08       0
 2832.84      .1       0
Bank Sta=1890.16,2049.04
XS Rating Curve= 0 ,0
Exp/Cntr=0.3,0.1

Type RM Length L Ch R = 1 ,9817    ,200,200,200
BEGIN DESCRIPTION:
Mapping XS 00920c8e
END DESCRIPTION:
XS GIS Cut Line= 3
       2308106.2     13284068.35      2307911.78     13284210.69
      2307543.76     13284561.36
#Sta/Elev= 30
  4709.4  145.76  4714.5  146.39  4720.7  145.81  4769.8  146.03  4770.8  146.04
  4806.7  145.73  4814.9  146.18  4821.1  145.07  4856.6  144.89  4871.3  143.97
  4894.2  144.16  4915.2  143.33  4931.5  143.21    4943  143.16  4949.8  142.51
  4957.5  141.98  4971.6  139.45  4978.9   139.7  4985.5  138.88  4988.8  139.38
  5021.3  140.18  5028.2  141.02  5077.9  140.92  5134.6  142.63  5211.8  144.68
  5240.6  145.35  5305.9  145.85  5350.6   146.2  5445.5  146.47  5458.7  146.43
#Mann= 11 ,-1 , 0
  4709.4     .08       0  4769.8      .1       0  4770.8     .08       0
  4894.2      .1       0  4931.5     .08       0  4949.8     .05       0
  5134.6     .08       0  5211.8     .08       0  5305.9      .1       0
  5350.6     .08       0  5445.5      .1       0
Bank Sta=4949.8,5134.6
XS Rating Curve= 0 ,0
Exp/Cntr=0.3,0.1

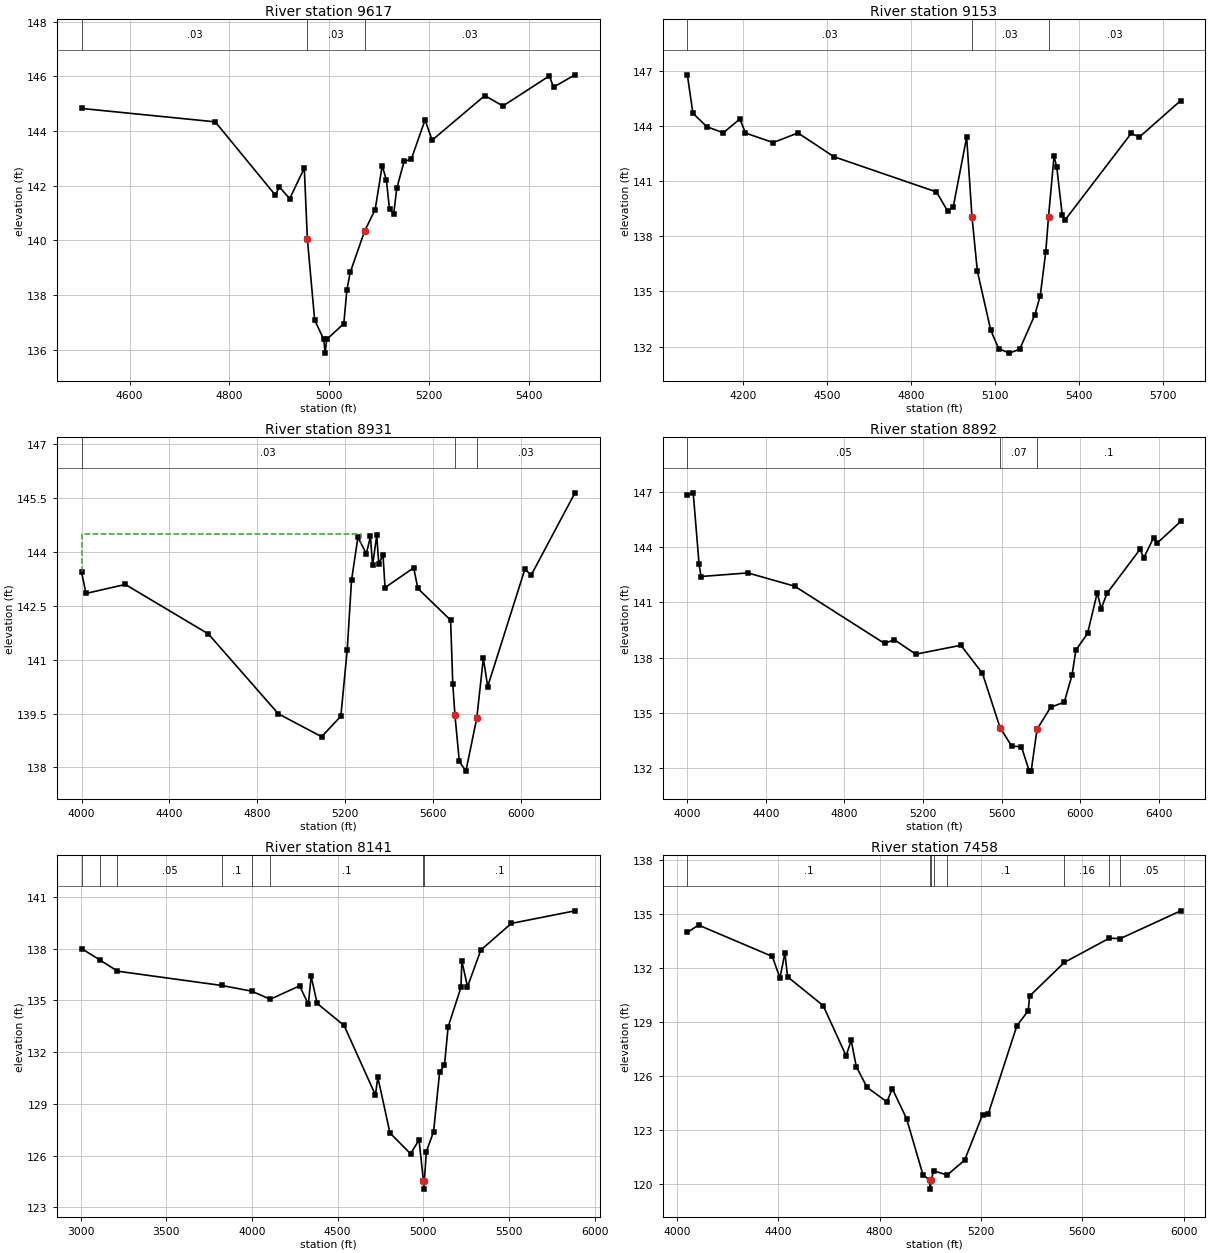
Type RM Length L Ch R = 1 ,9617    ,464,464,464
BEGIN DESCRIPTION:
Mapping XS 2cedba90
END DESCRIPTION:
XS GIS Cut Line= 4
      2308154.41     13283926.67      2307845.34     13283954.45
      2307564.09     13284329.45      2307494.65     13284527.36
#Sta/Elev= 30
  4503.7  144.82  4771.5  144.33    4892  141.65    4900  141.95  4920.8  141.52
    4950  142.64  4956.2  140.04  4970.8  137.08    4989  136.37  4991.8  135.87
    4995  136.37  5029.2  136.95  5035.4  138.18    5042  138.82  5070.8  140.33
    5092  141.12  5106.2  142.73  5114.6  142.19  5120.8  141.13  5129.2  140.97
  5135.4   141.9    5150  142.88  5164.6  142.97    5192   144.4  5206.2  143.66
  5311.8  145.29  5348.1  144.91  5441.1  146.01  5449.6   145.6  5492.5  146.05
#Mann= 3 , 0 , 0
  4503.7     .03       0  4956.2     .03       0  5070.8     .03       0
Bank Sta=4956.2,5070.8
XS Rating Curve= 0 ,0
Exp/Cntr=0.3,0.1

Type RM Length L Ch R = 1 ,9153    ,222,222,222
BEGIN DESCRIPTION:
UNT043 IN NURI 18.0
END DESCRIPTION:
XS GIS Cut Line= 6
     2308466.519    13283817.773     2307666.541    13283683.916
     2307520.694    13283753.668     2307334.817    13283879.402
     2307333.194    13283951.585     2307447.778     13284467.21
#Sta/Elev= 30
    4000 146.771 4019.78144.6868 4069.23143.9531 4128.57143.6203 4187.91144.3723
 4207.69143.6088 4306.58 143.088 4395.59143.6111 4524.16142.3194 4890.76140.4045
 4930.59139.3676  4950.5139.5744 4998.67143.3791 5017.78139.0405 5036.89136.1092
 5084.66132.8917 5113.32131.8873 5151.53131.6446 5188.52 131.861 5242.15133.7155
 5261.84134.7696 5281.54 137.153 5291.39139.0609 5311.09142.3464 5320.94141.7417
 5340.64139.1277 5350.49138.8805 5586.87143.5853 5616.41143.3892 5764.15145.3726
#Mann= 3 , 0 , 0
    4000     .03       0 5017.78     .03       0 5291.39     .03       0
Bank Sta=5017.78,5291.39
XS Rating Curve= 0 ,0
Exp/Cntr=0.3,0.1

Type RM Length L Ch R = 1 ,8931    ,39,39,39
BEGIN DESCRIPTION:
UNT043 IN NURI 17.0
END DESCRIPTION:
XS GIS Cut Line= 6
     2308497.769    13283731.835     2307518.603    13283583.398
     2307244.653    13283670.335     2307109.236    13283821.376
     2307119.653    13283962.001     2307301.944    13284545.335
#Sta/Elev= 30
    4000143.4361 4019.92142.8438 4199.17143.0939 4577.59141.7166 4896.26139.4941
 5093.38138.8564 5180.95 139.426 5210.14141.2778  5229.6143.2066 5258.79144.4058
 5296.99143.9503 5315.97144.4294 5325.47143.6252 5344.45144.4582 5353.94143.6607
 5372.92143.9232 5382.42143.0075 5512.87143.5565 5531.69142.9835    5681142.1007
 5690.94140.3233 5700.88139.4487 5720.76138.1664 5750.58137.8984 5800.28139.3757
  5830.1141.0384 5849.98140.2533 6018.96143.5109 6048.79143.3611 6247.59145.6442
#Mann= 3 , 0 , 0
    4000     .03       0 5700.88     .03       0 5800.28     .03       0
#XS Ineff= 2 , 0
         5274.15  144.49
Permanent Ineff=
       F       F
Bank Sta=5700.88,5800.28
XS Rating Curve= 0 ,0
Exp/Cntr=0.3,0.1

Type RM Length L Ch R = 1 ,8892    ,751,751,751
BEGIN DESCRIPTION:
UNT043 IN NURI 16.0
END DESCRIPTION:
XS GIS Cut Line= 5
     2308627.978    13283703.189     2307500.335    13283463.523
      2307187.36     13283607.83      2307041.53     13283878.67
      2307114.45     13284569.31
#Sta/Elev= 30
    4000146.7955 4029.82146.9398 4059.64143.0759 4069.58142.3985 4308.14142.5931
 4546.69141.8712 5003.93138.7654 5053.63138.9693 5162.97 138.182 5392.79138.6661
 5502.65137.1403 5591.98134.2001 5651.54133.1932 5701.17133.1586 5740.87131.8354
 5750.79131.8512 5780.57134.1063 5849.93135.3035 5919.12135.5772 5958.66137.0535
 5978.43138.4051 6037.74139.3086 6087.16141.5222 6106.93140.6451 6136.58141.4829
 6304.62143.8706 6324.39143.4227 6373.82144.4984 6393.59144.2262  6512.2145.3887
#Mann= 3 , 0 , 0
    4000     .05       0 5591.98     .07       0 5780.57      .1       0
Bank Sta=5591.98,5780.57
XS Rating Curve= 0 ,0
Exp/Cntr=0.3,0.1

Type RM Length L Ch R = 1 ,8141    ,683,683,683
BEGIN DESCRIPTION:
UNT043 IN NURI 15.0
END DESCRIPTION:
XS GIS Cut Line= 4
      2308197.75      13282894.3      2306708.26     13283233.46
      2306239.44     13283706.79      2306041.72     13284362.41
#Sta/Elev= 30
  3006.1     138  3114.3  137.33  3215.6  136.69  3823.9  135.86    3999  135.53
  4106.5  135.06  4277.9  135.84  4329.1  134.77  4345.4  136.39  4380.4  134.82
  4537.6  133.54  4720.4  129.51  4734.5  130.54  4805.2  127.31  4925.4   126.1
  4974.9   126.9  5000.2  124.55  5002.9  124.05  5006.2  124.55  5017.3  126.22
  5059.7  127.38  5095.1  130.84  5123.4  131.25  5144.6  133.46  5219.4  135.75
  5224.7  137.29  5257.6  135.79  5335.8  137.92  5513.3  139.46  5884.7  140.19
#Mann= 8 ,-1 , 0
  3006.1     .05       0  3114.3      .1       0  3215.6     .05       0
  3823.9      .1       0    3999     .05       0  4106.5      .1       0
  5000.2     .07       0  5006.2      .1       0
Bank Sta=5000.2,5006.2
XS Rating Curve= 0 ,0
Exp/Cntr=0.3,0.1

Type RM Length L Ch R = 1 ,7458    ,360,360,360
BEGIN DESCRIPTION:
UNT043 IN NURI 14.0
END DESCRIPTION:
XS GIS Cut Line= 4
      2306801.57     13282987.49      2306121.04     13282924.99
      2305593.26     13283320.83      2305502.99     13283918.03
#Sta/Elev= 30
  4041.6  133.97  4085.6  134.38  4376.9  132.64    4407  131.44  4426.7  132.83
  4437.1  131.51  4577.7  129.91  4668.1  127.13  4688.2  127.98  4708.2  126.53
  4750.5  125.38  4829.1  124.57  4850.5   125.3  4906.7  123.64  4971.3  120.53
  4997.5  120.23  5000.2  119.73  5003.5  120.23  5013.6  120.75  5066.9  120.51
  5135.9  121.34  5206.7  123.86  5229.1  123.91  5342.2   128.8  5387.1  129.63
  5392.1  130.44  5529.6  132.31  5706.7  133.65  5750.2  133.63  5988.7  135.17
#Mann= 8 ,-1 , 0
  4041.6      .1       0  4997.5     .07       0  5003.5      .1       0
  5013.6     .12       0  5066.9      .1       0  5529.6     .16       0
  5706.7      .1       0  5750.2     .05       0
Bank Sta=4997.5,5003.5
XS Rating Curve= 0 ,0
Exp/Cntr=0.3,0.1

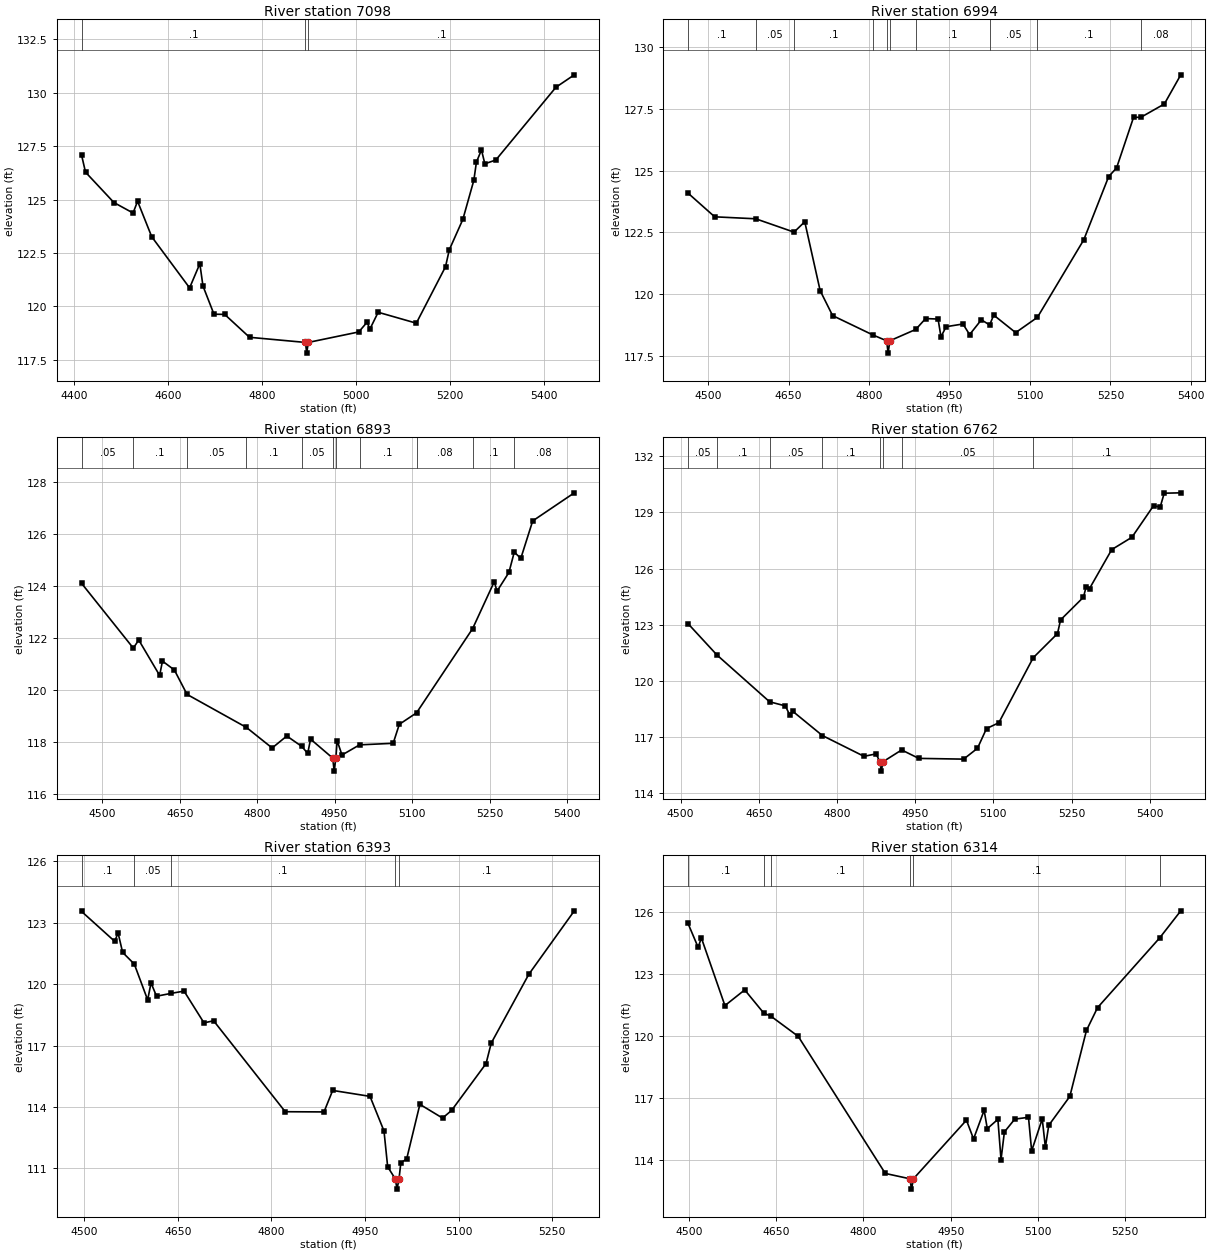
Type RM Length L Ch R = 1 ,7098    ,104,104,104
BEGIN DESCRIPTION:
Mapping XS 2ee90a39
END DESCRIPTION:
XS GIS Cut Line= 3
      2306246.05     13282640.27      2305996.04     13282668.05
      2305266.89     13282987.49
#Sta/Elev= 30
  4416.5  127.08  4424.9  126.28  4485.3  124.86    4526  124.37  4535.6  124.92
  4565.7  123.26  4646.2  120.87    4668     122  4674.6  120.96    4698  119.64
  4720.8  119.63  4773.6  118.56  4892.5  118.32  4895.2  117.82  4898.5  118.32
  5005.8  118.81  5023.7  119.27  5029.2  118.93  5047.1  119.73  5128.2  119.22
  5190.3  121.86  5198.3  122.65  5227.1  124.07  5250.5   125.9    5256  126.75
  5266.7  127.32  5273.9  126.67  5297.3  126.85  5425.1  130.25  5464.1  130.83
#Mann= 3 ,-1 , 0
  4416.5      .1       0  4892.5     .07       0  4898.5      .1       0
Bank Sta=4892.5,4898.5
XS Rating Curve= 0 ,0
Exp/Cntr=0.3,0.1

Type RM Length L Ch R = 1 ,6994    ,101,101,101
BEGIN DESCRIPTION:
UNT043 IN NURI 13.0
END DESCRIPTION:
XS GIS Cut Line= 2
      2306156.92     13282481.03      2305318.45       13282856.
#Sta/Elev= 30
  4462.7  124.09  4512.4  123.13  4588.9  123.05  4660.3  122.51  4680.3  122.93
    4709  120.14  4732.2  119.13  4806.9  118.35  4832.9  118.11  4835.7  117.61
  4838.9  118.11  4887.2  118.57  4905.6  119.01  4928.8  118.99  4934.2  118.27
  4943.8  118.68  4975.2  118.79  4987.6  118.36  5009.5  118.96  5024.9  118.75
  5032.5  119.15  5073.4  118.44    5114  119.06  5200.4   122.2  5246.8  124.76
  5261.5  125.11  5293.2  127.16  5306.8  127.16  5350.6   127.7  5381.2  128.88
#Mann= 10 ,-1 , 0
  4462.7      .1       0  4588.9     .05       0  4660.3      .1       0
  4806.9     .05       0  4832.9     .07       0  4838.9     .05       0
  4887.2      .1       0  5024.9     .05       0    5114      .1       0
  5306.8     .08       0
Bank Sta=4832.9,4838.9
XS Rating Curve= 0 ,0
Exp/Cntr=0.3,0.1

Type RM Length L Ch R = 1 ,6893    ,131,131,131
BEGIN DESCRIPTION:
Mapping XS a120cf7f
END DESCRIPTION:
XS GIS Cut Line= 2
      2306136.09     13282376.87      2305268.94     13282775.29
#Sta/Elev= 30
  4459.9  124.11  4560.1  121.62  4570.7  121.93  4611.1  120.57  4616.6  121.12
  4639.6  120.78  4664.2  119.84  4779.2  118.57    4829  117.78  4857.4  118.24
  4886.4  117.84  4897.9  117.57  4903.4  118.12  4946.4  117.39  4949.1  116.89
  4952.4  117.39  4954.9  118.06  4964.3  117.51  4998.3   117.9  5063.4  117.96
  5075.3  118.69  5108.6  119.13  5217.3  122.37  5259.1  124.17  5264.6  123.81
  5287.6  124.53  5297.9  125.31  5310.6  125.07  5333.6  126.51  5414.2  127.59
#Mann= 11 ,-1 , 0
  4459.9     .05       0  4560.1      .1       0  4664.2     .05       0
  4779.2      .1       0  4886.4     .05       0  4946.4     .07       0
  4952.4     .05       0  4998.3      .1       0  5108.6     .08       0
  5217.3      .1       0  5297.9     .08       0
Bank Sta=4946.4,4952.4
XS Rating Curve= 0 ,0
Exp/Cntr=0.3,0.1

Type RM Length L Ch R = 1 ,6762    ,369,369,369
BEGIN DESCRIPTION:
Mapping XS 6e87b4a6
END DESCRIPTION:
XS GIS Cut Line= 2
      2306100.23     13282369.43      2305176.64     13282570.82
#Sta/Elev= 30
  4514.1  123.06  4569.5  121.39  4670.6  118.89  4700.9  118.67  4709.6  118.16
  4714.7  118.39  4771.8  117.09  4851.7  115.98  4874.9  116.11  4882.1  115.69
  4884.9  115.19  4888.1  115.69  4923.9  116.32  4956.8  115.87  5042.8  115.83
  5069.4  116.41  5086.7  117.46  5110.3  117.77  5176.3  121.24  5222.9  122.53
  5228.8  123.26  5272.7  124.47  5277.8  125.02  5284.3  124.93  5326.9  127.01
  5365.7  127.67  5407.1  129.35  5419.9  129.28  5427.6  130.02  5459.4  130.04
#Mann= 8 ,-1 , 0
  4514.1     .05       0  4569.5      .1       0  4670.6     .05       0
  4771.8      .1       0  4882.1    .035       0  4888.1      .1       0
  4923.9     .05       0  5176.3      .1       0
Bank Sta=4882.1,4888.1
XS Rating Curve= 0 ,0
Exp/Cntr=0.3,0.1

Type RM Length L Ch R = 1 ,6393    ,79,79,79
BEGIN DESCRIPTION:
Mapping XS 5617df06
END DESCRIPTION:
XS GIS Cut Line= 4
      2306108.37     13282353.86      2305717.72     13282188.92
      2305598.36     13282002.29      2305455.13     13281989.27
#Sta/Elev= 30
  4495.9  123.55    4549  122.09  4554.4   122.5  4561.7  121.55  4580.4  120.98
  4601.8  119.23  4607.2  120.06    4616  119.41  4639.5  119.55  4660.1  119.66
    4692  118.11  4707.5  118.21  4822.2  113.77  4884.3  113.76  4898.2  114.81
    4958  114.52  4980.4  112.83  4986.3  111.08  4998.5  110.49  5001.3  109.99
  5004.5  110.49  5007.4  111.28  5016.7  111.46  5037.9  114.13  5074.2  113.46
  5088.6  113.83  5143.9  116.12  5152.2  117.12  5212.4  120.48  5285.3  123.58
#Mann= 5 ,-1 , 0
  4495.9      .1       0  4580.4     .05       0  4639.5      .1       0
  4998.5     .07       0  5004.5      .1       0
Bank Sta=4998.5,5004.5
XS Rating Curve= 0 ,0
Exp/Cntr=0.3,0.1

Type RM Length L Ch R = 1 ,6314    ,98,98,98
BEGIN DESCRIPTION:
Mapping XS d893b07e
END DESCRIPTION:
XS GIS Cut Line= 4
      2306125.67     13282310.43      2305752.44     13282139.01
      2305656.95     13281915.48        2305466.     13281889.45
#Sta/Elev= 30
  4498.8  125.44  4516.2  124.28  4521.7  124.74  4562.2  121.46  4596.2  122.22
  4628.8   121.1  4641.5  120.94  4688.1  119.97  4837.7  113.33    4880  113.07
  4882.7  112.57    4886  113.07  4977.1  115.91  4989.3     115  5007.5  116.39
  5012.9   115.5  5031.1  115.95  5036.5     114  5042.3  115.34  5060.1  115.96
  5083.7  116.05  5089.1  114.42  5107.3  115.97  5112.7   114.6  5118.5  115.66
  5154.7  117.06  5183.3  120.26  5202.3  121.36  5309.1  124.74  5345.3  126.05
#Mann= 6 ,-1 , 0
  4498.8      .1       0  4628.8     .05       0  4641.5      .1       0
    4880     .07       0    4886      .1       0  5309.1     .05       0
Bank Sta=4880,4886
XS Rating Curve= 0 ,0
Exp/Cntr=0.3,0.1

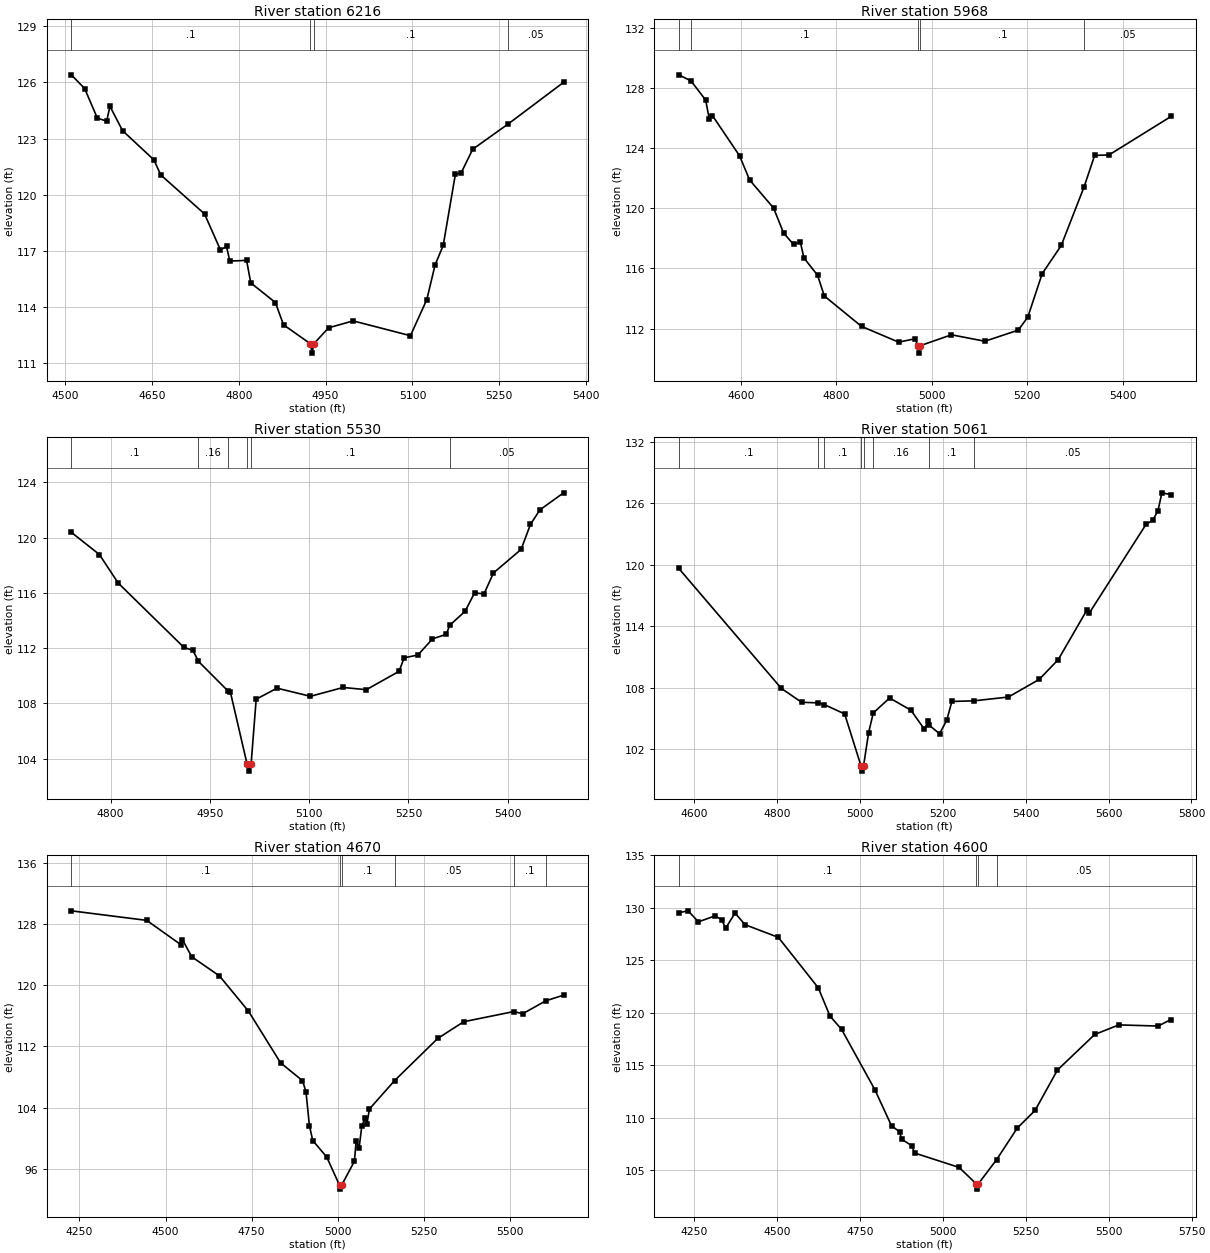
Type RM Length L Ch R = 1 ,6216    ,248,248,248
BEGIN DESCRIPTION:
UNT043 IN NURI 12.0
END DESCRIPTION:
XS GIS Cut Line= 4
      2306183.33     13282272.77      2305926.05      13282132.5
      2305674.31     13281869.91      2305480.82     13281872.06
#Sta/Elev= 30
  4510.7   126.4  4533.8  125.67  4555.7  124.09  4571.8  123.93  4577.5  124.72
  4599.3  123.42  4653.5  121.86  4665.2  121.06  4740.8  118.98  4768.3  117.06
  4778.8  117.24  4784.5  116.46  4813.5   116.5  4820.7   115.3  4863.2  114.25
  4877.3  113.06  4923.7  112.05  4926.5  111.55  4929.7  112.05    4955   112.9
  4997.5  113.27  5096.5  112.48  5124.8  114.41    5139  116.25  5153.1   117.3
  5174.1  121.09  5184.1  121.17  5204.1  122.43  5265.4  123.78    5361     126
#Mann= 4 ,-1 , 0
  4510.7      .1       0  4923.7     .07       0  4929.7      .1       0
  5265.4     .05       0
Bank Sta=4923.7,4929.7
XS Rating Curve= 0 ,0
Exp/Cntr=0.3,0.1

Type RM Length L Ch R = 1 ,5968    ,438,438,438
BEGIN DESCRIPTION:
UNT043 IN NURI 11.0
END DESCRIPTION:
XS GIS Cut Line= 3
      2306337.71     13282246.85      2305987.72     13281846.85
      2305487.72     13281846.85
#Sta/Elev= 30
    4470  128.88  4495.6  128.48  4526.5   127.2  4534.1  125.93  4540.7  126.17
  4597.6  123.49  4618.5  121.89  4668.8  120.02  4689.7  118.36  4710.6   117.6
  4724.8  117.76  4732.4   116.7  4760.9  115.55  4775.1  114.17    4853  112.15
  4930.8   111.1  4965.9  111.33  4970.5  110.87  4973.2  110.37  4976.5  110.87
  5041.5  111.59  5111.5  111.16  5181.5   111.9  5201.5  112.77  5231.5  115.65
  5271.5  117.53  5319.4  121.43  5341.5  123.52  5371.5  123.55  5501.5  126.11
#Mann= 5 ,-1 , 0
    4470     .08       0  4495.6      .1       0  4970.5     .07       0
  4976.5      .1       0  5319.4     .05       0
Bank Sta=4970.5,4976.5
XS Rating Curve= 0 ,0
Exp/Cntr=0.3,0.1

Type RM Length L Ch R = 1 ,5530    ,469,469,469
BEGIN DESCRIPTION:
UNT043 IN NURI 10.0
END DESCRIPTION:
XS GIS Cut Line= 3
      2306187.76     13281296.82      2305987.72     13281496.85
       2305637.7     13281796.88
#Sta/Elev= 30
  4740.6  120.39  4783.1  118.78  4811.4  116.72  4910.4  112.07  4924.5  111.83
  4932.8  111.04  4976.7  108.93  4981.1   108.8  5006.3  103.59  5009.1  103.09
  5012.3  103.59    5020   108.3  5051.5   109.1    5102  108.51  5151.4  109.15
  5186.5  108.99  5235.9  110.32  5243.6   111.3  5264.4   111.5  5286.4  112.67
  5307.2     113  5312.4  113.65  5335.7  114.67    5350     116  5364.3  115.93
  5378.6  117.45  5420.3  119.15  5434.5  120.97  5448.8  122.02  5484.5  123.25
#Mann= 6 ,-1 , 0
  4740.6      .1       0  4932.8     .16       0  4976.7      .1       0
  5006.3     .07       0  5012.3      .1       0  5312.4     .05       0
Bank Sta=5006.3,5012.3
XS Rating Curve= 0 ,0
Exp/Cntr=0.3,0.1

Type RM Length L Ch R = 1 ,5061    ,391,391,391
BEGIN DESCRIPTION:
UNT043 IN NURI 9.0
END DESCRIPTION:
XS GIS Cut Line= 3
      2306087.68     13280896.88      2305687.72     13281146.85
      2305387.74     13281796.82
#Sta/Elev= 30
  4563.2  119.65  4810.8  107.93  4859.7  106.58  4899.6  106.52  4914.6  106.35
  4963.5  105.44    5003  100.36  5005.7   99.86    5009  100.36  5021.3  103.62
  5032.5  105.54    5072     107  5123.4   105.8    5156  103.94  5163.8  104.71
  5167.9  104.33  5192.3  103.51  5209.7  104.82  5222.1  106.66  5275.2  106.72
  5358.4  107.09  5432.7  108.81  5478.6  110.74  5547.4  115.55    5553  115.25
  5690.6  123.95  5706.7  124.35  5719.1  125.25  5728.7  127.02  5750.7  126.84
#Mann= 8 ,-1 , 0
  4563.2      .1       0  4899.6     .16       0  4914.6      .1       0
    5003     .07       0    5009      .1       0  5032.5     .16       0
  5167.9      .1       0  5275.2     .05       0
Bank Sta=5003,5009
XS Rating Curve= 0 ,0
Exp/Cntr=0.3,0.1

Type RM Length L Ch R = 1 ,4670    ,70,70,70
BEGIN DESCRIPTION:
Mapping XS 703650a1
END DESCRIPTION:
XS GIS Cut Line= 3
      2306525.59     13280855.18      2305702.64     13280769.24
      2305155.78     13281021.83
#Sta/Elev= 30
  4226.2  129.74  4445.3  128.49  4543.9  125.33  4548.9  125.98    4576  123.73
  4656.4  121.23  4740.7  116.62  4834.1  109.85  4897.7  107.52  4907.8  106.08
  4917.8  101.64  4927.5   99.69  4968.1   97.53  5005.3   93.83    5008   93.33
  5011.3   93.83  5048.5   96.98  5053.6   99.63  5062.2   98.76  5070.1  101.61
  5079.6  102.63  5085.1  101.91  5092.1  103.81  5165.4  107.54  5290.4  113.04
  5365.9  115.23  5511.3  116.56  5537.5  116.28  5603.9  117.96    5656  118.71
#Mann= 6 ,-1 , 0
  4226.2      .1       0  5005.3     .07       0  5011.3      .1       0
  5165.4     .05       0  5511.3      .1       0  5603.9     .05       0
Bank Sta=5005.3,5011.3
XS Rating Curve= 0 ,0
Exp/Cntr=0.3,0.1

Type RM Length L Ch R = 1 ,4600    ,86,86,86
BEGIN DESCRIPTION:
UNT043 IN NURI 8.0
END DESCRIPTION:
XS GIS Cut Line= 4
      2306546.98      13280794.9      2305887.27      13280732.4
      2305682.41     13280690.73      2305131.54     13280960.97
#Sta/Elev= 30
  4202.4  129.54  4230.7  129.72  4261.9  128.67  4312.1  129.24  4332.2  128.87
    4344  128.06  4372.4  129.51  4402.5   128.4    4503  127.19  4623.5  122.38
  4658.7   119.7  4693.8  118.42  4794.3  112.67  4844.5  109.23  4868.8  108.67
  4874.8  107.96  4905.4  107.34  4914.2  106.64  5048.3  105.27  5100.3   103.7
    5103   103.2  5106.3   103.7  5161.7  106.02  5224.1  109.03  5277.6   110.7
  5345.1  114.55  5457.6  117.94  5530.6  118.85  5648.6  118.74  5687.7  119.36
#Mann= 4 ,-1 , 0
  4202.4      .1       0  5100.3     .07       0  5106.3      .1       0
  5161.7     .05       0
Bank Sta=5100.3,5106.3
XS Rating Curve= 0 ,0
Exp/Cntr=0.3,0.1

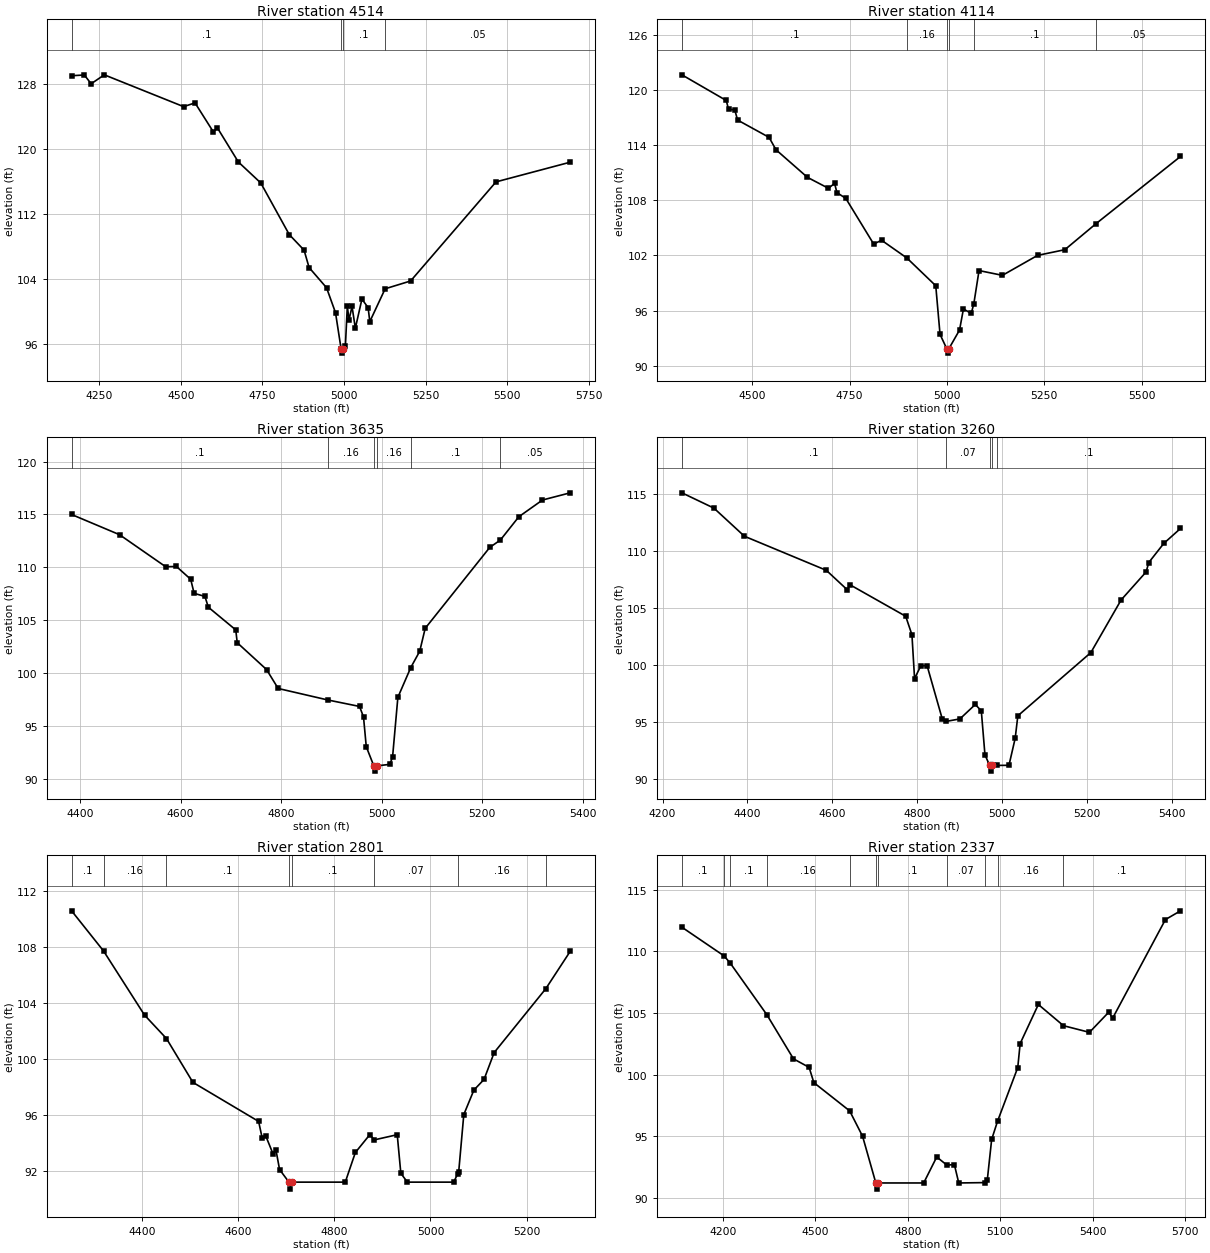
Type RM Length L Ch R = 1 ,4514    ,400,400,400
BEGIN DESCRIPTION:
Mapping XS 8609c2cf
END DESCRIPTION:
XS GIS Cut Line= 3
      2306556.81     13280748.41      2305559.41     13280597.36
      2305120.56     13280872.62
#Sta/Elev= 30
  4165.4  129.02  4204.5  129.11  4225.2  128.03  4265.6  129.13  4508.4  125.22
  4543.4  125.68  4599.4  122.12  4612.2  122.59    4676  118.42  4744.7  115.84
    4832  109.49  4877.3  107.58  4892.7  105.44  4946.1  102.96  4973.6   99.89
  4990.8   95.42  4993.6   94.92  4996.8   95.42  5003.9   95.84  5009.8   100.7
  5014.9   98.99  5024.2  100.66  5034.3   97.98  5054.5  101.56  5073.5  100.51
  5078.6   98.79  5125.6  102.83  5203.6  103.79  5465.1  115.97  5692.2  118.39
#Mann= 4 ,-1 , 0
  4165.4      .1       0  4990.8     .07       0  4996.8      .1       0
  5125.6     .05       0
Bank Sta=4990.8,4996.8
XS Rating Curve= 0 ,0
Exp/Cntr=0.3,0.1

Type RM Length L Ch R = 1 ,4114    ,479,479,479
BEGIN DESCRIPTION:
UNT043 IN NURI 7.0
END DESCRIPTION:
XS GIS Cut Line= 3
      2306121.87     13280490.58      2305710.45      13280308.3
      2304881.24     13280362.89
#Sta/Elev= 30
  4319.1  121.65    4433  118.86  4438.9  117.91  4454.9  117.83  4462.2  116.73
    4543  114.85  4560.8   113.5  4641.6   110.5  4695.5  109.31  4711.4  109.84
  4717.4  108.84  4740.2  108.21  4811.9  103.24    4832  103.66    4897  101.73
  4971.3   98.71  4982.3   93.42  4999.3   91.88  5002.1   91.38  5005.3   91.88
  5032.4   93.89  5042.4   96.18  5062.5    95.7  5069.2   96.77  5082.5  100.36
  5142.6   99.84  5232.8  102.01    5303  102.63  5382.8  105.45  5600.1  112.77
#Mann= 6 ,-1 , 0
  4319.1      .1       0    4897     .16       0  4999.3     .07       0
  5005.3     .16       0  5069.2      .1       0  5382.8     .05       0
Bank Sta=4999.3,5005.3
XS Rating Curve= 0 ,0
Exp/Cntr=0.3,0.1

Type RM Length L Ch R = 1 ,3635    ,375,375,375
BEGIN DESCRIPTION:
UNT043 IN NURI 6.0
END DESCRIPTION:
XS GIS Cut Line= 3
      2306026.19     13280253.26      2305803.94     13280013.65
       2305192.8     13279749.75
#Sta/Elev= 30
  4382.9  114.99  4478.3  113.08  4570.1  110.05  4591.6  110.07    4620  108.86
  4626.8  107.53  4648.3  107.24  4655.1  106.22  4709.7  104.07  4712.6  102.86
    4771  100.32  4794.1   98.53  4893.1   97.44  4956.1   96.83    4964   95.84
  4969.5   93.02  4984.5   91.21  4987.3   90.71  4990.5   91.21  5016.5   91.35
  5021.9   92.07  5032.4   97.69  5058.1  100.51  5075.9  102.05  5086.8  104.22
  5215.4  111.88  5236.4  112.57  5273.3  114.78  5320.3  116.36  5375.4  117.04
#Mann= 6 ,-1 , 0
  4382.9      .1       0  4893.1     .16       0  4984.5     .07       0
  4990.5     .16       0  5058.1      .1       0  5236.4     .05       0
Bank Sta=4984.5,4990.5
XS Rating Curve= 0 ,0
Exp/Cntr=0.3,0.1

Type RM Length L Ch R = 1 ,3260    ,459,459,459
BEGIN DESCRIPTION:
UNT043 IN NURI 5.0
END DESCRIPTION:
XS GIS Cut Line= 3
      2306102.54     13280208.07      2305939.36     13279742.82
      2305383.79     13279346.98
#Sta/Elev= 30
  4245.7  115.06  4321.2  113.72  4393.1  111.26  4586.1  108.28  4635.9  106.56
  4641.2  107.03  4773.2  104.26  4787.9  102.64  4794.1    98.8  4808.8   99.93
  4823.6   99.94  4859.2    95.3  4868.5   95.06    4901   95.28  4937.2   96.54
  4951.4   95.99    4960   92.14    4971   91.21  4973.8   90.71    4977   91.21
  4989.4   91.21  5016.6   91.22  5031.3   93.59  5037.5   95.55  5209.6  101.08
    5281  105.69  5339.9  108.14  5346.1  108.96  5381.7  110.64  5420.9  111.94
#Mann= 5 ,-1 , 0
  4245.7      .1       0  4868.5     .07       0    4971     .07       0
    4977     .07       0  4989.4      .1       0
Bank Sta=4971,4977
XS Rating Curve= 0 ,0
Exp/Cntr=0.3,0.1

Type RM Length L Ch R = 1 ,2801    ,464,464,464
BEGIN DESCRIPTION:
UNT043 IN NURI 4.0
END DESCRIPTION:
XS GIS Cut Line= 3
      2306487.71     13279546.85      2305887.72     13279146.85
      2305587.74     13279246.85
#Sta/Elev= 30
  4253.4   110.6  4319.9  107.73  4405.1  103.15  4450.8  101.47  4505.8   98.34
  4642.5   95.55    4650   94.35  4657.5    94.5  4672.5   93.23  4678.5   93.52
  4686.1   92.11  4705.6   91.21  4708.3   90.71  4711.6   91.21  4822.8   91.21
  4843.8   93.33  4873.8    94.6  4883.3   94.23  4930.9    94.6  4938.4   91.84
    4952   91.21  5048.3   91.21  5056.4   91.78  5058.8   91.95  5069.4   96.04
  5090.4   97.79  5111.5   98.55  5132.6  100.47  5240.1  105.04  5290.7   107.7
#Mann= 8 ,-1 , 0
  4253.4      .1       0  4319.9     .16       0  4450.8      .1       0
  4705.6     .07       0  4711.6      .1       0  4883.3     .07       0
  5056.4     .16       0  5240.1      .1       0
Bank Sta=4705.6,4711.6
XS Rating Curve= 0 ,0
Exp/Cntr=0.3,0.1

Type RM Length L Ch R = 1 ,2337    ,258,258,258
BEGIN DESCRIPTION:
UNT043 IN NURI 3.0
END DESCRIPTION:
XS GIS Cut Line= 4
      2306609.52     13279534.52      2306165.05     13278819.21
        2305922.     13278617.82      2305492.09     13278784.23
#Sta/Elev= 30
  4066.4  111.96  4203.5  109.63  4223.8  109.03  4342.2  104.86  4428.6  101.28
  4479.4  100.59  4494.8   99.35    4611   97.06    4653      95    4696   91.21
  4698.8   90.71    4702   91.21  4851.4   91.21  4893.8   93.32  4926.6   92.66
    4951    92.7  4965.3   91.21  5051.1   91.24  5057.8   91.42  5072.1   94.74
  5091.2   96.22  5156.8  100.57  5164.6  102.52  5223.7  105.69  5305.3  103.97
  5389.6  103.43  5452.8  105.08  5464.7  104.57  5636.3  112.58  5685.2  113.29
#Mann= 11 ,-1 , 0
  4066.4      .1       0  4203.5     .16       0  4223.8      .1       0
  4342.2     .16       0    4611      .1       0    4696     .07       0
    4702      .1       0  4926.6     .07       0  5051.1      .1       0
  5091.2     .16       0  5305.3      .1       0
Bank Sta=4696,4702
XS Rating Curve= 0 ,0
Exp/Cntr=0.3,0.1