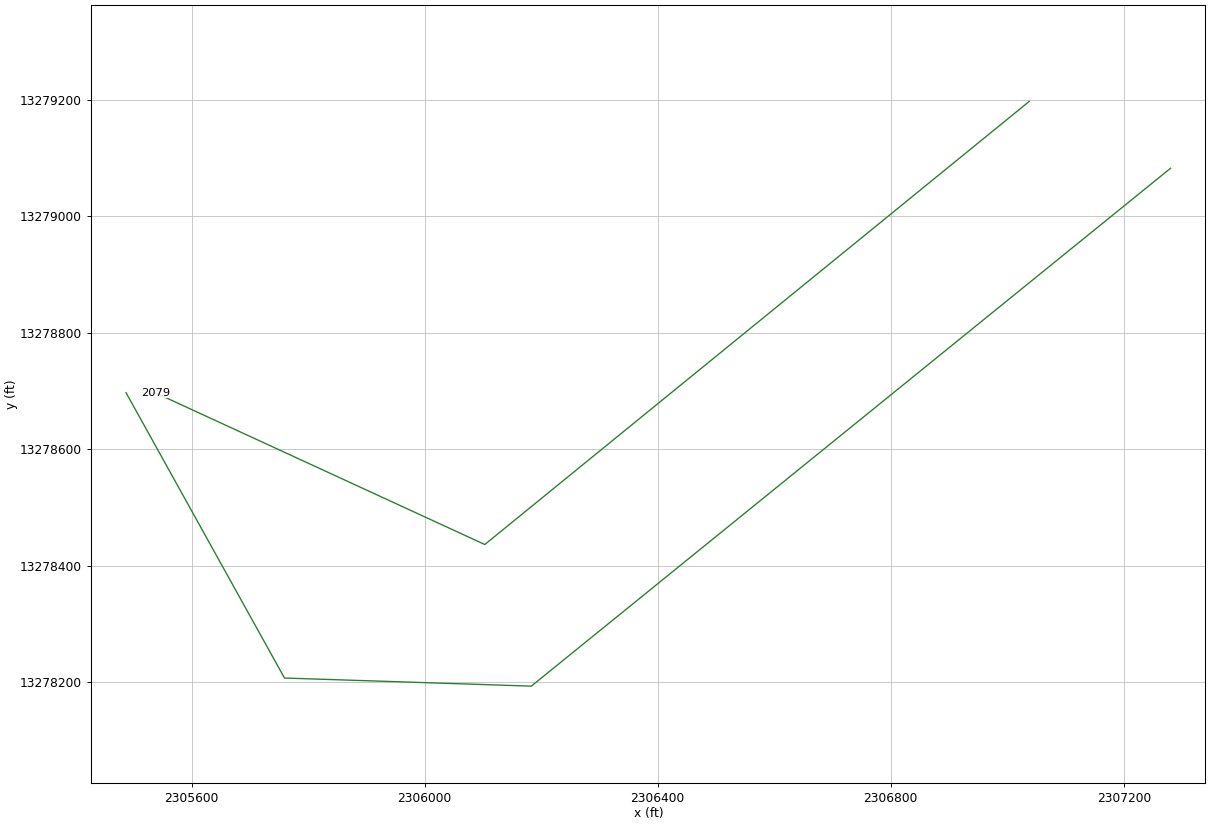
HEC-RAS study UNT043 IN NURI.prj: UNT043 IN NURI Base Level Engineering

--- UNT043 IN NURI.g01 (geometry) --- (continued)

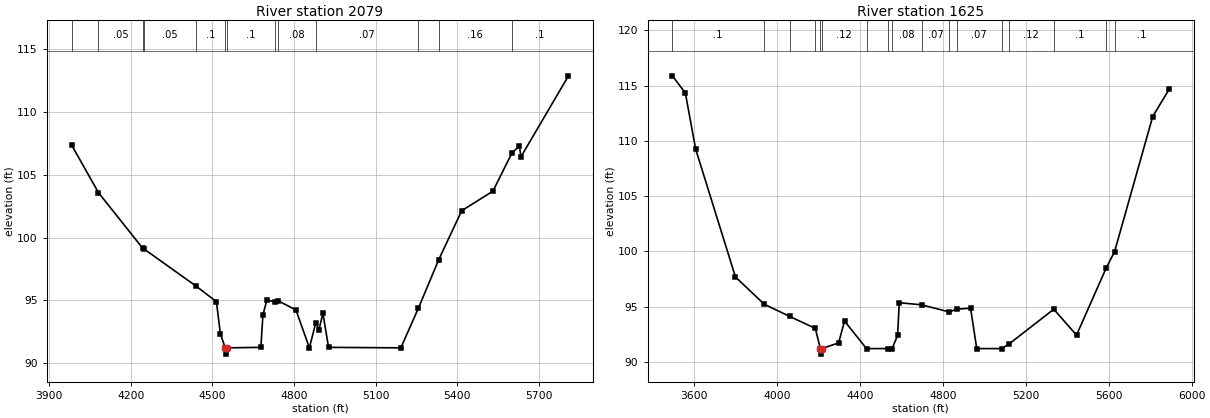
Type RM Length L Ch R = 1 ,2079    ,454,454,454
BEGIN DESCRIPTION:
UNT043 IN NURI 2.0
END DESCRIPTION:
XS GIS Cut Line= 3
      2307037.73     13279196.87      2306103.34     13278436.41
      2305537.75     13278696.84
#Sta/Elev= 30
  3981.8  107.39  4080.9  103.58  4243.2   99.16  4247.1   99.11  4441.2   96.11
  4514.7   94.89  4529.1   92.34  4546.9   91.21  4549.6   90.71  4552.9   91.21
  4678.1   91.25  4685.6   93.84    4700      95  4730.3    94.9  4741.7   94.96
    4807   94.23  4856.6   91.21  4879.7    93.2  4891.8   92.64  4906.1   93.98
    4927   91.25  5192.7   91.21  5257.7   94.39  5332.3   98.25  5416.6  102.14
  5531.4   103.7    5601  106.73  5628.7  107.31  5634.3  106.43  5809.2  112.89
#Mann= 13 ,-1 , 0
  3981.8      .1       0  4080.9     .05       0  4243.2      .1       0
  4247.1     .05       0  4441.2      .1       0  4546.9     .07       0
  4552.9      .1       0  4730.3      .1       0  4741.7     .08       0
  4879.7     .07       0  5257.7      .1       0  5332.3     .16       0
    5601      .1       0
Bank Sta=4546.9,4552.9
XS Rating Curve= 0 ,0
Exp/Cntr=0.3,0.1

Type RM Length L Ch R = 1 ,1625    ,0,0,0
BEGIN DESCRIPTION:
UNT043 IN NURI 1.0
END DESCRIPTION:
XS GIS Cut Line= 4
      2307280.42     13279082.24       2306183.2     13278193.36
      2305759.59     13278207.25       2305487.7     13278696.89
#Sta/Elev= 30
  3496.3  115.88  3559.1  114.32  3608.6  109.25  3800.5   97.69  3938.6   95.23
    4062   94.12  4185.4   93.04  4209.9   91.21  4212.7   90.71  4215.9   91.21
  4297.7   91.72  4326.4    93.7  4432.3   91.21  4534.7   91.21  4555.7   91.21
  4582.2   92.41  4590.2   95.36  4697.5   95.17    4831   94.53  4866.9   94.77
  4933.9   94.87  4963.9   91.21  5083.2   91.21  5119.1   91.62  5335.2   94.77
  5444.9   92.43  5588.9   98.54  5628.2   99.97  5812.2   112.2  5892.3  114.69
#Mann= 17 ,-1 , 0
  3496.3      .1       0  3938.6     .05       0    4062      .1       0
  4185.4     .12       0  4209.9     .07       0  4215.9     .12       0
  4432.3      .1       0  4534.7     .12       0  4555.7     .08       0
  4697.5     .07       0    4831     .08       0  4866.9     .07       0
  5083.2     .05       0  5119.1     .12       0  5335.2      .1       0
  5588.9     .16       0  5628.2      .1       0
Bank Sta=4209.9,4215.9
XS Rating Curve= 0 ,0
Exp/Cntr=0.3,0.1

Chan Stop Cuts=-1
Use User Specified Reach Order=0
Composite Channel Slope=5