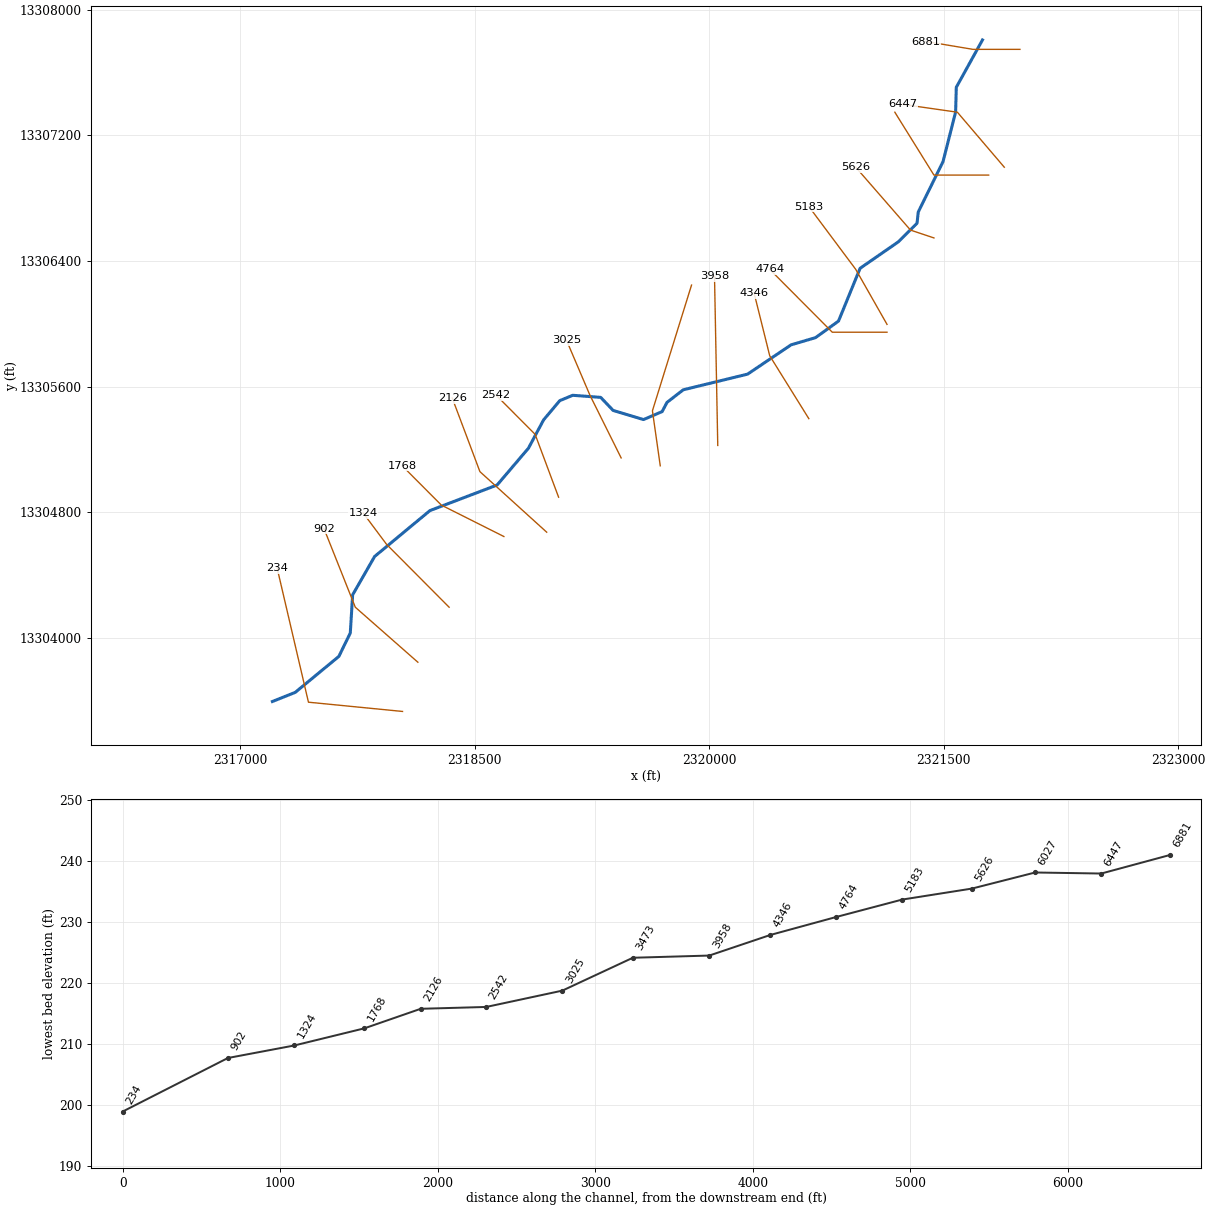
--- UNT045 IN NURI.prj (project) ---

Proj Title=UNT045 IN NURI Base Level Engineering
Current Plan=p01
Default Exp/Contr=0.3,0.1
English Units
Geom File=g01
Flow File=f01
Plan File=p01
Y Axis Title=Elevation
X Axis Title(PF)=Main Channel Distance
X Axis Title(XS)=Station
BEGIN DESCRIPTION:
UNT045 IN NURI
END DESCRIPTION:
DSS Export Rating Curves= 0
DSS Export Rating Curve Sorted= 0
DSS Export Volume Flow Curves= 0
DXF OffsetX= 0
DXF OffsetY= 0
DXF ScaleX= 1
DXF ScaleY= 10

--- UNT045 IN NURI.p01 (plan) ---

Plan Title=Multiple Run
Short Identifier=Multiple
Geom File=g01
Flow File=f01
Subcritical Flow
K Sum by GR= 0
Std Step Tol= 0.01
Critical Tol= 0.01
Num of Std Step Trials= 20
Max Error Tol= 0.3
Flow Tol Ratio= 0.001
Split Flow NTrial= 30
Split Flow Tol= 0.02
Split Flow Ratio= 0.02
Log Output Level= 0
Friction Slope Method= 1
Unsteady Friction Slope Method= 2
Unsteady Bridges Friction Slope Method= 1
Parabolic Critical Depth
Global Vel Dist=  1 , 1 , 1
Global Log Level= 0
CheckData=True
Encroach Param= -1, 0, 0, 0
BEGIN DESCRIPTION:
Multiple Run
END DESCRIPTION:

--- UNT045 IN NURI.f01 (steady flow) ---

Flow Title=Multiple
Number of Profiles=7
Profile Names=10-year,25-year,50-year,1pct_min,100-year,1pct_plu,500-year
River Rch & RM= UNT045 IN NURI,Reach-1,6881
     594     836    1037     940    1271    1719    1917
River Rch & RM= UNT045 IN NURI,Reach-1,6447
     877    1258    1581    1450    1960    2651    3026
Boundary for River Rch & Prof#=UNT045 IN NURI,Reach-1,1
Up Type=0
Dn Type=3
Dn Slope=0.005
Boundary for River Rch & Prof#=UNT045 IN NURI,Reach-1,2
Up Type=0
Dn Type=3
Dn Slope=0.005
Boundary for River Rch & Prof#=UNT045 IN NURI,Reach-1,3
Up Type=0
Dn Type=3
Dn Slope=0.005
Boundary for River Rch & Prof#=UNT045 IN NURI,Reach-1,4
Up Type=0
Dn Type=3
Dn Slope=0.005
Boundary for River Rch & Prof#=UNT045 IN NURI,Reach-1,5
Up Type=0
Dn Type=3
Dn Slope=0.005
Boundary for River Rch & Prof#=UNT045 IN NURI,Reach-1,6
Up Type=0
Dn Type=3
Dn Slope=0.005
Boundary for River Rch & Prof#=UNT045 IN NURI,Reach-1,7
Up Type=0
Dn Type=3
Dn Slope=0.005

--- UNT045 IN NURI.g01 (geometry) ---

Geom Title=Existing Conditions
Program Version=4.10

River Reach=UNT045 IN NURI  ,Reach-1
Reach XY= 30
      2321748.08      13307806.6      2321580.77     13307505.59
      2321576.42     13307348.64      2321495.99     13307032.57
      2321337.46     13306711.85      2321329.69      13306640.3
      2321210.12     13306521.96      2320965.51     13306353.57
       2320827.5     13306017.49      2320680.23     13305912.17
      2320524.25     13305866.51      2320246.35     13305680.17
      2319834.75     13305580.37      2319730.81     13305500.25
       2319699.9     13305441.77      2319580.73     13305390.98
      2319386.43     13305449.12      2319306.94      13305532.2
        2319128.     13305545.46      2319045.23     13305511.42
      2318942.29     13305389.68       2318844.8     13305208.64
      2318644.67     13304974.54      2318215.06     13304811.72
      2317861.48     13304519.86      2317720.75      13304275.6
      2317705.73     13304032.68      2317632.68     13303883.87
       2317353.8     13303654.93      2317207.72     13303596.85

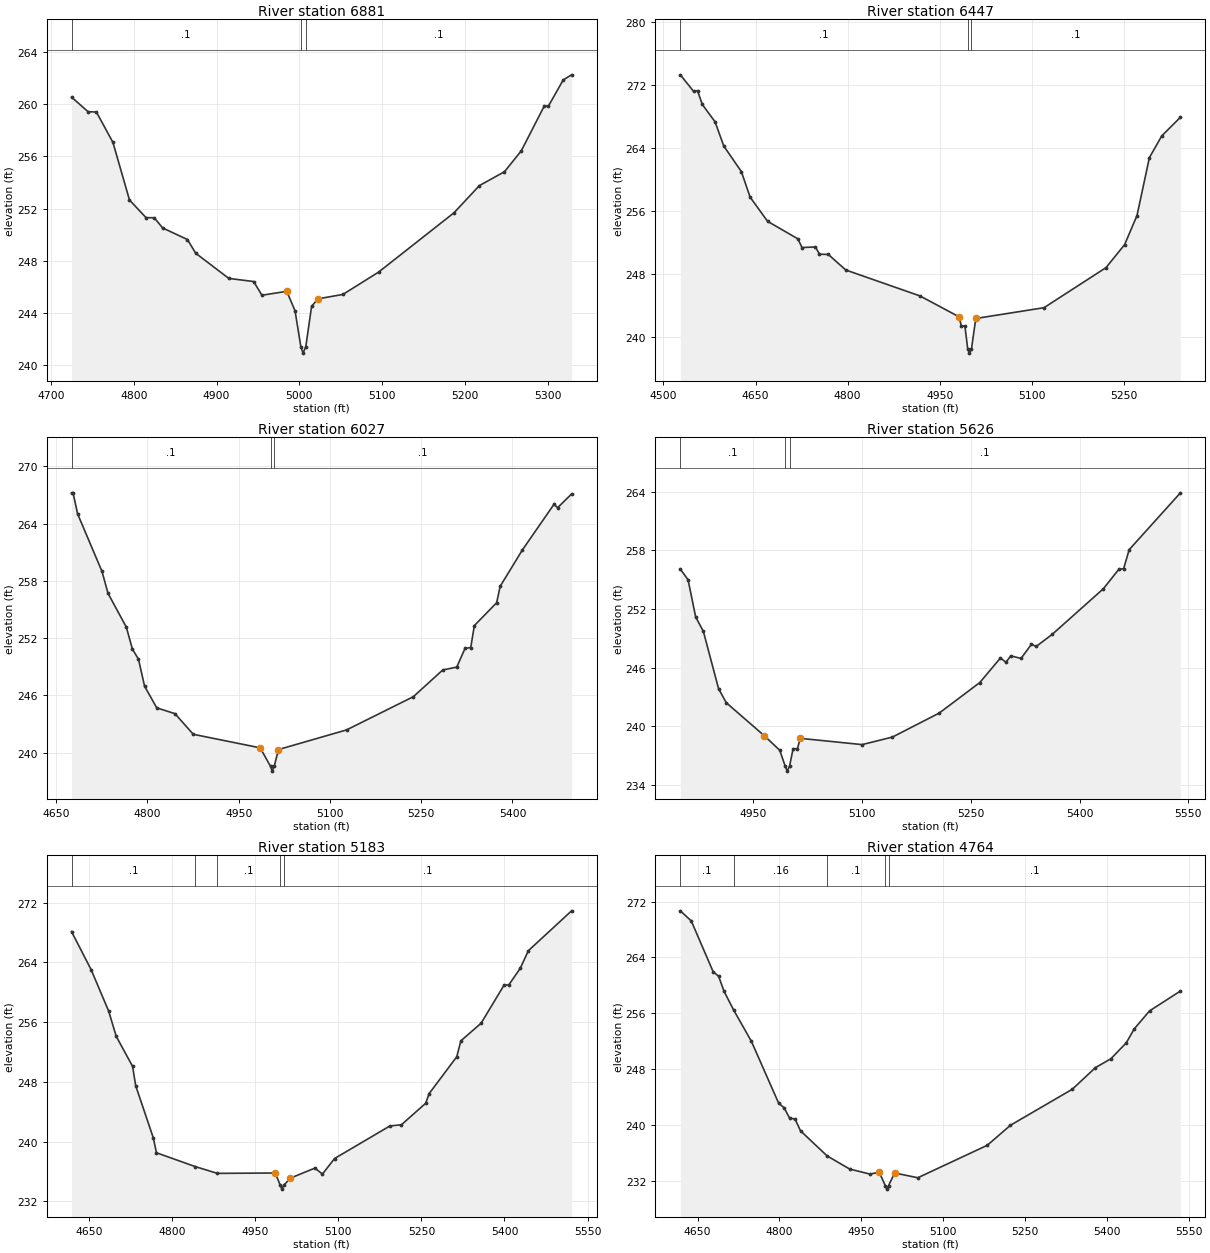
Type RM Length L Ch R = 1 ,6881    ,434,434,434
BEGIN DESCRIPTION:
UNT045 IN NURI 16.0
END DESCRIPTION:
XS GIS Cut Line= 3
      2321987.68     13307746.85      2321687.72     13307746.85
      2321387.71     13307796.86
#Sta/Elev= 30
  4724.8  260.55  4744.8  259.43  4754.8  259.41  4774.8  257.08  4794.8  252.66
  4814.8  251.31  4824.8   251.3  4834.8  250.52  4864.8  249.63  4874.8  248.58
  4914.8  246.65  4944.8  246.41  4954.8  245.36  4984.8  245.66  4994.8  244.17
  5001.8  241.42  5004.5  240.92  5007.8  241.42  5014.8   244.5  5022.3  245.08
  5052.6  245.42  5095.7  247.13    5187  251.69  5217.4  253.76  5247.8  254.83
  5268.1  256.43  5295.9  259.87    5301  259.87  5318.8  261.87  5328.9  262.26
#Mann= 3 ,-1 , 0
  4724.8      .1       0  5001.8     .07       0  5007.8      .1       0
Bank Sta=4984.8,5022.3
XS Rating Curve= 0 ,0
Exp/Cntr=0.3,0.1

Type RM Length L Ch R = 1 ,6447    ,420,420,420
BEGIN DESCRIPTION:
UNT045 IN NURI 15.0
END DESCRIPTION:
XS GIS Cut Line= 3
       2321887.7     13306996.88      2321587.72     13307346.85
      2321237.72     13307396.85
#Sta/Elev= 30
  4527.6  273.25    4549  271.16  4555.6  271.24  4563.2   269.5  4584.1  267.28
  4598.4  264.19  4626.9  260.97  4641.2  257.71  4669.7  254.64  4719.1  252.41
  4725.7  251.31  4747.6  251.39  4754.2  250.46  4768.5  250.44    4797  248.46
  4917.8  245.17  4981.4  242.52  4985.3  241.35  4991.1  241.35  4995.7   238.4
  4998.4   237.9  5001.7   238.4  5008.8   242.3  5119.9  243.67  5220.9  248.76
  5251.2  251.68  5271.4  255.38  5291.6  262.74  5311.8   265.5  5342.1  267.86
#Mann= 3 ,-1 , 0
  4527.6      .1       0  4995.7     .07       0  5001.7      .1       0
Bank Sta=4981.4,5008.8
XS Rating Curve= 0 ,0
Exp/Cntr=0.3,0.1

Type RM Length L Ch R = 1 ,6027    ,401,401,401
BEGIN DESCRIPTION:
UNT045 IN NURI 14.0
END DESCRIPTION:
XS GIS Cut Line= 3
      2321787.74     13306946.85      2321437.72     13306946.85
      2321187.73     13307346.84
#Sta/Elev= 30
  4675.4  267.23  4677.9  267.23  4685.4  265.02  4725.4     259  4735.4  256.69
  4765.4  253.16  4775.4  250.86  4785.4   249.8  4795.4  246.97  4815.4   244.7
  4845.4  244.09  4875.4  241.93  4985.4  240.51  5002.4  238.57  5005.2  238.07
  5008.4  238.57  5015.4  240.33  5127.4  242.39  5237.1  245.87  5285.4  248.67
  5308.4  248.97    5322  250.93  5331.4  251.02  5337.3  253.32  5373.9  255.71
  5379.8  257.44  5416.3  261.25  5468.2  266.03  5474.1  265.67  5497.1  267.11
#Mann= 3 ,-1 , 0
  4675.4      .1       0  5002.4     .07       0  5008.4      .1       0
Bank Sta=4985.4,5015.4
XS Rating Curve= 0 ,0
Exp/Cntr=0.3,0.1

Type RM Length L Ch R = 1 ,5626    ,443,443,443
BEGIN DESCRIPTION:
UNT045 IN NURI 13.0
END DESCRIPTION:
XS GIS Cut Line= 3
      2321437.76     13306546.84      2321287.72     13306596.85
       2320937.7     13306996.88
#Sta/Elev= 30
  4849.3  256.07  4859.9  254.99  4870.4  251.19    4881  249.72    4902  243.86
  4912.6  242.43  4965.3  239.04  4986.4  237.57  4993.9  235.94  4996.7  235.44
  4999.9  235.94  5004.8  237.73  5010.8  237.73  5014.6  238.79    5100  238.15
  5141.8  238.92  5206.3  241.37  5262.3  244.49  5290.8     247  5298.4  246.56
    5305  247.22  5319.2  246.95  5333.5   248.4  5340.1  248.18    5362   249.4
  5432.7  254.07    5454  256.05  5460.7  256.12  5468.3  258.06    5539  263.87
#Mann= 3 ,-1 , 0
  4849.3      .1       0  4993.9     .07       0  4999.9      .1       0
Bank Sta=4965.3,5014.6
XS Rating Curve= 0 ,0
Exp/Cntr=0.3,0.1

Type RM Length L Ch R = 1 ,5183    ,419,419,419
BEGIN DESCRIPTION:
UNT045 IN NURI 12.0
END DESCRIPTION:
XS GIS Cut Line= 3
      2321137.73     13305996.83      2320937.72     13306346.85
      2320637.74     13306746.82
#Sta/Elev= 30
  4618.1  268.13  4653.4  263.04  4685.1  257.49  4698.8   254.1  4728.3  250.09
    4734  247.48  4765.7  240.52  4771.5  238.51    4841  236.67  4881.6  235.75
    4986   235.8  4995.2  234.14    4998  233.64  5001.2  234.14  5013.3  235.11
  5057.7  236.46  5071.2  235.65  5093.1  237.74  5193.1   242.1  5213.9  242.26
  5257.7  245.14  5263.9  246.43  5313.9  251.38  5321.2   253.5  5357.7  255.85
  5399.4  260.98  5407.7  260.98  5428.5  263.21  5443.1  265.57  5521.2  270.91
#Mann= 5 ,-1 , 0
  4618.1      .1       0    4841     .16       0  4881.6      .1       0
  4995.2     .07       0  5001.2      .1       0
Bank Sta=4986,5013.3
XS Rating Curve= 0 ,0
Exp/Cntr=0.3,0.1

Type RM Length L Ch R = 1 ,4764    ,418,418,418
BEGIN DESCRIPTION:
UNT045 IN NURI 11.0
END DESCRIPTION:
XS GIS Cut Line= 3
       2321137.7     13305946.85      2320787.72     13305946.85
      2320387.69     13306346.88
#Sta/Elev= 30
  4618.5  270.69  4638.5  269.24  4678.5  261.96  4688.5  261.32  4698.5  259.15
  4716.4  256.42  4748.5  251.99  4798.5  243.11  4808.5  242.46  4818.5  240.97
  4828.5  240.85  4838.5  239.15  4887.1  235.56  4928.5  233.67    4966  232.94
  4982.6  233.23  4993.8  231.29  4996.5  230.79  4999.8  231.29  5010.9  233.11
  5053.3  232.42  5180.6  237.08    5223  239.95  5336.2  245.11  5378.6  248.21
  5406.9  249.48  5435.2  251.78  5449.3  253.73  5477.6  256.34  5534.2  259.19
#Mann= 5 ,-1 , 0
  4618.5      .1       0  4716.4     .16       0  4887.1      .1       0
  4993.8     .07       0  4999.8      .1       0
Bank Sta=4982.6,5010.9
XS Rating Curve= 0 ,0
Exp/Cntr=0.3,0.1

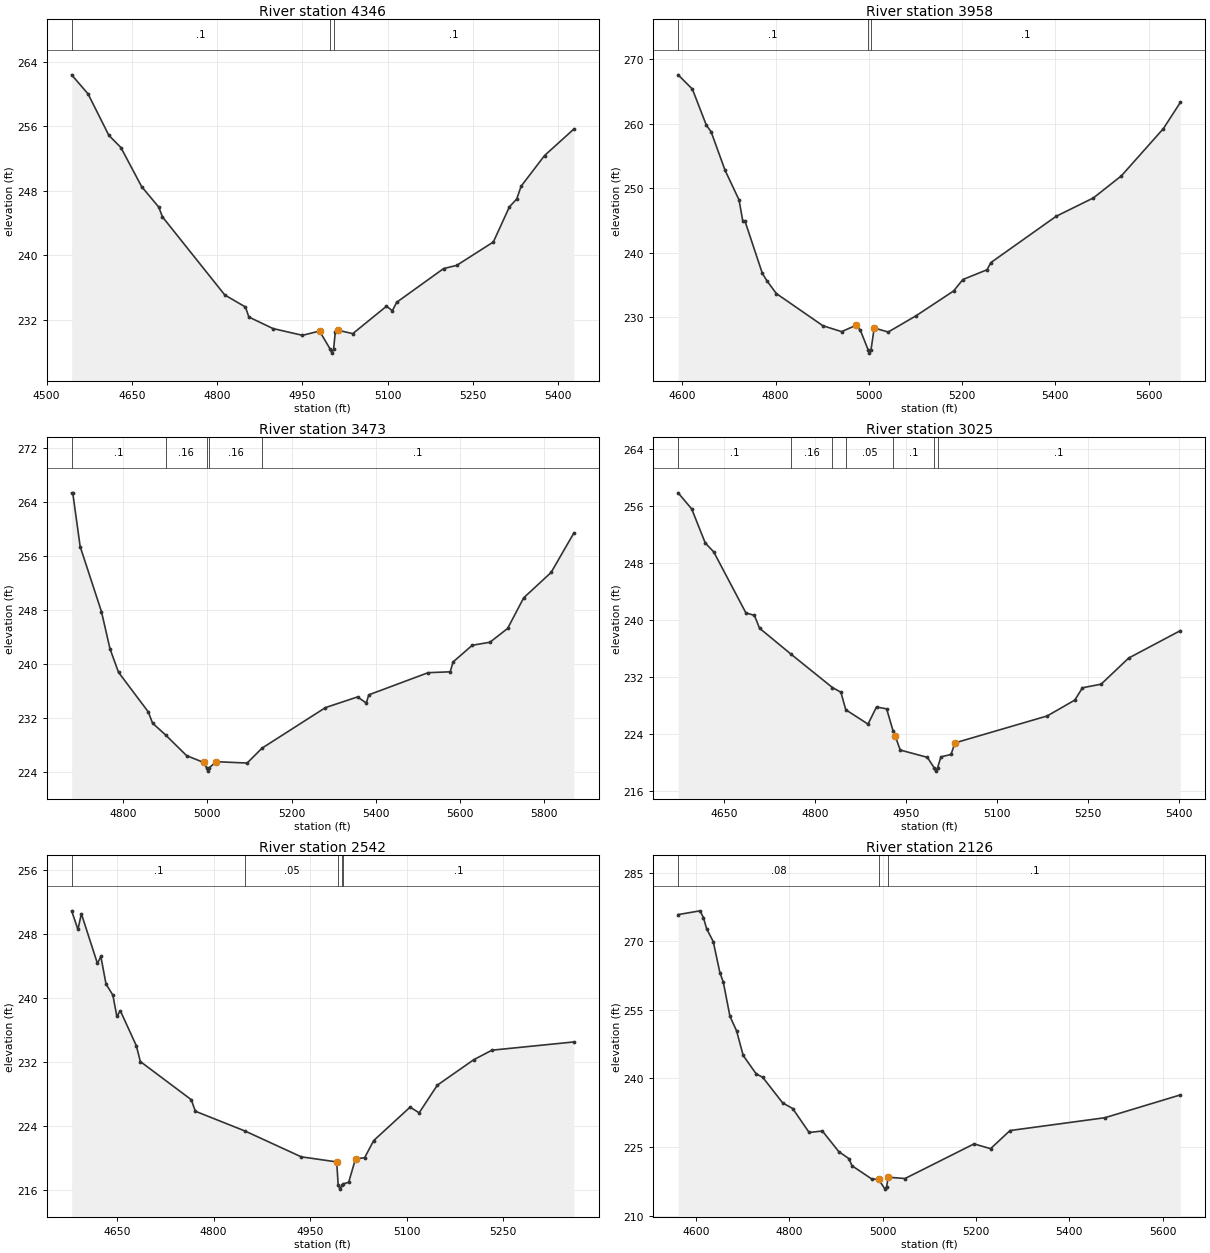
Type RM Length L Ch R = 1 ,4346    ,388,388,388
BEGIN DESCRIPTION:
UNT045 IN NURI 10.0
END DESCRIPTION:
XS GIS Cut Line= 3
      2320637.72     13305396.85      2320387.72     13305796.85
      2320287.72     13306196.84
#Sta/Elev= 30
    4544  262.38  4572.9  260.01  4609.5  254.87  4630.7  253.36  4667.2  248.51
  4697.3  245.97  4703.8  244.76  4813.5  235.07    4850  233.57  4855.9  232.33
  4898.4   230.9  4950.3  230.06  4980.3  230.59  4999.1  228.35  5001.9  227.85
  5005.1  228.35    5008  230.41  5012.8  230.69  5038.9  230.27  5098.2  233.67
  5108.5  233.11  5116.2  234.16  5198.7  238.34  5221.9  238.74  5286.3  241.64
  5314.6     246  5327.5  246.98  5335.2  248.56  5376.5  252.37    5428  255.65
#Mann= 3 ,-1 , 0
    4544      .1       0  4999.1     .07       0  5005.1      .1       0
Bank Sta=4980.3,5012.8
XS Rating Curve= 0 ,0
Exp/Cntr=0.3,0.1

Type RM Length L Ch R = 1 ,3958    ,485,485,485
BEGIN DESCRIPTION:
UNT045 IN NURI 9.0
END DESCRIPTION:
XS GIS Cut Line= 2
      2320055.46     13305226.31      2320034.65     13306303.11
#Sta/Elev= 30
  4590.8  267.58  4621.4  265.37  4651.4  259.77  4661.4  258.79  4691.4  252.81
  4721.4  248.22  4729.4  244.98  4734.4  244.88  4771.4  236.84  4781.4  235.67
  4801.4  233.71  4901.4  228.72  4941.4  227.81  4971.4  228.76  4981.4  228.06
  4998.4  224.98  5001.2  224.48  5004.4  224.98  5011.4  228.37  5041.4  227.75
  5101.4  230.28  5181.5   234.1  5201.5  235.88  5253.3  237.39  5261.5   238.5
  5401.5  245.67  5481.5  248.52  5541.5  251.94  5631.5  259.25  5667.8   263.3
#Mann= 3 ,-1 , 0
  4590.8      .1       0  4998.4     .07       0  5004.4      .1       0
Bank Sta=4971.4,5011.4
XS Rating Curve= 0 ,0
Exp/Cntr=0.3,0.1

Type RM Length L Ch R = 1 ,3473    ,448,448,448
BEGIN DESCRIPTION:
UNT045 IN NURI 8.0
END DESCRIPTION:
XS GIS Cut Line= 3
      2319687.73     13305096.81      2319637.72     13305446.85
      2319887.74      13306246.9
#Sta/Elev= 30
  4678.1  265.42  4680.7  265.42  4698.3  257.45  4748.9  247.78  4769.1  242.27
  4789.3  238.79    4860  232.91  4870.1  231.24  4901.2  229.48  4950.9  226.42
  4991.3  225.41  4998.4  224.62  5001.1  224.12  5004.4  224.62  5021.6  225.52
  5094.6  225.32  5129.9  227.53  5280.5  233.55  5356.5  235.13  5377.4  234.23
  5383.2  235.44  5524.1  238.73  5576.5  238.86  5583.3  240.32  5628.9   242.8
  5670.8  243.25  5712.7  245.29  5750.9  249.84  5815.9   253.6  5869.9  259.45
#Mann= 5 ,-1 , 0
  4678.1      .1       0  4901.2     .16       0  4998.4     .07       0
  5004.4     .16       0  5129.9      .1       0
Bank Sta=4991.3,5021.6
XS Rating Curve= 0 ,0
Exp/Cntr=0.3,0.1

Type RM Length L Ch R = 1 ,3025    ,483,483,483
BEGIN DESCRIPTION:
UNT045 IN NURI 7.0
END DESCRIPTION:
XS GIS Cut Line= 3
      2319437.74     13305146.82      2319237.72     13305546.85
      2319087.74     13305896.82
#Sta/Elev= 30
  4574.4  257.81  4596.8  255.55  4619.2  250.76  4633.1  249.52  4686.2  240.95
  4700.2  240.61  4708.6  238.81  4761.1  235.12  4828.9  230.47  4842.8  229.82
  4850.8  227.36  4887.5  225.34  4901.5  227.75  4918.2  227.48  4929.1  224.31
  4932.2  223.71  4940.6   221.7  4985.3  220.68  4996.3  219.24    4999  218.74
  5002.3  219.24  5007.7  220.74  5024.4  221.08  5030.7   222.7    5183  226.49
  5228.4  228.71  5241.1  230.44  5271.9  230.95  5317.2  234.61  5402.4  238.46
#Mann= 7 ,-1 , 0
  4574.4      .1       0  4761.1     .16       0  4828.9      .1       0
  4850.8     .05       0  4929.1      .1       0  4996.3     .07       0
  5002.3      .1       0
Bank Sta=4932.2,5030.7
XS Rating Curve= 0 ,0
Exp/Cntr=0.3,0.1

Type RM Length L Ch R = 1 ,2542    ,416,416,416
BEGIN DESCRIPTION:
UNT045 IN NURI 6.0
END DESCRIPTION:
XS GIS Cut Line= 3
      2319037.72     13304896.84      2318887.72     13305296.85
       2318637.7     13305546.88
#Sta/Elev= 30
  4579.2  250.86    4589  248.53  4594.3   250.5  4619.3  244.28  4624.6  245.16
  4632.6  241.72  4643.3  240.32  4649.5  237.65  4654.9  238.37  4679.8  233.99
    4686  232.02  4765.2  227.25  4771.5  225.81  4848.9  223.33  4936.1  220.11
  4991.3  219.47  4993.6  216.57  4996.4  216.07  4999.6  216.57  5001.3  216.72
  5009.9  216.93  5020.6  219.87  5034.7  219.99  5048.8  222.14  5105.4  226.32
  5119.5  225.61  5147.8  229.07  5204.4  232.25  5232.7  233.44    5360  234.47
#Mann= 5 ,-1 , 0
  4579.2      .1       0  4848.9     .05       0  4993.6     .04       0
  4999.6     .05       0  5001.3      .1       0
Bank Sta=4991.3,5020.6
XS Rating Curve= 0 ,0
Exp/Cntr=0.3,0.1

Type RM Length L Ch R = 1 ,2126    ,358,358,358
BEGIN DESCRIPTION:
UNT045 IN NURI 5.0
END DESCRIPTION:
XS GIS Cut Line= 3
      2318961.68     13304674.22      2318534.62      13305059.6
      2318357.55     13305528.34
#Sta/Elev= 30
  4561.4  275.81  4608.3  276.63  4615.7  275.14  4622.5  272.72  4636.7   269.9
  4650.9  263.13  4658.3  261.01  4672.5  253.57  4686.7  250.38  4700.9     245
  4728.6  240.99  4742.8  240.22  4785.4  234.64    4807  233.39  4842.2  228.16
  4870.6  228.48  4905.7  223.98  4927.4  222.44  4934.1  220.88  4976.7  217.97
  4990.9  217.93  5004.8  215.77  5008.1  216.27  5011.8  218.37  5047.7  218.09
  5195.6  225.66  5231.1  224.62  5272.7  228.58  5475.8  231.38  5637.7  236.37
#Mann= 3 , 0 , 0
  4561.4     .08       0  4990.9     .05       0  5011.8      .1       0
Bank Sta=4990.9,5011.8
XS Rating Curve= 0 ,0
Exp/Cntr=0.3,0.1

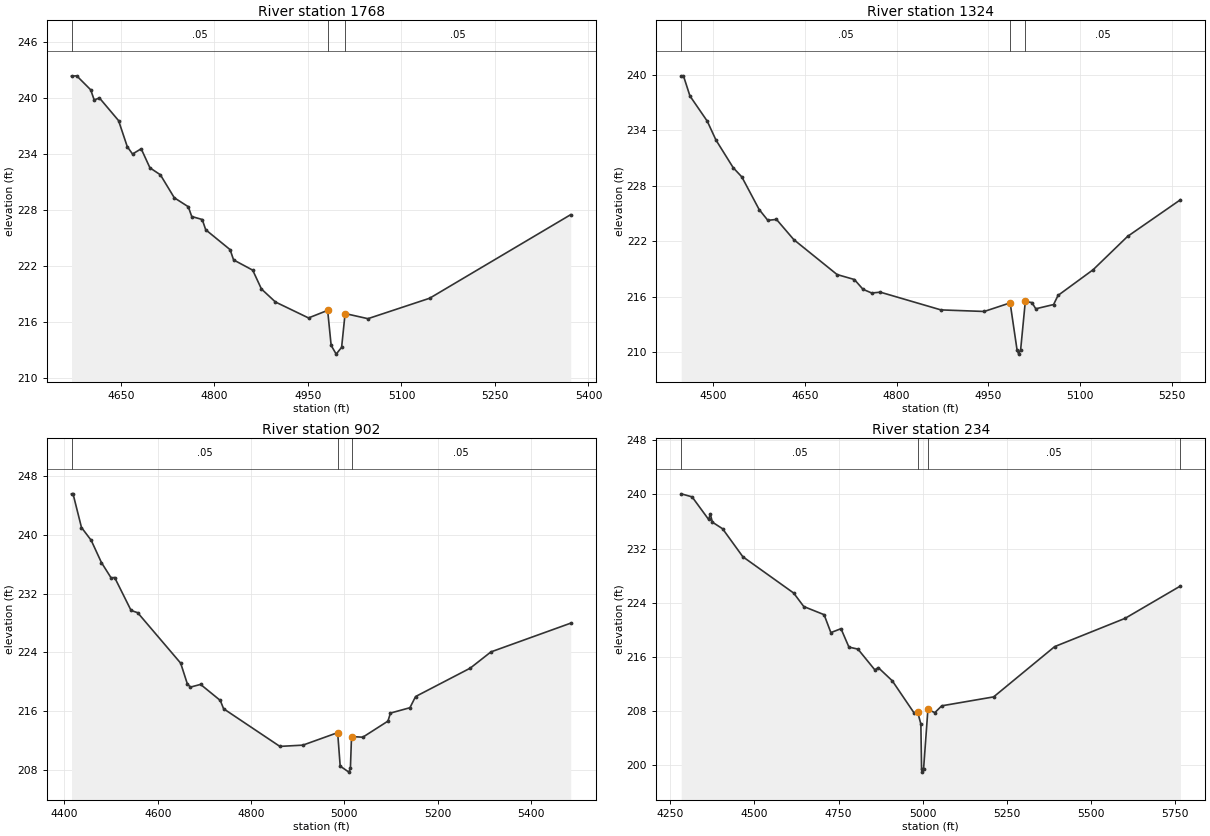
Type RM Length L Ch R = 1 ,1768    ,444,444,444
BEGIN DESCRIPTION:
UNT045 IN NURI 4.0
END DESCRIPTION:
XS GIS Cut Line= 3
      2318687.75     13304646.84      2318287.72     13304846.85
      2318037.72     13305096.86
#Sta/Elev= 30
  4570.7  242.37  4579.1   242.4  4601.5   240.9  4607.1  239.81  4615.5  240.03
  4646.2   237.6  4660.2   234.8  4668.6  234.02  4682.5  234.58  4696.5  232.54
  4713.3  231.79  4735.6  229.33    4758  228.37  4763.6  227.32  4780.4     227
    4786   225.9  4825.1  223.77  4830.7  222.67  4861.4  221.57  4875.4  219.55
  4897.8  218.16  4950.9  216.45  4981.6  217.26  4987.2  213.51  4995.3  212.57
    5004   213.3  5009.6  216.92  5046.2  216.37  5145.2  218.56  5371.5  227.52
#Mann= 3 , 0 , 0
  4570.7     .05       0  4981.6     .03       0  5009.6     .05       0
Bank Sta=4981.6,5009.6
XS Rating Curve= 0 ,0
Exp/Cntr=0.3,0.1

Type RM Length L Ch R = 1 ,1324    ,422,422,422
BEGIN DESCRIPTION:
UNT045 IN NURI 3.0
END DESCRIPTION:
XS GIS Cut Line= 3
      2318337.75     13304196.82      2317937.72     13304596.85
      2317787.74     13304796.83
#Sta/Elev= 30
    4448  239.91  4451.6  239.91  4462.2  237.73  4490.5     235  4504.6  232.97
  4532.9  229.96    4547  228.96  4575.3  225.43  4589.5  224.26  4603.6  224.36
  4631.9  222.17  4702.6  218.39  4730.9  217.85    4745  216.79  4759.2  216.39
  4773.3  216.48  4872.3  214.56    4943  214.39  4985.4  215.32  4996.6  210.27
  4999.3  209.77  5002.6  210.27  5010.2  215.48    5021  215.35  5027.3  214.68
  5056.4  215.14  5063.7  216.13    5121  218.91  5177.3  222.52  5263.7  226.49
#Mann= 3 , 0 , 0
    4448     .05       0  4985.4     .03       0  5010.2     .05       0
Bank Sta=4985.4,5010.2
XS Rating Curve= 0 ,0
Exp/Cntr=0.3,0.1

Type RM Length L Ch R = 1 ,902     ,668,668,668
BEGIN DESCRIPTION:
UNT045 IN NURI 2.0
END DESCRIPTION:
XS GIS Cut Line= 3
      2318137.72     13303846.85      2317737.72     13304196.85
      2317537.73     13304696.83
#Sta/Elev= 30
  4415.1  245.57  4418.4  245.57  4436.5  240.99  4457.3  239.25  4479.2  236.23
    4500  234.14  4507.6  234.19  4542.8  229.71    4557   229.4  4649.1  222.54
  4663.3  219.74  4669.9  219.28  4691.8  219.65    4734  217.47  4741.1  216.34
  4861.7  211.22    4911  211.39  4985.6  213.09    4991  208.54  5009.6  207.72
  5012.9  208.22  5015.3  212.56  5039.5  212.47  5093.4  214.66  5098.7  215.75
  5140.5  216.48  5152.6     218  5269.7  221.86  5314.1  224.07  5485.1  227.98
#Mann= 3 , 0 , 0
  4415.1     .05       0  4985.6     .03       0  5015.3     .05       0
Bank Sta=4985.6,5015.3
XS Rating Curve= 0 ,0
Exp/Cntr=0.3,0.1

Type RM Length L Ch R = 1 ,234     ,0,0,0
BEGIN DESCRIPTION:
UNT045 IN NURI 1.0
END DESCRIPTION:
XS GIS Cut Line= 3
      2318039.81     13303533.57      2317438.23      13303592.4
      2317237.73     13304446.83
#Sta/Elev= 30
  4282.9  240.09  4315.1  239.64  4364.2   236.3  4369.2  237.09  4375.4   235.9
  4405.6  234.93  4465.8  230.79  4616.6  225.43  4646.7  223.43    4707  222.23
  4727.1  219.58  4757.2  220.16  4780.7  217.44  4807.5  217.14  4857.7  214.07
  4867.8  214.41  4909.4  212.46  4974.1  207.71  4984.4   207.9  4994.3  206.07
  4996.4  199.46  4999.1  198.96  5002.4  199.46  5015.2  208.23  5035.7  207.75
  5056.3  208.76  5210.4  210.08  5391.5  217.51  5600.7  221.69    5765  226.47
#Mann= 4 ,-1 , 0
  4282.9     .05       0  4984.4     .03       0  5015.2     .05       0
    5765      .1       0
Bank Sta=4984.4,5015.2
XS Rating Curve= 0 ,0
Exp/Cntr=0.3,0.1

Chan Stop Cuts=-1
Use User Specified Reach Order=0
Composite Channel Slope=5