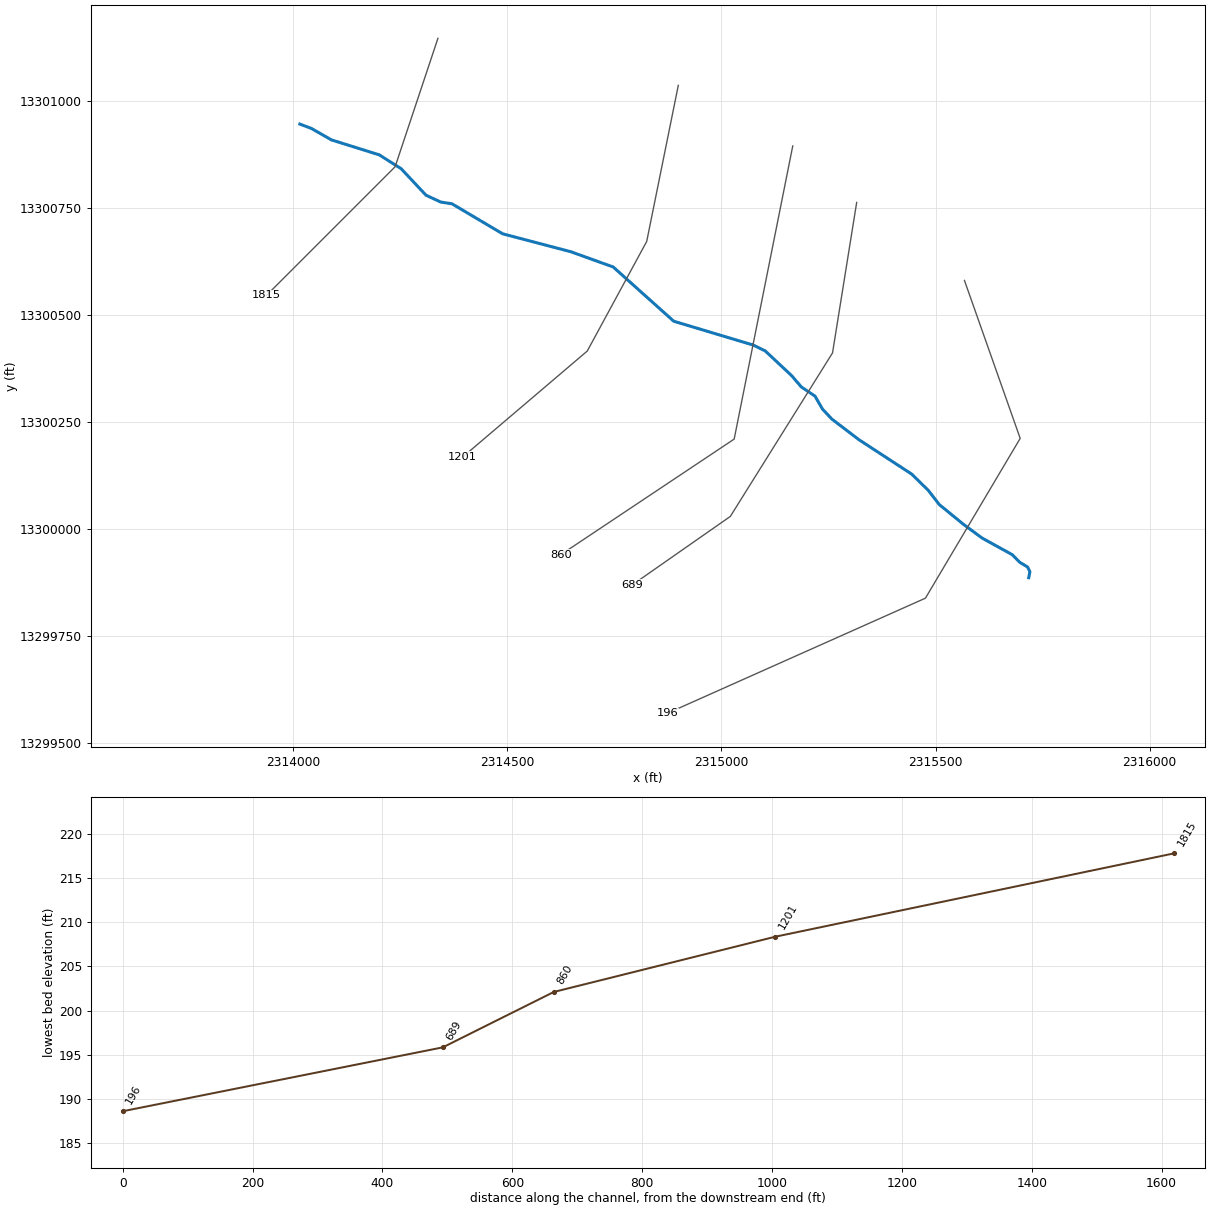
--- UNT046 IN NURI.prj (project) ---

Proj Title=UNT046 IN NURI Base Level Engineering
Current Plan=p01
Default Exp/Contr=0.3,0.1
English Units
Geom File=g01
Flow File=f01
Plan File=p01
BEGIN DESCRIPTION:
UNT046 IN NURI
END DESCRIPTION:

--- UNT046 IN NURI.p01 (plan) ---

Plan Title=Multiple Run
Short Identifier=Multiple
Geom File=g01
Flow File=f01
Subcritical Flow
K Sum by GR= 0
Std Step Tol= 0.01
Critical Tol= 0.01
Num of Std Step Trials= 20
Max Error Tol= 0.3
Flow Tol Ratio= 0.001
Split Flow NTrial= 30
Split Flow Tol= 0.02
Split Flow Ratio= 0.02
Log Output Level= 0
Friction Slope Method= 1
Unsteady Friction Slope Method= 2
Unsteady Bridges Friction Slope Method= 1
Parabolic Critical Depth
Global Vel Dist=  1 , 1 , 1
Global Log Level= 0
CheckData=True
Encroach Param= -1, 0, 0, 0
BEGIN DESCRIPTION:
Multiple Run
END DESCRIPTION:

--- UNT046 IN NURI.f01 (steady flow) ---

Flow Title=Multiple
Number of Profiles=7
Profile Names=10-year,25-year,50-year,1pct_min,100-year,1pct_plu,500-year
River Rch & RM= UNT046 IN NURI,Reach-1,1815
     367     509     625     564     763    1031    1136
Boundary for River Rch & Prof#=UNT046 IN NURI,Reach-1,1
Up Type=0
Dn Type=3
Dn Slope=0.005
Boundary for River Rch & Prof#=UNT046 IN NURI,Reach-1,2
Up Type=0
Dn Type=3
Dn Slope=0.005
Boundary for River Rch & Prof#=UNT046 IN NURI,Reach-1,3
Up Type=0
Dn Type=3
Dn Slope=0.005
Boundary for River Rch & Prof#=UNT046 IN NURI,Reach-1,4
Up Type=0
Dn Type=3
Dn Slope=0.005
Boundary for River Rch & Prof#=UNT046 IN NURI,Reach-1,5
Up Type=0
Dn Type=3
Dn Slope=0.005
Boundary for River Rch & Prof#=UNT046 IN NURI,Reach-1,6
Up Type=0
Dn Type=3
Dn Slope=0.005
Boundary for River Rch & Prof#=UNT046 IN NURI,Reach-1,7
Up Type=0
Dn Type=3
Dn Slope=0.005

--- UNT046 IN NURI.g01 (geometry) ---

Geom Title=Existing Conditions

River Reach=UNT046 IN NURI,Reach-1
Reach XY= 30
      2314015.22     13300946.48      2314042.44     13300936.21
      2314088.87     13300909.63      2314200.46     13300874.73
      2314251.70     13300842.40      2314309.90     13300780.38
      2314344.32     13300764.38      2314370.42     13300760.41
      2314488.80     13300690.25      2314648.08     13300648.37
      2314747.04     13300612.77      2314888.53     13300486.04
      2315074.83     13300430.14      2315102.24     13300416.65
      2315163.86     13300359.01      2315186.41     13300332.65
      2315218.61     13300311.01      2315235.94     13300280.86
      2315257.88     13300257.49      2315320.85     13300209.47
      2315444.45     13300128.87      2315483.22     13300090.82
      2315508.75     13300057.86      2315565.03     13300011.81
      2315608.84     13299979.49      2315679.19     13299940.76
      2315696.71     13299923.00      2315715.14     13299911.88
      2315720.49     13299900.91      2315717.72     13299886.86

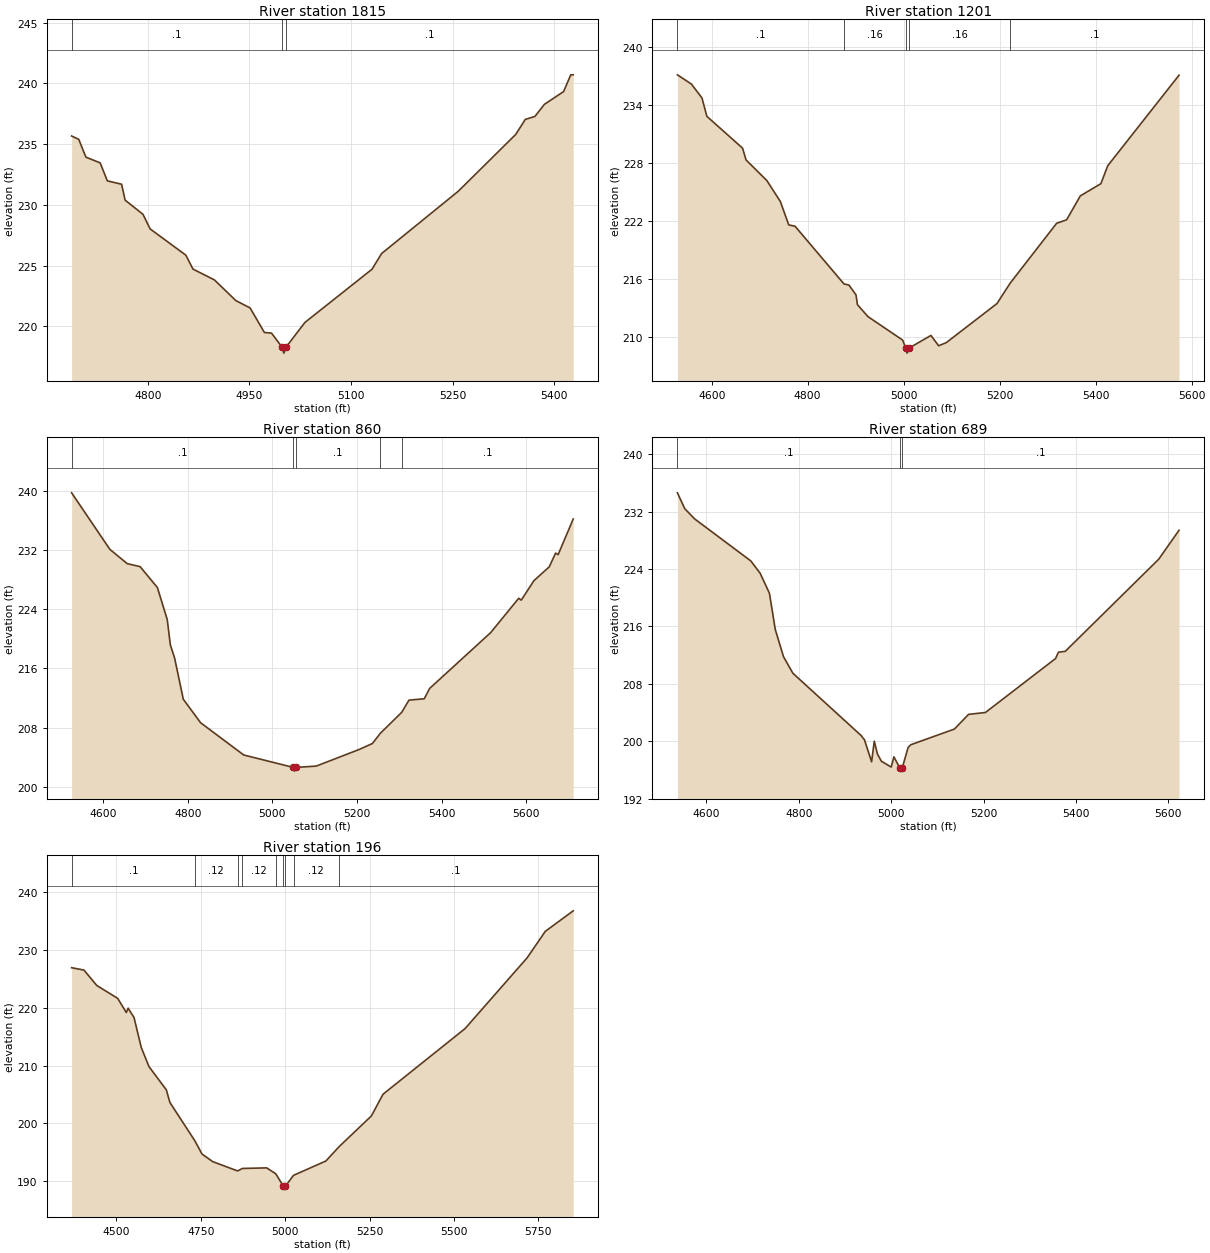
Type RM Length L Ch R = 1,1815,614,614,614
BEGIN DESCRIPTION:
UNT046 IN NURI 4.0
END DESCRIPTION:
XS GIS Cut Line= 3
      2314337.71     13301146.83      2314237.72     13300846.85
      2313937.70     13300546.83
#Sta/Elev= 30
  4687.6  235.67  4698.1  235.40  4708.7  233.93  4729.7  233.46  4740.3  231.98
  4761.4  231.70  4766.6  230.39  4793.0  229.22  4803.5  228.02  4856.2  225.86
  4866.8  224.71  4898.4  223.82  4930.0  222.12  4951.1  221.51  4972.2  219.49
  4982.7  219.44  4998.2  218.29  5000.9  217.79  5004.2  218.29  5032.1  220.32
  5131.1  224.70  5145.2  225.99  5258.4  231.12  5343.2  235.80  5357.4  237.04
  5371.5  237.28  5385.6  238.28  5413.9  239.33  5424.5  240.71  5428.1  240.71
#Mann=3,-1,0
  4687.6     0.1       0  4998.2    0.07       0  5004.2     0.1       0
Bank Sta=4998.2,5004.2
Exp/Cntr=0.3,0.1

Type RM Length L Ch R = 1,1201,341,341,341
BEGIN DESCRIPTION:
UNT046 IN NURI 3.0
END DESCRIPTION:
XS GIS Cut Line= 4
      2314899.20     13301037.01      2314825.42     13300672.45
      2314686.53     13300416.38      2314395.71     13300168.96
#Sta/Elev= 30
  4528.6  237.17  4557.8  236.21  4579.8  234.77  4590.0  232.87  4664.3  229.58
  4671.6  228.36  4715.0  226.22  4743.0  224.06  4760.6  221.63  4773.6  221.50
  4875.7  215.52  4885.9  215.41  4900.6  214.40  4903.7  213.38  4925.6  212.14
  4997.9  209.71  5004.4  208.86  5007.1  208.36  5010.4  208.86  5056.8  210.19
  5072.9  209.12  5088.9  209.45  5194.4  213.49  5222.0  215.61  5318.7  221.80
  5339.5  222.16  5368.1  224.64  5410.9  225.90  5425.2  227.76  5573.7  237.13
#Mann=5,-1,0
  4528.6     0.1       0  4875.7    0.16       0  5004.4    0.07       0
  5010.4    0.16       0  5222.0     0.1       0
Bank Sta=5004.4,5010.4
Exp/Cntr=0.3,0.1

Type RM Length L Ch R = 1,860,171,171,171
BEGIN DESCRIPTION:
UNT046 IN NURI 2.0
END DESCRIPTION:
XS GIS Cut Line= 3
      2315166.56     13300895.50      2315029.70     13300210.72
      2314624.93     13299940.87
#Sta/Elev= 30
  4525.8  239.70  4616.2  232.06  4657.0  230.14  4687.6  229.73  4728.4  226.91
  4751.7  222.58  4759.0  219.16  4769.2  217.36  4789.6  211.82  4830.4  208.65
  4932.3  204.29  5049.6  202.61  5052.4  202.11  5055.6  202.61  5103.6  202.79
  5205.7  205.05  5236.3  205.84  5255.2  207.23  5305.5  210.05  5322.7  211.70
  5358.7  211.88  5371.5  213.28  5515.7  220.82  5581.8  225.45  5587.9  225.21
  5617.9  227.84  5654.0  229.70  5669.0  231.56  5675.0  231.35  5710.6  236.16
#Mann=5,-1,0
  4525.8     0.1       0  5049.6    0.07       0  5055.6     0.1       0
  5255.2    0.16       0  5305.5     0.1       0
Bank Sta=5049.6,5055.6
Exp/Cntr=0.3,0.1

Type RM Length L Ch R = 1,689,493,493,493
BEGIN DESCRIPTION:
UNT046 IN NURI 2.1
END DESCRIPTION:
XS GIS Cut Line= 4
      2315315.87     13300763.55      2315259.45     13300412.04
      2315020.74     13300030.09      2314791.74     13299870.22
#Sta/Elev= 30
  4537.3  234.62  4553.2  232.41  4574.5  230.99  4696.0  225.14  4716.3  223.42
  4736.5  220.62  4749.1  215.58  4766.9  211.79  4787.2  209.48  4934.8  200.81
  4942.2  200.20  4957.6  197.14  4963.4  200.01  4970.2  198.23  4978.8  197.22
  5000.0  196.41  5005.9  197.83  5018.2  196.34  5021.0  195.84  5024.2  196.34
  5036.6  199.13  5042.5  199.52  5136.8  201.70  5167.5  203.75  5204.0  204.01
  5355.8  211.53  5361.9  212.41  5376.7  212.53  5579.1  225.37  5623.0  229.40
#Mann=3,-1,0
  4537.3     0.1       0  5018.2    0.07       0  5024.2     0.1       0
Bank Sta=5018.2,5024.2
Exp/Cntr=0.3,0.1

Type RM Length L Ch R = 1,196,0,0,0
BEGIN DESCRIPTION:
UNT046 IN NURI 1.0
END DESCRIPTION:
XS GIS Cut Line= 4
      2315567.60     13300581.33      2315697.82     13300212.38
      2315476.46     13299839.12      2314873.17     13299570.02
#Sta/Elev= 30
  4367.3  226.95  4403.9  226.54  4441.9  223.87  4503.7  221.65  4529.4  219.19
  4534.7  219.94  4552.3  218.31  4573.5  213.15  4596.5  209.82  4647.8  205.81
  4658.4  203.62  4732.6  196.96  4753.5  194.69  4785.3  193.37  4859.0  191.76
  4873.4  192.19  4945.1  192.29  4972.2  191.26  4994.5  189.11  4997.3  188.61
  5000.5  189.11  5024.7  191.00  5120.5  193.48  5159.4  195.95  5255.4  201.29
  5289.7  205.04  5532.8  216.41  5716.7  228.67  5770.5  233.25  5853.1  236.80
#Mann=9,-1,0
  4367.3     0.1       0  4732.6    0.12       0  4859.0     0.1       0
  4873.4    0.12       0  4972.2     0.1       0  4994.5    0.07       0
  5000.5     0.1       0  5024.7    0.12       0  5159.4     0.1       0
Bank Sta=4994.5,5000.5
Exp/Cntr=0.3,0.1

Chan Stop Cuts=-1