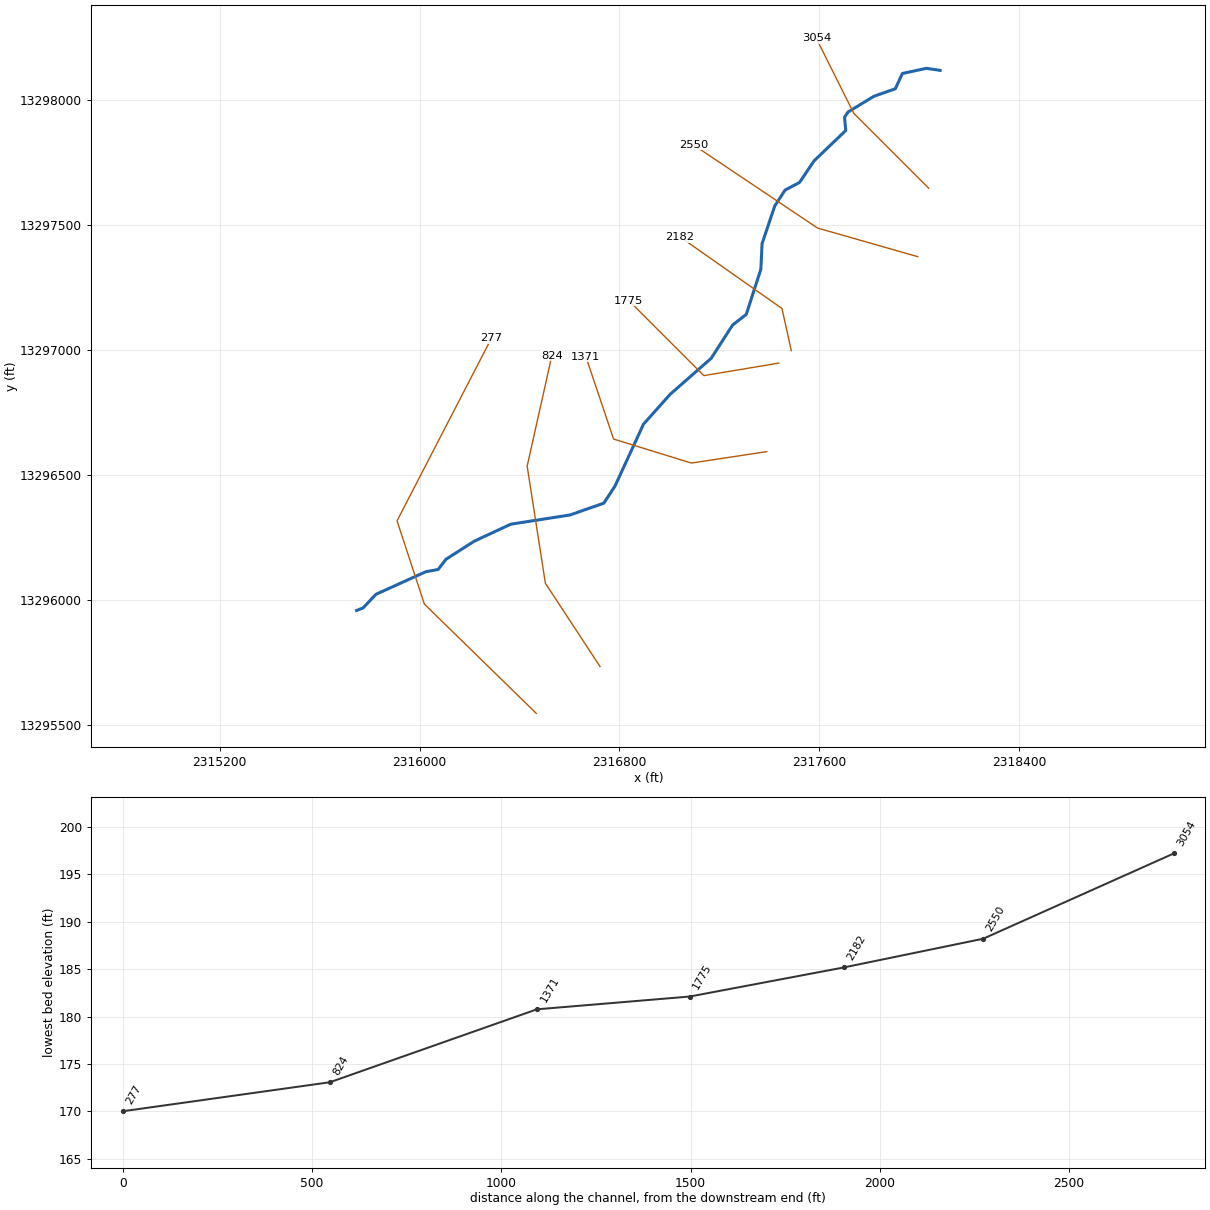
--- UNT047 IN NURI.prj (project) ---

Proj Title=UNT047 IN NURI Base Level Engineering
Current Plan=p01
Default Exp/Contr=0.3,0.1
English Units
Geom File=g01
Flow File=f01
Plan File=p01
BEGIN DESCRIPTION:
UNT047 IN NURI
END DESCRIPTION:

--- UNT047 IN NURI.p01 (plan) ---

Plan Title=Multiple Run
Short Identifier=Multiple
Geom File=g01
Flow File=f01
Subcritical Flow
K Sum by GR= 0
Std Step Tol= 0.01
Critical Tol= 0.01
Num of Std Step Trials= 20
Max Error Tol= 0.3
Flow Tol Ratio= 0.001
Split Flow NTrial= 30
Split Flow Tol= 0.02
Split Flow Ratio= 0.02
Log Output Level= 0
Friction Slope Method= 1
Unsteady Friction Slope Method= 2
Unsteady Bridges Friction Slope Method= 1
Parabolic Critical Depth
Global Vel Dist=  1 , 1 , 1
Global Log Level= 0
CheckData=True
Encroach Param= -1, 0, 0, 0
BEGIN DESCRIPTION:
Multiple Run
END DESCRIPTION:

--- UNT047 IN NURI.f01 (steady flow) ---

Flow Title=Multiple
Number of Profiles=7
Profile Names=10-year,25-year,50-year,1pct_min,100-year,1pct_plu,500-year
River Rch & RM= UNT047 IN NURI,Reach-1,3054
     544     761     941     850    1149    1554    1722
River Rch & RM= UNT047 IN NURI,Reach-1,1371
     737    1050    1315    1202    1626    2199    2494
Boundary for River Rch & Prof#=UNT047 IN NURI,Reach-1,1
Up Type=0
Dn Type=3
Dn Slope=0.005
Boundary for River Rch & Prof#=UNT047 IN NURI,Reach-1,2
Up Type=0
Dn Type=3
Dn Slope=0.005
Boundary for River Rch & Prof#=UNT047 IN NURI,Reach-1,3
Up Type=0
Dn Type=3
Dn Slope=0.005
Boundary for River Rch & Prof#=UNT047 IN NURI,Reach-1,4
Up Type=0
Dn Type=3
Dn Slope=0.005
Boundary for River Rch & Prof#=UNT047 IN NURI,Reach-1,5
Up Type=0
Dn Type=3
Dn Slope=0.005
Boundary for River Rch & Prof#=UNT047 IN NURI,Reach-1,6
Up Type=0
Dn Type=3
Dn Slope=0.005
Boundary for River Rch & Prof#=UNT047 IN NURI,Reach-1,7
Up Type=0
Dn Type=3
Dn Slope=0.005

--- UNT047 IN NURI.g01 (geometry) ---

Geom Title=Existing Conditions

River Reach=UNT047 IN NURI,Reach-1
Reach XY= 30
      2318083.41     13298118.63      2318028.30     13298126.83
      2317932.33     13298106.09      2317904.07     13298045.01
      2317818.51     13298014.99      2317714.74     13297951.88
      2317700.88     13297931.13      2317705.65     13297877.88
      2317578.74     13297756.42      2317520.90     13297670.16
      2317462.68     13297639.36      2317421.30     13297575.43
      2317370.83     13297425.57      2317365.84     13297322.42
      2317307.42     13297141.92      2317252.83     13297099.25
      2317166.90     13296965.92      2317003.42     13296822.66
      2316896.07     13296702.45      2316782.01     13296454.51
      2316737.17     13296386.14      2316601.84     13296338.98
      2316364.97     13296302.11      2316218.82     13296234.20
      2316105.56     13296161.78      2316074.11     13296120.74
      2316025.22     13296111.96      2315825.17     13296021.42
      2315773.75     13295966.83      2315747.72     13295956.86

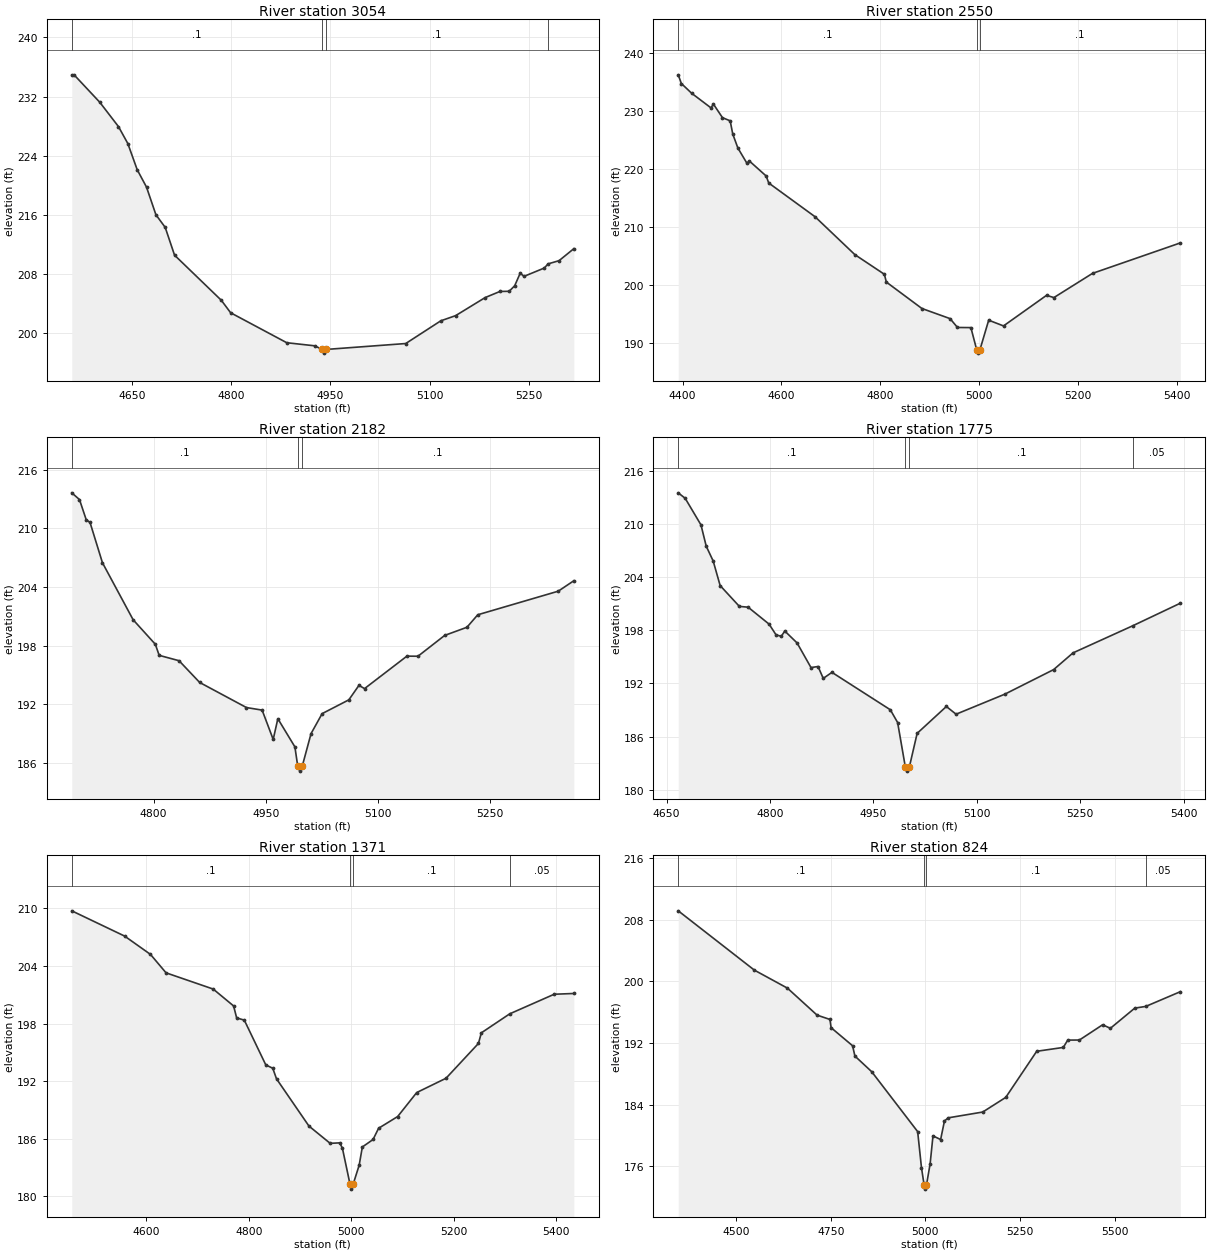
Type RM Length L Ch R = 1,3054,504,504,504
BEGIN DESCRIPTION:
UNT047 IN NURI 7.0
END DESCRIPTION:
XS GIS Cut Line= 3
      2318037.71     13297646.87      2317737.72     13297946.85
      2317587.70     13298246.89
#Sta/Elev= 30
  4558.7  234.94  4562.2  234.94  4601.1  231.22  4629.4  227.92  4643.5  225.63
  4657.7  222.08  4671.8  219.72  4686.0  215.98  4700.1  214.26  4714.2  210.50
  4785.0  204.38  4799.1  202.69  4884.0  198.63  4926.4  198.21  4937.5  197.72
  4940.3  197.22  4943.5  197.72  5064.0  198.52  5117.1  201.60  5139.5  202.30
  5184.2  204.75  5206.6  205.58  5220.5  205.60  5228.9  206.35  5237.3  208.07
  5242.9  207.62  5273.6  208.75  5279.5  209.32  5296.0  209.75  5318.4  211.38
#Mann=4,-1,0
  4558.7     0.1       0  4937.5    0.07       0  4943.5     0.1       0
  5279.5    0.05       0
Bank Sta=4937.5,4943.5
Exp/Cntr=0.3,0.1

Type RM Length L Ch R = 1,2550,368,368,368
BEGIN DESCRIPTION:
UNT047 IN NURI 6.0
END DESCRIPTION:
XS GIS Cut Line= 3
      2317993.80     13297372.98      2317592.78     13297487.56
      2317095.41     13297820.87
#Sta/Elev= 30
  4391.2  236.29  4397.5  234.79  4418.3  233.11  4457.3  230.59  4462.5  231.22
  4480.7  228.89  4496.3  228.34  4501.5  226.06  4511.9  223.64  4530.1  221.02
  4535.3  221.39  4569.1  218.81  4574.3  217.60  4667.9  211.78  4748.5  205.23
  4808.3  201.83  4812.2  200.49  4884.2  195.92  4941.2  194.17  4956.2  192.64
  4983.3  192.62  4995.3  188.71  4998.0  188.21  5001.3  188.71  5019.3  193.90
  5049.3  192.91  5136.3  198.19  5151.3  197.81  5229.4  201.99  5407.0  207.25
#Mann=3,-1,0
  4391.2     0.1       0  4995.3    0.07       0  5001.3     0.1       0
Bank Sta=4995.3,5001.3
Exp/Cntr=0.3,0.1

Type RM Length L Ch R = 1,2182,407,407,407
BEGIN DESCRIPTION:
UNT047 IN NURI 5.0
END DESCRIPTION:
XS GIS Cut Line= 3
      2317487.72     13296996.84      2317450.42     13297165.51
      2317042.65     13297451.82
#Sta/Elev= 30
  4690.7  213.64  4701.0  212.95  4710.0  210.89  4715.1  210.61  4731.7  206.49
  4772.7  200.66  4802.4  198.15  4807.5  197.02  4834.1  196.47  4861.6  194.25
  4924.2  191.68  4945.1  191.42  4959.9  188.42  4966.1  190.54  4988.9  187.66
  4992.7  185.68  4995.4  185.18  4998.7  185.68  5010.5  189.02  5025.3  191.06
  5061.0  192.47  5074.5  193.95  5082.0  193.62  5138.6  196.94  5153.4  196.93
  5189.1  199.06  5218.8  199.89  5233.3  201.17  5340.8  203.58  5361.7  204.65
#Mann=3,-1,0
  4690.7     0.1       0  4992.7    0.07       0  4998.7     0.1       0
Bank Sta=4992.7,4998.7
Exp/Cntr=0.3,0.1

Type RM Length L Ch R = 1,1775,404,404,404
BEGIN DESCRIPTION:
UNT047 IN NURI 4.0
END DESCRIPTION:
XS GIS Cut Line= 3
      2317437.73     13296946.86      2317137.72     13296896.85
      2316837.73     13297196.85
#Sta/Elev= 30
  4666.8  213.50  4676.9  212.88  4699.8  209.88  4707.4  207.48  4717.5  205.81
  4727.6  203.04  4755.5  200.69  4768.2  200.60  4798.6  198.69  4808.7  197.48
  4816.3  197.32  4821.4  197.91  4839.2  196.57  4859.4  193.79  4869.6  193.91
  4877.2  192.57  4889.8  193.25  4974.5  189.03  4985.1  187.59  4996.2  182.61
  4999.0  182.11  5002.2  182.61  5013.4  186.37  5055.8  189.40  5069.9  188.53
  5140.6  190.79  5211.4  193.56  5239.6  195.45  5326.9  198.53  5395.2  201.05
#Mann=4,-1,0
  4666.8     0.1       0  4996.2    0.07       0  5002.2     0.1       0
  5326.9    0.05       0
Bank Sta=4996.2,5002.2
Exp/Cntr=0.3,0.1

Type RM Length L Ch R = 1,1371,547,547,547
BEGIN DESCRIPTION:
UNT047 IN NURI 3.0
END DESCRIPTION:
XS GIS Cut Line= 4
      2317389.62     13296592.59      2317087.72     13296546.85
      2316776.34     13296642.89      2316665.28     13296973.22
#Sta/Elev= 30
  4454.4  209.75  4557.5  207.12  4608.0  205.21  4638.4  203.29  4730.4  201.60
  4770.2  199.84  4776.1  198.60  4791.1  198.36  4833.0  193.70  4846.6  193.35
  4853.9  192.25  4917.2  187.33  4958.6  185.53  4977.3  185.58  4982.5  185.02
  4997.4  181.26  5000.2  180.76  5003.4  181.26  5015.2  183.25  5021.4  185.15
  5042.3  185.93  5053.1  187.10  5090.3  188.32  5127.5  190.82  5184.7  192.31
  5248.0  195.94  5253.6  197.04  5309.0  199.02  5395.7  201.06  5434.1  201.14
#Mann=4,-1,0
  4454.4     0.1       0  4997.4    0.07       0  5003.4     0.1       0
  5309.0    0.05       0
Bank Sta=4997.4,5003.4
Exp/Cntr=0.3,0.1

Type RM Length L Ch R = 1,824,547,547,547
BEGIN DESCRIPTION:
UNT047 IN NURI 2.0
END DESCRIPTION:
XS GIS Cut Line= 4
      2316722.15     13295732.31      2316503.37     13296065.68
      2316430.46     13296534.43      2316529.42     13296977.17
#Sta/Elev= 30
  4346.9  209.16  4548.0  201.47  4635.5  199.13  4713.8  195.63  4747.8  195.07
  4750.9  194.00  4807.6  191.66  4813.8  190.32  4858.2  188.29  4979.6  180.52
  4989.7  175.84  4996.8  173.56  4999.6  173.06  5002.8  173.56  5012.6  176.36
  5020.1  179.97  5040.3  179.49  5050.4  181.90  5060.6  182.31  5151.6  183.06
  5212.4  184.96  5294.2  190.94  5364.4  191.44  5376.2  192.39  5407.0  192.40
  5468.4  194.38  5488.9  193.92  5553.4  196.54  5582.4  196.76  5673.7  198.67
#Mann=4,-1,0
  4346.9     0.1       0  4996.8    0.07       0  5002.8     0.1       0
  5582.4    0.05       0
Bank Sta=4996.8,5002.8
Exp/Cntr=0.3,0.1

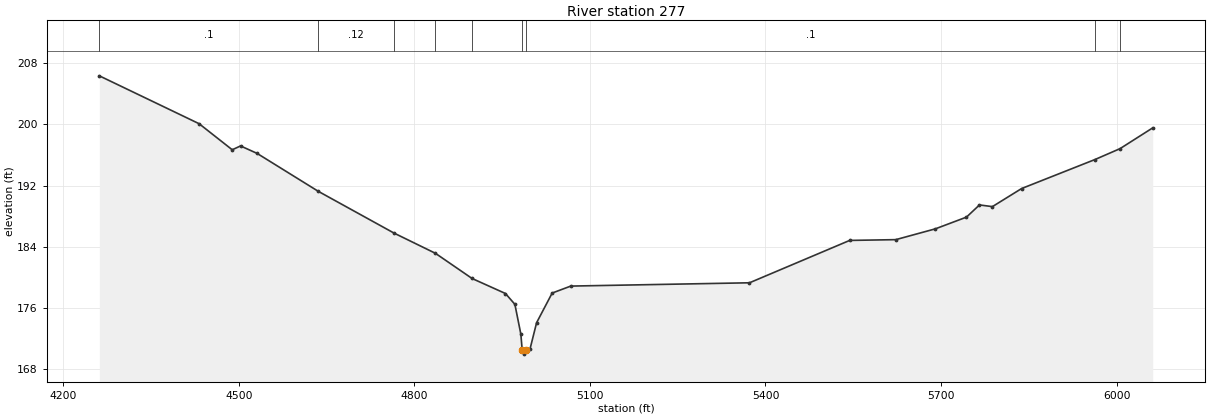
Type RM Length L Ch R = 1,277,0,0,0
BEGIN DESCRIPTION:
UNT047 IN NURI 1.0
END DESCRIPTION:
XS GIS Cut Line= 4
      2316466.92     13295544.85      2316019.00     13295982.35
      2315909.62     13296315.68      2316287.72     13297046.86
#Sta/Elev= 30
  4261.7  206.32  4432.2  200.07  4488.8  196.67  4503.0  197.17  4531.2  196.20
  4636.0  191.24  4765.2  185.80  4836.0  183.16  4898.7  179.87  4955.7  177.91
  4971.8  176.50  4982.0  172.61  4984.3  170.50  4987.0  170.00  4990.3  170.50
  4997.8  170.71  5008.9  174.10  5035.5  177.97  5067.3  178.88  5372.7  179.31
  5543.9  184.84  5622.7  184.94  5690.3  186.35  5743.5  187.88  5765.7  189.47
  5787.8  189.25  5837.7  191.61  5963.2  195.40  6006.0  196.82  6061.8  199.53
#Mann=9,-1,0
  4261.7     0.1       0  4636.0    0.12       0  4765.2     0.1       0
  4836.0    0.12       0  4898.7     0.1       0  4984.3    0.07       0
  4990.3     0.1       0  5963.2    0.05       0  6006.0     0.1       0
Bank Sta=4984.3,4990.3
Exp/Cntr=0.3,0.1

Chan Stop Cuts=-1