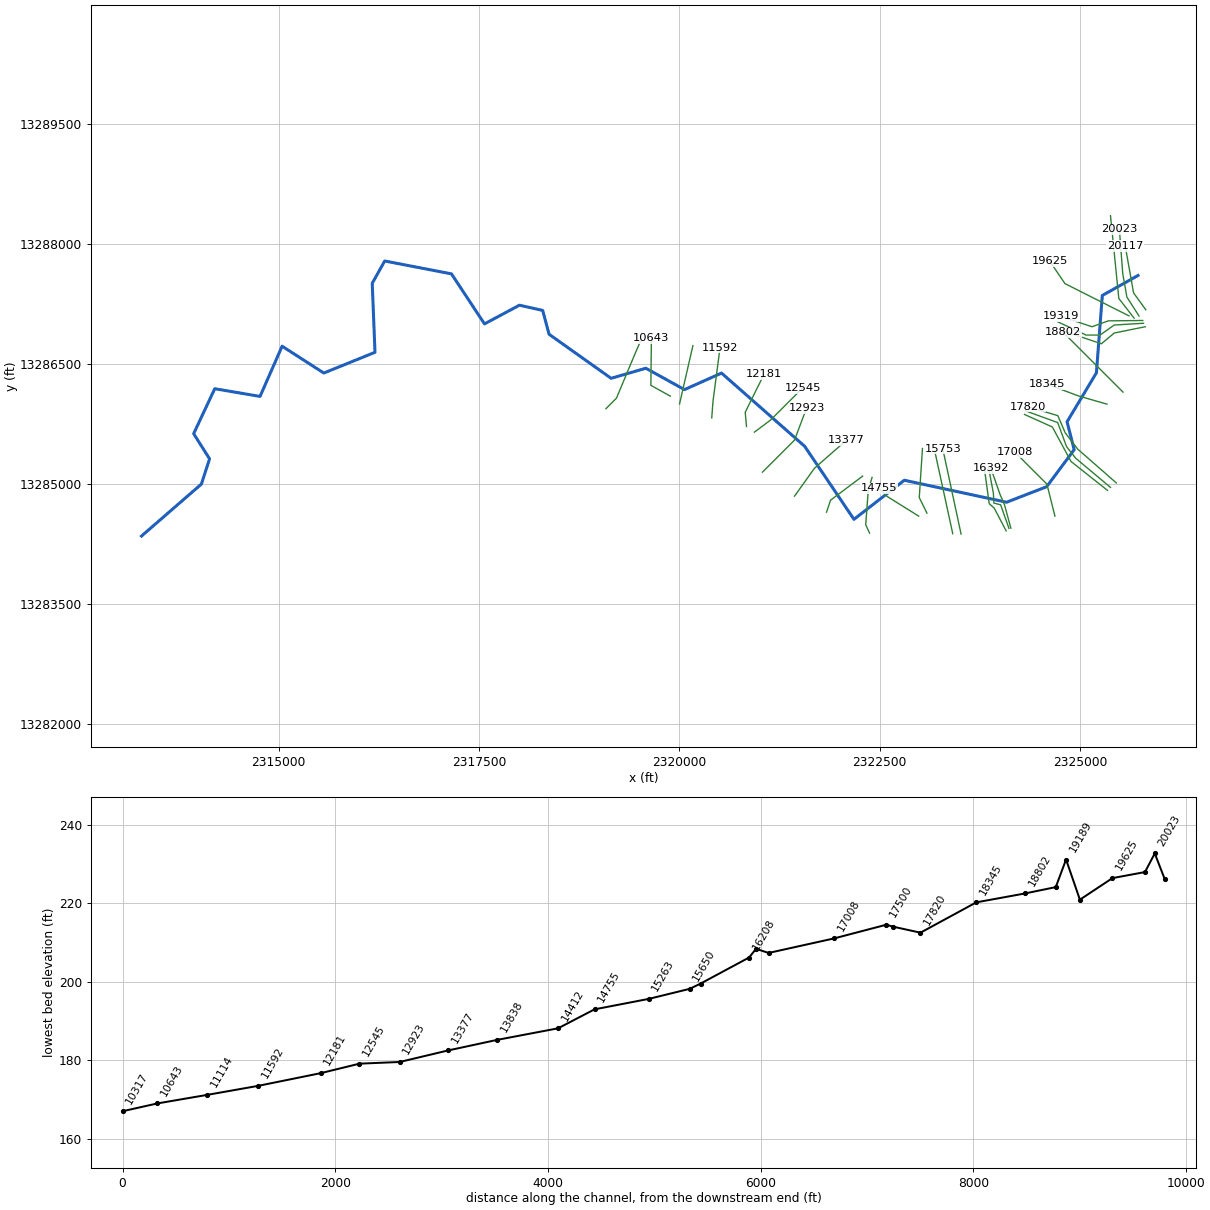
--- UNT048 IN NURI.prj (project) ---

Proj Title=UNT048 IN NURI Base Level Engineering
Current Plan=p01
Default Exp/Contr=0.3,0.1
English Units
Geom File=g01
Flow File=f01
Plan File=p01
BEGIN DESCRIPTION:
UNT048 IN NURI
END DESCRIPTION:

--- UNT048 IN NURI.p01 (plan) ---

Plan Title=Multiple Run
Short Identifier=Multiple
Geom File=g01
Flow File=f01
Subcritical Flow
K Sum by GR= 0
Std Step Tol= 0.01
Critical Tol= 0.01
Num of Std Step Trials= 20
Max Error Tol= 0.3
Flow Tol Ratio= 0.001
Split Flow NTrial= 30
Split Flow Tol= 0.02
Split Flow Ratio= 0.02
Log Output Level= 0
Friction Slope Method= 1
Unsteady Friction Slope Method= 2
Unsteady Bridges Friction Slope Method= 1
Parabolic Critical Depth
Global Vel Dist=  1 , 1 , 1
Global Log Level= 0
CheckData=True
Encroach Param= -1, 0, 0, 0
BEGIN DESCRIPTION:
Multiple Run
END DESCRIPTION:

--- UNT048 IN NURI.f01 (steady flow) ---

Flow Title=Multiple
Number of Profiles=7
Profile Names=10-year,25-year,50-year,1pct_min,100-year,1pct_plu,500-year
River Rch & RM= UNT048 IN NURI,Reach-1,20117
     443     607     739     657     889    1202    1290
River Rch & RM= UNT048 IN NURI,Reach-1,19319
     594     827    1018     914    1236    1672    1830
River Rch & RM= UNT048 IN NURI,Reach-1,15650
     870    1238    1548    1410    1907    2579    2908
River Rch & RM= UNT048 IN NURI,Reach-1,8148
    1533    2248    2866    2659    3596    4863    5688
Boundary for River Rch & Prof#=UNT048 IN NURI,Reach-1,1
Up Type=0
Dn Type=3
Dn Slope=0.005
Boundary for River Rch & Prof#=UNT048 IN NURI,Reach-1,2
Up Type=0
Dn Type=3
Dn Slope=0.005
Boundary for River Rch & Prof#=UNT048 IN NURI,Reach-1,3
Up Type=0
Dn Type=3
Dn Slope=0.005
Boundary for River Rch & Prof#=UNT048 IN NURI,Reach-1,4
Up Type=0
Dn Type=3
Dn Slope=0.005
Boundary for River Rch & Prof#=UNT048 IN NURI,Reach-1,5
Up Type=0
Dn Type=3
Dn Slope=0.005
Boundary for River Rch & Prof#=UNT048 IN NURI,Reach-1,6
Up Type=0
Dn Type=3
Dn Slope=0.005
Boundary for River Rch & Prof#=UNT048 IN NURI,Reach-1,7
Up Type=0
Dn Type=3
Dn Slope=0.005

--- UNT048 IN NURI.g01 (geometry) ---

Geom Title=Existing Conditions

River Reach=UNT048 IN NURI,Reach-1
Reach XY= 30
      2325724.39     13287604.55      2325279.08     13287354.55
      2325205.27     13286387.83      2324839.22     13285776.26
      2324927.72     13285426.85      2324584.13     13284964.53
      2324084.13     13284770.86      2322807.83     13285045.56
      2322179.36     13284557.09      2321564.20     13285470.23
      2320526.70     13286384.89      2320064.68     13286177.99
      2319582.33     13286445.19      2319148.94     13286319.40
      2318374.31     13286870.25      2318295.22     13287167.63
      2318004.83     13287232.91      2317568.71     13286999.21
      2317156.76     13287624.40      2316323.41     13287785.38
      2316167.79     13287506.74      2316202.18     13286644.27
      2315563.83     13286385.24      2315043.00     13286720.31
      2314767.95     13286093.26      2314202.35     13286189.01
      2313939.18     13285627.37      2314137.55     13285313.32
      2314036.02     13284997.56      2313288.41     13284348.08

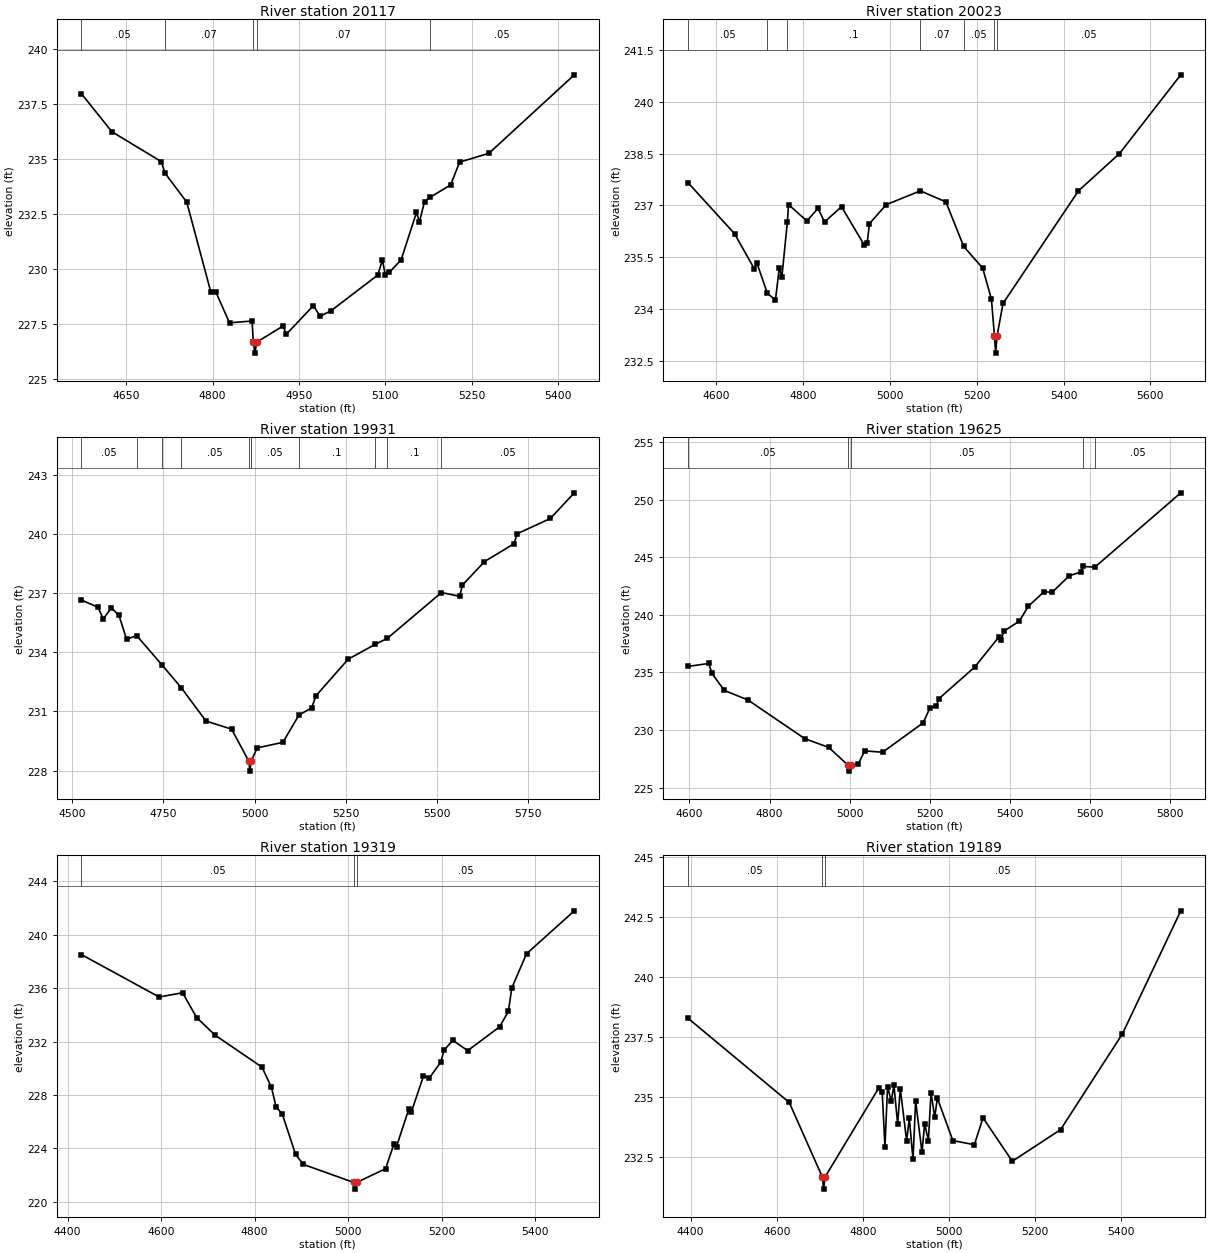
Type RM Length L Ch R = 1,20117,94,94,94
BEGIN DESCRIPTION:
UNT048 IN NURI 45.0
END DESCRIPTION:
XS GIS Cut Line= 3
      2325821.77     13287176.32      2325669.12     13287386.75
      2325565.10     13287972.72
#Sta/Elev= 30
  4572.6  237.96  4625.5  236.23  4711.3  234.87  4717.5  234.35  4755.3  233.03
  4797.1  228.94  4805.6  228.95  4829.5  227.54  4868.7  227.62  4870.8  226.66
  4873.5  226.16  4876.8  226.66  4922.7  227.40  4927.8  227.01  4974.9  228.32
  4986.8  227.84  5005.3  228.08  5086.6  229.71  5094.8  230.39  5099.9  229.70
  5106.9  229.84  5127.2  230.40  5153.9  232.56  5159.0  232.13  5167.8  233.05
  5176.9  233.24  5213.0  233.81  5228.8  234.85  5279.6  235.25  5427.7  238.82
#Mann=5,-1,0
  4572.6    0.05       0  4717.5    0.07       0  4870.8    0.07       0
  4876.8    0.07       0  5176.9    0.05       0
Bank Sta=4870.8,4876.8
Exp/Cntr=0.3,0.1

Type RM Length L Ch R = 1,20023,92,92,92
BEGIN DESCRIPTION:
UNT048 IN NURI 44.0
END DESCRIPTION:
XS GIS Cut Line= 4
      2325737.71     13287096.88      2325585.78     13287334.66
      2325533.70     13287629.80      2325492.03     13288181.86
#Sta/Elev= 30
  4534.5  237.66  4641.9  236.18  4687.6  235.16  4693.5  235.33  4717.6  234.45
  4736.2  234.26  4745.1  235.19  4751.0  234.93  4763.7  236.52  4766.3  237.02
  4808.6  236.55  4834.2  236.91  4849.4  236.52  4888.4  236.96  4940.8  235.85
  4947.6  235.91  4952.7  236.47  4991.5  237.02  5070.0  237.42  5128.9  237.10
  5169.9  235.81  5213.7  235.18  5233.8  234.28  5240.8  233.22  5243.5  232.72
  5246.8  233.22  5260.5  234.16  5434.3  237.42  5528.8  238.50  5670.0  240.78
#Mann=7,-1,0
  4534.5    0.05       0  4717.6    0.07       0  4763.7     0.1       0
  5070.0    0.07       0  5169.9    0.05       0  5240.8    0.07       0
  5246.8    0.05       0
Bank Sta=5240.8,5246.8
Exp/Cntr=0.3,0.1

Type RM Length L Ch R = 1,19931,306,306,306
BEGIN DESCRIPTION:
UNT048 IN NURI 43.0
END DESCRIPTION:
XS GIS Cut Line= 3
      2325676.09     13287070.74      2325485.09     13287317.30
      2325380.92     13288351.99
#Sta/Elev= 30
  4525.2  236.65  4570.9  236.28  4584.8  235.69  4607.4  236.25  4628.2  235.87
  4649.1  234.65  4676.5  234.85  4745.6  233.37  4798.6  232.21  4866.8  230.51
  4937.1  230.10  4984.4  228.47  4987.1  227.97  4990.4  228.47  5007.5  229.15
  5077.8  229.43  5121.9  230.82  5156.7  231.18  5168.3  231.79  5256.9  233.65
  5331.7  234.41  5363.8  234.70  5512.6  237.03  5562.4  236.84  5570.3  237.41
  5630.6  238.60  5711.0  239.50  5721.1  240.02  5811.5  240.79  5877.0  242.09
#Mann=10,-1,0
  4525.2    0.05       0  4676.5    0.07       0  4745.6     0.1       0
  4798.6    0.05       0  4984.4    0.03       0  4990.4    0.05       0
  5121.9     0.1       0  5331.7    0.05       0  5363.8     0.1       0
  5512.6    0.05       0
Bank Sta=4984.4,4990.4
Exp/Cntr=0.3,0.1

Type RM Length L Ch R = 1,19625,306,306,306
BEGIN DESCRIPTION:
Mapping XS ec3ff118
END DESCRIPTION:
XS GIS Cut Line= 3
      2325611.42     13287099.78      2324812.80     13287502.56
      2324625.29     13287780.36
#Sta/Elev= 30
  4596.2  235.52  4648.0  235.78  4656.3  234.91  4687.0  233.44  4745.9  232.61
  4887.7  229.25  4947.5  228.49  4996.2  226.93  4999.0  226.43  5002.2  226.93
  5021.5  227.06  5037.1  228.19  5081.9  228.07  5183.3  230.63  5200.0  231.92
  5216.3  232.10  5222.3  232.72  5311.5  235.46  5372.8  238.11  5378.4  237.84
  5384.3  238.58  5423.0  239.46  5445.3  240.74  5484.3  242.00  5505.3  241.97
  5547.3  243.39  5577.2  243.74  5582.9  244.21  5611.3  244.14  5825.8  250.60
#Mann=5,-1,0
  4596.2    0.05       0  4996.2    0.03       0  5002.2    0.05       0
  5582.9     0.1       0  5611.3    0.05       0
Bank Sta=4996.2,5002.2
Exp/Cntr=0.3,0.1

Type RM Length L Ch R = 1,19319,130,130,130
BEGIN DESCRIPTION:
Mapping XS 50738e05
END DESCRIPTION:
XS GIS Cut Line= 4
      2325783.99     13287041.84      2325354.35     13287037.50
      2325150.35     13286963.72      2324764.10     13287093.91
#Sta/Elev= 30
  4429.5  238.52  4595.8  235.34  4645.8  235.66  4675.8  233.80  4715.8  232.47
  4815.8  230.08  4835.8  228.57  4845.8  227.12  4859.2  226.56  4887.5  223.54
  4904.3  222.79  5012.1  221.44  5014.8  220.94  5018.1  221.44  5080.1  222.47
  5098.1  224.35  5103.4  224.13  5129.6  226.93  5134.9  226.69  5161.1  229.42
  5173.9  229.28  5197.9  230.45  5205.5  231.38  5224.1  232.09  5255.6  231.32
  5323.8  233.10  5342.7  234.26  5350.0  236.02  5381.5  238.58  5483.7  241.80
#Mann=3,-1,0
  4429.5    0.05       0  5012.1    0.03       0  5018.1    0.05       0
Bank Sta=5012.1,5018.1
Exp/Cntr=0.3,0.1

Type RM Length L Ch R = 1,19189,97,97,97
BEGIN DESCRIPTION:
Mapping XS df2ff7a9
END DESCRIPTION:
XS GIS Cut Line= 5
      2325792.68     13287007.12      2325428.13     13286985.42
      2325250.18     13286859.55      2325076.57     13286859.55
      2324725.01     13287024.48
#Sta/Elev= 30
  4393.6  238.28  4629.0  234.77  4706.1  231.66  4708.9  231.16  4712.1  231.66
  4836.6  235.36  4845.0  235.21  4851.4  232.93  4857.5  235.43  4866.1  234.82
  4872.3  235.49  4880.9  233.87  4887.0  235.34  4901.8  233.17  4908.0  234.11
  4916.6  232.40  4922.7  234.83  4937.5  232.69  4943.6  233.89  4952.3  233.17
  4958.4  235.17  4967.1  234.16  4973.2  234.95  5009.2  233.18  5059.2  233.01
  5079.2  234.13  5147.3  232.32  5259.6  233.64  5403.2  237.63  5538.7  242.75
#Mann=3,-1,0
  4393.6    0.05       0  4706.1    0.03       0  4712.1    0.05       0
Bank Sta=4706.1,4712.1
Exp/Cntr=0.3,0.1

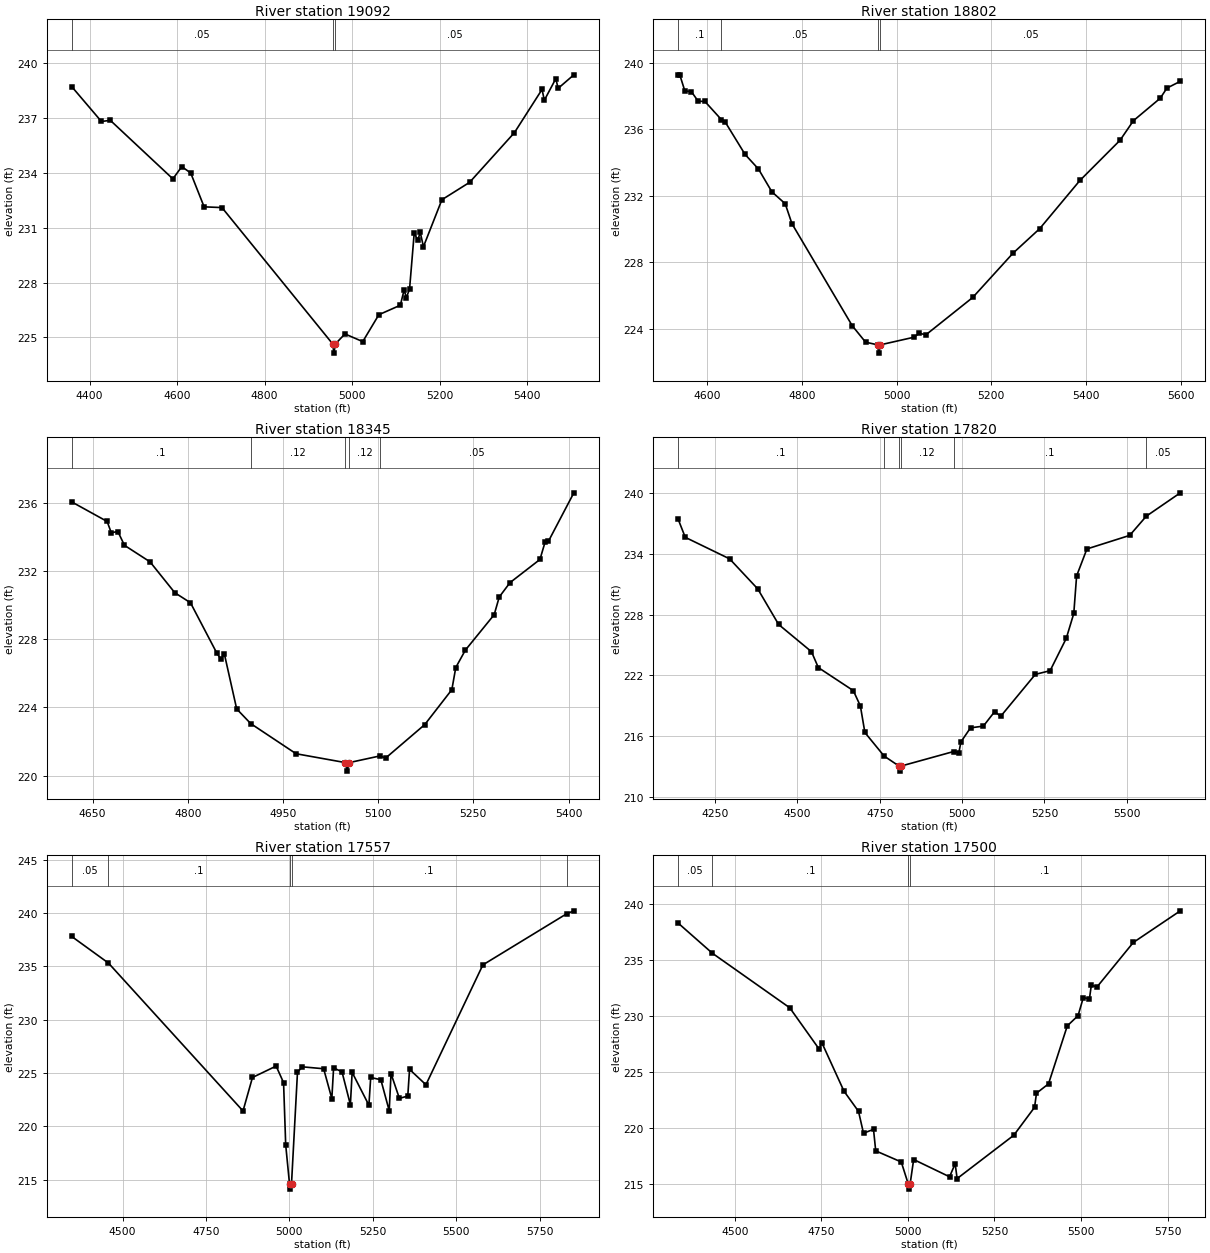
Type RM Length L Ch R = 1,19092,290,290,290
BEGIN DESCRIPTION:
Mapping XS 2b019865
END DESCRIPTION:
XS GIS Cut Line= 4
      2325814.40     13286963.71      2325428.13     13286885.59
      2325267.54     13286751.04      2324751.89     13286924.37
#Sta/Elev= 30
  4359.0  238.72  4427.0  236.81  4447.4  236.87  4590.3  233.67  4610.7  234.34
  4631.1  233.99  4661.7  232.14  4702.5  232.10  4955.6  224.64  4958.3  224.14
  4961.6  224.64  4983.5  225.19  5024.2  224.77  5061.0  226.24  5110.1  226.76
  5118.7  227.59  5124.0  227.18  5131.2  227.65  5141.8  230.70  5150.2  230.31
  5155.5  230.76  5162.9  229.96  5205.1  232.53  5268.4  233.48  5370.9  236.20
  5433.9  238.56  5439.2  237.97  5465.4  239.15  5470.7  238.62  5506.6  239.36
#Mann=3,-1,0
  4359.0    0.05       0  4955.6    0.03       0  4961.6    0.05       0
Bank Sta=4955.6,4961.6
Exp/Cntr=0.3,0.1

Type RM Length L Ch R = 1,18802,457,457,457
BEGIN DESCRIPTION:
UNT048 IN NURI 42.0
END DESCRIPTION:
XS GIS Cut Line= 3
      2325537.69     13286146.88      2325187.72     13286496.85
      2324787.74     13286896.84
#Sta/Elev= 30
  4538.6  239.27  4542.1  239.27  4552.7  238.31  4566.8  238.25  4581.0  237.68
  4595.1  237.67  4629.8  236.58  4637.6  236.45  4680.0  234.48  4708.3  233.60
  4736.6  232.23  4764.8  231.51  4779.0  230.31  4906.3  224.17  4934.5  223.18
  4959.8  223.02  4962.6  222.52  4965.8  223.02  5037.1  223.48  5047.7  223.72
  5061.8  223.62  5160.8  225.87  5245.7  228.53  5302.2  230.01  5387.1  232.91
  5471.9  235.33  5500.2  236.51  5556.8  237.86  5570.9  238.47  5599.2  238.88
#Mann=4,-1,0
  4538.6     0.1       0  4629.8    0.05       0  4959.8    0.03       0
  4965.8    0.05       0
Bank Sta=4959.8,4965.8
Exp/Cntr=0.3,0.1

Type RM Length L Ch R = 1,18345,525,525,525
BEGIN DESCRIPTION:
UNT048 IN NURI 41.0
END DESCRIPTION:
XS GIS Cut Line= 3
      2325337.73     13285996.85      2324987.72     13286096.85
      2324587.73     13286246.85
#Sta/Elev= 30
  4617.1  236.06  4673.0  234.91  4679.5  234.25  4689.9  234.32  4700.3  233.51
  4740.6  232.54  4779.6  230.73  4804.3  230.14  4845.9  227.18  4852.4  226.82
  4857.6  227.15  4877.1  223.91  4899.2  223.05  4970.7  221.28  5048.4  220.76
  5051.2  220.26  5054.4  220.76  5102.6  221.15  5111.9  221.03  5173.4  222.99
  5216.1  225.04  5222.3  226.34  5237.4  227.36  5282.8  229.44  5290.8  230.48
  5307.7  231.32  5354.9  232.68  5362.9  233.69  5368.3  233.75  5408.3  236.59
#Mann=5,-1,0
  4617.1     0.1       0  4899.2    0.12       0  5048.4    0.07       0
  5054.4    0.12       0  5102.6    0.05       0
Bank Sta=5048.4,5054.4
Exp/Cntr=0.3,0.1

Type RM Length L Ch R = 1,17820,263,263,263
BEGIN DESCRIPTION:
UNT048 IN NURI 40.0
END DESCRIPTION:
XS GIS Cut Line= 5
      2325453.84     13285011.75      2324971.20     13285435.36
      2324814.95     13285640.22      2324724.67     13285852.02
      2324346.20     13285966.61
#Sta/Elev= 30
  4137.4  237.46  4159.1  235.66  4293.9  233.53  4379.3  230.56  4442.8  227.04
  4542.5  224.35  4563.3  222.78  4669.6  220.50  4691.1  218.98  4704.7  216.36
  4763.2  214.03  4808.5  213.04  4811.2  212.54  4814.5  213.04  4974.6  214.48
  4990.2  214.35  4996.5  215.43  5025.6  216.82  5064.6  216.99  5099.1  218.43
  5117.3  217.96  5222.6  222.11  5267.4  222.47  5316.5  225.67  5339.3  228.13
  5347.9  231.84  5379.2  234.51  5509.1  235.85  5559.6  237.75  5662.9  240.06
#Mann=6,-1,0
  4137.4     0.1       0  4763.2    0.12       0  4808.5    0.07       0
  4814.5    0.12       0  4974.6     0.1       0  5559.6    0.05       0
Bank Sta=4808.5,4814.5
Exp/Cntr=0.3,0.1

Type RM Length L Ch R = 1,17557,57,57,57
BEGIN DESCRIPTION:
UNT048 IN NURI 39.0
END DESCRIPTION:
XS GIS Cut Line= 5
      2325380.90     13284956.21      2324946.89     13285320.77
      2324832.31     13285466.61      2324721.88     13285766.36
      2324314.93     13285914.53
#Sta/Elev= 30
  4347.5  237.80  4457.8  235.30  4861.0  221.43  4889.3  224.57  4960.2  225.64
  4982.5  224.09  4988.9  218.24  5000.3  214.60  5003.1  214.10  5006.3  214.60
  5024.2  225.06  5038.6  225.57  5102.6  225.39  5127.1  222.59  5132.4  225.46
  5157.5  225.11  5182.7  222.02  5188.0  225.05  5238.2  221.97  5243.6  224.57
  5274.0  224.36  5299.1  221.45  5304.5  224.93  5329.6  222.61  5354.7  222.83
  5360.0  225.33  5409.1  223.89  5579.7  235.13  5831.1  239.93  5852.3  240.20
#Mann=5,-1,0
  4347.5    0.05       0  4457.8     0.1       0  5000.3    0.07       0
  5006.3     0.1       0  5831.1    0.05       0
Bank Sta=5000.3,5006.3
Exp/Cntr=0.3,0.1

Type RM Length L Ch R = 1,17500,492,492,492
BEGIN DESCRIPTION:
Mapping XS 5b4e543e
END DESCRIPTION:
XS GIS Cut Line= 4
      2325343.03     13284919.47      2324888.20     13285280.56
      2324655.56     13285711.11      2324308.32     13285867.37
#Sta/Elev= 30
  4336.0  238.28  4435.0  235.59  4658.5  230.73  4743.4  227.05  4751.4  227.61
  4815.2  223.30  4857.2  221.50  4871.6  219.55  4900.5  219.90  4906.9  217.98
  4980.7  216.99  5000.5  215.07  5003.2  214.57  5006.5  215.07  5016.5  217.21
  5120.2  215.67  5136.4  216.83  5142.1  215.51  5305.8  219.37  5365.8  221.86
  5371.4  223.12  5406.1  223.95  5460.4  229.12  5491.5  230.03  5506.7  231.64
  5524.3  231.52  5529.8  232.74  5546.3  232.59  5651.1  236.55  5786.9  239.37
#Mann=4,-1,0
  4336.0    0.05       0  4435.0     0.1       0  5000.5    0.07       0
  5006.5     0.1       0
Bank Sta=5000.5,5006.5
Exp/Cntr=0.3,0.1

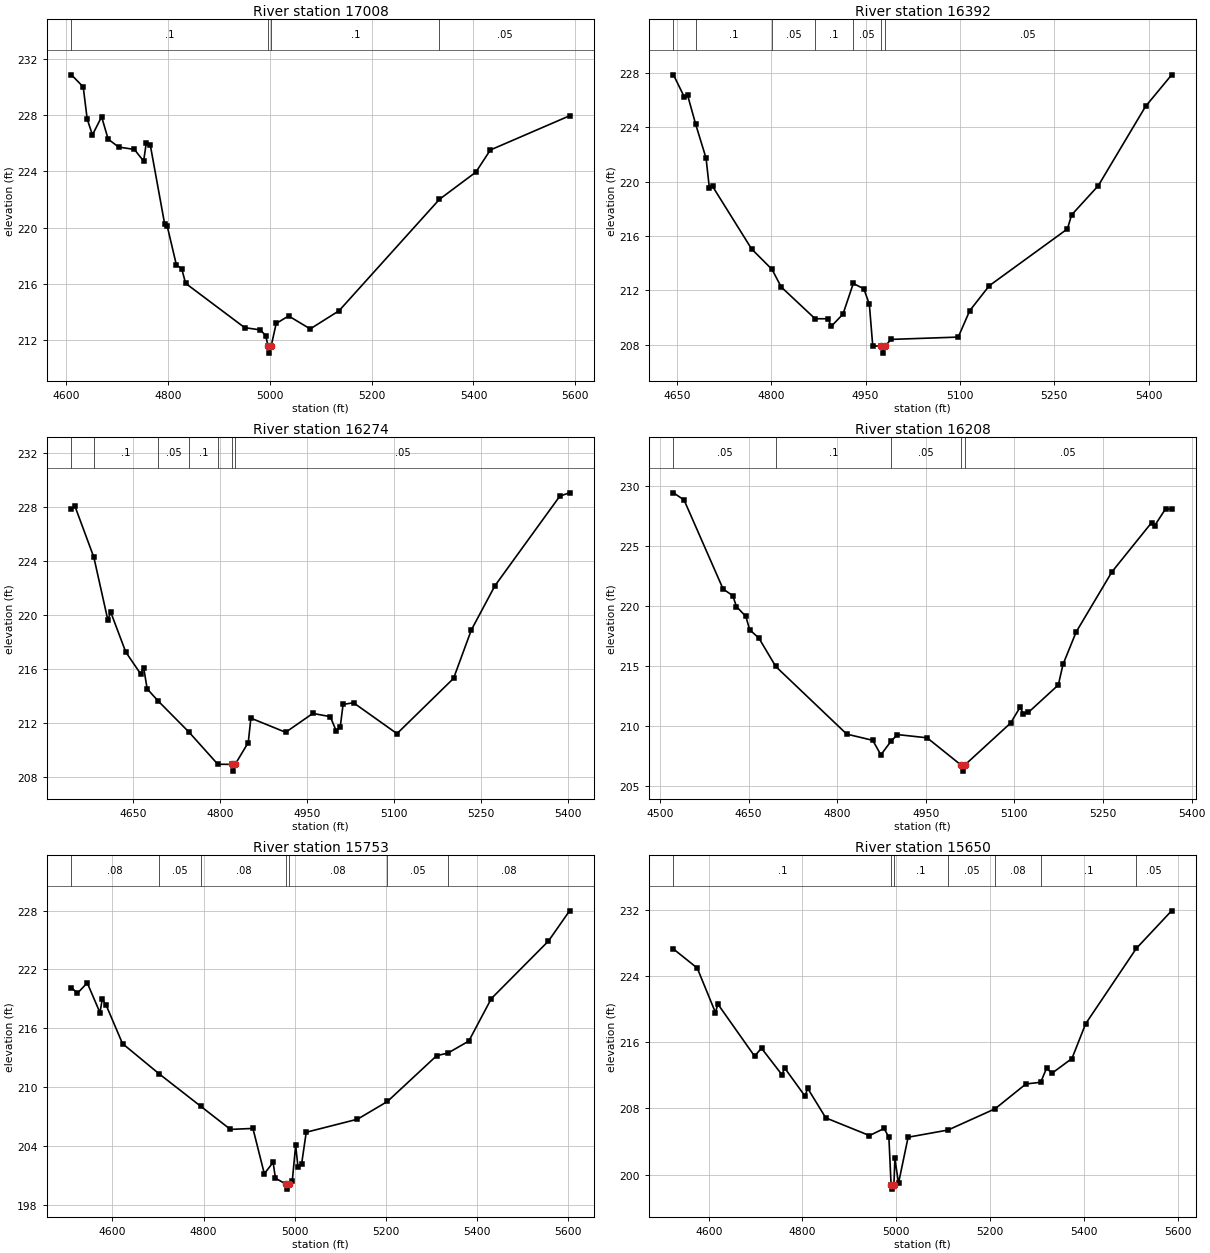
Type RM Length L Ch R = 1,17008,616,616,616
BEGIN DESCRIPTION:
UNT048 IN NURI 38.0
END DESCRIPTION:
XS GIS Cut Line= 3
      2324687.71     13284596.90      2324587.72     13284996.85
      2324187.69     13285396.89
#Sta/Elev= 30
  4610.7  230.85  4633.8  229.99  4641.6  227.71  4651.9  226.58  4669.9  227.87
  4682.8  226.28  4703.4  225.72  4734.3  225.55  4752.4  224.72  4757.5  225.98
  4765.3  225.90  4793.6  220.27  4798.8  220.10  4816.8  217.33  4827.1  217.09
  4834.8  216.04  4950.8  212.89  4981.7  212.73  4992.0  212.32  4996.8  211.58
  4999.5  211.08  5002.8  211.58  5012.7  213.19  5037.1  213.72  5079.5  212.80
  5136.1  214.09  5333.3  222.01  5404.8  223.94  5433.1  225.51  5588.7  227.94
#Mann=4,-1,0
  4610.7     0.1       0  4996.8    0.07       0  5002.8     0.1       0
  5333.3    0.05       0
Bank Sta=4996.8,5002.8
Exp/Cntr=0.3,0.1

Type RM Length L Ch R = 1,16392,118,118,118
BEGIN DESCRIPTION:
UNT048 IN NURI 37.0
END DESCRIPTION:
XS GIS Cut Line= 4
      2324137.71     13284446.88      2324058.34     13284738.89
      2324002.78     13284867.36      2323887.71     13285196.87
#Sta/Elev= 30
  4644.8  227.86  4662.1  226.23  4667.3  226.36  4680.2  224.21  4696.6  221.73
  4701.9  219.52  4707.0  219.65  4769.1  215.04  4801.5  213.54  4816.0  212.25
  4869.9  209.91  4890.4  209.91  4895.6  209.35  4914.2  210.25  4930.6  212.51
  4947.4  212.11  4956.1  210.98  4961.5  207.92  4974.9  207.88  4977.6  207.38
  4980.9  207.88  4990.5  208.39  5097.4  208.56  5115.6  210.50  5146.7  212.34
  5270.9  216.52  5277.5  217.55  5319.9  219.70  5395.1  225.54  5436.4  227.85
#Mann=7,-1,0
  4644.8    0.05       0  4680.2     0.1       0  4801.5    0.05       0
  4869.9     0.1       0  4930.6    0.05       0  4974.9    0.03       0
  4980.9    0.05       0
Bank Sta=4974.9,4980.9
Exp/Cntr=0.3,0.1

Type RM Length L Ch R = 1,16274,66,66,66
BEGIN DESCRIPTION:
Mapping XS cb7e5370
END DESCRIPTION:
XS GIS Cut Line= 5
      2324113.88     13284443.78      2324009.73     13284738.89
      2323926.39     13284759.72      2323919.45     13284884.72
      2323857.20     13285213.24
#Sta/Elev= 30
  4544.3  227.87  4550.3  228.08  4582.9  224.29  4606.9  219.66  4612.2  220.20
  4637.8  217.27  4663.4  215.65  4668.7  216.11  4674.8  214.53  4693.3  213.65
  4746.7  211.33  4796.5  208.94  4820.4  208.93  4823.1  208.43  4826.4  208.93
  4849.0  210.55  4853.5  212.36  4913.4  211.31  4960.3  212.71  4990.3  212.47
  5000.4  211.43  5007.4  211.67  5012.4  213.38  5030.4  213.50  5105.3  211.21
  5202.8  215.31  5233.4  218.90  5274.1  222.18  5386.0  228.83  5402.7  229.07
#Mann=7,-1,0
  4544.3    0.05       0  4582.9     0.1       0  4693.3    0.05       0
  4746.7     0.1       0  4796.5    0.05       0  4820.4    0.03       0
  4826.4    0.05       0
Bank Sta=4820.4,4826.4
Exp/Cntr=0.3,0.1

Type RM Length L Ch R = 1,16208,455,455,455
BEGIN DESCRIPTION:
UNT048 IN NURI 36.0
END DESCRIPTION:
XS GIS Cut Line= 4
      2324079.18     13284412.49      2323929.87     13284697.22
      2323867.37     13284752.78      2323808.33     13285186.85
#Sta/Elev= 30
  4522.8  229.43  4540.7  228.84  4606.9  221.40  4623.3  220.85  4629.4  219.94
  4645.3  219.12  4651.9  218.00  4667.4  217.31  4696.0  214.94  4816.1  209.30
  4860.1  208.78  4873.9  207.57  4890.9  208.69  4901.9  209.26  4952.2  208.99
  5009.8  206.71  5012.5  206.21  5015.8  206.71  5093.5  210.22  5109.7  211.55
  5114.8  211.00  5123.8  211.12  5174.3  213.40  5182.2  215.11  5204.5  217.82
  5265.1  222.84  5332.1  226.94  5337.1  226.67  5355.9  228.10  5366.0  228.06
#Mann=5,-1,0
  4522.8    0.05       0  4696.0     0.1       0  4890.9    0.05       0
  5009.8    0.03       0  5015.8    0.05       0
Bank Sta=5009.8,5015.8
Exp/Cntr=0.3,0.1

Type RM Length L Ch R = 1,15753,103,103,103
BEGIN DESCRIPTION:
UNT048 IN NURI 35.0
END DESCRIPTION:
XS GIS Cut Line= 2
      2323516.33     13284372.89      2323287.21     13285442.12
#Sta/Elev= 30
  4509.9  220.13  4523.1  219.57  4544.6  220.62  4572.5  217.59  4577.6  218.96
  4585.5  218.41  4622.0  214.43  4701.8  211.37  4793.4  208.05  4858.9  205.68
  4908.3  205.78  4933.3  201.16  4952.6  202.32  4957.7  200.70  4981.4  200.09
  4984.1  199.59  4987.4  200.09  4994.6  200.39  5002.1  204.05  5007.2  201.86
  5015.1  202.14  5025.3  205.39  5137.8  206.72  5203.6  208.53  5311.7  213.20
  5336.2  213.46  5382.2  214.69  5431.6  219.02  5557.1  224.89  5603.4  227.97
#Mann=7,-1,0
  4509.9    0.08       0  4701.8    0.05       0  4793.4    0.08       0
  4981.4    0.07       0  4987.4    0.08       0  5203.6    0.05       0
  5336.2    0.08       0
Bank Sta=4981.4,4987.4
Exp/Cntr=0.3,0.1

Type RM Length L Ch R = 1,15650,387,387,387
BEGIN DESCRIPTION:
Mapping XS 07613c79
END DESCRIPTION:
XS GIS Cut Line= 2
      2323412.50     13284377.80      2323186.82     13285415.95
#Sta/Elev= 30
  4524.8  227.29  4575.5  224.99  4614.4  219.60  4619.5  220.63  4697.8  214.33
  4712.6  215.29  4756.6  212.05  4761.7  212.92  4805.7  209.47  4810.9  210.45
  4849.7  206.86  4942.9  204.72  4974.1  205.58  4984.3  204.51  4989.0  198.74
  4991.7  198.24  4995.0  198.74  4997.1  201.95  5004.8  198.95  5025.3  204.52
  5110.4  205.39  5210.8  207.96  5276.5  210.96  5308.0  211.17  5320.5  212.85
  5332.3  212.27  5374.7  214.04  5403.9  218.24  5512.0  227.36  5587.2  231.91
#Mann=7,-1,0
  4524.8     0.1       0  4989.0    0.07       0  4995.0     0.1       0
  5110.4    0.05       0  5210.8    0.08       0  5308.0     0.1       0
  5512.0    0.05       0
Bank Sta=4989,4995
Exp/Cntr=0.3,0.1

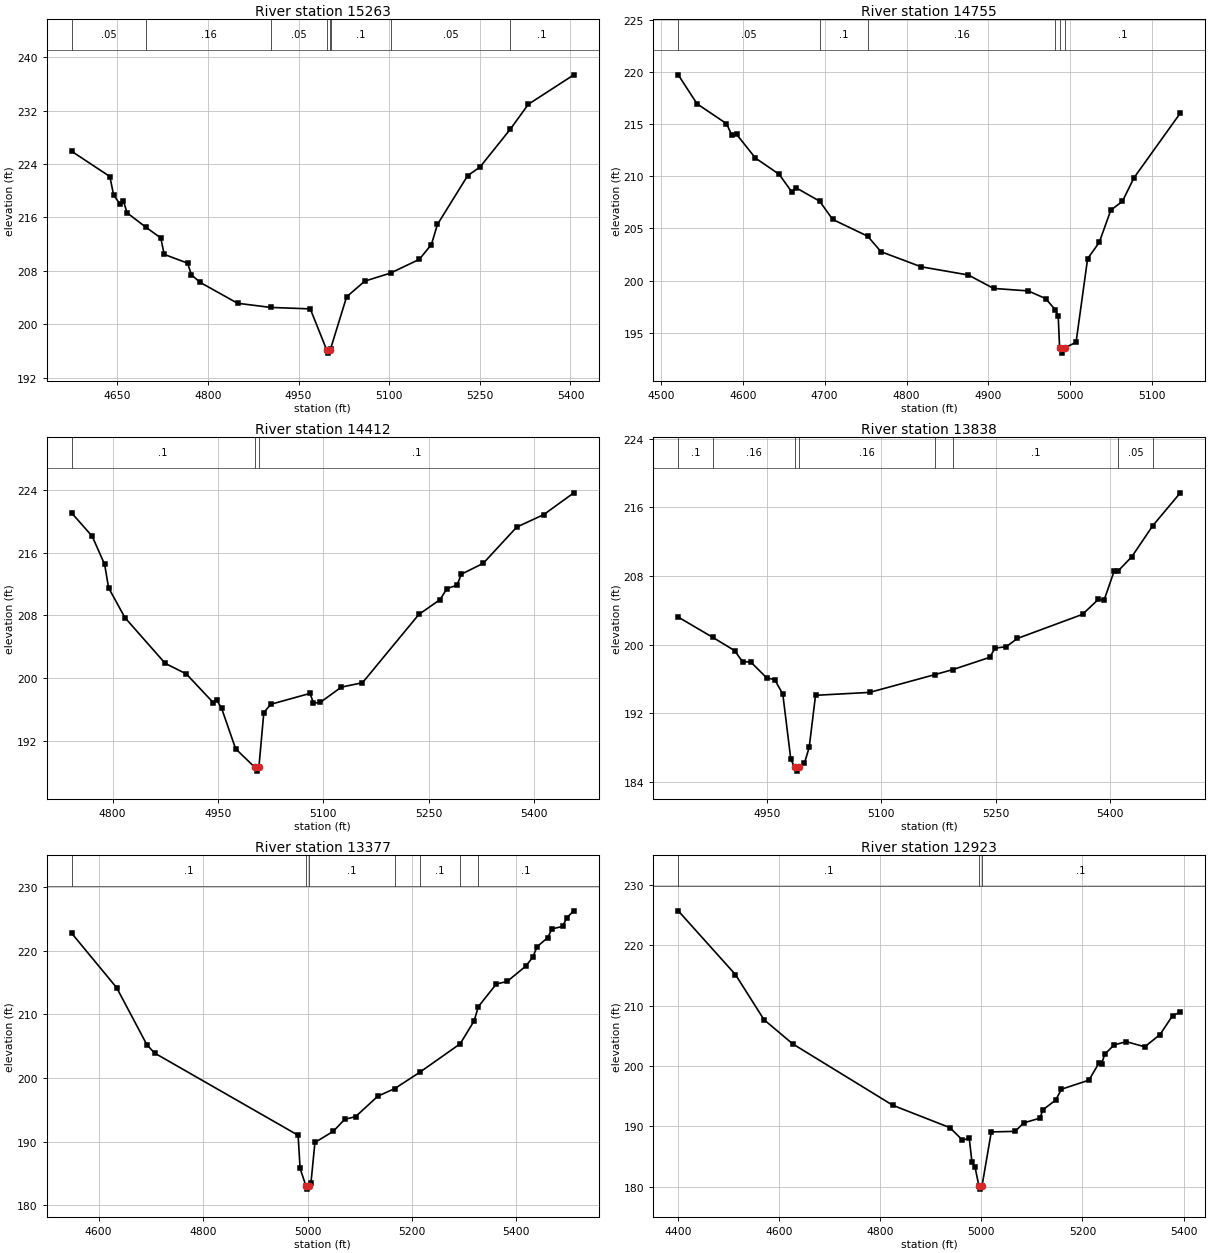
Type RM Length L Ch R = 1,15263,508,508,508
BEGIN DESCRIPTION:
UNT048 IN NURI 34.0
END DESCRIPTION:
XS GIS Cut Line= 3
      2323090.12     13284634.68      2322994.65     13284829.60
      2323034.42     13285442.07
#Sta/Elev= 30
  4574.8  225.91  4637.8  222.14  4644.0  219.39  4654.7  217.98  4660.3  218.46
  4666.3  216.70  4697.7  214.52  4722.0  212.94  4727.8  210.47  4766.5  209.15
  4772.8  207.40  4787.5  206.26  4849.2  203.14  4904.0  202.52  4969.5  202.30
  4996.5  196.17  4999.3  195.67  5002.5  196.17  5003.2  196.35  5029.6  204.11
  5059.7  206.46  5102.3  207.67  5149.8  209.72  5169.9  211.94  5179.9  214.96
  5230.0  222.28  5250.1  223.54  5300.6  229.24  5330.2  232.96  5405.6  237.38
#Mann=8,-1,0
  4574.8    0.05       0  4697.7    0.16       0  4904.0    0.05       0
  4996.5   0.035       0  5002.5    0.05       0  5003.2     0.1       0
  5102.3    0.05       0  5300.6     0.1       0
Bank Sta=4996.5,5002.5
Exp/Cntr=0.3,0.1

Type RM Length L Ch R = 1,14755,343,343,343
BEGIN DESCRIPTION:
UNT048 IN NURI 33.0
END DESCRIPTION:
XS GIS Cut Line= 3
      2322987.69     13284596.87      2322587.72     13284846.85
      2322487.71     13284946.87
#Sta/Elev= 30
  4521.2  219.77  4544.2  216.98  4580.1  215.08  4586.6  213.98  4592.5  214.04
  4615.5  211.77  4644.4  210.21  4659.7  208.53  4665.6  208.89  4693.8  207.63
  4709.8  205.87  4752.5  204.26  4768.8  202.77  4817.7  201.32  4875.5  200.53
  4906.2  199.24  4948.6  199.00  4969.9  198.26  4981.6  197.19  4985.2  196.59
  4986.9  193.52  4989.7  193.02  4992.9  193.52  5007.0  194.06  5021.1  202.10
  5035.3  203.66  5049.4  206.76  5063.6  207.61  5077.7  209.87  5134.3  216.09
#Mann=6,-1,0
  4521.2    0.05       0  4693.8     0.1       0  4752.5    0.16       0
  4981.6     0.1       0  4986.9    0.07       0  4992.9     0.1       0
Bank Sta=4986.9,4992.9
Exp/Cntr=0.3,0.1

Type RM Length L Ch R = 1,14412,574,574,574
BEGIN DESCRIPTION:
UNT048 IN NURI 32.0
END DESCRIPTION:
XS GIS Cut Line= 4
      2322374.04     13284384.09      2322326.32     13284491.46
      2322358.14     13284921.10      2322405.89     13285080.27
#Sta/Elev= 30
  4742.0  221.03  4771.1  218.08  4788.8  214.49  4794.4  211.52  4817.6  207.73
  4874.9  201.91  4905.0  200.56  4943.2  196.92  4948.2  197.25  4955.2  196.19
  4975.2  191.03  5002.3  188.69  5005.0  188.19  5008.3  188.69  5015.3  195.64
  5025.3  196.70  5081.0  198.08  5086.0  196.86  5095.5  196.93  5125.6  198.88
  5155.7  199.44  5235.9  208.13  5266.0  210.01  5276.0  211.43  5290.3  211.85
  5296.3  213.25  5327.6  214.64  5375.2  219.25  5413.5  220.83  5456.5  223.61
#Mann=3,-1,0
  4742.0     0.1       0  5002.3    0.07       0  5008.3     0.1       0
Bank Sta=5002.3,5008.3
Exp/Cntr=0.3,0.1

Type RM Length L Ch R = 1,13838,461,461,461
BEGIN DESCRIPTION:
UNT048 IN NURI 31.0
END DESCRIPTION:
XS GIS Cut Line= 3
      2321837.71     13284646.81      2321887.72     13284796.85
      2322287.75     13285096.88
#Sta/Elev= 30
  4833.9  203.20  4878.9  200.85  4907.7  199.30  4918.3  197.99  4928.8  197.98
  4949.9  196.11  4960.4  195.91  4971.0  194.21  4981.5  186.60  4986.4  185.74
  4989.2  185.24  4992.4  185.74  4999.4  186.18  5005.6  188.02  5013.9  194.08
  5084.8  194.42  5170.6  196.50  5193.9  197.08  5242.1  198.50  5249.4  199.58
  5263.9  199.75  5278.5  200.71  5363.9  203.52  5384.8  205.28  5392.1  205.16
  5405.6  208.62  5411.0  208.62  5428.5  210.24  5456.1  213.87  5492.1  217.69
#Mann=8,-1,0
  4833.9     0.1       0  4878.9    0.16       0  4986.4    0.07       0
  4992.4    0.16       0  5170.6    0.05       0  5193.9     0.1       0
  5411.0    0.05       0  5456.1     0.1       0
Bank Sta=4986.4,4992.4
Exp/Cntr=0.3,0.1

Type RM Length L Ch R = 1,13377,454,454,454
BEGIN DESCRIPTION:
UNT048 IN NURI 30.0
END DESCRIPTION:
XS GIS Cut Line= 3
      2321437.71     13284846.84      2321687.72     13285196.85
      2322087.69     13285546.83
#Sta/Elev= 30
  4548.5  222.73  4634.5  214.19  4692.3  205.24  4707.0  203.93  4982.0  191.01
  4985.8  185.80  4997.0  183.05  4999.7  182.55  5003.0  183.05  5006.6  183.50
  5014.2  189.88  5049.3  191.63  5071.2  193.51  5092.1  193.94  5134.8  197.16
  5166.8  198.33  5214.7  200.89  5292.4  205.38  5318.9  208.95  5327.4  211.24
  5361.6  214.77  5382.5  215.18  5417.6  217.55  5431.8  219.01  5439.4  220.62
  5460.3  222.07  5467.9  223.42  5488.8  223.83  5496.4  225.18  5510.1  226.27
#Mann=7,-1,0
  4548.5     0.1       0  4997.0    0.07       0  5003.0     0.1       0
  5166.8    0.05       0  5214.7     0.1       0  5292.4    0.05       0
  5327.4     0.1       0
Bank Sta=4997,5003
Exp/Cntr=0.3,0.1

Type RM Length L Ch R = 1,12923,378,378,378
BEGIN DESCRIPTION:
UNT048 IN NURI 29.0
END DESCRIPTION:
XS GIS Cut Line= 3
      2321037.73     13285146.86      2321437.72     13285546.85
      2321587.73     13285946.88
#Sta/Elev= 30
  4400.6  225.69  4513.7  215.14  4570.3  207.66  4626.9  203.67  4824.9  193.50
  4938.0  189.79  4962.7  187.73  4976.1  188.04  4981.4  184.13  4987.6  183.23
  4995.3  180.12  4998.1  179.62  5001.3  180.12  5019.7  189.09  5066.8  189.18
  5083.8  190.58  5115.8  191.37  5122.0  192.77  5146.9  194.35  5158.5  196.16
  5212.8  197.66  5232.4  200.46  5237.7  200.31  5244.0  201.95  5262.6  203.49
  5286.7  204.03  5323.2  203.18  5353.4  205.21  5378.3  208.35  5393.5  208.90
#Mann=3,-1,0
  4400.6     0.1       0  4995.3    0.07       0  5001.3     0.1       0
Bank Sta=4995.3,5001.3
Exp/Cntr=0.3,0.1

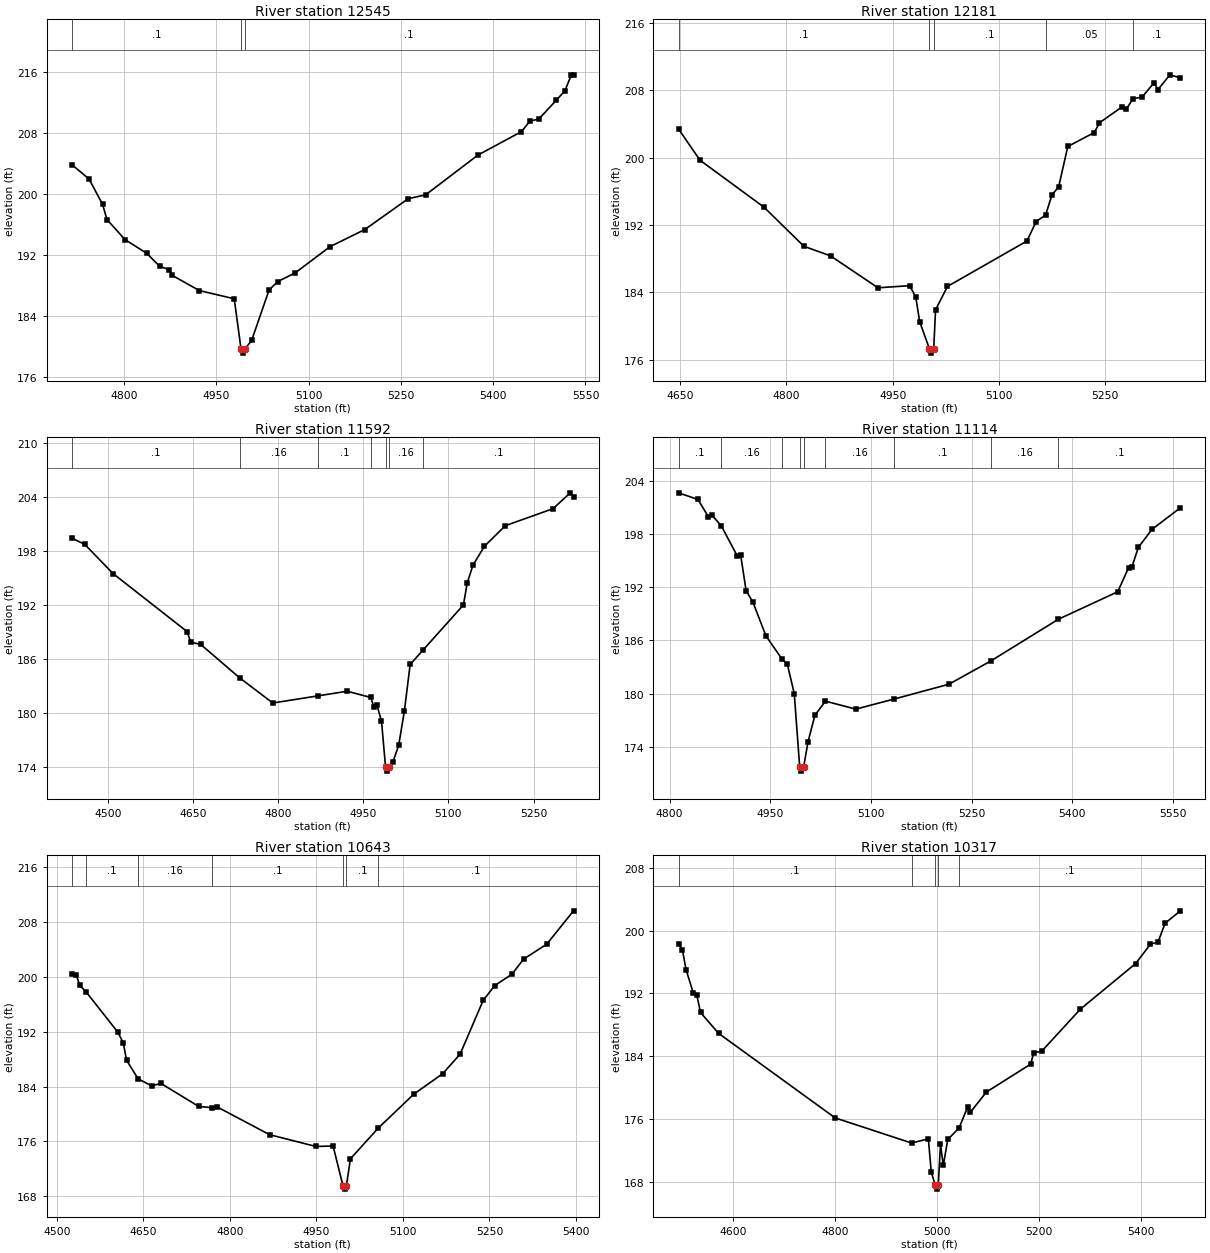
Type RM Length L Ch R = 1,12545,364,364,364
BEGIN DESCRIPTION:
UNT048 IN NURI 28.0
END DESCRIPTION:
XS GIS Cut Line= 3
      2320937.75     13285646.88      2321137.72     13285796.85
      2321537.69     13286196.82
#Sta/Elev= 30
  4715.0  203.90  4743.1  202.01  4765.0  198.70  4772.3  196.69  4801.4  194.08
  4836.8  192.27  4857.7  190.59  4872.3  190.14  4878.5  189.37  4922.3  187.39
  4979.1  186.31  4990.2  179.69  4993.0  179.19  4996.2  179.69  5007.4  180.86
  5035.7  187.46  5049.8  188.57  5078.1  189.70  5134.7  193.14  5191.2  195.38
  5261.9  199.43  5290.2  199.93  5375.1  205.14  5445.8  208.21  5459.9  209.61
  5474.1  209.86  5502.4  212.32  5516.5  213.56  5527.1  215.66  5530.6  215.66
#Mann=3,-1,0
  4715.0     0.1       0  4990.2    0.07       0  4996.2     0.1       0
Bank Sta=4990.2,4996.2
Exp/Cntr=0.3,0.1

Type RM Length L Ch R = 1,12181,589,589,589
BEGIN DESCRIPTION:
UNT048 IN NURI 27.0
END DESCRIPTION:
XS GIS Cut Line= 3
      2320838.48     13285716.71      2320822.57     13285895.75
      2321057.26     13286369.12
#Sta/Elev= 30
  4647.7  203.40  4678.0  199.69  4768.3  194.11  4824.6  189.47  4862.2  188.33
  4929.1  184.54  4973.8  184.79  4982.4  183.46  4988.0  180.51  5001.8  177.28
  5004.5  176.78  5007.8  177.28  5010.4  181.91  5027.2  184.70  5139.3  190.09
  5152.4  192.41  5165.7  193.18  5174.7  195.58  5184.1  196.53  5197.0  201.32
  5234.5  202.98  5241.7  204.13  5273.8  206.04  5279.4  205.74  5289.3  207.01
  5301.8  207.18  5318.6  208.88  5324.2  208.07  5341.1  209.83  5355.8  209.47
#Mann=5,-1,0
  4647.7     0.1       0  5001.8    0.07       0  5007.8     0.1       0
  5165.7    0.05       0  5289.3     0.1       0
Bank Sta=5001.8,5007.8
Exp/Cntr=0.3,0.1

Type RM Length L Ch R = 1,11592,478,478,478
BEGIN DESCRIPTION:
UNT048 IN NURI 26.0
END DESCRIPTION:
XS GIS Cut Line= 3
      2320404.86     13285824.16      2320420.77     13286034.99
      2320508.19     13286702.56
#Sta/Elev= 30
  4435.9  199.47  4458.7  198.78  4508.8  195.52  4639.2  189.07  4645.8  187.89
  4663.3  187.64  4731.7  183.93  4790.4  181.12  4870.4  181.92  4921.5  182.43
  4963.0  181.74  4968.7  180.68  4973.7  180.94  4982.0  179.11  4989.1  174.04
  4991.9  173.54  4995.1  174.04  5002.2  174.58  5012.3  176.41  5022.4  180.25
  5032.5  185.41  5055.2  187.01  5126.4  192.03  5133.3  194.51  5143.4  196.48
  5163.6  198.57  5200.2  200.85  5284.6  202.75  5314.8  204.51  5320.6  204.06
#Mann=7,-1,0
  4435.9     0.1       0  4731.7    0.16       0  4870.4     0.1       0
  4963.0    0.16       0  4989.1    0.07       0  4995.1    0.16       0
  5055.2     0.1       0
Bank Sta=4989.1,4995.1
Exp/Cntr=0.3,0.1

Type RM Length L Ch R = 1,11114,471,471,471
BEGIN DESCRIPTION:
UNT048 IN NURI 25.0
END DESCRIPTION:
XS GIS Cut Line= 2
      2320002.68     13285998.71      2320169.79     13286727.91
#Sta/Elev= 30
  4813.2  202.63  4842.1  201.88  4857.8  199.92  4862.9  200.11  4876.8  198.93
  4900.7  195.52  4905.8  195.65  4913.9  191.60  4924.1  190.30  4943.6  186.49
  4967.4  183.89  4975.4  183.31  4985.7  180.00  4993.8  171.75  4996.5  171.25
  4999.8  171.75  5006.2  174.54  5016.5  177.55  5032.2  179.14  5077.4  178.24
  5135.1  179.39  5216.4  181.05  5278.5  183.66  5379.6  188.38  5467.9  191.47
  5484.1  194.17  5489.2  194.29  5498.7  196.48  5519.2  198.52  5561.3  200.94
#Mann=9,-1,0
  4813.2     0.1       0  4876.8    0.16       0  4967.4     0.1       0
  4993.8    0.07       0  4999.8     0.1       0  5032.2    0.16       0
  5135.1     0.1       0  5278.5    0.16       0  5379.6     0.1       0
Bank Sta=4993.8,4999.8
Exp/Cntr=0.3,0.1

Type RM Length L Ch R = 1,10643,326,326,326
BEGIN DESCRIPTION:
UNT048 IN NURI 24.0
END DESCRIPTION:
XS GIS Cut Line= 3
      2319887.68     13286096.88      2319644.90     13286231.37
      2319651.83     13286823.49
#Sta/Elev= 30
  4526.0  200.39  4534.0  200.22  4539.7  198.76  4550.5  197.84  4606.0  191.91
  4615.3  190.36  4621.0  187.84  4641.0  185.13  4664.5  184.11  4680.5  184.46
  4745.8  181.12  4768.5  180.93  4777.5  181.06  4869.0  176.99  4949.0  175.28
  4979.0  175.34  4996.0  169.56  4998.8  169.06  5002.0  169.56  5009.0  173.48
  5057.3  177.96  5119.0  182.91  5169.1  185.89  5199.1  188.73  5239.1  196.57
  5259.1  198.72  5289.1  200.38  5309.1  202.58  5349.1  204.74  5395.7  209.61
#Mann=7,-1,0
  4526.0    0.16       0  4550.5     0.1       0  4641.0    0.16       0
  4768.5     0.1       0  4996.0    0.07       0  5002.0     0.1       0
  5057.3     0.1       0
Bank Sta=4996,5002
Exp/Cntr=0.3,0.1

Type RM Length L Ch R = 1,10317,373,373,373
BEGIN DESCRIPTION:
UNT048 IN NURI 23.0
END DESCRIPTION:
XS GIS Cut Line= 4
      2319084.11     13285939.52      2319215.38     13286070.79
      2319458.05     13286651.61      2319525.70     13286806.79
#Sta/Elev= 30
  4493.4  198.35  4501.1  197.49  4508.2  195.02  4522.3  192.05  4529.4  191.74
  4536.5  189.57  4571.8  186.92  4800.6  176.15  4950.5  172.95  4983.5  173.48
  4989.1  169.30  4996.9  167.58  4999.7  167.08  5002.9  167.58  5007.3  172.78
  5012.8  170.11  5021.6  173.40  5043.7  174.86  5060.4  177.51  5065.8  176.85
  5097.4  179.44  5184.1  182.99  5190.2  184.44  5205.8  184.63  5281.7  189.99
  5390.2  195.80  5419.1  198.25  5434.2  198.57  5448.0  200.93  5477.8  202.51
#Mann=5,-1,0
  4493.4     0.1       0  4950.5    0.16       0  4996.9    0.07       0
  5002.9    0.16       0  5043.7     0.1       0
Bank Sta=4996.9,5002.9
Exp/Cntr=0.3,0.1