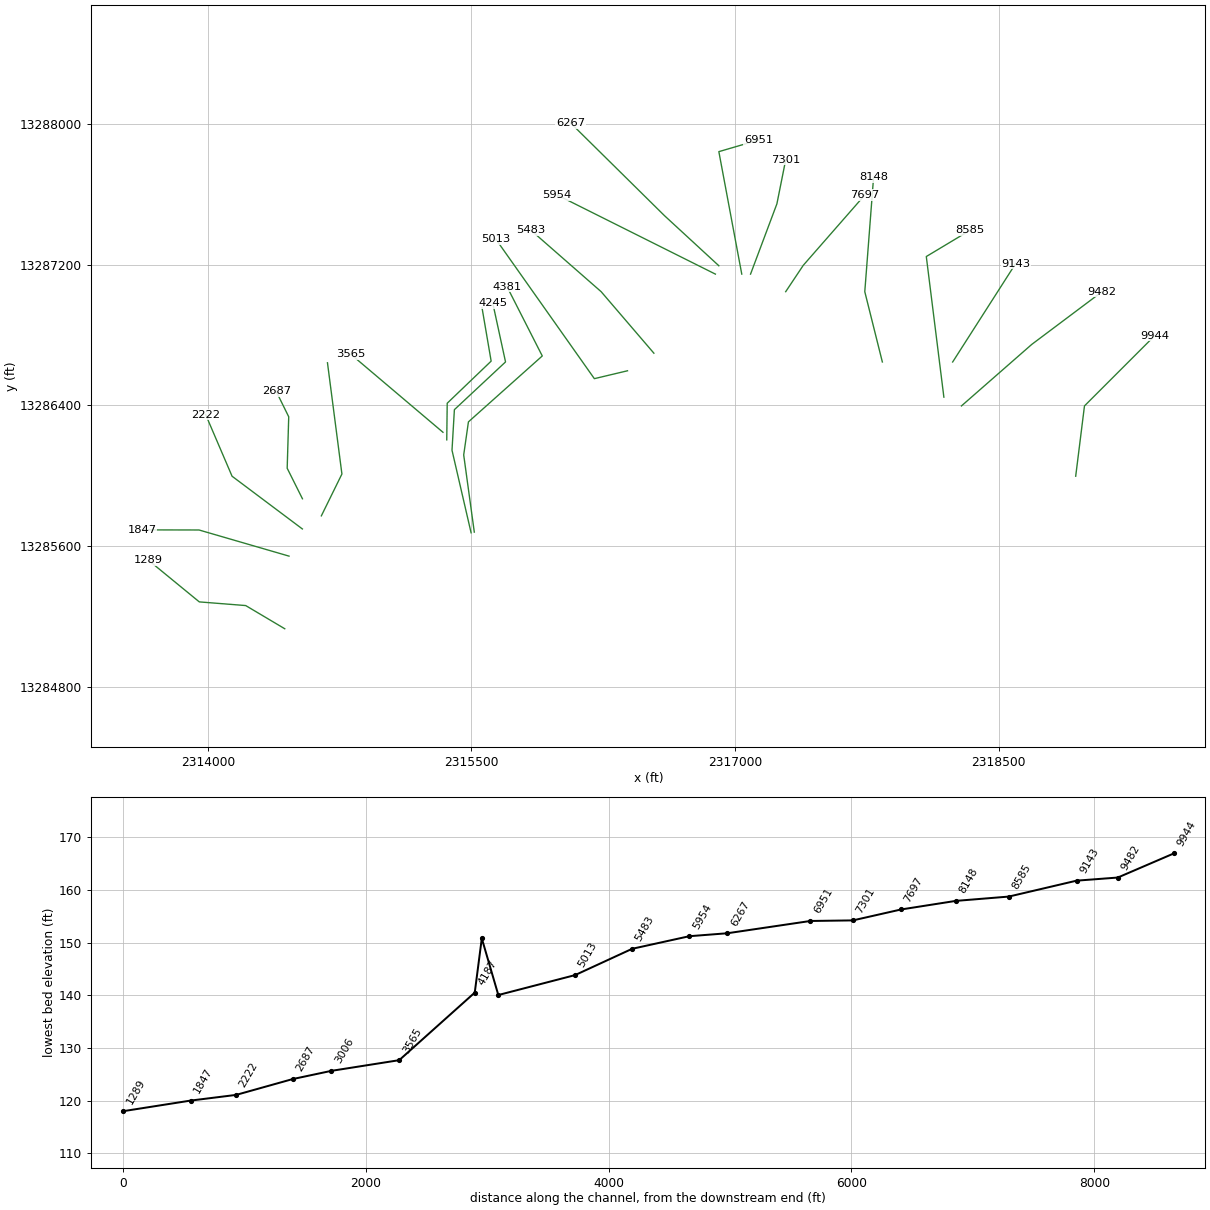
HEC-RAS study UNT048 IN NURI.prj: UNT048 IN NURI Base Level Engineering

--- UNT048 IN NURI.g01 (geometry) --- (continued)

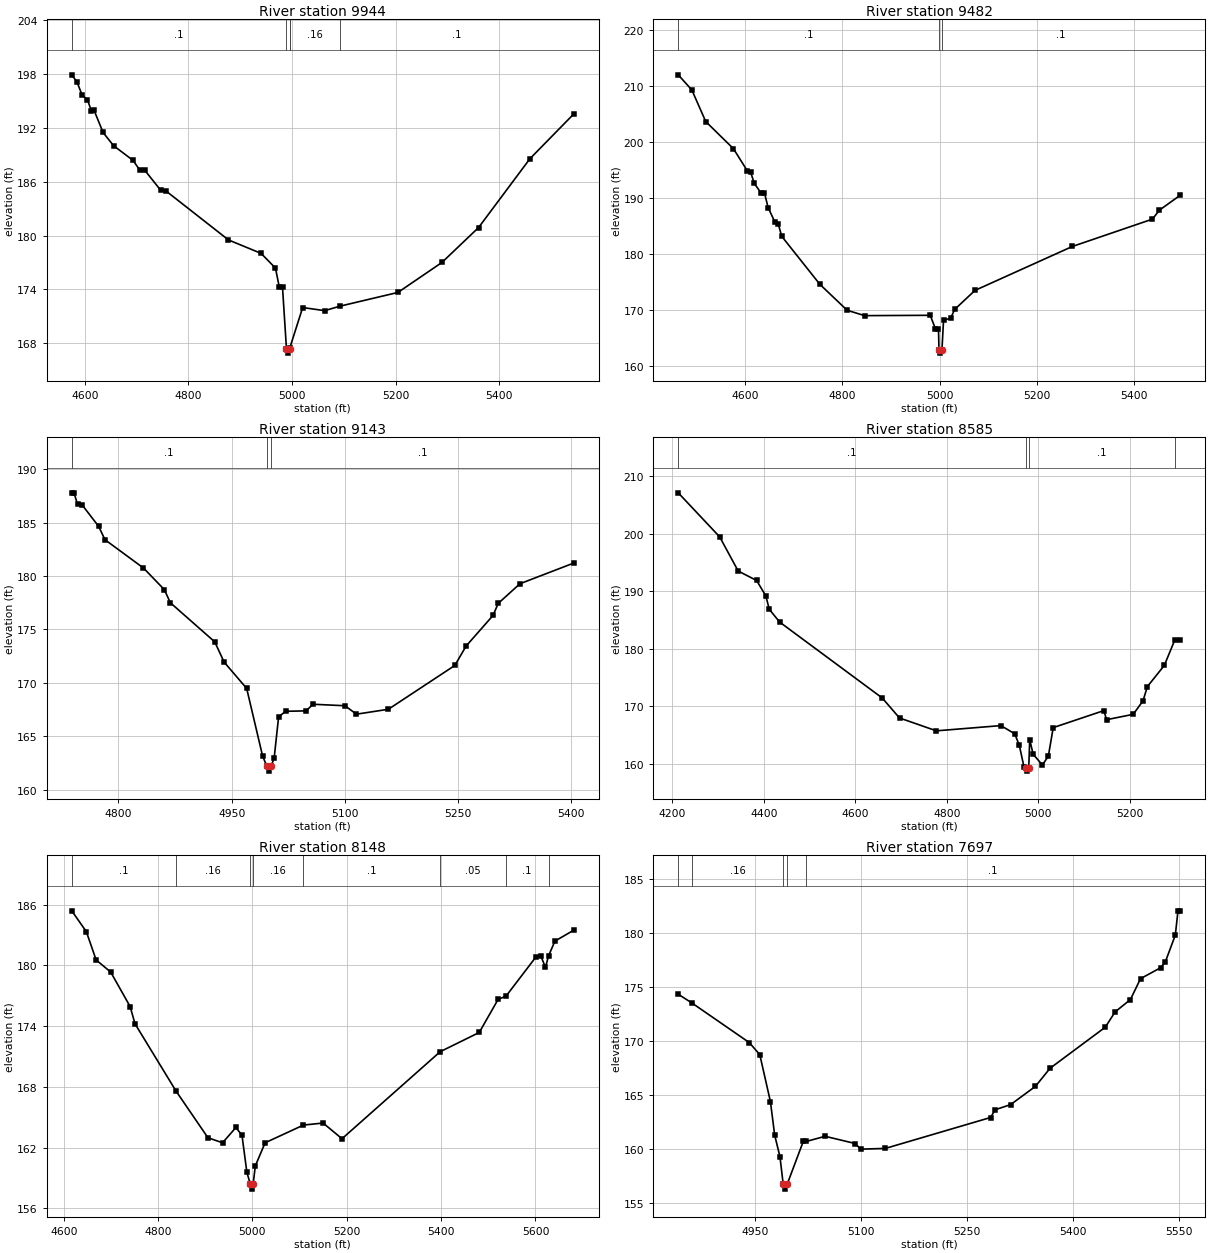
Type RM Length L Ch R = 1,9944,462,462,462
BEGIN DESCRIPTION:
UNT048 IN NURI 22.0
END DESCRIPTION:
XS GIS Cut Line= 3
      2318937.73     13285996.90      2318987.72     13286396.85
      2319387.69     13286796.82
#Sta/Elev= 30
  4575.0  197.91  4585.0  197.12  4595.1  195.64  4605.2  195.14  4612.7  193.92
  4617.8  193.99  4635.4  191.49  4655.6  190.02  4693.4  188.37  4706.0  187.31
  4716.0  187.27  4746.3  185.07  4756.4  184.99  4877.3  179.52  4940.3  178.02
  4968.0  176.38  4975.5  174.24  4981.6  174.24  4989.2  167.41  4992.0  166.91
  4995.2  167.41  4995.8  167.51  5020.5  171.99  5062.9  171.64  5092.4  172.14
  5204.3  173.67  5289.2  177.01  5359.9  180.90  5458.9  188.56  5543.7  193.56
#Mann=5,-1,0
  4575.0     0.1       0  4989.2    0.07       0  4995.2     0.1       0
  4995.8    0.16       0  5092.4     0.1       0
Bank Sta=4989.2,4995.2
Exp/Cntr=0.3,0.1

Type RM Length L Ch R = 1,9482,339,339,339
BEGIN DESCRIPTION:
UNT048 IN NURI 21.0
END DESCRIPTION:
XS GIS Cut Line= 3
      2318287.68     13286396.82      2318687.72     13286746.85
      2319087.76     13287046.88
#Sta/Elev= 30
  4462.9  212.07  4490.9  209.36  4519.4  203.72  4576.4  198.86  4604.8  194.92
  4611.5  194.71  4619.1  192.68  4633.3  190.92  4640.0  190.98  4647.6  188.33
  4661.8  185.71  4668.4  185.41  4675.6  183.20  4753.9  174.63  4809.9  169.99
  4845.9  169.03  4980.7  169.09  4991.1  166.73  4997.6  166.73  4998.7  162.83
  5001.5  162.33  5004.7  162.83  5008.0  168.20  5022.6  168.58  5030.9  170.14
  5072.6  173.54  5272.6  181.39  5437.2  186.28  5451.7  187.89  5494.5  190.56
#Mann=3,-1,0
  4462.9     0.1       0  4998.7    0.07       0  5004.7     0.1       0
Bank Sta=4998.7,5004.7
Exp/Cntr=0.3,0.1

Type RM Length L Ch R = 1,9143,558,558,558
BEGIN DESCRIPTION:
UNT048 IN NURI 20.0
END DESCRIPTION:
XS GIS Cut Line= 2
      2318237.72     13286646.85      2318596.27     13287207.03
#Sta/Elev= 30
  4738.2  187.79  4741.2  187.79  4745.8  186.71  4751.7  186.68  4773.8  184.65
  4782.2  183.40  4833.2  180.75  4860.8  178.73  4868.8  177.50  4927.6  173.84
  4940.0  171.95  4969.9  169.48  4991.0  163.15  4996.4  162.24  4999.2  161.74
  5002.4  162.24  5006.3  162.96  5012.2  166.82  5021.5  167.34  5048.6  167.38
  5057.8  168.00  5100.1  167.86  5115.3  167.07  5157.6  167.53  5245.6  171.63
  5260.6  173.45  5296.2  176.31  5303.1  177.44  5331.9  179.28  5403.3  181.22
#Mann=3,-1,0
  4738.2     0.1       0  4996.4    0.07       0  5002.4     0.1       0
Bank Sta=4996.4,5002.4
Exp/Cntr=0.3,0.1

Type RM Length L Ch R = 1,8585,437,437,437
BEGIN DESCRIPTION:
UNT048 IN NURI 19.0
END DESCRIPTION:
XS GIS Cut Line= 3
      2318187.73     13286446.81      2318087.72     13287246.85
      2318337.70     13287396.85
#Sta/Elev= 30
  4212.7  207.14  4303.4  199.47  4343.8  193.53  4384.1  191.89  4404.2  189.21
  4411.8  186.87  4434.5  184.65  4658.7  171.45  4696.5  167.97  4777.1  165.73
  4918.2  166.64  4948.4  165.22  4958.5  163.21  4968.6  159.47  4973.1  159.22
  4975.9  158.72  4979.1  159.22  4981.2  164.21  4988.7  161.66  5008.9  159.79
  5021.9  161.31  5032.6  166.29  5143.4  169.25  5149.2  167.67  5207.5  168.60
  5228.9  170.95  5238.6  173.44  5275.5  177.11  5298.4  181.53  5310.5  181.53
#Mann=4,-1,0
  4212.7     0.1       0  4973.1    0.07       0  4979.1     0.1       0
  5298.4    0.05       0
Bank Sta=4973.1,4979.1
Exp/Cntr=0.3,0.1

Type RM Length L Ch R = 1,8148,451,451,451
BEGIN DESCRIPTION:
UNT048 IN NURI 18.0
END DESCRIPTION:
XS GIS Cut Line= 3
      2317837.72     13286646.84      2317737.72     13287046.85
      2317787.72     13287696.81
#Sta/Elev= 30
  4617.1  185.40  4648.0  183.34  4668.7  180.55  4699.6  179.35  4740.8  175.94
  4751.1  174.24  4838.1  167.59  4905.7  162.98  4936.7  162.48  4965.0  163.99
  4977.9  163.22  4988.2  159.58  4995.5  158.40  4998.3  157.90  5001.5  158.40
  5006.2  160.20  5026.9  162.48  5108.2  164.23  5149.8  164.43  5189.9  162.88
  5398.0  171.48  5480.8  173.38  5520.9  176.66  5537.4  176.96  5601.1  180.85
  5611.1  180.96  5621.2  179.81  5627.6  180.94  5641.2  182.41  5681.3  183.49
#Mann=8,-1,0
  4617.1     0.1       0  4838.1    0.16       0  4995.5    0.07       0
  5001.5    0.16       0  5108.2     0.1       0  5398.0    0.05       0
  5537.4     0.1       0  5627.6    0.05       0
Bank Sta=4995.5,5001.5
Exp/Cntr=0.3,0.1

Type RM Length L Ch R = 1,7697,396,396,396
BEGIN DESCRIPTION:
UNT048 IN NURI 17.0
END DESCRIPTION:
XS GIS Cut Line= 3
      2317287.75     13287046.89      2317387.72     13287196.85
      2317737.69     13287596.83
#Sta/Elev= 30
  4840.7  174.31  4860.1  173.50  4941.3  169.84  4956.3  168.72  4971.4  164.36
  4977.4  161.27  4984.9  159.27  4989.4  156.77  4992.1  156.27  4995.4  156.77
  5017.9  160.68  5022.0  160.68  5048.9  161.16  5091.6  160.49  5099.2  159.97
  5134.4  160.04  5283.4  162.90  5290.0  163.62  5311.8  164.09  5347.0  165.78
  5367.8  167.46  5446.1  171.26  5459.9  172.67  5481.7  173.82  5496.0  175.75
  5524.4  176.76  5531.1  177.29  5545.3  179.78  5549.1  182.03  5552.4  182.03
#Mann=5,-1,0
  4840.7     0.1       0  4860.1    0.16       0  4989.4    0.07       0
  4995.4    0.16       0  5022.0     0.1       0
Bank Sta=4989.4,4995.4
Exp/Cntr=0.3,0.1

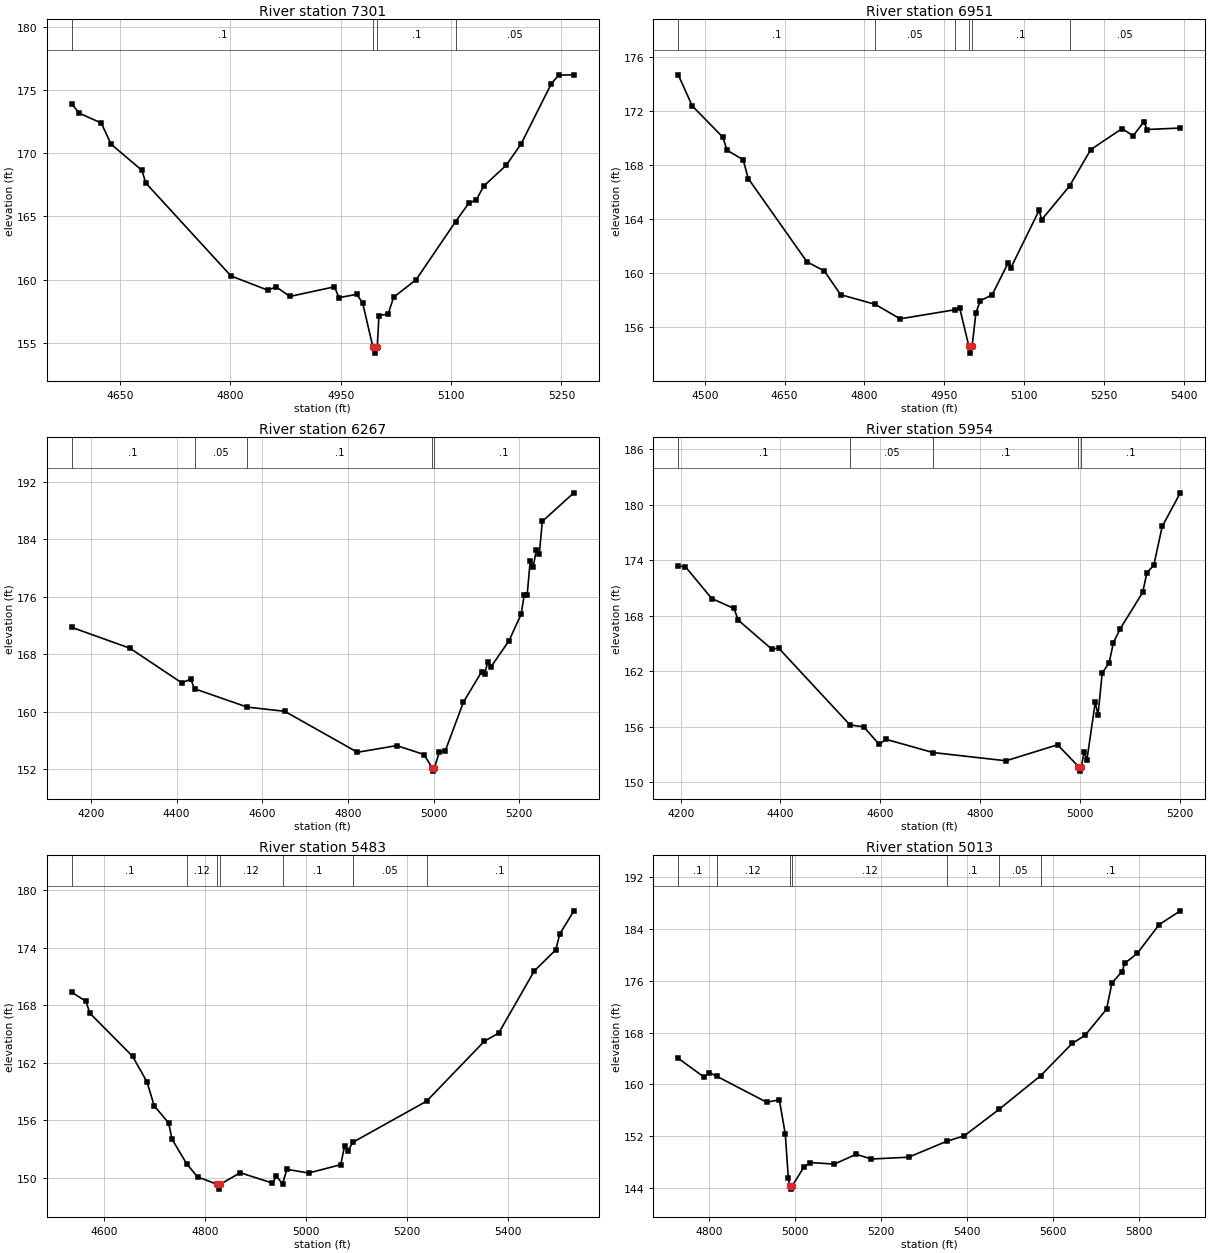
Type RM Length L Ch R = 1,7301,350,350,350
BEGIN DESCRIPTION:
UNT048 IN NURI 16.0
END DESCRIPTION:
XS GIS Cut Line= 3
      2317087.72     13287146.84      2317237.72     13287546.85
      2317287.73     13287796.89
#Sta/Elev= 30
  4584.6  173.91  4594.4  173.17  4624.7  172.38  4638.0  170.71  4679.8  168.65
  4685.2  167.64  4800.9  160.30  4850.7  159.18  4862.3  159.43  4881.0  158.68
  4941.5  159.44  4947.7  158.58  4971.8  158.85  4979.8  158.17  4993.7  154.70
  4996.4  154.20  4999.7  154.70  5002.0  157.17  5014.4  157.29  5022.0  158.62
  5052.6  160.01  5106.1  164.59  5124.0  166.04  5134.2  166.31  5144.4  167.40
  5175.0  169.05  5195.4  170.76  5236.2  175.49  5246.4  176.17  5266.8  176.19
#Mann=4,-1,0
  4584.6     0.1       0  4993.7    0.07       0  4999.7     0.1       0
  5106.1    0.05       0
Bank Sta=4993.7,4999.7
Exp/Cntr=0.3,0.1

Type RM Length L Ch R = 1,6951,684,684,684
BEGIN DESCRIPTION:
UNT048 IN NURI 15.0
END DESCRIPTION:
XS GIS Cut Line= 3
      2317037.73     13287146.82      2316907.40     13287843.64
      2317132.87     13287909.55
#Sta/Elev= 30
  4450.1  174.70  4476.4  172.40  4534.2  170.07  4541.7  169.12  4572.2  168.41
  4581.7  167.02  4692.1  160.85  4724.8  160.17  4755.3  158.42  4820.5  157.70
  4867.2  156.63  4969.9  157.30  4979.1  157.44  4996.5  154.59  4999.2  154.09
  5002.5  154.59  5009.7  157.09  5018.0  157.97  5040.2  158.41  5070.6  160.80
  5075.7  160.43  5128.4  164.66  5133.5  163.98  5185.6  166.46  5225.5  169.16
  5284.4  170.72  5305.2  170.18  5325.8  171.24  5331.0  170.65  5393.9  170.76
#Mann=6,-1,0
  4450.1     0.1       0  4820.5    0.05       0  4969.9     0.1       0
  4996.5    0.07       0  5002.5     0.1       0  5185.6    0.05       0
Bank Sta=4996.5,5002.5
Exp/Cntr=0.3,0.1

Type RM Length L Ch R = 1,6267,313,313,313
BEGIN DESCRIPTION:
UNT048 IN NURI 14.0
END DESCRIPTION:
XS GIS Cut Line= 3
      2316907.40     13287194.34      2316598.37     13287479.06
      2316063.66     13288006.83
#Sta/Elev= 30
  4155.6  171.75  4291.3  168.85  4412.1  164.04  4433.1  164.54  4442.2  163.21
  4565.2  160.66  4652.5  160.08  4822.2  154.38  4914.1  155.31  4977.8  154.06
  4995.9  152.26  4998.7  151.76  5001.9  152.26  5013.1  154.37  5027.2  154.59
  5069.6  161.37  5112.1  165.59  5119.2  165.25  5126.2  166.98  5133.3  166.22
  5175.8  169.89  5204.0  173.56  5211.1  176.19  5218.2  176.26  5225.2  180.94
  5232.3  180.20  5239.4  182.45  5246.5  181.98  5253.5  186.49  5327.1  190.46
#Mann=5,-1,0
  4155.6     0.1       0  4442.2    0.05       0  4565.2     0.1       0
  4995.9    0.07       0  5001.9     0.1       0
Bank Sta=4995.9,5001.9
Exp/Cntr=0.3,0.1

Type RM Length L Ch R = 1,5954,471,471,471
BEGIN DESCRIPTION:
UNT048 IN NURI 13.0
END DESCRIPTION:
XS GIS Cut Line= 3
      2316887.73     13287146.85      2316187.72     13287496.85
      2315987.76     13287596.84
#Sta/Elev= 30
  4195.1  173.37  4209.1  173.33  4262.2  169.87  4306.9  168.79  4315.3  167.53
  4382.4  164.40  4396.4  164.50  4539.3  156.20  4566.9  155.99  4597.6  154.10
  4611.6  154.64  4705.6  153.21  4852.0  152.32  4955.4  154.05  4997.1  151.70
  4999.8  151.20  5003.1  151.70  5008.5  153.27  5014.1  152.41  5030.8  158.63
  5036.4  157.31  5044.8  161.81  5058.8  162.93  5067.2  165.10  5081.1  166.62
  5125.9  170.53  5134.3  172.65  5148.2  173.48  5165.0  177.66  5201.3  181.30
#Mann=5,-1,0
  4195.1     0.1       0  4539.3    0.05       0  4705.6     0.1       0
  4997.1    0.07       0  5003.1     0.1       0
Bank Sta=4997.1,5003.1
Exp/Cntr=0.3,0.1

Type RM Length L Ch R = 1,5483,470,470,470
BEGIN DESCRIPTION:
UNT048 IN NURI 12.0
END DESCRIPTION:
XS GIS Cut Line= 3
      2316537.72     13286696.86      2316237.72     13287046.85
      2315837.71     13287396.87
#Sta/Elev= 30
  4536.8  169.34  4564.8  168.42  4572.5  167.17  4657.0  162.67  4685.5  160.00
  4699.8  157.50  4728.3  155.71  4734.9  154.03  4764.1  151.44  4785.4  150.09
  4824.1  149.31  4826.9  148.81  4830.1  149.31  4869.9  150.52  4933.6  149.44
  4941.2  150.16  4953.4  149.37  4962.1  150.88  5004.9  150.49  5068.5  151.36
  5076.1  153.32  5082.7  152.84  5093.2  153.72  5238.3  157.99  5352.3  164.24
  5380.7  165.09  5451.0  171.57  5493.7  173.79  5501.3  175.41  5529.3  177.85
#Mann=7,-1,0
  4536.8     0.1       0  4764.1    0.12       0  4824.1    0.07       0
  4830.1    0.12       0  4953.4     0.1       0  5093.2    0.05       0
  5238.3     0.1       0
Bank Sta=4824.1,4830.1
Exp/Cntr=0.3,0.1

Type RM Length L Ch R = 1,5013,632,632,632
BEGIN DESCRIPTION:
UNT048 IN NURI 11.0
END DESCRIPTION:
XS GIS Cut Line= 3
      2316387.67     13286596.84      2316199.07     13286551.97
      2315637.71     13287346.87
#Sta/Elev= 30
  4729.1  164.02  4789.7  161.09  4801.0  161.82  4818.1  161.27  4934.5  157.24
  4964.1  157.60  4977.9  152.33  4985.0  145.51  4988.1  144.32  4990.9  143.82
  4994.1  144.32  5020.7  147.17  5035.5  147.92  5092.1  147.69  5142.6  149.20
  5178.3  148.47  5264.5  148.75  5352.9  151.20  5394.1  152.06  5474.5  156.12
  5571.2  161.32  5644.9  166.32  5674.5  167.55  5724.7  171.61  5737.2  175.65
  5760.7  177.42  5766.8  178.66  5796.4  180.25  5846.9  184.66  5896.1  186.79
#Mann=7,-1,0
  4729.1     0.1       0  4818.1    0.12       0  4988.1    0.07       0
  4994.1    0.12       0  5352.9     0.1       0  5474.5    0.05       0
  5571.2     0.1       0
Bank Sta=4988.1,4994.1
Exp/Cntr=0.3,0.1

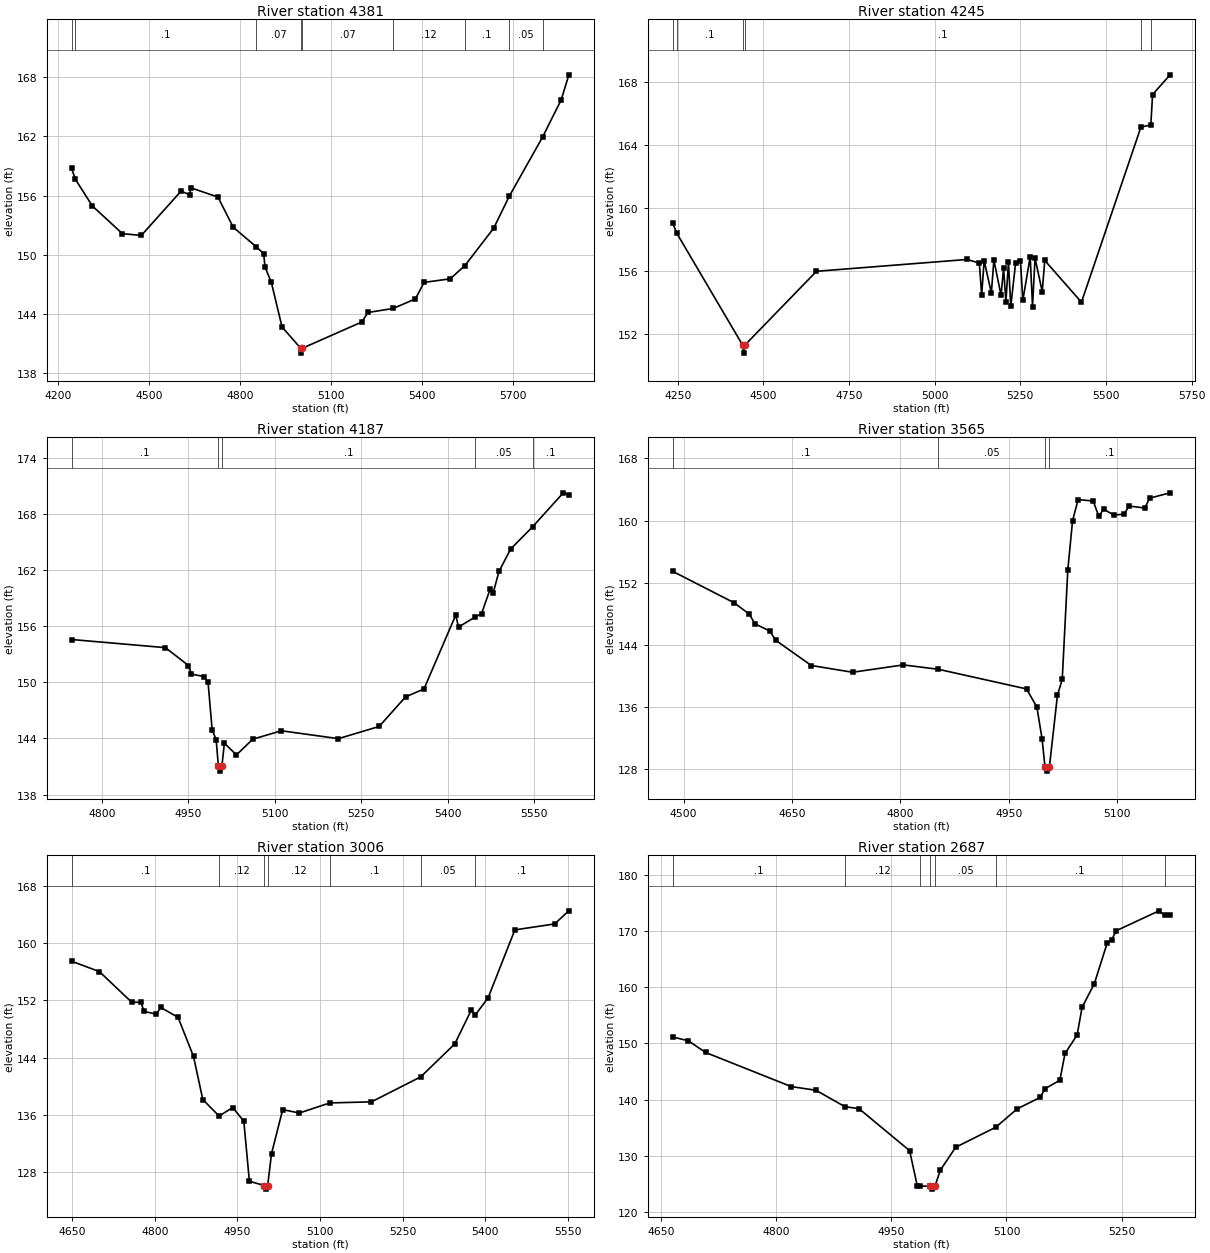
Type RM Length L Ch R = 1,4381,136,136,136
BEGIN DESCRIPTION:
UNT048 IN NURI 10.0
END DESCRIPTION:
XS GIS Cut Line= 5
      2315515.94     13285678.97      2315455.66     13286117.93
      2315482.54     13286306.13      2315902.68     13286681.13
      2315702.00     13287075.57
#Sta/Elev= 30
  4245.6  158.77  4258.5  157.65  4314.1  154.96  4413.2  152.15  4475.6  151.97
  4606.8  156.47  4634.4  156.09  4639.5  156.79  4728.0  155.86  4778.5  152.80
  4853.9  150.83  4878.8  150.13  4883.2  148.77  4904.1  147.20  4939.4  142.69
  5000.6  140.54  5003.4  140.04  5006.6  140.54  5201.7  143.19  5222.7  144.16
  5305.7  144.57  5379.0  145.54  5407.4  147.21  5493.3  147.57  5541.4  148.89
  5636.9  152.71  5688.8  155.98  5797.9  161.94  5859.4  165.72  5884.5  168.25
#Mann=9,-1,0
  4245.6    0.05       0  4258.5     0.1       0  4853.9    0.07       0
  5000.6    0.07       0  5006.6    0.07       0  5305.7    0.12       0
  5541.4     0.1       0  5688.8    0.05       0  5797.9     0.1       0
Bank Sta=5000.6,5006.6
Exp/Cntr=0.3,0.1

Type RM Length L Ch R = 1,4245,58,58,58
BEGIN DESCRIPTION:
UNT048 IN NURI 9.0
END DESCRIPTION:
XS GIS Cut Line= 5
      2315497.71     13285675.10      2315389.10     13286144.69
      2315402.68     13286375.58      2315693.65     13286647.15
      2315621.44     13286979.71
#Sta/Elev= 30
  4235.4  159.04  4246.4  158.42  4439.5  151.29  4442.2  150.79  4445.5  151.29
  4654.9  155.98  5094.5  156.73  5130.2  156.50  5137.0  154.48  5144.3  156.65
  5165.3  154.61  5172.7  156.69  5193.7  154.45  5201.0  156.18  5207.8  154.04
  5215.2  156.55  5222.0  153.75  5236.2  156.52  5250.3  156.63  5257.2  154.13
  5278.7  156.91  5285.5  153.74  5292.8  156.82  5313.8  154.69  5321.2  156.67
  5428.3  154.02  5602.0  165.13  5630.8  165.26  5635.9  167.19  5687.0  168.44
#Mann=6,-1,0
  4235.4    0.05       0  4246.4     0.1       0  4439.5    0.07       0
  4445.5     0.1       0  5602.0    0.05       0  5630.8     0.1       0
Bank Sta=4439.5,4445.5
Exp/Cntr=0.3,0.1

Type RM Length L Ch R = 1,4187,622,622,622
BEGIN DESCRIPTION:
Mapping XS b5f11802
END DESCRIPTION:
XS GIS Cut Line= 4
      2315359.21     13286203.82      2315361.82     13286412.13
      2315611.82     13286651.71      2315559.73     13286956.40
#Sta/Elev= 30
  4746.9  154.56  4910.0  153.69  4950.0  151.78  4955.1  150.87  4977.0  150.60
  4984.0  149.99  4991.1  144.92  4998.1  143.83  5002.0  141.00  5004.8  140.50
  5008.0  141.00  5012.3  143.49  5033.3  142.23  5061.6  143.91  5111.3  144.81
  5210.4  143.97  5281.1  145.27  5327.0  148.43  5359.0  149.28  5414.0  157.15
  5419.1  155.90  5448.2  156.97  5458.9  157.31  5474.1  159.98  5479.2  159.54
  5489.3  161.84  5509.6  164.23  5547.9  166.62  5600.9  170.23  5610.6  170.03
#Mann=5,-1,0
  4746.9     0.1       0  5002.0    0.07       0  5008.0     0.1       0
  5448.2    0.05       0  5547.9     0.1       0
Bank Sta=5002,5008
Exp/Cntr=0.3,0.1

Type RM Length L Ch R = 1,3565,559,559,559
BEGIN DESCRIPTION:
UNT048 IN NURI 8.0
END DESCRIPTION:
XS GIS Cut Line= 2
      2315337.68     13286246.89      2314812.57     13286691.41
#Sta/Elev= 30
  4485.1  153.44  4570.2  149.38  4591.0  147.92  4598.8  146.68  4619.6  145.73
  4627.4  144.56  4676.8  141.30  4733.9  140.43  4804.2  141.38  4852.7  140.81
  4974.5  138.28  4988.8  135.95  4996.0  131.86  5000.1  128.18  5002.8  127.68
  5006.1  128.18  5017.3  137.48  5023.9  139.50  5031.6  153.62  5038.2  159.99
  5045.9  162.70  5066.8  162.51  5074.5  160.52  5081.1  161.47  5095.3  160.70
  5109.6  160.82  5116.2  161.87  5138.2  161.61  5144.8  162.88  5173.1  163.57
#Mann=4,-1,0
  4485.1     0.1       0  4852.7    0.05       0  5000.1    0.04       0
  5006.1     0.1       0
Bank Sta=5000.1,5006.1
Exp/Cntr=0.3,0.1

Type RM Length L Ch R = 1,3006,319,319,319
BEGIN DESCRIPTION:
UNT048 IN NURI 7.0
END DESCRIPTION:
XS GIS Cut Line= 3
      2314645.75     13285771.44      2314762.71     13286009.34
      2314680.52     13286642.43
#Sta/Elev= 30
  4648.7  157.46  4699.3  156.01  4757.9  151.74  4774.8  151.71  4780.4  150.46
  4802.8  150.07  4810.7  151.00  4842.2  149.63  4870.3  144.17  4887.2  138.15
  4916.8  135.85  4941.5  137.04  4961.7  135.13  4971.8  126.75  4999.0  126.15
  5001.8  125.65  5005.0  126.15  5012.1  130.62  5032.3  136.75  5062.6  136.27
  5117.8  137.68  5193.6  137.83  5283.1  141.32  5344.9  145.91  5375.0  150.64
  5382.3  149.97  5405.4  152.33  5454.1  161.83  5526.4  162.66  5552.2  164.49
#Mann=7,-1,0
  4648.7     0.1       0  4916.8    0.12       0  4999.0    0.07       0
  5005.0    0.12       0  5117.8     0.1       0  5283.1    0.05       0
  5382.3     0.1       0
Bank Sta=4999,5005
Exp/Cntr=0.3,0.1

Type RM Length L Ch R = 1,2687,465,465,465
BEGIN DESCRIPTION:
UNT048 IN NURI 6.0
END DESCRIPTION:
XS GIS Cut Line= 4
      2314538.11     13285868.61      2314451.29     13286042.24
      2314460.10     13286334.98      2314388.78     13286479.77
#Sta/Elev= 30
  4664.9  151.15  4685.3  150.46  4707.7  148.39  4819.5  142.32  4851.6  141.67
  4889.5  138.74  4907.6  138.41  4973.7  130.93  4983.7  124.67  4987.2  124.65
  5000.7  124.59  5003.5  124.09  5006.7  124.59  5013.7  127.45  5033.7  131.53
  5086.1  135.10  5113.8  138.35  5143.8  140.40  5150.3  141.95  5169.6  143.46
  5176.3  148.21  5192.1  151.50  5198.6  156.43  5214.6  160.65  5231.5  167.94
  5237.0  168.40  5243.2  170.05  5298.9  173.58  5306.1  172.79  5313.3  172.79
#Mann=7,-1,0
  4664.9     0.1       0  4889.5    0.12       0  4987.2    0.05       0
  5000.7    0.04       0  5006.7    0.05       0  5086.1     0.1       0
  5306.1    0.16       0
Bank Sta=5000.7,5006.7
Exp/Cntr=0.3,0.1

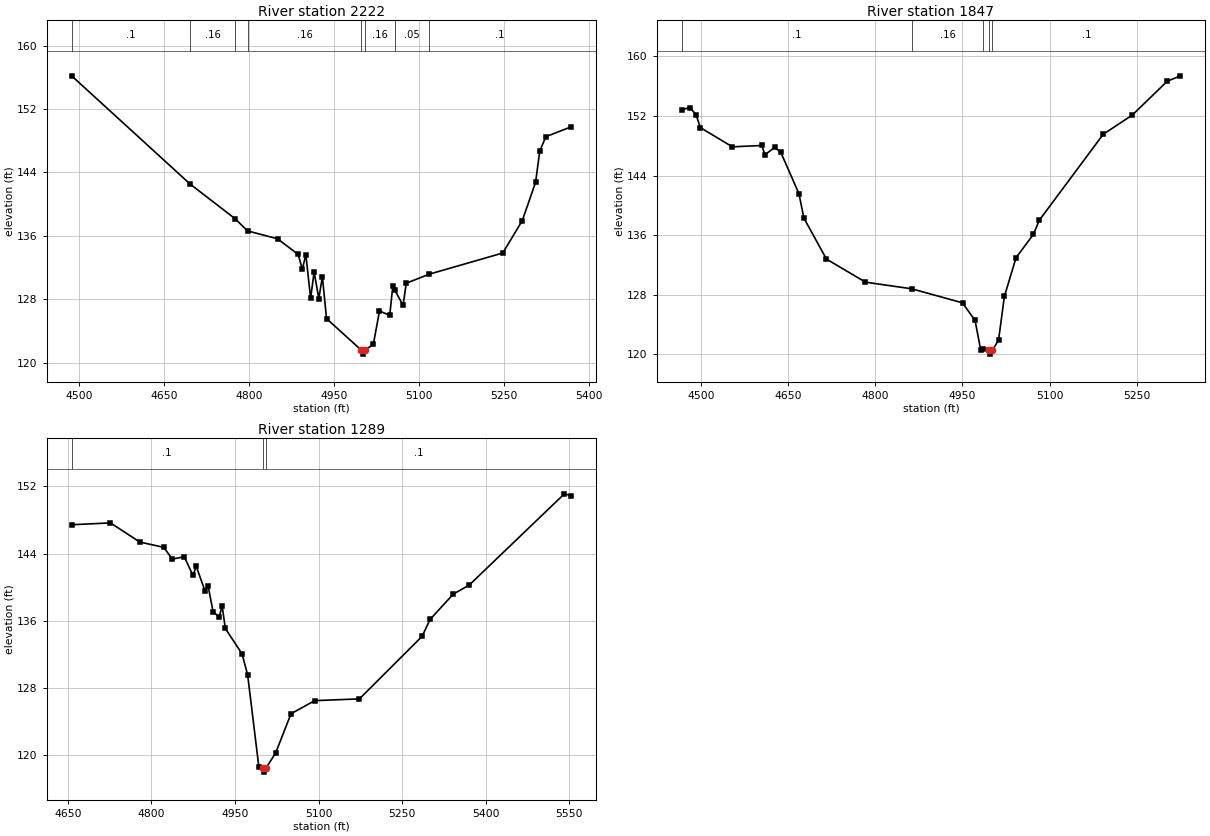
Type RM Length L Ch R = 1,2222,375,375,375
BEGIN DESCRIPTION:
UNT048 IN NURI 5.0
END DESCRIPTION:
XS GIS Cut Line= 3
      2314537.71     13285696.86      2314137.72     13285996.85
      2313987.71     13286346.87
#Sta/Elev= 30
  4487.3  156.18  4696.7  142.52  4775.4  138.19  4797.9  136.63  4850.8  135.63
  4887.3  133.66  4894.6  131.78  4900.8  133.64  4909.2  128.13  4915.4  131.44
  4923.7  128.10  4930.0  130.85  4937.3  125.57  4998.8  121.59  5001.5  121.09
  5004.8  121.59  5019.9  122.31  5030.8  126.53  5048.9  125.98  5054.4  129.74
  5057.5  129.20  5072.5  127.24  5078.0  130.03  5118.6  131.17  5248.4  133.84
  5282.9  137.93  5306.4  142.77  5313.7  146.70  5324.6  148.51  5368.1  149.72
#Mann=8,-1,0
  4487.3     0.1       0  4696.7    0.16       0  4775.4    0.12       0
  4797.9    0.16       0  4998.8    0.07       0  5004.8    0.16       0
  5057.5    0.05       0  5118.6     0.1       0
Bank Sta=4998.8,5004.8
Exp/Cntr=0.3,0.1

Type RM Length L Ch R = 1,1847,558,558,558
BEGIN DESCRIPTION:
UNT048 IN NURI 4.0
END DESCRIPTION:
XS GIS Cut Line= 3
      2314461.70     13285542.24      2313949.77     13285690.97
      2313624.87     13285691.55
#Sta/Elev= 30
  4466.9  152.87  4481.5  153.11  4491.9  152.19  4499.2  150.45  4554.4  147.86
  4605.0  148.04  4610.3  146.79  4627.3  147.80  4637.7  147.10  4668.9  141.55
  4677.3  138.29  4716.1  132.78  4783.2  129.68  4862.5  128.79  4950.1  126.90
  4971.7  124.53  4981.3  120.60  4985.7  120.68  4995.5  120.51  4998.2  120.01
  5001.5  120.51  5012.1  121.91  5022.1  127.76  5042.1  132.96  5072.1  136.11
  5082.1  137.99  5192.1  149.55  5242.1  152.13  5302.1  156.67  5324.9  157.40
#Mann=5,-1,0
  4466.9     0.1       0  4862.5    0.16       0  4985.7     0.1       0
  4995.5    0.07       0  5001.5     0.1       0
Bank Sta=4995.5,5001.5
Exp/Cntr=0.3,0.1

Type RM Length L Ch R = 1,1289,313,313,313
BEGIN DESCRIPTION:
UNT048 IN NURI 3.0
END DESCRIPTION:
XS GIS Cut Line= 4
      2314437.44     13285129.03      2314215.18     13285260.99
      2313951.29     13285281.83      2313663.06     13285517.97
#Sta/Elev= 30
  4656.7  147.44  4726.5  147.66  4779.1  145.38  4822.0  144.75  4837.6  143.35
  4859.0  143.63  4874.6  141.40  4880.4  142.50  4896.0  139.59  4901.8  140.14
  4910.8  137.05  4921.9  136.47  4926.9  137.81  4932.7  135.09  4962.8  132.06
  4972.8  129.54  4992.9  118.58  4999.9  118.49  5002.7  117.99  5005.9  118.49
  5023.0  120.27  5050.6  124.94  5093.2  126.50  5173.4  126.71  5285.9  134.15
  5300.3  136.17  5341.9  139.18  5370.6  140.26  5541.4  151.12  5552.5  150.92
#Mann=3,-1,0
  4656.7     0.1       0  4999.9    0.07       0  5005.9     0.1       0
Bank Sta=4999.9,5005.9
Exp/Cntr=0.3,0.1