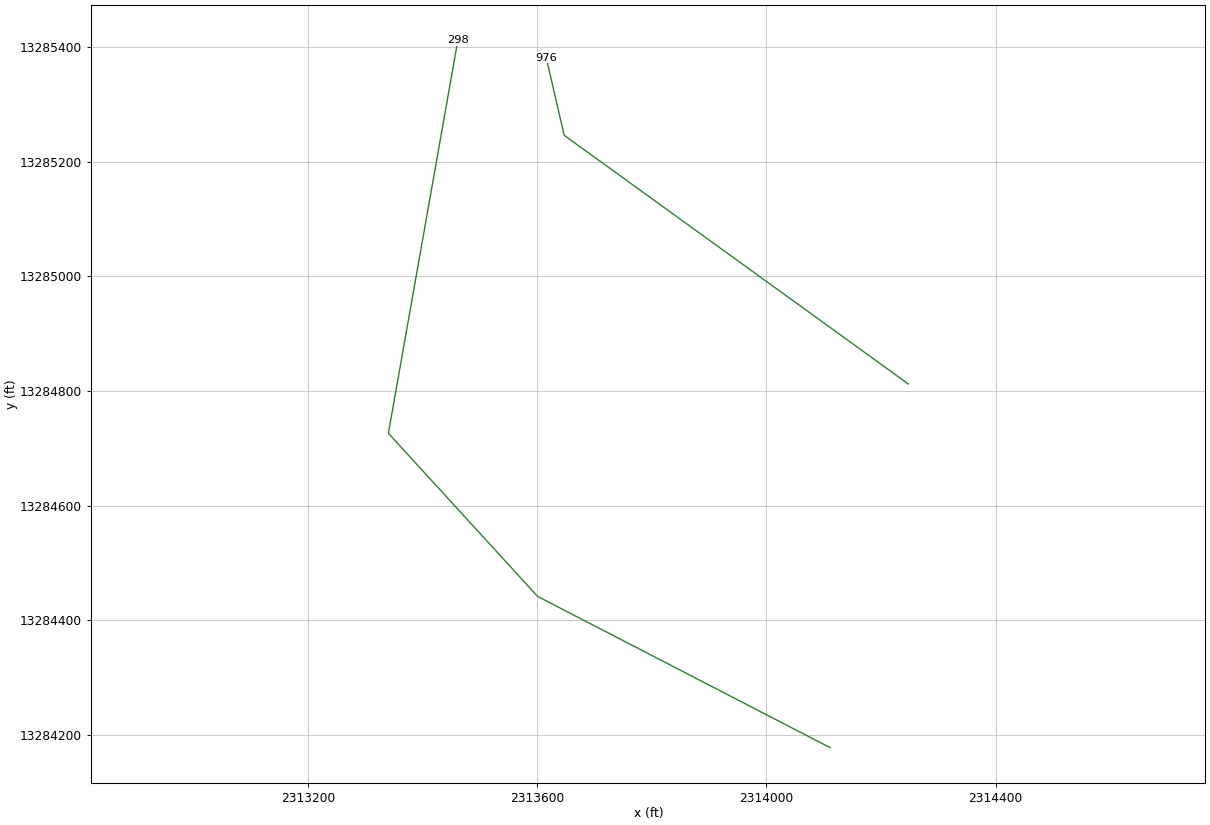
HEC-RAS study UNT048 IN NURI.prj: UNT048 IN NURI Base Level Engineering

--- UNT048 IN NURI.g01 (geometry) --- (continued)

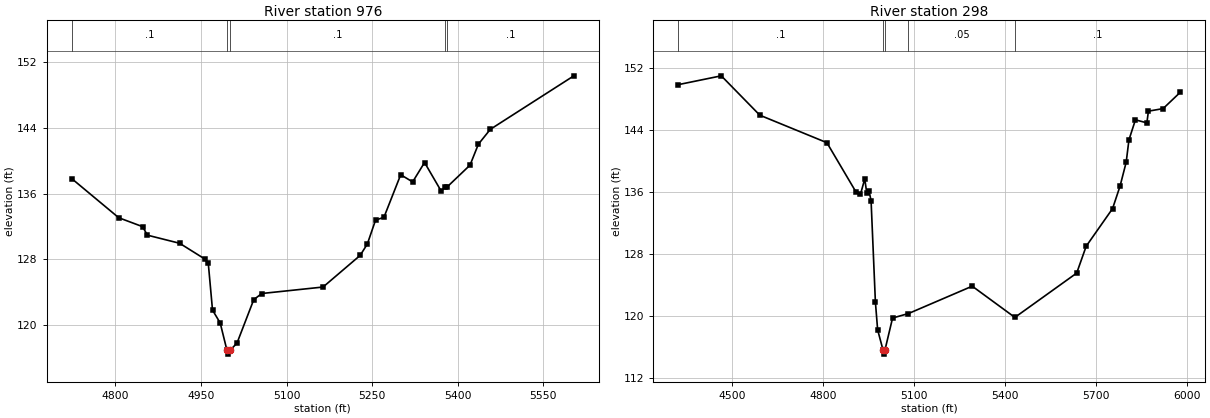
Type RM Length L Ch R = 1,976,678,678,678
BEGIN DESCRIPTION:
UNT048 IN NURI 2.0
END DESCRIPTION:
XS GIS Cut Line= 3
      2314247.69     13284812.39      2313646.98     13285246.42
      2313615.73     13285381.86
#Sta/Elev= 30
  4723.5  137.82  4805.8  133.05  4847.6  131.96  4856.1  130.92  4912.6  129.93
  4956.7  128.01  4962.8  127.49  4970.2  121.78  4983.7  120.20  4995.4  116.90
  4998.2  116.40  5001.4  116.90  5013.1  117.74  5042.5  123.05  5056.6  123.80
  5164.0  124.59  5229.0  128.45  5241.6  129.84  5256.0  132.76  5270.7  133.10
  5300.1  138.30  5321.0  137.42  5341.9  139.79  5371.3  136.27  5378.1  136.83
  5380.8  136.76  5421.6  139.47  5436.3  142.03  5457.2  143.84  5603.6  150.37
#Mann=5,-1,0
  4723.5     0.1       0  4995.4    0.07       0  5001.4     0.1       0
  5378.1    0.05       0  5380.8     0.1       0
Bank Sta=4995.4,5001.4
Exp/Cntr=0.3,0.1

Type RM Length L Ch R = 1,298,0,0,0
BEGIN DESCRIPTION:
UNT048 IN NURI 1.0
END DESCRIPTION:
XS GIS Cut Line= 4
      2314110.99     13284177.67      2313600.60     13284441.55
      2313340.18     13284726.27      2313461.54     13285412.80
#Sta/Elev= 30
  4321.2  149.84  4463.3  150.98  4590.5  145.90  4812.0  142.35  4908.6  135.95
  4922.8  135.68  4937.0  137.68  4943.7  135.82  4951.1  136.15  4957.9  134.83
  4972.1  121.80  4979.5  118.20  4997.5  115.56  5000.2  115.06  5003.5  115.56
  5028.8  119.72  5081.4  120.30  5291.8  123.83  5432.6  119.80  5636.7  125.52
  5668.1  128.99  5755.1  133.84  5779.8  136.74  5800.1  139.83  5809.2  142.71
  5830.6  145.30  5868.4  144.91  5873.5  146.42  5922.0  146.75  5978.8  148.86
#Mann=5,-1,0
  4321.2     0.1       0  4997.5    0.07       0  5003.5     0.1       0
  5081.4    0.05       0  5432.6     0.1       0
Bank Sta=4997.5,5003.5
Exp/Cntr=0.3,0.1

Chan Stop Cuts=-1