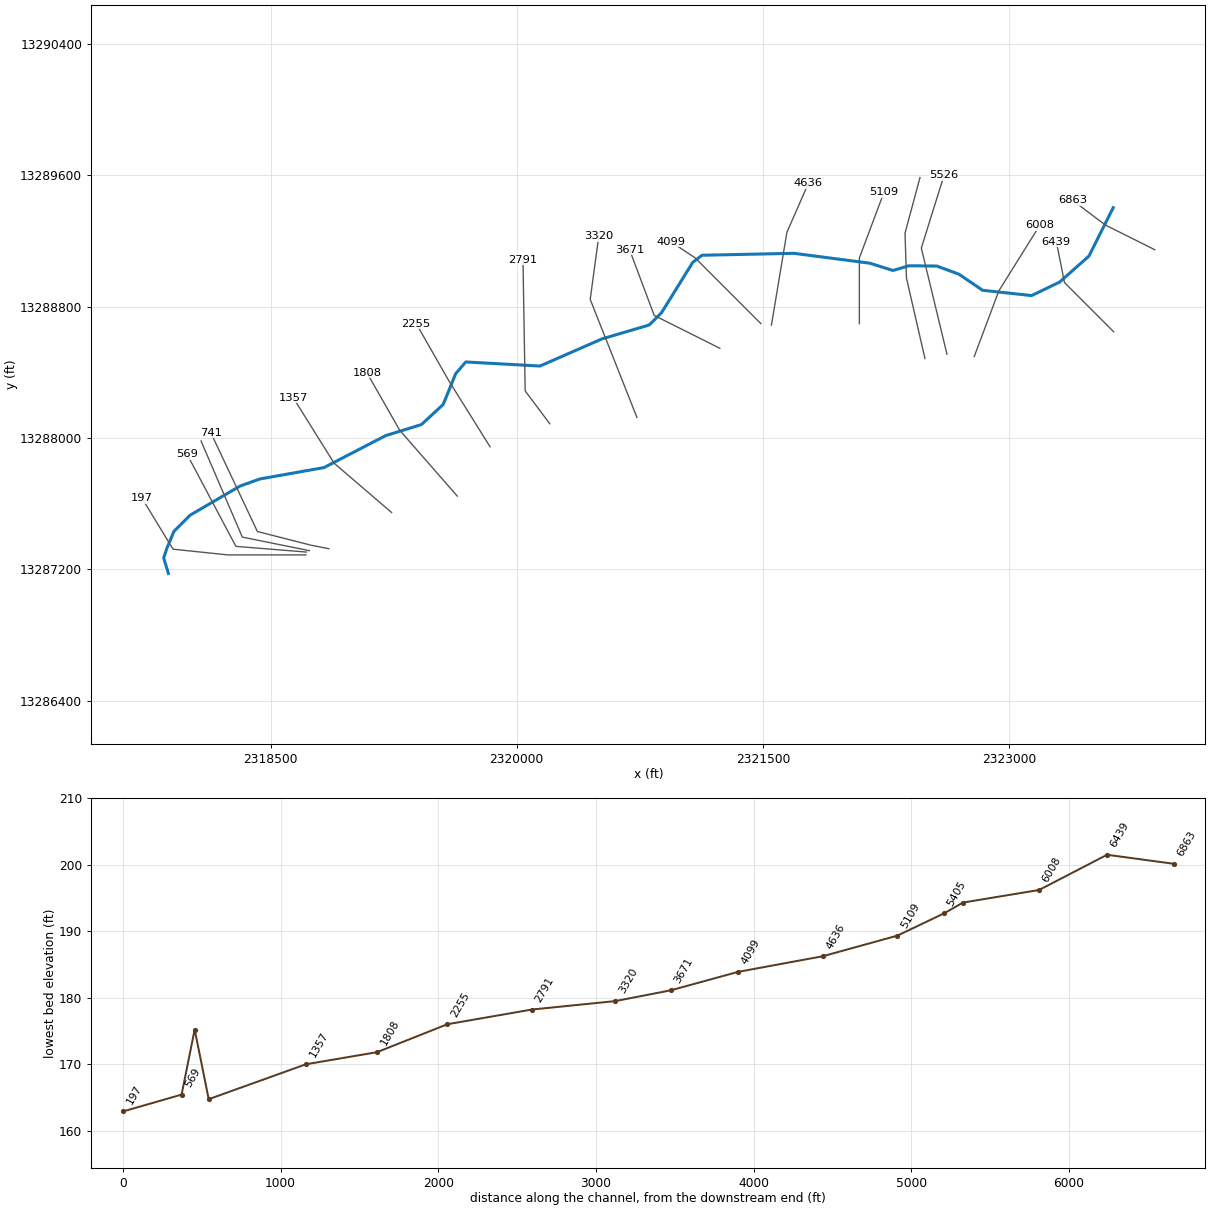
--- UNT049 IN NURI.prj (project) ---

Proj Title=UNT049 IN NURI Base Level Engineering
Current Plan=p01
Default Exp/Contr=0.3,0.1
English Units
Geom File=g01
Flow File=f01
Plan File=p01
BEGIN DESCRIPTION:
UNT049 IN NURI
END DESCRIPTION:

--- UNT049 IN NURI.p01 (plan) ---

Plan Title=Multiple Run
Short Identifier=Multiple
Geom File=g01
Flow File=f01
Subcritical Flow
K Sum by GR= 0
Std Step Tol= 0.01
Critical Tol= 0.01
Num of Std Step Trials= 20
Max Error Tol= 0.3
Flow Tol Ratio= 0.001
Split Flow NTrial= 30
Split Flow Tol= 0.02
Split Flow Ratio= 0.02
Log Output Level= 0
Friction Slope Method= 1
Unsteady Friction Slope Method= 2
Unsteady Bridges Friction Slope Method= 1
Parabolic Critical Depth
Global Vel Dist=  1 , 1 , 1
Global Log Level= 0
CheckData=True
Encroach Param= -1, 0, 0, 0
BEGIN DESCRIPTION:
Multiple Run
END DESCRIPTION:

--- UNT049 IN NURI.f01 (steady flow) ---

Flow Title=Multiple
Number of Profiles=7
Profile Names=10-year,25-year,50-year,1pct_min,100-year,1pct_plu,500-year
River Rch & RM= UNT049 IN NURI,Reach-1,6863
     502     696     855     767    1037    1402    1531
River Rch & RM= UNT049 IN NURI,Reach-1,6008
     527     733     902     811    1096    1483    1626
River Rch & RM= UNT049 IN NURI,Reach-1,5405
     796    1134    1419    1295    1751    2368    2677
Boundary for River Rch & Prof#=UNT049 IN NURI,Reach-1,1
Up Type=0
Dn Type=3
Dn Slope=0.005
Boundary for River Rch & Prof#=UNT049 IN NURI,Reach-1,2
Up Type=0
Dn Type=3
Dn Slope=0.005
Boundary for River Rch & Prof#=UNT049 IN NURI,Reach-1,3
Up Type=0
Dn Type=3
Dn Slope=0.005
Boundary for River Rch & Prof#=UNT049 IN NURI,Reach-1,4
Up Type=0
Dn Type=3
Dn Slope=0.005
Boundary for River Rch & Prof#=UNT049 IN NURI,Reach-1,5
Up Type=0
Dn Type=3
Dn Slope=0.005
Boundary for River Rch & Prof#=UNT049 IN NURI,Reach-1,6
Up Type=0
Dn Type=3
Dn Slope=0.005
Boundary for River Rch & Prof#=UNT049 IN NURI,Reach-1,7
Up Type=0
Dn Type=3
Dn Slope=0.005

--- UNT049 IN NURI.g01 (geometry) ---

Geom Title=Existing Conditions

River Reach=UNT049 IN NURI,Reach-1
Reach XY= 30
      2323634.29     13289402.81      2323486.49     13289108.16
      2323306.75     13288949.20      2323137.23     13288867.85
      2322838.94     13288899.79      2322693.38     13288998.49
      2322559.70     13289047.53      2322389.57     13289049.27
      2322292.64     13289020.57      2322151.92     13289064.93
      2321688.57     13289125.06      2321129.15     13289113.42
      2321072.45     13289069.81      2320882.69     13288764.17
      2320807.09     13288688.52      2320518.98     13288603.82
      2320142.05     13288438.75      2319689.34     13288463.52
      2319628.00     13288391.82      2319551.89     13288204.56
      2319419.51     13288082.41      2319200.76     13288014.70
      2318825.46     13287820.23      2318435.76     13287751.25
      2318314.23     13287707.85      2318010.41     13287530.77
      2317911.45     13287431.81      2317869.79     13287332.85
      2317848.95     13287270.35      2317877.87     13287176.12

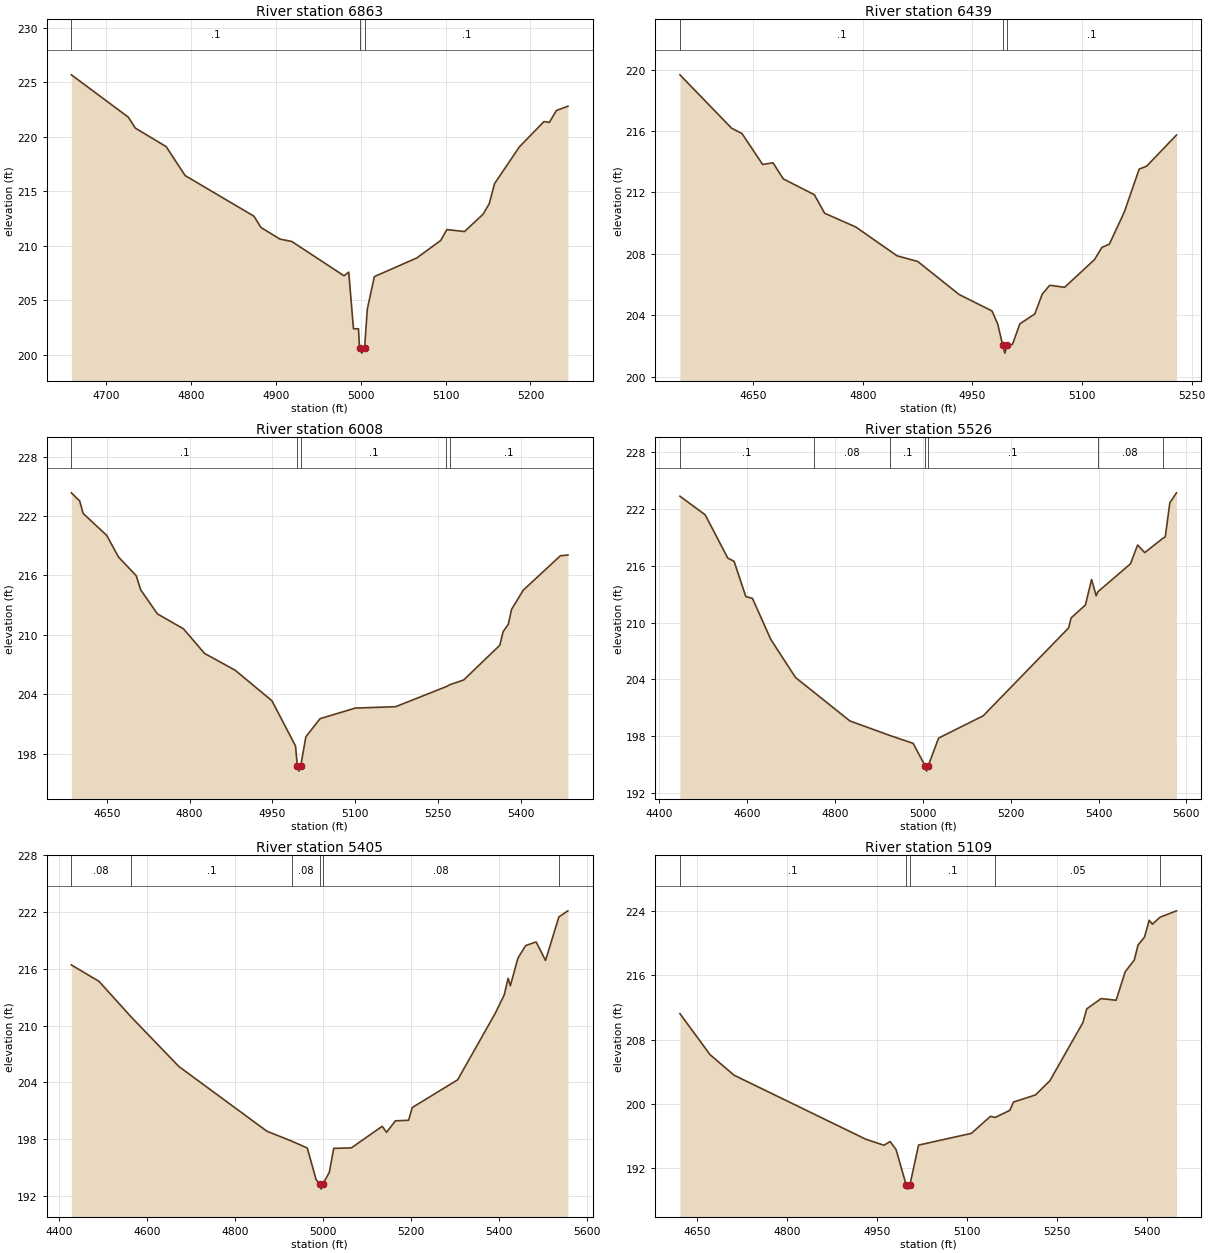
Type RM Length L Ch R = 1,6863,424,424,424
BEGIN DESCRIPTION:
UNT049 IN NURI 15.0
END DESCRIPTION:
XS GIS Cut Line= 3
      2323887.68     13289146.87      2323587.72     13289296.85
      2323387.70     13289446.87
#Sta/Elev= 30
  4658.8  225.67  4725.8  221.80  4734.2  220.79  4770.6  219.09  4792.9  216.44
  4874.0  212.72  4882.4  211.68  4904.7  210.62  4918.7  210.40  4980.2  207.26
  4985.8  207.59  4991.4  202.40  4997.3  202.40  4998.5  200.67  5001.2  200.17
  5004.5  200.67  5007.7  204.20  5016.0  207.18  5066.0  208.89  5094.2  210.49
  5101.5  211.49  5122.3  211.31  5144.2  212.90  5151.5  213.87  5157.7  215.70
  5186.9  219.06  5216.0  221.39  5222.3  221.31  5230.6  222.40  5244.2  222.79
#Mann=3,-1,0
  4658.8     0.1       0  4998.5    0.07       0  5004.5     0.1       0
Bank Sta=4998.5,5004.5
Exp/Cntr=0.3,0.1

Type RM Length L Ch R = 1,6439,431,431,431
BEGIN DESCRIPTION:
UNT049 IN NURI 14.0
END DESCRIPTION:
XS GIS Cut Line= 3
      2323637.71     13288646.86      2323337.72     13288946.85
      2323287.72     13289196.85
#Sta/Elev= 30
  4550.0  219.66  4620.7  216.18  4634.8  215.84  4663.1  213.82  4677.3  213.93
  4691.4  212.88  4733.8  211.85  4748.0  210.64  4790.4  209.75  4847.0  207.87
  4875.3  207.50  4931.8  205.35  4976.8  204.28  4984.5  203.45  4991.6  202.03
  4994.4  201.53  4997.6  202.03  5004.8  202.10  5015.0  203.44  5035.4  204.08
  5045.6  205.38  5055.8  205.95  5076.2  205.82  5117.0  207.62  5127.2  208.42
  5137.4  208.63  5157.8  210.72  5178.2  213.52  5188.4  213.71  5229.2  215.74
#Mann=3,-1,0
  4550.0     0.1       0  4991.6    0.07       0  4997.6     0.1       0
Bank Sta=4991.6,4997.6
Exp/Cntr=0.3,0.1

Type RM Length L Ch R = 1,6008,482,482,482
BEGIN DESCRIPTION:
UNT049 IN NURI 13.0
END DESCRIPTION:
XS GIS Cut Line= 3
      2322787.73     13288496.87      2322937.72     13288896.85
      2323187.73     13289296.87
#Sta/Elev= 30
  4586.0  224.35  4601.1  223.52  4607.3  222.27  4650.1  220.04  4671.4  217.86
  4703.5  215.97  4711.5  214.55  4741.7  212.12  4788.9  210.61  4827.2  208.12
  4882.4  206.43  4949.1  203.34  4991.8  198.77  4995.1  196.73  4997.8  196.23
  5001.1  196.73  5010.5  199.70  5036.2  201.53  5099.9  202.60  5173.0  202.74
  5265.1  204.78  5271.9  204.98  5296.2  205.44  5361.6  208.95  5367.5  210.31
  5377.0  211.07  5382.9  212.57  5404.1  214.52  5471.3  217.99  5484.9  218.07
#Mann=5,-1,0
  4586.0     0.1       0  4995.1    0.07       0  5001.1     0.1       0
  5265.1    0.16       0  5271.9     0.1       0
Bank Sta=4995.1,5001.1
Exp/Cntr=0.3,0.1

Type RM Length L Ch R = 1,5526,121,121,121
BEGIN DESCRIPTION:
UNT049 IN NURI 12.0
END DESCRIPTION:
XS GIS Cut Line= 3
      2322621.42     13288511.03      2322465.18     13289156.83
      2322604.08     13289601.30
#Sta/Elev= 30
  4447.3  223.31  4504.7  221.36  4556.2  216.79  4570.5  216.46  4597.3  212.73
  4612.3  212.55  4654.2  208.21  4710.5  204.20  4752.5  202.65  4834.0  199.63
  4925.6  198.09  4978.0  197.27  5005.9  194.84  5008.6  194.34  5011.9  194.84
  5035.9  197.82  5137.5  200.17  5331.8  209.43  5337.6  210.49  5370.1  211.85
  5384.2  214.54  5394.6  212.82  5398.7  213.25  5472.7  216.19  5488.9  218.17
  5505.2  217.37  5545.6  218.85  5551.8  219.02  5562.3  222.63  5577.4  223.67
#Mann=7,-1,0
  4447.3     0.1       0  4752.5    0.08       0  4925.6     0.1       0
  5005.9    0.07       0  5011.9     0.1       0  5398.7    0.08       0
  5545.6     0.1       0
Bank Sta=5005.9,5011.9
Exp/Cntr=0.3,0.1

Type RM Length L Ch R = 1,5405,296,296,296
BEGIN DESCRIPTION:
Mapping XS 2c0b00ec
END DESCRIPTION:
XS GIS Cut Line= 4
      2322487.50     13288484.04      2322374.66     13288974.48
      2322365.98     13289247.92      2322457.12     13289586.44
#Sta/Elev= 30
  4428.6  216.41  4491.2  214.68  4564.4  210.91  4672.8  205.67  4872.7  198.83
  4929.2  197.78  4964.2  197.06  4984.3  193.71  4993.1  193.21  4995.8  192.71
  4999.1  193.21  5014.3  194.49  5024.3  197.02  5064.3  197.07  5134.3  199.35
  5144.3  198.72  5164.3  199.93  5194.4  199.99  5202.4  201.33  5305.5  204.26
  5390.7  211.27  5411.4  213.24  5420.2  215.00  5425.3  214.21  5442.5  217.13
  5460.1  218.46  5483.9  218.84  5505.2  216.88  5535.5  221.49  5556.0  222.13
#Mann=6,-1,0
  4428.6    0.08       0  4564.4     0.1       0  4929.2    0.08       0
  4993.1    0.07       0  4999.1    0.08       0  5535.5     0.1       0
Bank Sta=4993.1,4999.1
Exp/Cntr=0.3,0.1

Type RM Length L Ch R = 1,5109,473,473,473
BEGIN DESCRIPTION:
UNT049 IN NURI 11.0
END DESCRIPTION:
XS GIS Cut Line= 3
      2322087.72     13288696.90      2322087.72     13289096.85
      2322237.73     13289496.89
#Sta/Elev= 30
  4621.4  211.24  4671.4  206.14  4711.4  203.57  4931.4  195.57  4961.4  194.83
  4971.4  195.30  4981.4  194.30  4998.4  189.86  5001.1  189.36  5004.4  189.86
  5018.9  194.85  5106.8  196.31  5138.8  198.44  5146.5  198.30  5170.9  199.18
  5177.1  200.22  5213.6  201.10  5237.6  202.87  5292.8  210.14  5299.0  211.83
  5323.1  213.12  5348.0  212.91  5363.1  216.45  5378.3  217.93  5384.5  219.79
  5395.2  220.77  5403.2  222.88  5408.5  222.39  5421.1  223.26  5448.6  224.06
#Mann=5,-1,0
  4621.4     0.1       0  4998.4    0.07       0  5004.4     0.1       0
  5146.5    0.05       0  5421.1    0.08       0
Bank Sta=4998.4,5004.4
Exp/Cntr=0.3,0.1

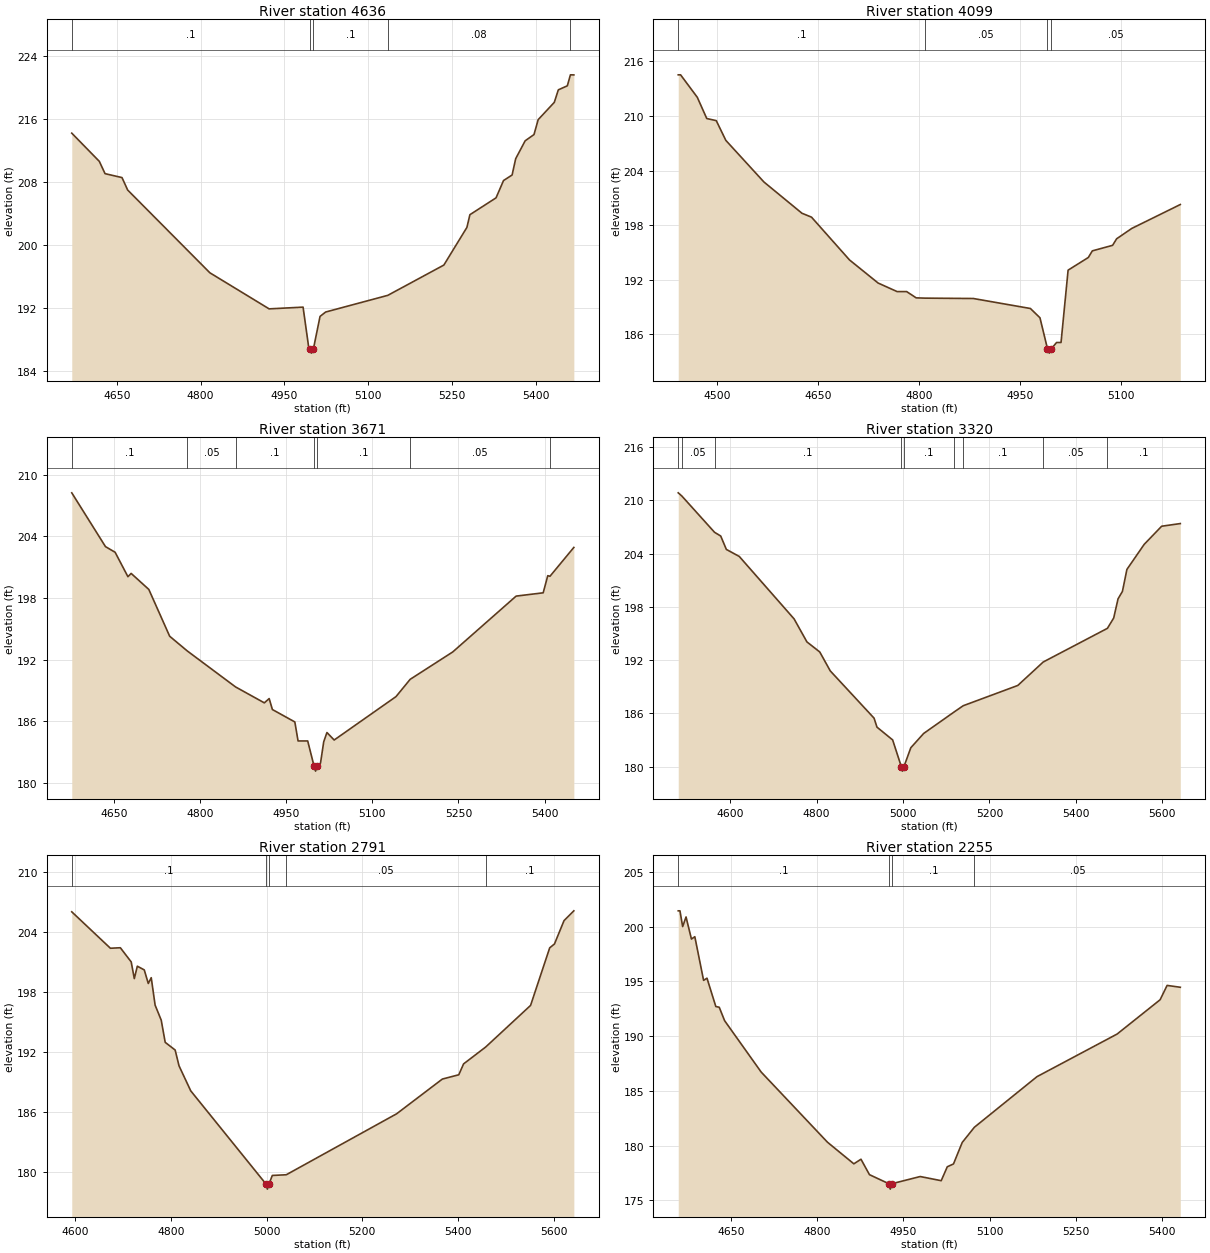
Type RM Length L Ch R = 1,4636,537,537,537
BEGIN DESCRIPTION:
UNT049 IN NURI 10.0
END DESCRIPTION:
XS GIS Cut Line= 3
      2321551.99     13288688.11      2321646.13     13289252.60
      2321777.51     13289552.28
#Sta/Elev= 30
  4569.1  214.24  4618.5  210.65  4628.7  209.09  4659.1  208.59  4669.2  207.01
  4816.5  196.48  4922.7  191.89  4983.5  192.11  4993.6  186.99  4995.9  186.76
  4998.6  186.26  5001.9  186.76  5013.9  190.93  5024.0  191.49  5135.3  193.61
  5235.7  197.46  5277.0  202.25  5282.4  203.87  5329.2  206.01  5342.6  208.21
  5358.0  208.92  5364.4  210.99  5381.4  213.27  5397.2  214.06  5404.7  215.96
  5433.6  218.16  5440.8  219.75  5456.9  220.26  5462.5  221.66  5468.6  221.65
#Mann=5,-1,0
  4569.1     0.1       0  4995.9    0.07       0  5001.9     0.1       0
  5135.3    0.08       0  5462.5     0.1       0
Bank Sta=4995.9,5001.9
Exp/Cntr=0.3,0.1

Type RM Length L Ch R = 1,4099,428,428,428
BEGIN DESCRIPTION:
UNT049 IN NURI 9.0
END DESCRIPTION:
XS GIS Cut Line= 3
      2321487.71     13288696.87      2321087.72     13289096.85
      2320937.76     13289196.83
#Sta/Elev= 30
  4442.5  214.53  4446.0  214.53  4470.8  212.06  4484.9  209.72  4499.0  209.49
  4513.2  207.32  4569.8  202.74  4626.3  199.30  4640.5  198.87  4697.0  194.16
  4739.5  191.62  4767.7  190.68  4781.9  190.68  4796.0  189.99  4809.3  189.96
  4880.9  189.92  4965.7  188.82  4979.9  187.80  4991.0  184.41  4993.8  183.91
  4997.0  184.41  5004.6  185.08  5011.2  185.08  5021.7  193.04  5051.7  194.43
  5057.7  195.16  5087.8  195.77  5093.8  196.49  5116.3  197.63  5188.4  200.26
#Mann=4,-1,0
  4442.5     0.1       0  4809.3    0.05       0  4991.0    0.03       0
  4997.0    0.05       0
Bank Sta=4991,4997
Exp/Cntr=0.3,0.1

Type RM Length L Ch R = 1,3671,351,351,351
BEGIN DESCRIPTION:
UNT049 IN NURI 8.0
END DESCRIPTION:
XS GIS Cut Line= 3
      2321237.73     13288546.85      2320837.72     13288746.85
      2320687.73     13289146.84
#Sta/Elev= 30
  4576.5  208.24  4635.2  203.00  4652.0  202.45  4674.3  200.07  4679.9  200.39
  4710.7  198.83  4747.0  194.27  4777.6  192.84  4861.8  189.33  4911.9  187.78
  4920.3  188.20  4925.9  187.13  4965.0  185.92  4970.6  184.07  4987.4  184.07
  4998.4  181.63  5001.1  181.13  5004.4  181.63  5009.7  181.91  5015.3  183.99
  5020.9  184.89  5033.5  184.16  5141.2  188.39  5165.8  190.07  5240.0  192.74
  5350.4  198.18  5397.5  198.50  5405.5  200.17  5409.3  200.11  5450.9  202.92
#Mann=7,-1,0
  4576.5     0.1       0  4777.6    0.05       0  4861.8     0.1       0
  4998.4    0.07       0  5004.4     0.1       0  5165.8    0.05       0
  5409.3     0.1       0
Bank Sta=4998.4,5004.4
Exp/Cntr=0.3,0.1

Type RM Length L Ch R = 1,3320,529,529,529
BEGIN DESCRIPTION:
UNT049 IN NURI 7.0
END DESCRIPTION:
XS GIS Cut Line= 3
      2320732.67     13288125.48      2320447.82     13288844.33
      2320499.90     13289229.69
#Sta/Elev= 30
  4479.6  210.83  4488.0  210.47  4563.6  206.39  4577.9  205.97  4591.0  204.46
  4620.9  203.67  4747.8  196.64  4777.5  194.05  4807.2  192.92  4831.5  190.79
  4932.9  185.47  4939.6  184.46  4975.9  183.02  4996.0  180.01  4998.7  179.51
  5002.0  180.01  5017.9  182.14  5047.7  183.75  5118.0  186.16  5139.2  186.87
  5265.5  189.15  5324.4  191.79  5473.0  195.58  5487.5  196.74  5497.6  198.90
  5507.7  199.73  5518.1  202.21  5558.1  205.03  5598.5  207.07  5641.7  207.37
#Mann=9,-1,0
  4479.6     0.1       0  4488.0    0.05       0  4563.6     0.1       0
  4996.0    0.07       0  5002.0     0.1       0  5118.0    0.05       0
  5139.2     0.1       0  5324.4    0.05       0  5473.0     0.1       0
Bank Sta=4996,5002
Exp/Cntr=0.3,0.1

Type RM Length L Ch R = 1,2791,536,536,536
BEGIN DESCRIPTION:
UNT049 IN NURI 6.0
END DESCRIPTION:
XS GIS Cut Line= 3
      2320201.30     13288087.36      2320051.58     13288287.22
      2320038.10     13289087.38
#Sta/Elev= 30
  4592.3  206.03  4673.1  202.38  4693.9  202.43  4716.6  201.01  4723.1  199.34
  4729.4  200.58  4743.9  200.21  4752.3  198.85  4758.5  199.43  4766.6  196.68
  4779.4  195.17  4787.7  192.95  4808.5  192.18  4816.6  190.60  4841.1  188.09
  4998.7  178.74  5001.4  178.24  5004.7  178.74  5011.7  179.61  5040.9  179.68
  5271.7  185.79  5367.3  189.27  5401.7  189.70  5411.7  190.79  5457.9  192.48
  5551.8  196.65  5591.8  202.42  5601.8  202.81  5621.8  205.15  5642.3  206.13
#Mann=5,-1,0
  4592.3     0.1       0  4998.7    0.07       0  5004.7     0.1       0
  5040.9    0.05       0  5457.9     0.1       0
Bank Sta=4998.7,5004.7
Exp/Cntr=0.3,0.1

Type RM Length L Ch R = 1,2255,447,447,447
BEGIN DESCRIPTION:
UNT049 IN NURI 5.0
END DESCRIPTION:
XS GIS Cut Line= 3
      2319837.73     13287946.83      2319587.72     13288346.85
      2319387.74     13288696.82
#Sta/Elev= 30
  4557.6  201.44  4560.6  201.44  4565.3  200.00  4571.2  200.88  4580.6  198.86
  4586.5  199.08  4601.8  195.09  4607.7  195.29  4623.1  192.70  4629.0  192.64
  4638.4  191.41  4702.1  186.72  4817.7  180.31  4863.6  178.34  4876.0  178.76
  4890.8  177.35  4924.3  176.53  4927.1  176.03  4930.3  176.53  4979.2  177.18
  5015.8  176.80  5026.4  178.07  5037.2  178.33  5052.4  180.29  5073.6  181.68
  5182.7  186.30  5322.3  190.19  5397.2  193.32  5409.4  194.63  5432.4  194.46
#Mann=4,-1,0
  4557.6     0.1       0  4924.3    0.07       0  4930.3     0.1       0
  5073.6    0.05       0
Bank Sta=4924.3,4930.3
Exp/Cntr=0.3,0.1

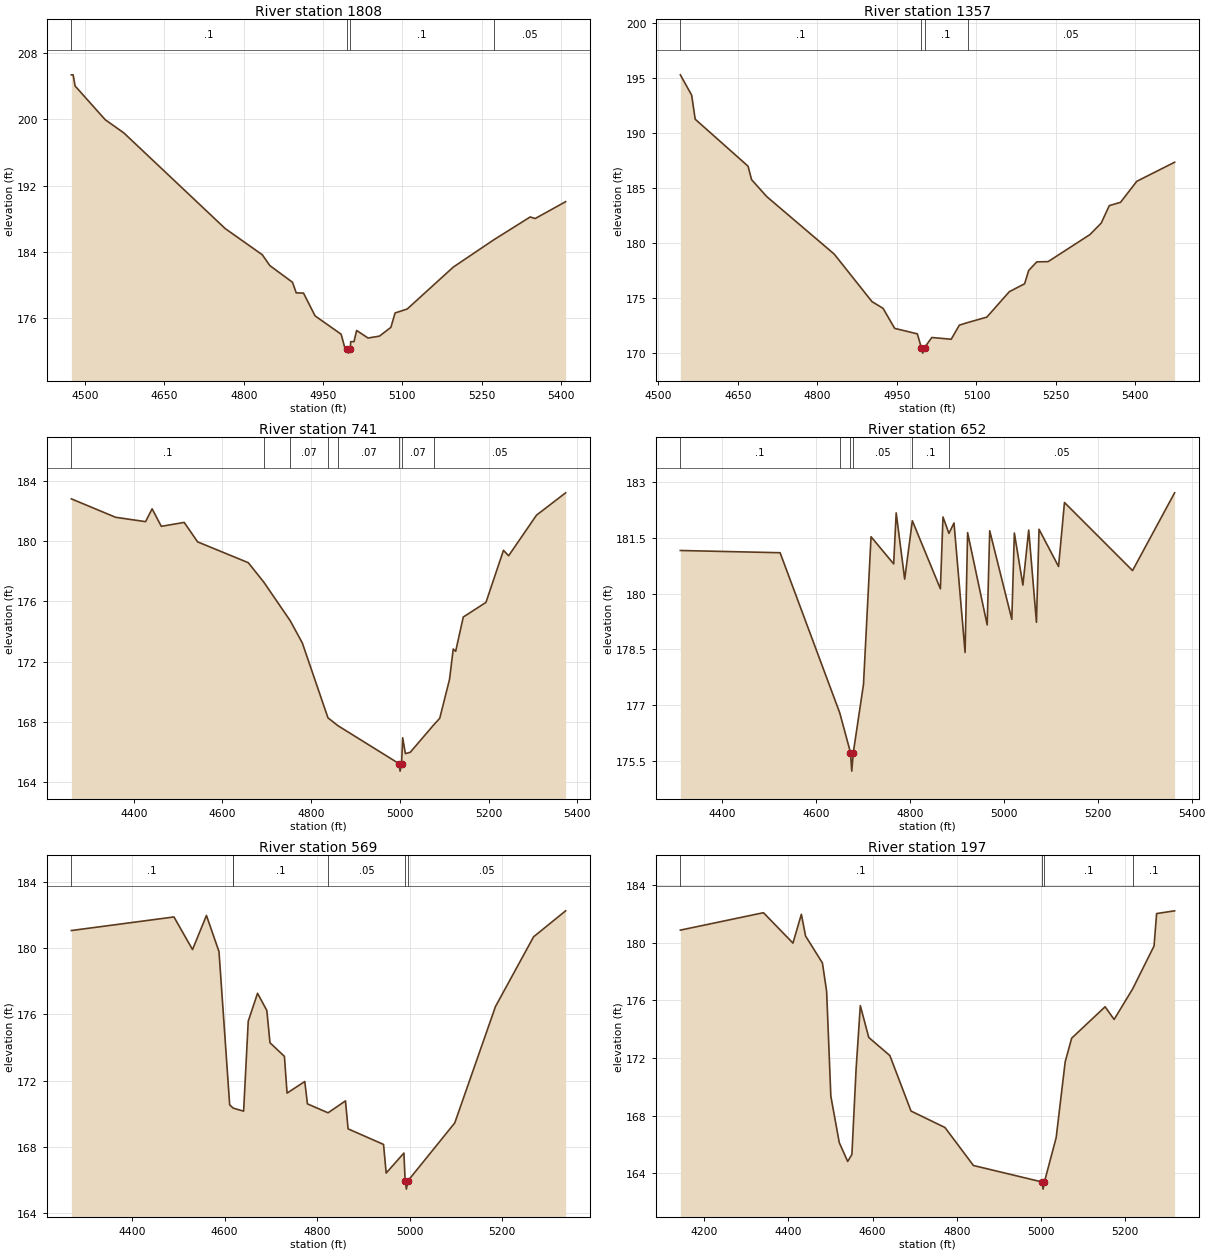
Type RM Length L Ch R = 1,1808,451,451,451
BEGIN DESCRIPTION:
UNT049 IN NURI 4.0
END DESCRIPTION:
XS GIS Cut Line= 3
      2319637.70     13287646.88      2319287.72     13288046.85
      2319087.72     13288396.86
#Sta/Elev= 30
  4474.0  205.36  4477.3  205.36  4481.1  204.01  4538.0  199.95  4573.2  198.36
  4764.9  186.83  4835.1  183.67  4849.3  182.37  4892.1  180.36  4899.2  179.08
  4912.9  179.06  4934.8  176.31  4984.1  174.10  4991.7  172.32  4995.4  172.32
  4998.1  171.82  5001.4  172.32  5002.2  173.20  5008.4  173.20  5013.4  174.55
  5035.0  173.64  5056.6  173.87  5078.2  174.93  5086.1  176.66  5109.1  177.14
  5196.2  182.19  5272.3  185.46  5341.6  188.23  5351.0  188.04  5408.6  190.07
#Mann=4,-1,0
  4474.0     0.1       0  4995.4    0.07       0  5001.4     0.1       0
  5272.3    0.05       0
Bank Sta=4995.4,5001.4
Exp/Cntr=0.3,0.1

Type RM Length L Ch R = 1,1357,616,616,616
BEGIN DESCRIPTION:
UNT049 IN NURI 3.0
END DESCRIPTION:
XS GIS Cut Line= 3
      2319237.70     13287546.87      2318887.72     13287846.85
      2318637.75     13288246.81
#Sta/Elev= 30
  4541.3  195.28  4562.7  193.43  4569.3  191.25  4669.1  186.98  4675.7  185.76
  4704.3  184.22  4831.6  179.00  4902.9  174.68  4923.8  174.07  4945.7  172.25
  4988.5  171.75  4996.0  170.50  4998.7  170.00  5002.0  170.50  5015.8  171.42
  5052.4  171.26  5067.7  172.54  5083.7  172.78  5119.6  173.27  5162.0  175.58
  5190.9  176.30  5198.6  177.51  5213.9  178.29  5235.2  178.31  5314.2  180.77
  5335.4  181.81  5350.7  183.40  5371.9  183.70  5402.6  185.61  5473.9  187.34
#Mann=4,-1,0
  4541.3     0.1       0  4996.0    0.07       0  5002.0     0.1       0
  5083.7    0.05       0
Bank Sta=4996,5002
Exp/Cntr=0.3,0.1

Type RM Length L Ch R = 1,741,89,89,89
BEGIN DESCRIPTION:
UNT049 IN NURI 2.0
END DESCRIPTION:
XS GIS Cut Line= 4
      2318855.44     13287326.27      2318744.29     13287348.35
      2318420.04     13287431.13      2318135.71     13288033.53
#Sta/Elev= 30
  4259.4  182.79  4359.0  181.57  4426.6  181.28  4441.4  182.13  4462.1  180.97
  4513.7  181.23  4544.0  179.94  4658.2  178.56  4693.2  177.27  4752.6  174.72
  4780.0  173.24  4837.8  168.28  4860.3  167.76  4997.7  165.25  5000.4  164.75
  5003.7  165.25  5006.2  166.96  5012.3  165.91  5023.3  166.00  5075.7  167.80
  5089.7  168.25  5111.8  170.83  5120.1  172.84  5125.6  172.69  5142.8  174.96
  5193.9  175.93  5233.4  179.38  5245.0  179.02  5307.8  181.71  5373.5  183.19
#Mann=8,-1,0
  4259.4     0.1       0  4693.2    0.05       0  4752.6    0.07       0
  4837.8     0.1       0  4860.3    0.07       0  4997.7    0.07       0
  5003.7    0.07       0  5075.7    0.05       0
Bank Sta=4997.7,5003.7
Exp/Cntr=0.3,0.1

Type RM Length L Ch R = 1,652,83,83,83
BEGIN DESCRIPTION:
Mapping XS 9bfd00a9
END DESCRIPTION:
XS GIS Cut Line= 3
      2318736.06     13287314.69      2318328.07     13287397.15
      2318076.60     13287982.48
#Sta/Elev= 30
  4310.4  181.16  4523.0  181.10  4650.0  176.80  4673.0  175.73  4675.7  175.23
  4679.0  175.73  4700.7  177.56  4716.8  181.53  4765.0  180.80  4770.4  182.17
  4788.5  180.39  4804.8  181.96  4864.6  180.13  4870.1  182.06  4882.8  181.62
  4893.6  181.90  4917.2  178.42  4922.6  181.64  4964.3  179.16  4969.7  181.69
  5016.8  179.31  5022.2  181.63  5040.4  180.23  5052.8  181.71  5069.3  179.23
  5074.8  181.73  5116.4  180.73  5129.0  182.45  5274.1  180.62  5363.7  182.71
#Mann=6,-1,0
  4310.4     0.1       0  4650.0    0.05       0  4673.0    0.03       0
  4679.0    0.05       0  4804.8     0.1       0  4882.8    0.05       0
Bank Sta=4673,4679
Exp/Cntr=0.3,0.1

Type RM Length L Ch R = 1,569,372,372,372
BEGIN DESCRIPTION:
Mapping XS 658d7db3
END DESCRIPTION:
XS GIS Cut Line= 3
      2318718.71     13287306.00      2318289.01     13287340.73
      2317990.37     13287903.39
#Sta/Elev= 30
  4269.1  181.06  4490.8  181.88  4530.9  179.91  4561.0  181.97  4588.1  179.79
  4611.2  170.53  4617.8  170.36  4618.9  170.33  4641.3  170.15  4651.3  175.58
  4671.4  177.27  4691.5  176.23  4698.3  174.28  4729.5  173.46  4735.2  171.24
  4773.5  171.94  4779.2  170.59  4823.8  170.05  4861.4  170.77  4867.1  169.08
  4943.7  168.14  4949.4  166.41  4987.7  167.62  4990.4  165.94  4993.1  165.44
  4996.4  165.94  5097.6  169.44  5185.6  176.47  5267.9  180.68  5337.2  182.25
#Mann=6,-1,0
  4269.1     0.1       0  4617.8    0.05       0  4618.9     0.1       0
  4823.8    0.05       0  4990.4    0.03       0  4996.4    0.05       0
Bank Sta=4990.4,4996.4
Exp/Cntr=0.3,0.1

Type RM Length L Ch R = 1,197,0,0,0
BEGIN DESCRIPTION:
UNT049 IN NURI 1.0
END DESCRIPTION:
XS GIS Cut Line= 4
      2318715.15     13287288.77      2318239.49     13287288.77
      2317906.15     13287323.49      2317717.22     13287633.32
#Sta/Elev= 30
  4143.4  180.88  4340.8  182.09  4410.8  179.98  4430.8  181.98  4440.8  180.47
  4480.8  178.60  4490.8  176.62  4500.8  169.35  4520.8  166.13  4540.8  164.82
  4550.8  165.31  4560.8  171.25  4570.8  175.64  4590.8  173.43  4641.0  172.17
  4691.2  168.32  4771.7  167.18  4839.4  164.54  5002.0  163.40  5004.8  162.90
  5008.0  163.40  5035.9  166.48  5057.3  171.74  5072.7  173.38  5152.1  175.56
  5173.5  174.68  5217.5  176.80  5268.3  179.78  5274.4  182.03  5317.1  182.22
#Mann=4,-1,0
  4143.4     0.1       0  5002.0    0.07       0  5008.0     0.1       0
  5217.5     0.1       0
Bank Sta=5002,5008
Exp/Cntr=0.3,0.1

Chan Stop Cuts=-1