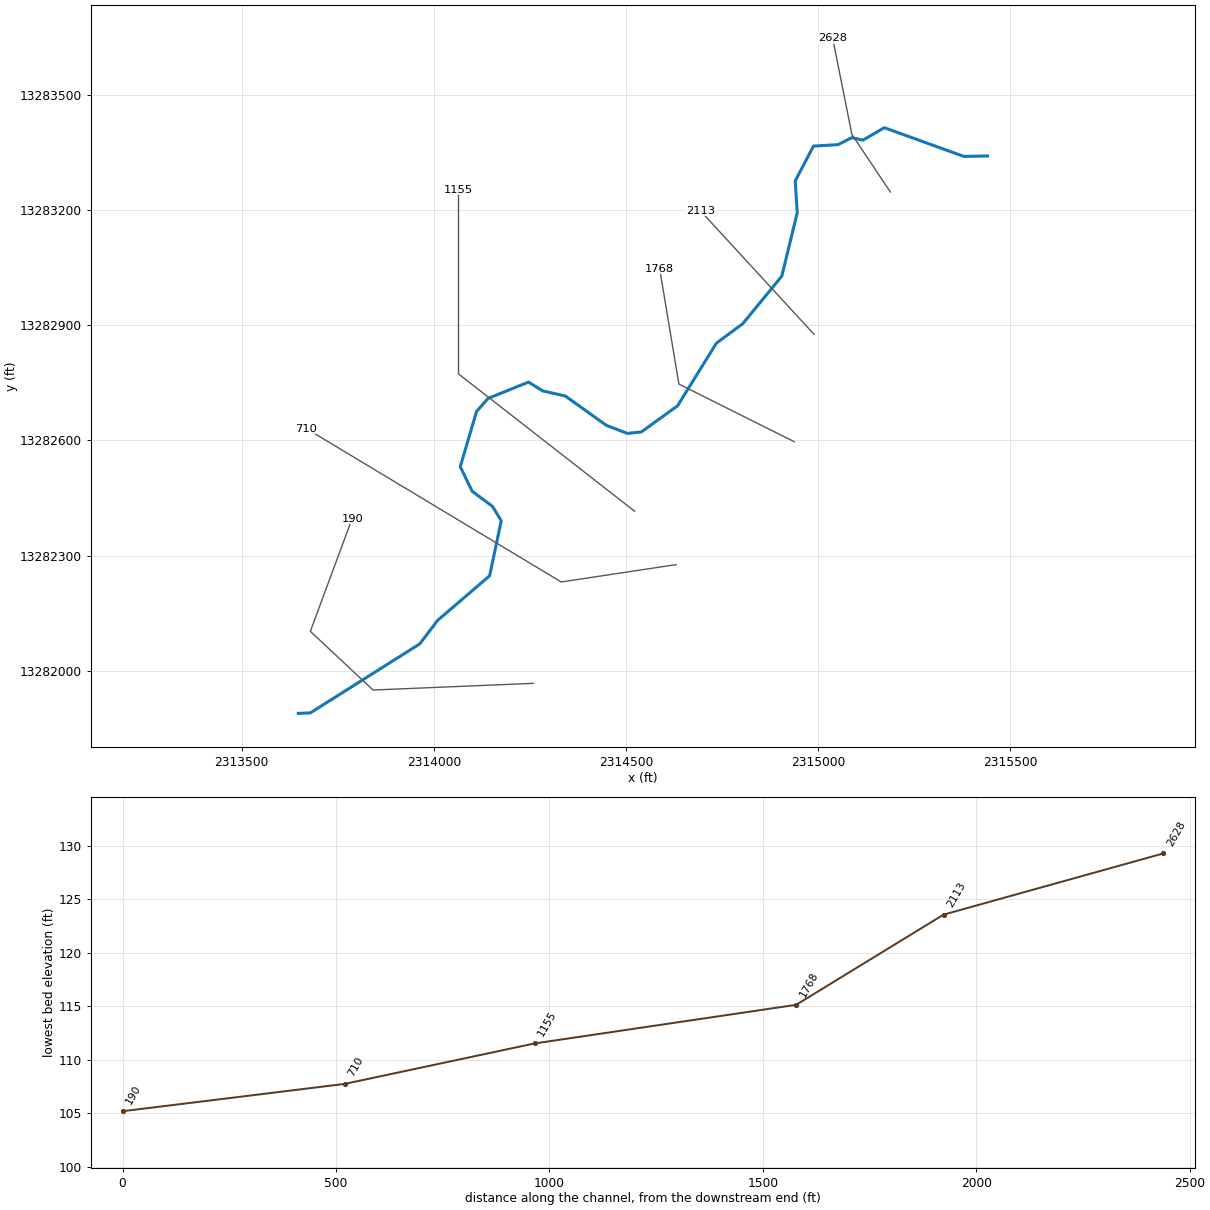
--- UNT050 IN NURI.prj (project) ---

Proj Title=UNT050 IN NURI Base Level Engineering
Current Plan=p01
Default Exp/Contr=0.3,0.1
English Units
Geom File=g01
Flow File=f01
Plan File=p01
BEGIN DESCRIPTION:
UNT050 IN NURI
END DESCRIPTION:

--- UNT050 IN NURI.p01 (plan) ---

Plan Title=Multiple Run
Short Identifier=Multiple
Geom File=g01
Flow File=f01
Subcritical Flow
K Sum by GR= 0
Std Step Tol= 0.01
Critical Tol= 0.01
Num of Std Step Trials= 20
Max Error Tol= 0.3
Flow Tol Ratio= 0.001
Split Flow NTrial= 30
Split Flow Tol= 0.02
Split Flow Ratio= 0.02
Log Output Level= 0
Friction Slope Method= 1
Unsteady Friction Slope Method= 2
Unsteady Bridges Friction Slope Method= 1
Parabolic Critical Depth
Global Vel Dist=  1 , 1 , 1
Global Log Level= 0
CheckData=True
Encroach Param= -1, 0, 0, 0
BEGIN DESCRIPTION:
Multiple Run
END DESCRIPTION:

--- UNT050 IN NURI.f01 (steady flow) ---

Flow Title=Multiple
Number of Profiles=7
Profile Names=10-year,25-year,50-year,1pct_min,100-year,1pct_plu,500-year
River Rch & RM= UNT050 IN NURI,Reach-1,2628
     634     901    1127    1030    1393    1884    2136
River Rch & RM= UNT050 IN NURI,Reach-1,1768
     690     985    1235    1132    1531    2070    2358
Boundary for River Rch & Prof#=UNT050 IN NURI,Reach-1,1
Up Type=0
Dn Type=3
Dn Slope=0.005
Boundary for River Rch & Prof#=UNT050 IN NURI,Reach-1,2
Up Type=0
Dn Type=3
Dn Slope=0.005
Boundary for River Rch & Prof#=UNT050 IN NURI,Reach-1,3
Up Type=0
Dn Type=3
Dn Slope=0.005
Boundary for River Rch & Prof#=UNT050 IN NURI,Reach-1,4
Up Type=0
Dn Type=3
Dn Slope=0.005
Boundary for River Rch & Prof#=UNT050 IN NURI,Reach-1,5
Up Type=0
Dn Type=3
Dn Slope=0.005
Boundary for River Rch & Prof#=UNT050 IN NURI,Reach-1,6
Up Type=0
Dn Type=3
Dn Slope=0.005
Boundary for River Rch & Prof#=UNT050 IN NURI,Reach-1,7
Up Type=0
Dn Type=3
Dn Slope=0.005

--- UNT050 IN NURI.g01 (geometry) ---

Geom Title=Existing Conditions

River Reach=UNT050 IN NURI,Reach-1
Reach XY= 30
      2315440.78     13283340.57      2315378.99     13283339.46
      2315172.07     13283414.19      2315116.57     13283381.83
      2315087.19     13283388.30      2315051.80     13283370.11
      2314987.86     13283366.34      2314940.37     13283275.67
      2314945.55     13283192.59      2314905.44     13283027.80
      2314803.82     13282903.97      2314735.30     13282853.30
      2314634.23     13282690.21      2314540.01     13282622.17
      2314503.67     13282618.33      2314448.83     13282639.42
      2314342.29     13282715.73      2314283.53     13282729.04
      2314246.48     13282751.97      2314141.17     13282709.43
      2314111.33     13282675.53      2314068.96     13282531.73
      2314099.88     13282467.82      2314152.68     13282428.44
      2314175.58     13282391.21      2314145.37     13282247.77
      2314010.33     13282131.95      2313963.48     13282070.44
      2313678.76     13281890.76      2313647.62     13281889.61

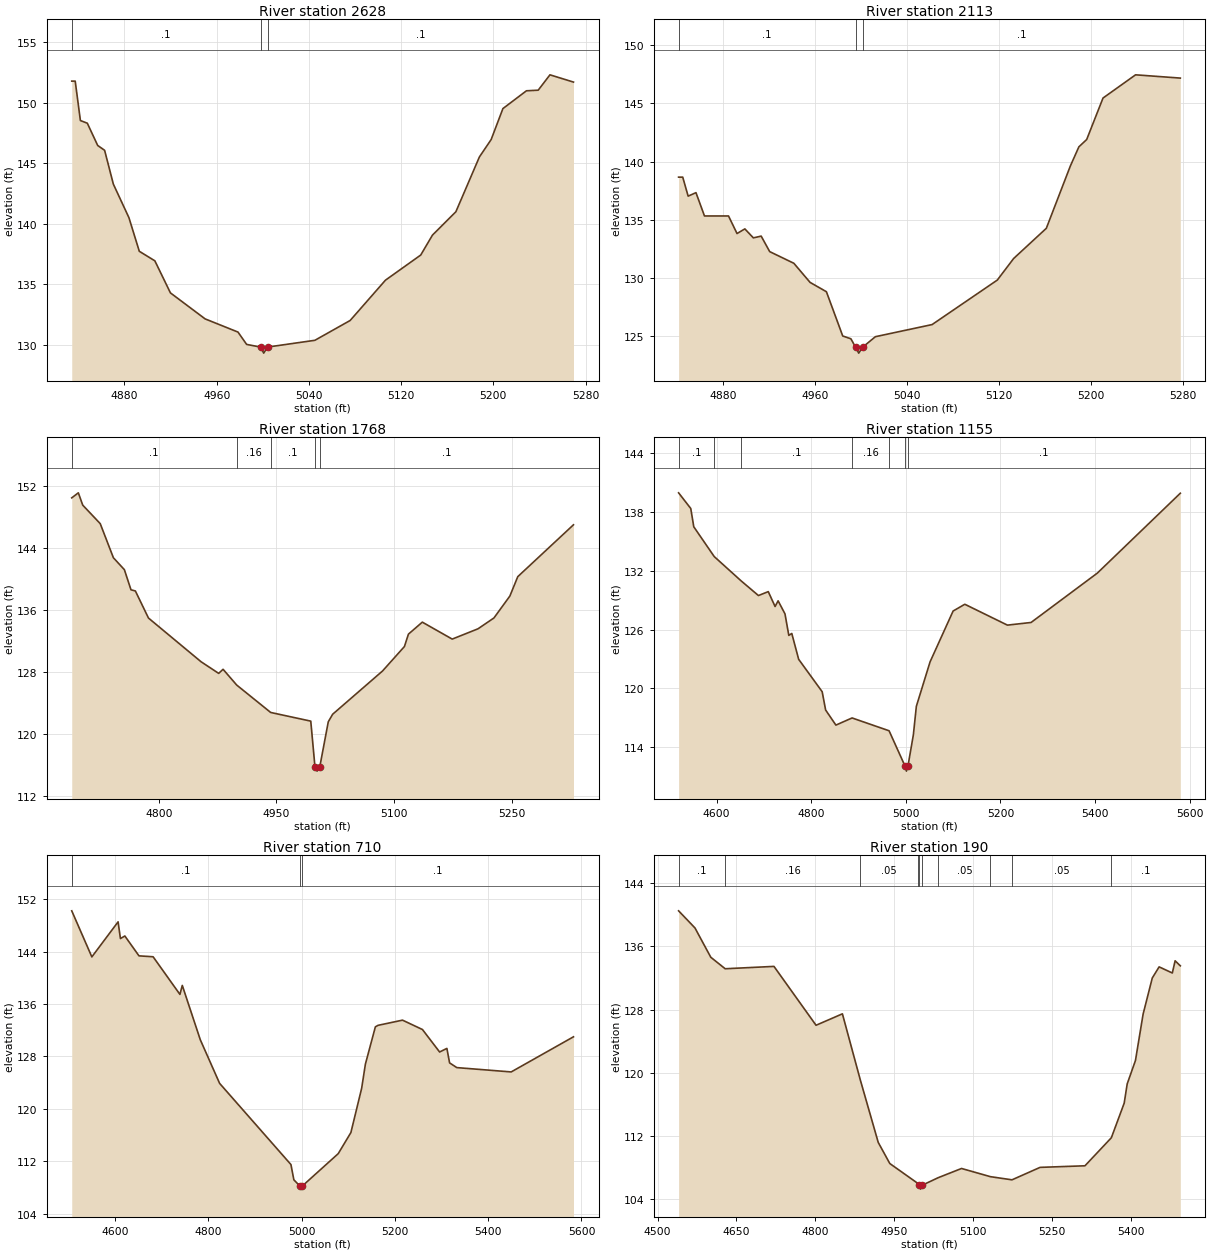
Type RM Length L Ch R = 1,2628,515,515,515
BEGIN DESCRIPTION:
UNT050 IN NURI 6.0
END DESCRIPTION:
XS GIS Cut Line= 3
      2315187.72     13283246.86      2315087.72     13283396.85
      2315037.73     13283646.83
#Sta/Elev= 30
  4834.3  151.78  4837.3  151.78  4841.8  148.52  4847.8  148.30  4856.8  146.46
  4862.8  146.06  4870.4  143.26  4883.9  140.49  4892.9  137.71  4906.4  136.92
  4919.9  134.27  4950.0  132.12  4978.5  131.03  4986.0  130.01  4998.1  129.79
  5000.8  129.29  5004.1  129.79  5045.2  130.35  5075.8  131.99  5106.4  135.32
  5137.0  137.40  5147.2  139.05  5167.5  140.98  5187.9  145.51  5198.1  146.95
  5208.3  149.51  5228.7  150.98  5238.9  151.03  5249.1  152.30  5269.5  151.70
#Mann=3,-1,0
  4834.3     0.1       0  4998.1    0.07       0  5004.1     0.1       0
Bank Sta=4998.1,5004.1
Exp/Cntr=0.3,0.1

Type RM Length L Ch R = 1,2113,345,345,345
BEGIN DESCRIPTION:
UNT050 IN NURI 5.0
END DESCRIPTION:
XS GIS Cut Line= 2
      2314989.05     13282876.53      2314693.90     13283197.72
#Sta/Elev= 30
  4841.6  138.67  4845.2  138.67  4849.9  137.04  4856.7  137.34  4864.1  135.34
  4885.0  135.34  4892.4  133.83  4899.2  134.23  4906.6  133.46  4913.4  133.61
  4920.8  132.28  4941.8  131.28  4955.9  129.64  4970.1  128.84  4984.3  125.04
  4991.4  124.80  4995.5  124.07  4998.2  123.57  5001.5  124.07  5012.7  124.98
  5062.0  126.02  5118.7  129.84  5132.9  131.69  5161.3  134.28  5182.2  139.63
  5189.6  141.27  5196.4  141.90  5210.6  145.46  5238.9  147.45  5277.8  147.17
#Mann=3,-1,0
  4841.6     0.1       0  4995.5    0.07       0  5001.5     0.1       0
Bank Sta=4995.5,5001.5
Exp/Cntr=0.3,0.1

Type RM Length L Ch R = 1,1768,613,613,613
BEGIN DESCRIPTION:
UNT050 IN NURI 4.0
END DESCRIPTION:
XS GIS Cut Line= 3
      2314937.73     13282596.85      2314637.72     13282746.85
      2314587.71     13283046.90
#Sta/Elev= 30
  4689.0  150.46  4697.4  151.11  4703.0  149.52  4725.3  147.13  4742.1  142.72
  4756.1  141.18  4764.5  138.58  4770.1  138.43  4786.8  134.93  4853.9  129.28
  4876.3  127.78  4881.9  128.31  4899.3  126.27  4942.6  122.73  4993.7  121.61
  4999.1  115.65  5001.8  115.15  5005.1  115.65  5016.0  121.52  5021.6  122.50
  5085.2  128.09  5113.1  131.25  5118.2  132.85  5135.9  134.40  5174.0  132.21
  5206.9  133.54  5227.2  134.94  5247.5  137.77  5257.6  140.28  5328.6  146.98
#Mann=5,-1,0
  4689.0     0.1       0  4899.3    0.16       0  4942.6     0.1       0
  4999.1    0.07       0  5005.1     0.1       0
Bank Sta=4999.1,5005.1
Exp/Cntr=0.3,0.1

Type RM Length L Ch R = 1,1155,445,445,445
BEGIN DESCRIPTION:
UNT050 IN NURI 3.0
END DESCRIPTION:
XS GIS Cut Line= 3
      2314522.64     13282415.72      2314064.34     13282773.33
      2314064.34     13283252.22
#Sta/Elev= 30
  4519.9  139.96  4545.6  138.36  4552.0  136.49  4595.2  133.45  4652.0  130.97
  4688.6  129.47  4709.4  129.87  4723.8  128.35  4730.2  128.93  4744.7  127.60
  4752.8  125.40  4759.1  125.60  4773.6  122.96  4823.3  119.65  4830.6  117.78
  4852.3  116.24  4886.5  116.97  4964.7  115.66  4998.5  112.04  5001.3  111.54
  5004.5  112.04  5016.0  115.25  5022.3  118.16  5051.3  122.70  5100.0  127.89
  5124.7  128.58  5214.7  126.45  5264.7  126.72  5404.7  131.76  5580.1  139.92
#Mann=7,-1,0
  4519.9     0.1       0  4595.2    0.16       0  4652.0     0.1       0
  4886.5    0.16       0  4964.7     0.1       0  4998.5    0.07       0
  5004.5     0.1       0
Bank Sta=4998.5,5004.5
Exp/Cntr=0.3,0.1

Type RM Length L Ch R = 1,710,520,520,520
BEGIN DESCRIPTION:
UNT050 IN NURI 2.0
END DESCRIPTION:
XS GIS Cut Line= 3
      2314630.31     13282276.81      2314331.70     13282231.67
      2313668.53     13282630.96
#Sta/Elev= 30
  4506.8  150.22  4549.9  143.19  4606.2  148.54  4611.2  145.99  4620.7  146.38
  4651.0  143.35  4681.3  143.21  4738.8  137.47  4743.9  138.84  4782.5  130.55
  4823.9  123.90  4976.9  111.51  4983.2  109.18  4995.7  108.26  4998.5  107.76
  5001.7  108.26  5078.3  113.17  5105.5  116.39  5128.6  123.15  5136.6  126.83
  5158.0  132.52  5163.8  132.75  5216.2  133.54  5259.0  132.11  5295.8  128.68
  5311.4  129.23  5317.2  127.02  5332.7  126.30  5449.3  125.64  5582.9  131.00
#Mann=3,-1,0
  4506.8     0.1       0  4995.7    0.07       0  5001.7     0.1       0
Bank Sta=4995.7,5001.7
Exp/Cntr=0.3,0.1

Type RM Length L Ch R = 1,190,0,0,0
BEGIN DESCRIPTION:
UNT050 IN NURI 1.0
END DESCRIPTION:
XS GIS Cut Line= 4
      2314258.83     13281967.78      2313842.12     13281950.42
      2313678.92     13282103.20      2313787.72     13282396.87
#Sta/Elev= 30
  4540.0  140.52  4571.1  138.35  4601.2  134.63  4628.6  133.17  4721.3  133.47
  4801.3  126.00  4851.4  127.45  4885.5  119.05  4919.5  111.14  4941.5  108.46
  4994.5  105.95  4997.2  105.71  5000.0  105.21  5003.2  105.71  5033.8  106.67
  5077.9  107.83  5132.8  106.79  5173.8  106.39  5227.2  107.97  5312.5  108.17
  5362.7  111.73  5387.1  116.12  5392.8  118.56  5408.5  121.53  5423.1  127.43
  5440.5  132.00  5453.5  133.41  5478.6  132.63  5483.9  134.18  5493.8  133.54
#Mann=10,-1,0
  4540.0     0.1       0  4628.6    0.16       0  4885.5    0.05       0
  4994.5     0.1       0  4997.2    0.07       0  5003.2     0.1       0
  5033.8    0.05       0  5132.8     0.1       0  5173.8    0.05       0
  5362.7     0.1       0
Bank Sta=4997.2,5003.2
Exp/Cntr=0.3,0.1

Chan Stop Cuts=-1