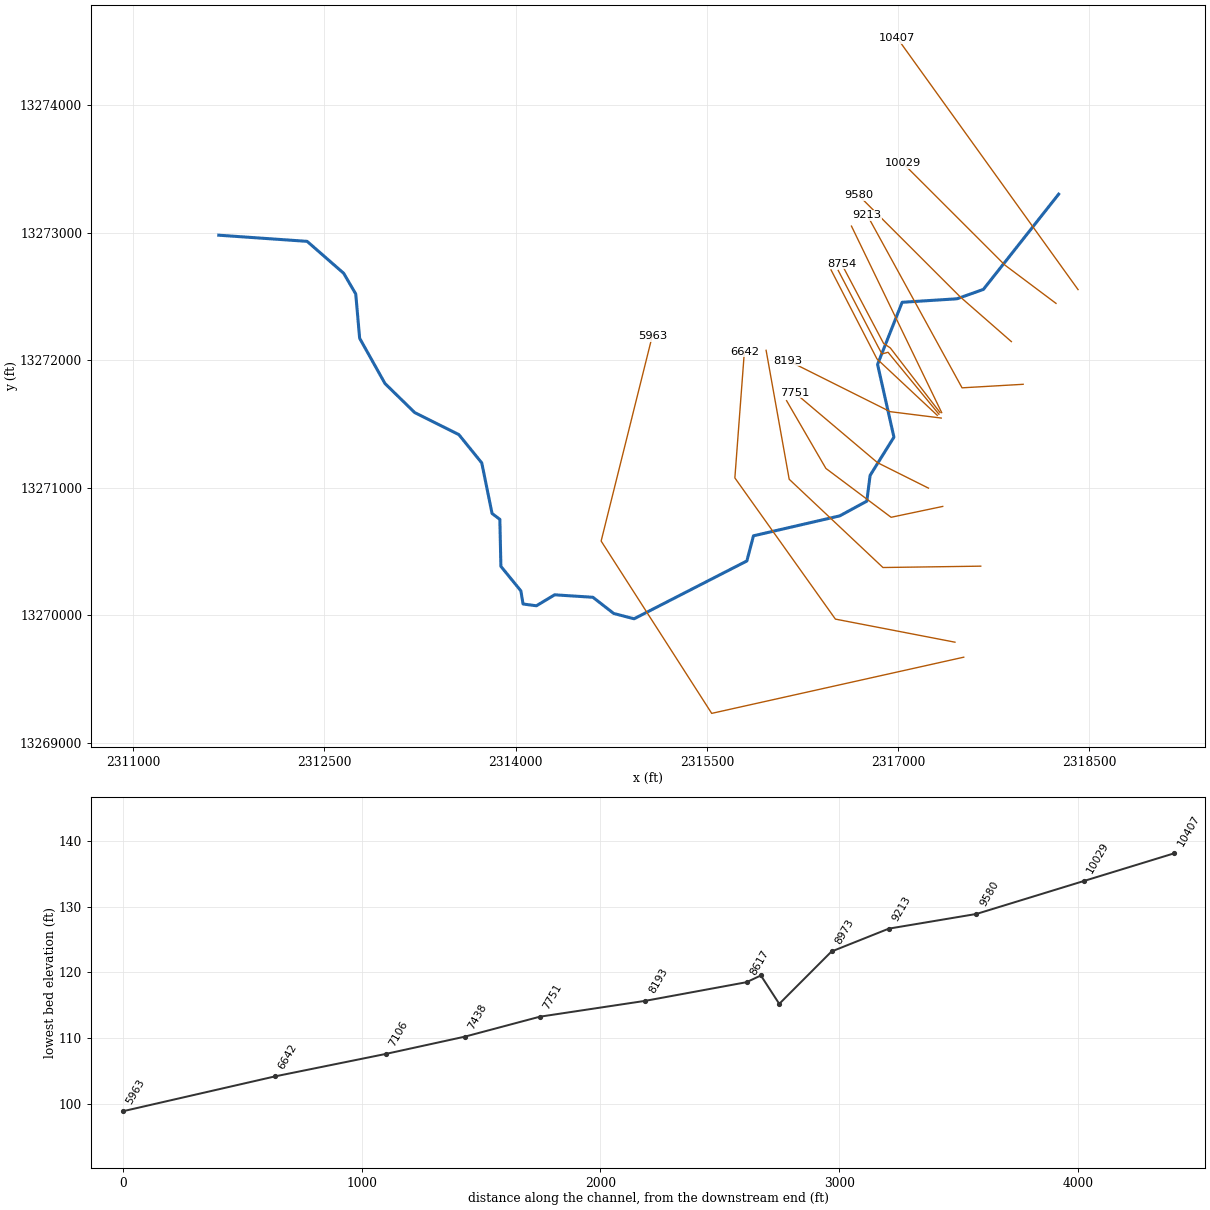
--- UNT051 IN NURI.prj (project) ---

Proj Title=UNT051 IN NURI Base Level Engineering
Current Plan=p01
Default Exp/Contr=0.3,0.1
English Units
Geom File=g01
Flow File=f01
Plan File=p01
Y Axis Title=Elevation
X Axis Title(PF)=Main Channel Distance
X Axis Title(XS)=Station
BEGIN DESCRIPTION:
UNT051 IN NURI
END DESCRIPTION:
DSS File=dss
DSS Export Rating Curves= 0
DSS Export Rating Curve Sorted= 0
DSS Export Volume Flow Curves= 0
DXF OffsetX= 0
DXF OffsetY= 0
DXF ScaleX= 1
DXF ScaleY= 10

--- UNT051 IN NURI.p01 (plan) ---

Plan Title=Multiple Run
Program Version=4.10
Short Identifier=Multiple Run
Geom File=g01
Flow File=f01
Subcritical Flow
K Sum by GR= 0
Std Step Tol= 0.01
Critical Tol= 0.01
Num of Std Step Trials= 20
Max Error Tol= 0.3
Flow Tol Ratio= 0.001
Split Flow NTrial= 30
Split Flow Tol= 0.02
Split Flow Ratio= 0.02
Log Output Level= 0
Friction Slope Method= 1
Unsteady Friction Slope Method= 2
Unsteady Bridges Friction Slope Method= 1
Parabolic Critical Depth
Global Vel Dist= 1 , 1 , 1
Global Log Level= 0
CheckData=True
Encroach Param=-1 ,0,0, 0
BEGIN DESCRIPTION:
Multiple Run
END DESCRIPTION:
Computation Interval=1HOUR
Output Interval=1HOUR
Run HTab= 0
Run UNet= 0
Run PostProcess= 0
Run WQNet= 0
UNET Theta= 1
UNET Theta Warmup= 1
UNET ZTol= 0.02
UNET ZSATol= 0.05
UNET MxIter= 20
UNET MaxInSteps= 0
UNET DtIC= 0
UNET DtMin= 0
UNET MaxCRTS= 20
UNET WFStab= 2
UNET SFStab= 1
UNET WFX= 1
UNET SFX= 1
UNET DSS MLevel= 4
UNET DZMax Abort= 100
UNET Convert EG Bridges= 0
UNET Use Existing IB Tables=-1
UNET Froude Reduction=False
UNET Froude Limit= 1
UNET Froude Power= 10
UNET Time Slicing=0,0, 5
UNET Junction Losses=0
Instantaneous Interval=1HOUR
DSS File=dss
Write IC File= 0
Write IC File at Sim End=0
Echo Input=False
Echo Parameters=False
Echo Output=False
Write Detailed= 0
WQ AD Non Conservative
WQ ULTIMATE=-1
WQ Max Comp Step=1HOUR
WQ Output Interval=15MIN
WQ Output Selected Increments= 0
WQ Output face flow=0
WQ Output face velocity=0
WQ Output face area=0
WQ Output face dispersion=0
WQ Output cell volume=0
WQ Output cell surface area=0
WQ Output cell continuity=0
WQ Output cumulative cell continuity=0
WQ Output face conc=0
WQ Output face dconc_dx=0
WQ Output face courant=0
WQ Output face peclet=0
WQ Output face adv mass=0
WQ Output face disp mass=0
WQ Output cell mass=0
WQ Output cell source sink temp=0
WQ Output cell source sink nsm=0
WQ Output MaxMinRange=-1
WQ Daily Max Min Mean=-1
WQ Daily Range=0
WQ Daily Time=0
WQ Create Restart=0
WQ Fixed Restart=0
WQ System Summary=0
WQ Use Fixed Temperature=0
Sorting and Armoring Iterations= 10
XS Update Threshold= 0.02
Hydraulics Update Threshold= 0.02
Energy Slope Method= 1
Volume Change Method= 0
XS Weighting Method= 0
Number of US Weighted Cross Sections= 1
Number of DS Weighted Cross Sections= 1
Upstream XS Weight=0.25
Main XS Weight=0.5
Downstream XS Weight=0.25
Number of DS XS's Weighted with US Boundary= 1
Upstream Boundary Weight= 1
Weight of XSs Associated with US Boundary= 0
Number of US XS's Weighted with DS Boundary= 1
Downstream Boundary Weight= 0.5
Weight of XSs Associated with DS Boundary= 0.5
Sediment Output Level= 4
Mass or Volume Output= 0
Output Increment Type= 1
Profile and TS Output Increment= 10
XS Output Flag= 0
XS Output Increment= 10
Disregard all LS=0
Disregard all Conn=0
Disregard all Breaches=0
Disregard all Pumps=0

--- UNT051 IN NURI.f01 (steady flow) ---

Flow Title=Multiple
Program Version=4.10
Number of Profiles= 7
Profile Names=10-year,25-year,50-year,1pct_min,100-year,1pct_plu,500-year
River Rch & RM=UNT051 IN NURI,Reach-1         ,10407
     888    1281    1617    1489    2014    2724    3138
Boundary for River Rch & Prof#=UNT051 IN NURI,Reach-1         , 1
Up Type= 0
Dn Type= 3
Dn Slope=0.009
Boundary for River Rch & Prof#=UNT051 IN NURI,Reach-1         , 2
Up Type= 0
Dn Type= 3
Dn Slope=0.009
Boundary for River Rch & Prof#=UNT051 IN NURI,Reach-1         , 3
Up Type= 0
Dn Type= 3
Dn Slope=0.009
Boundary for River Rch & Prof#=UNT051 IN NURI,Reach-1         , 4
Up Type= 0
Dn Type= 3
Dn Slope=0.009
Boundary for River Rch & Prof#=UNT051 IN NURI,Reach-1         , 5
Up Type= 0
Dn Type= 3
Dn Slope=0.009
Boundary for River Rch & Prof#=UNT051 IN NURI,Reach-1         , 6
Up Type= 0
Dn Type= 3
Dn Slope=0.009
Boundary for River Rch & Prof#=UNT051 IN NURI,Reach-1         , 7
Up Type= 0
Dn Type= 3
Dn Slope=0.009
DSS Import GetInterval= 0
DSS Import GetPeak= 0
DSS Import FillOption= 0

--- UNT051 IN NURI.g01 (geometry) ---

Geom Title=Existing Conditions
Program Version=4.10

River Reach=UNT051 IN NURI  ,Reach-1
Reach XY= 30
       2318258.6      13273304.2      2317668.11      13272556.4
      2317460.47     13272482.86      2317031.11     13272455.46
      2316838.36     13271968.12      2316966.64       13271397.
      2316779.67     13271096.25      2316754.05     13270894.61
      2316541.78     13270779.13      2315865.17     13270622.63
      2315813.15     13270425.15      2314928.77     13269971.42
      2314769.05     13270013.09      2314605.88      13270140.2
      2314305.71     13270159.58      2314162.83     13270073.58
        2314058.     13270087.54      2314040.91     13270190.63
      2313884.29      13270382.9      2313876.06     13270751.84
      2313815.05     13270797.82      2313734.22     13271194.81
      2313554.71     13271416.74      2313208.36     13271589.92
      2312975.29     13271817.78      2312776.52     13272173.12
      2312745.88     13272521.03      2312651.07     13272683.33
      2312364.61     13272933.67      2311671.74     13272982.01

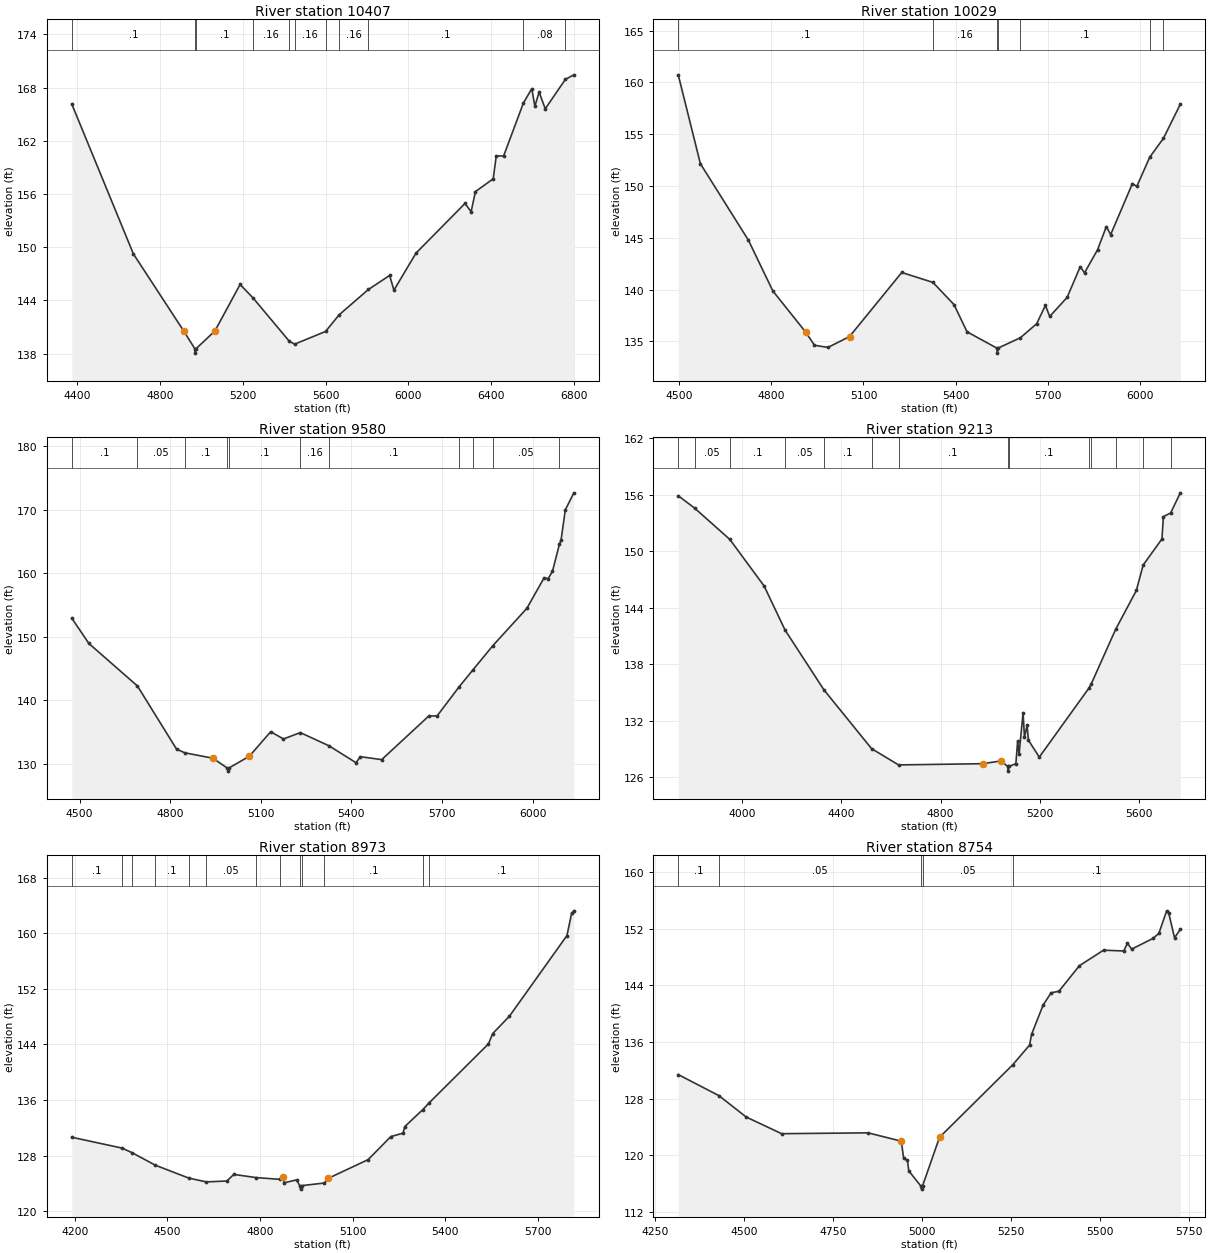
Type RM Length L Ch R = 1 ,10407   ,378,378,378
BEGIN DESCRIPTION:
UNT051 IN NURI 18.0
END DESCRIPTION:
XS GIS Cut Line= 2
      2318410.71     13272554.84      2316994.04     13274527.07
#Sta/Elev= 30
  4372.8  166.15  4670.8  149.25  4914.4  140.55  4967.9  138.56  4970.6  138.06
  4973.9  138.56  5064.8  140.55  5186.9   145.8  5249.2  144.29  5424.6  139.41
  5450.5  139.07  5600.1   140.5  5666.3  142.39  5807.7  145.24  5910.1  146.82
    5931  145.16  6037.8  149.34  6274.8  154.94  6304.2     154  6325.1  156.27
  6411.1  157.72  6425.8  160.29  6461.4  160.29  6557.1  166.26  6597.7  167.88
  6612.4   165.9  6633.3  167.49  6662.7  165.61  6760.3  168.93  6801.1  169.44
#Mann= 11 ,-1 , 0
  4372.8      .1       0  4967.9     .07       0  4973.9      .1       0
  5249.2     .16       0  5424.6      .1       0  5450.5     .16       0
  5600.1      .1       0  5666.3     .16       0  5807.7      .1       0
  6557.1     .08       0  6760.3     .05       0
Bank Sta=4914.4,5064.8
XS Rating Curve= 0 ,0
Exp/Cntr=0.3,0.1

Type RM Length L Ch R = 1 ,10029   ,449,449,449
BEGIN DESCRIPTION:
UNT051 IN NURI 17.0
END DESCRIPTION:
XS GIS Cut Line= 3
      2318237.75     13272446.83      2317837.72     13272746.85
      2317037.72     13273546.85
#Sta/Elev= 30
  4498.1  160.74    4570  152.16  4726.3  144.76  4805.4  139.87  4911.7  135.91
  4940.8  134.62  4984.6  134.41  5054.7  135.46  5224.4  141.65  5325.7  140.69
  5394.1  138.55  5436.5  135.92  5532.5  134.36  5535.3  133.86  5538.5  134.36
    5610  135.35  5662.8   136.7  5691.1  138.47  5705.2   137.4  5761.8  139.25
  5804.2   142.2  5818.4  141.62  5860.8  143.86  5889.1  146.08  5903.2  145.31
  5973.9  150.24  5988.1  149.96  6030.4   152.8  6074.6   154.6  6129.5   157.9
#Mann= 7 ,-1 , 0
  4498.1      .1       0  5325.7     .16       0  5532.5     .07       0
  5538.5     .16       0    5610      .1       0  6030.4     .05       0
  6074.6      .1       0
Bank Sta=4911.7,5054.7
XS Rating Curve= 0 ,0
Exp/Cntr=0.3,0.1

Type RM Length L Ch R = 1 ,9580    ,367,367,367
BEGIN DESCRIPTION:
UNT051 IN NURI 16.0
END DESCRIPTION:
XS GIS Cut Line= 3
       2317887.7     13272146.87      2317487.72     13272496.85
      2316687.69     13273296.89
#Sta/Elev= 30
  4473.9  152.94  4530.4  148.96  4691.5  142.26  4820.8  132.34  4847.8  131.76
  4941.3   130.9  4988.6  129.37  4991.4  128.87  4994.6  129.37    5062  131.21
  5132.7  135.07  5175.1  133.93  5230.9  134.93  5325.7  132.86  5415.5  130.19
  5429.6  131.14  5500.4  130.68  5655.9  137.52  5684.2  137.57  5757.1  142.15
  5803.1  144.83  5868.4   148.6  5981.2  154.48  6037.8  159.24  6051.9  159.17
    6066  160.29  6089.2  164.61  6094.3  165.16  6108.5  169.97  6136.8  172.65
#Mann= 11 ,-1 , 0
  4473.9      .1       0  4691.5     .05       0  4847.8      .1       0
  4988.6     .07       0  4994.6      .1       0  5230.9     .16       0
  5325.7      .1       0  5757.1     .05       0  5803.1      .1       0
  5868.4     .05       0  6089.2      .1       0
Bank Sta=4941.3,5062
XS Rating Curve= 0 ,0
Exp/Cntr=0.3,0.1

Type RM Length L Ch R = 1 ,9213    ,240,240,240
BEGIN DESCRIPTION:
UNT051 IN NURI 15.0
END DESCRIPTION:
XS GIS Cut Line= 3
      2317980.15     13271811.82      2317500.96     13271784.04
      2316757.92     13273138.18
#Sta/Elev= 30
  3741.7  155.91  3807.6   154.6  3949.7  151.27  4088.2  146.31  4172.5  141.63
  4329.2  135.28  4521.3  129.03  4630.2   127.3  4969.2  127.43    5045  127.73
  5069.5  127.14  5072.3  126.64  5075.5  127.14  5103.2  127.43  5110.4  129.86
  5116.1  128.43  5132.2  132.83  5137.9  130.26  5148.3  131.49    5154  129.92
  5197.6  128.13  5396.9  135.43  5407.3  135.92  5505.7  141.72    5589  145.84
  5616.6  148.55  5692.3  151.32    5698  153.69  5727.4  154.08  5766.3  156.22
#Mann= 14 ,-1 , 0
  3741.7      .1       0  3807.6     .05       0  3949.7      .1       0
  4172.5     .05       0  4329.2      .1       0  4521.3     .05       0
  4630.2      .1       0  5069.5     .07       0  5075.5      .1       0
  5396.9     .05       0  5407.3      .1       0  5505.7     .05       0
  5616.6      .1       0  5727.4     .05       0
Bank Sta=4969.2,5045
XS Rating Curve= 0 ,0
Exp/Cntr=0.3,0.1

Type RM Length L Ch R = 1 ,8973    ,219,219,219
BEGIN DESCRIPTION:
UNT051 IN NURI 14.0
END DESCRIPTION:
XS GIS Cut Line= 2
      2317341.24     13271589.59      2316633.65     13273053.33
#Sta/Elev= 30
  4190.4  130.64    4353  129.08  4385.9  128.41  4461.2  126.61  4569.3  124.76
    4626  124.21  4692.6  124.34  4715.2  125.29  4785.6  124.84  4866.2  124.57
  4873.4   124.9  4878.9  124.09  4918.6   124.5  4928.5  123.67  4931.3  123.17
  4934.5  123.67  5008.5  124.05  5020.4  124.71  5150.1  127.42  5223.4  130.73
  5263.1  131.23  5268.6  132.17  5326.4  134.59  5346.5  135.54  5539.8  144.09
  5553.5  145.57  5607.5  148.06  5793.9  159.68    5809  162.88  5816.2  163.24
#Mann= 13 ,-1 , 0
  4190.4      .1       0    4353     .08       0  4385.9     .05       0
  4461.2      .1       0  4569.3     .08       0    4626     .05       0
  4785.6     .08       0  4866.2     .05       0  4928.5     .03       0
  4934.5     .05       0  5008.5      .1       0  5326.4     .08       0
  5346.5      .1       0
Bank Sta=4873.4,5020.4
XS Rating Curve= 0 ,0
Exp/Cntr=0.3,0.1

Type RM Length L Ch R = 1 ,8754    ,77,77,77
BEGIN DESCRIPTION:
Mapping XS b098c280
END DESCRIPTION:
XS GIS Cut Line= 4
      2317328.41     13271589.97       2316937.8     13272097.77
      2316885.71     13272132.49      2316555.83     13272757.53
#Sta/Elev= 30
  4315.1   131.4  4429.5  128.42  4505.8  125.41  4605.4  123.05  4848.3  123.17
  4941.7  121.99    4948  119.59  4958.8  119.31  4962.5   117.8  4995.5  115.72
  4998.3  115.22  5001.5  115.72  5048.9  122.54  5254.6  132.79  5301.8  135.57
  5307.4  137.08  5339.9  141.23  5362.2  142.95  5384.2  143.17  5441.7  146.78
  5509.5  148.97    5566  148.86  5576.7  149.92  5588.6  149.12  5648.5  150.64
  5664.8  151.34  5686.8  154.53  5692.5  154.22  5708.9  150.72  5725.1  151.92
#Mann= 5 ,-1 , 0
  4315.1      .1       0  4429.5     .05       0  4995.5     .03       0
  5001.5     .05       0  5254.6      .1       0
Bank Sta=4941.7,5048.9
XS Rating Curve= 0 ,0
Exp/Cntr=0.3,0.1

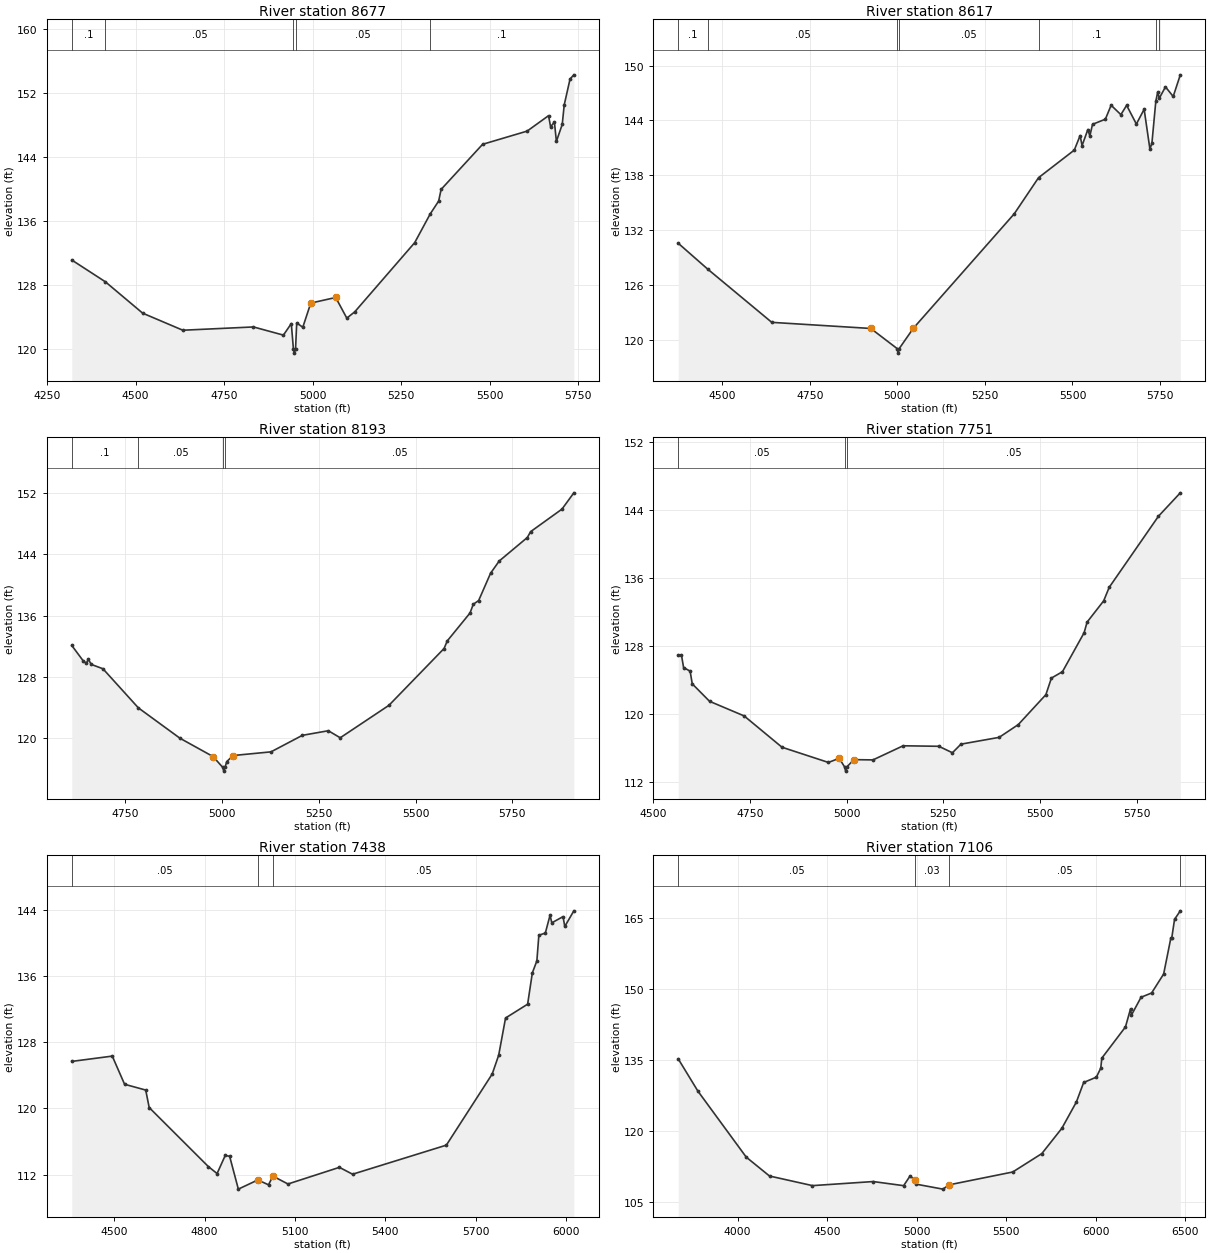
Type RM Length L Ch R = 1 ,8677    ,60,60,60
BEGIN DESCRIPTION:
Mapping XS e6942d1f
END DESCRIPTION:
XS GIS Cut Line= 5
      2317319.75     13271576.92      2316920.44     13272063.05
      2316872.69     13272050.03      2316837.97     13272115.13
      2316529.83     13272705.36
#Sta/Elev= 30
  4319.5  131.16  4414.4  128.44  4519.8  124.52  4633.2  122.39  4832.7   122.8
  4917.3  121.78  4939.6  123.22  4945.6  120.03  4948.4  119.53  4951.6  120.03
  4954.9   123.3  4972.1  122.76  4994.6  125.78    5065  126.48  5096.4   123.9
  5118.9  124.69  5288.2  133.33  5331.9  136.91  5355.8  138.52  5362.8  139.98
  5479.9  145.61  5605.7  147.26  5666.3  149.19    5672   147.8  5682.8  148.39
  5688.4  145.98  5704.9  148.09  5710.5  150.53    5727  153.77  5737.7  154.29
#Mann= 5 ,-1 , 0
  4319.5      .1       0  4414.4     .05       0  4945.6     .03       0
  4951.6     .05       0  5331.9      .1       0
Bank Sta=4994.6,5065
XS Rating Curve= 0 ,0
Exp/Cntr=0.3,0.1

Type RM Length L Ch R = 1 ,8617    ,424,424,424
BEGIN DESCRIPTION:
Mapping XS 35ae2acd
END DESCRIPTION:
XS GIS Cut Line= 3
      2317306.69     13271568.28      2316833.63     13272010.96
      2316473.37     13272709.78
#Sta/Elev= 30
  4373.9  130.54  4458.3   127.7  4641.1  121.88  4923.9  121.21  4999.1  119.01
  5001.8  118.51  5005.1  119.01  5045.4  121.23  5333.6  133.76  5403.1  137.72
  5505.2  140.74  5521.8  142.33  5527.4  141.23  5543.9  142.99  5549.6  142.28
  5557.2  143.56  5593.9  144.12  5610.4  145.65  5638.2  144.62  5654.7  145.64
  5682.5  143.59  5704.7  145.21  5721.2  140.84  5726.9   141.5    5738  146.08
  5743.4  147.09  5748.1  146.43  5765.6  147.66  5787.7  146.61    5808  148.98
#Mann= 7 ,-1 , 0
  4373.9      .1       0  4458.3     .05       0  4999.1     .03       0
  5005.1     .05       0  5403.1      .1       0    5738     .05       0
  5748.1      .1       0
Bank Sta=4923.9,5045.4
XS Rating Curve= 0 ,0
Exp/Cntr=0.3,0.1

Type RM Length L Ch R = 1 ,8193    ,442,442,442
BEGIN DESCRIPTION:
UNT051 IN NURI 13.0
END DESCRIPTION:
XS GIS Cut Line= 3
       2317337.7     13271546.86      2316937.72     13271596.85
      2316137.74     13271996.85
#Sta/Elev= 30
  4611.4  132.11  4641.6  130.05  4649.2  129.79  4654.2   130.3  4661.8  129.63
    4692  129.06  4783.5  123.95    4891  119.98  4976.7  117.58  5001.4  116.18
  5004.2  115.68  5007.4  116.18    5012  116.93  5028.5  117.72  5126.3   118.2
  5207.4  120.36  5274.4  120.96  5305.2  120.04    5431  124.28  5573.5  131.71
  5581.9  132.71  5640.6  136.35    5649  137.49  5662.9  137.98  5693.7  141.55
  5716.1  143.15  5788.7  146.22  5797.1  146.98  5878.2  149.93  5908.9  152.06
#Mann= 4 ,-1 , 0
  4611.4      .1       0  4783.5     .05       0  5001.4     .03       0
  5007.4     .05       0
Bank Sta=4976.7,5028.5
XS Rating Curve= 0 ,0
Exp/Cntr=0.3,0.1

Type RM Length L Ch R = 1 ,7751    ,313,313,313
BEGIN DESCRIPTION:
UNT051 IN NURI 12.0
END DESCRIPTION:
XS GIS Cut Line= 3
      2317237.69     13270996.87      2316837.72     13271196.85
      2316187.76     13271746.83
#Sta/Elev= 30
  4564.5  126.88  4572.8  126.92  4578.4  125.44  4595.2  125.03  4600.8  123.53
  4645.5  121.48    4735  119.76  4832.8  116.08    4953  114.29  4980.9  114.78
  4994.7  113.77  4997.5  113.27  5000.7  113.77  5018.8  114.62  5068.2  114.59
  5146.2  116.25  5238.5  116.19  5273.7  115.43  5295.7  116.44  5394.5  117.24
    5444  118.74  5515.4  122.26  5529.7  124.21  5558.3  124.96  5614.3  129.54
    5622  130.79  5664.9  133.29  5679.2  134.88  5806.6  143.24  5863.1  145.99
#Mann= 3 ,-1 , 0
  4564.5     .05       0  4994.7     .03       0  5000.7     .05       0
Bank Sta=4980.9,5018.8
XS Rating Curve= 0 ,0
Exp/Cntr=0.3,0.1

Type RM Length L Ch R = 1 ,7438    ,332,332,332
BEGIN DESCRIPTION:
UNT051 IN NURI 11.0
END DESCRIPTION:
XS GIS Cut Line= 4
      2317349.31     13270853.25      2316944.48     13270768.02
      2316433.04     13271151.59      2316124.79     13271683.07
#Sta/Elev= 30
  4358.6  125.67  4493.1  126.31    4534  122.91  4604.2  122.21  4615.7   120.1
    4812  112.98  4841.2  112.13  4868.3  114.32  4882.9  114.21  4911.8  110.25
  4976.6  111.36    5012  110.77  5026.6  111.82  5076.6  110.87  5247.4  112.88
  5291.2  112.05  5602.6  115.56  5754.9  124.15  5776.4  126.42  5799.2  130.91
  5872.5  132.58  5888.2  136.36  5903.2  137.81  5909.8   140.9  5931.3  141.17
    5947  143.32  5952.8   142.4  5990.1  143.15  5995.9  141.96    6026  143.85
#Mann= 3 , 0 , 0
  4358.6     .05       0  4976.6     .03       0  5026.6     .05       0
Bank Sta=4976.6,5026.6
XS Rating Curve= 0 ,0
Exp/Cntr=0.3,0.1

Type RM Length L Ch R = 1 ,7106    ,464,464,464
BEGIN DESCRIPTION:
UNT051 IN NURI 10.0
END DESCRIPTION:
XS GIS Cut Line= 4
      2317647.71     13270384.45      2316880.55     13270373.79
      2316145.36     13271066.36      2315964.24     13272078.52
#Sta/Elev= 30
  3668.2  135.14  3778.2  128.32  4048.2  114.38  4178.2  110.39  4418.3  108.36
  4757.8  109.22  4927.7  108.35  4962.9  110.36  4991.3  109.58  4998.6  108.66
  5146.8  107.62  5182.2  108.53  5537.4  111.24  5699.9  115.13  5811.7  120.47
    5893  126.03  5933.6  130.15  6004.7  131.28  6029.1  133.18  6035.2   135.3
  6167.2  141.89  6195.6  145.72  6200.6  144.39  6254.4  148.16  6313.3  149.06
  6380.6  153.07  6420.8  160.67  6425.9  160.68  6441.5  164.62  6473.7  166.42
#Mann= 4 ,-1 , 0
  3668.2     .05       0  4991.3     .03       0  5182.2     .05       0
  6473.7      .1       0
Bank Sta=4991.3,5182.2
XS Rating Curve= 0 ,0
Exp/Cntr=0.3,0.1

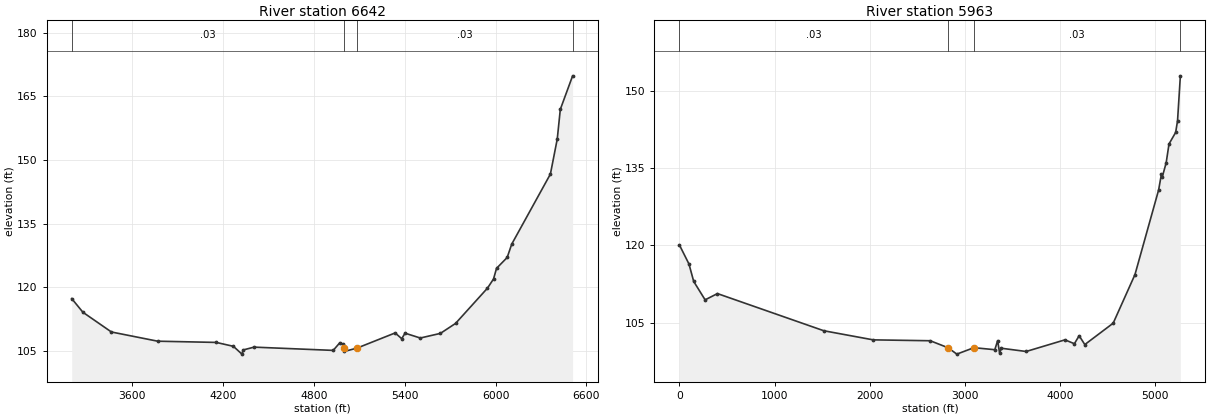
Type RM Length L Ch R = 1 ,6642    ,637,637,637
BEGIN DESCRIPTION:
UNT051 IN NURI 1.0
END DESCRIPTION:
XS GIS Cut Line= 4
      2317445.28     13269787.77      2316507.63     13269968.91
      2315719.17     13271077.01      2315793.76     13272067.94
#Sta/Elev= 30
  3199.9  117.31    3274  114.08  3462.2  109.43  3767.8  107.26  4154.9  106.97
  4267.9  106.05  4324.2  104.21  4333.1   105.2  4404.4  105.86    4927  105.09
  4971.3  106.91  4992.2  106.56  4995.5  105.61  4999.2  104.83  5085.1  105.64
  5336.5  109.21  5379.7  107.85  5401.7  109.15  5502.4  108.01  5635.1   109.1
  5735.3  111.45  5945.9  119.76    5986  121.92  6006.1  124.44  6076.3     127
  6106.4  130.15  6361.8  146.67  6407.2  154.95  6427.3  161.93  6508.6  169.84
#Mann= 4 ,-1 , 0
  3199.9     .03       0  4995.5    .025       0  5085.1     .03       0
  6508.6      .1       0
Bank Sta=4995.5,5085.1
XS Rating Curve= 0 ,0
Exp/Cntr=0.3,0.1

Type RM Length L Ch R = 1 ,5963    ,0,0,0
XS GIS Cut Line= 4
     2317514.183    13269670.059     2315537.548    13269229.034
     2314670.433    13270581.518     2315071.474    13272190.893
#Sta/Elev= 30
       0120.059399.84036116.3904149.7605113.0066 269.569109.4415399.3615110.6523
1517.573103.44952036.749101.68432635.948101.51392825.694100.14412915.574 98.9199
3095.333100.1694 3315.04 99.7776    3345101.53673364.973 99.16563384.946100.0575
3644.477 99.43224052.265101.68764151.725100.93894201.455102.48574261.131100.7727
4559.512104.91934788.271114.33025036.922130.7242 5066.76133.81935076.706133.3368
 5116.49136.00695146.328139.65425215.951 141.8835235.843144.12285265.681152.8561
#Mann= 4 ,-1 , 0
       0     .03       02825.694    .025       03095.333     .03       0
5265.681      .1       0
Bank Sta=2825.694,3095.333
XS Rating Curve= 0 ,0
Exp/Cntr=0.3,0.1

Chan Stop Cuts=-1
Use User Specified Reach Order=0
Composite Channel Slope=5