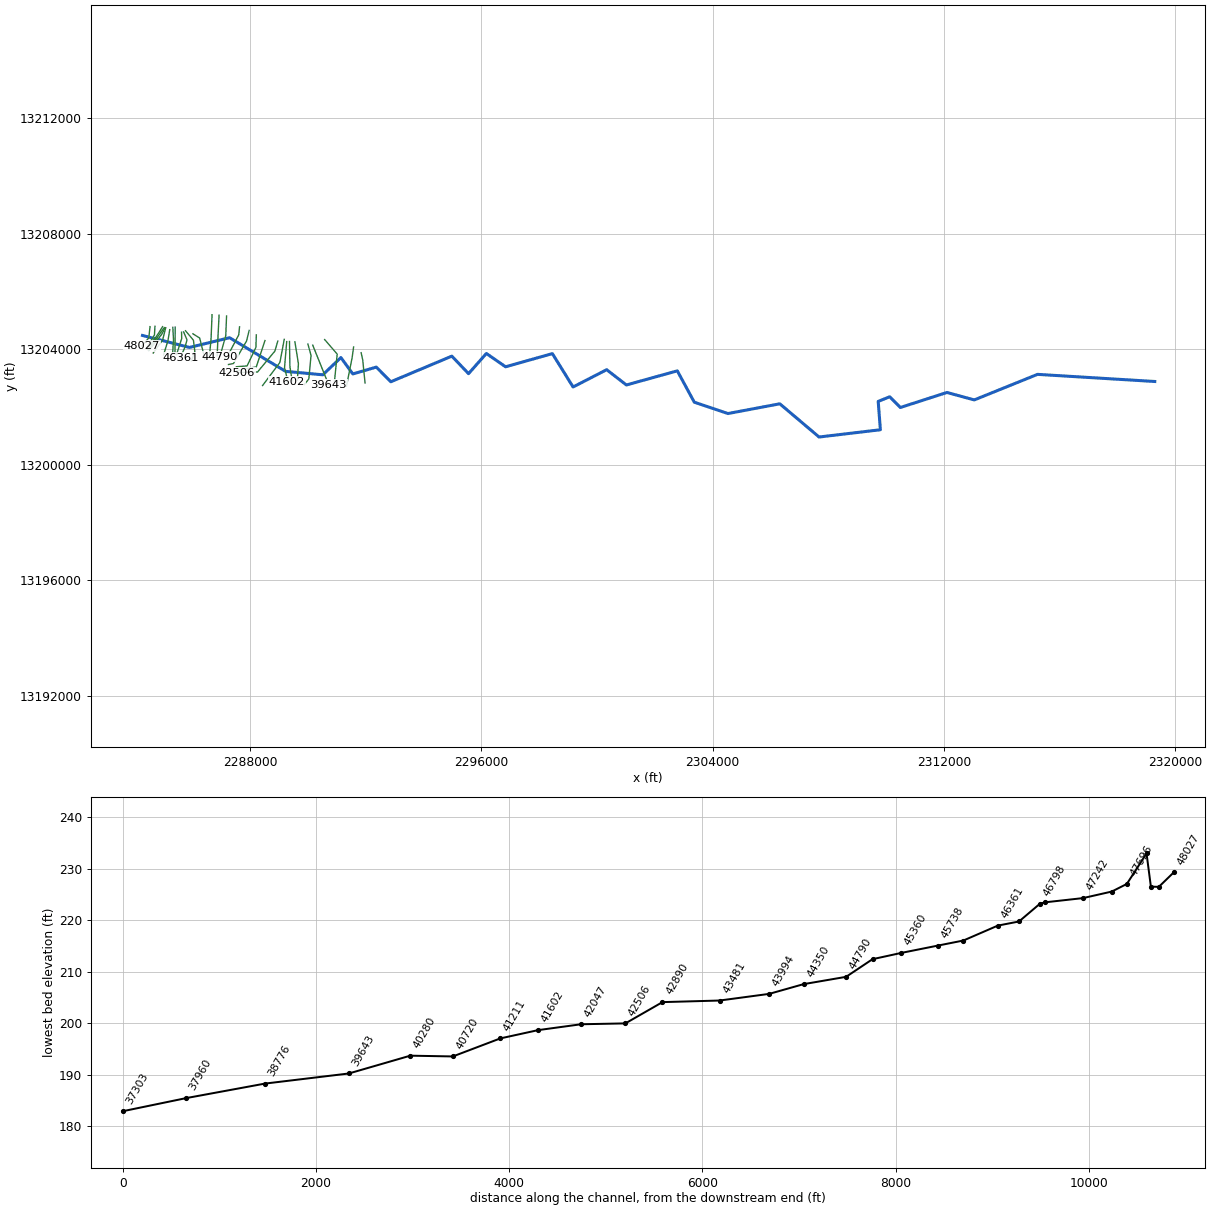
--- BARBONE CREEK.prj (project) ---

Proj Title=BARBONE CREEK Base Level Engineering
Current Plan=p01
Default Exp/Contr=0.3,0.1
English Units
Geom File=g01
Flow File=f01
Plan File=p01
Y Axis Title=Elevation
X Axis Title(PF)=Main Channel Distance
X Axis Title(XS)=Station
BEGIN DESCRIPTION:
BARBONE CREEK
END DESCRIPTION:
DSS Export Rating Curves= 0
DSS Export Rating Curve Sorted= 0
DSS Export Volume Flow Curves= 0
DXF OffsetX= 0
DXF OffsetY= 0
DXF ScaleX= 1
DXF ScaleY= 10

--- BARBONE CREEK.p01 (plan) ---

Plan Title=Multiple Run
Short Identifier=Multiple
Geom File=g01
Flow File=f01
Subcritical Flow
K Sum by GR= 0
Std Step Tol= 0.01
Critical Tol= 0.01
Num of Std Step Trials= 20
Max Error Tol= 0.3
Flow Tol Ratio= 0.001
Split Flow NTrial= 30
Split Flow Tol= 0.02
Split Flow Ratio= 0.02
Log Output Level= 0
Friction Slope Method= 1
Unsteady Friction Slope Method= 2
Unsteady Bridges Friction Slope Method= 1
Parabolic Critical Depth
Global Vel Dist=  1 , 1 , 1
Global Log Level= 0
CheckData=True
Encroach Param= -1, 0, 0, 0
BEGIN DESCRIPTION:
Multiple Run
END DESCRIPTION:

--- BARBONE CREEK.f01 (steady flow) ---

Flow Title=Multiple
Program Version=4.10
Number of Profiles= 7
Profile Names=10-year,25-year,50-year,1pct_min,100-year,1pct_plu,500-year
River Rch & RM=BARBONE CREEK,Reach-1         ,48027
     114     149     176     154     208     281     293
River Rch & RM=BARBONE CREEK,Reach-1         ,45360
     418     586     725     659     891    1205    1364
River Rch & RM=BARBONE CREEK,Reach-1         ,34639
     613     871    1088     996    1347    1821    2086
River Rch & RM=BARBONE CREEK,Reach-1         ,31221
     937    1348    1699    1563    2114    2859    3306
River Rch & RM=BARBONE CREEK,Reach-1         ,23085
    1221    1774    2250    2081    2814    3806    4442
River Rch & RM=BARBONE CREEK,Reach-1         ,18669
    1655    2428    3099    2881    3896    5268    6205
River Rch & RM=BARBONE CREEK,Reach-1         ,7654
    1717    2522    3221    2996    4051    5479    6458
River Rch & RM=BARBONE CREEK,Reach-1         ,6825
    1826    2678    3416    3171    4289    5800    6810
Boundary for River Rch & Prof#=BARBONE CREEK,Reach-1         , 1
Up Type= 0
Dn Type= 3
Dn Slope=0.0001
Boundary for River Rch & Prof#=BARBONE CREEK,Reach-1         , 2
Up Type= 0
Dn Type= 3
Dn Slope=0.0001
Boundary for River Rch & Prof#=BARBONE CREEK,Reach-1         , 3
Up Type= 0
Dn Type= 3
Dn Slope=0.0001
Boundary for River Rch & Prof#=BARBONE CREEK,Reach-1         , 4
Up Type= 0
Dn Type= 3
Dn Slope=0.0001
Boundary for River Rch & Prof#=BARBONE CREEK,Reach-1         , 5
Up Type= 0
Dn Type= 3
Dn Slope=0.0001
Boundary for River Rch & Prof#=BARBONE CREEK,Reach-1         , 6
Up Type= 0
Dn Type= 3
Dn Slope=0.0001
Boundary for River Rch & Prof#=BARBONE CREEK,Reach-1         , 7
Up Type= 0
Dn Type= 3
Dn Slope=0.0001
DSS Import GetInterval= 0
DSS Import GetPeak= 0
DSS Import FillOption= 0

--- BARBONE CREEK.g01 (geometry) ---

Geom Title=Existing Conditions
Program Version=4.10

River Reach=BARBONE CREEK   ,Reach-1
Reach XY= 30
      2284284.33     13204481.63      2285910.79     13204066.23
      2287296.32     13204403.31      2289236.75      13203236.8
       2290521.8     13203118.67      2291147.37     13203715.68
       2291558.5     13203148.36      2292371.87     13203385.39
      2292872.96     13202877.39      2294983.66     13203764.89
      2295561.66     13203158.58      2296177.72     13203856.85
      2296842.82     13203396.25      2298460.85     13203852.39
      2299176.81      13202696.6      2300338.45     13203295.16
      2301020.43     13202766.34      2302781.89      13203255.2
      2303369.09     13202170.15      2304532.65     13201776.69
      2306326.53      13202114.2       2307684.9     13200963.52
      2309805.57     13201215.52      2309730.05     13202196.94
      2310126.58     13202357.36      2310496.09     13201986.25
       2312106.9     13202506.59      2313052.09     13202248.47
       2315239.3     13203133.88      2319295.03     13202886.85

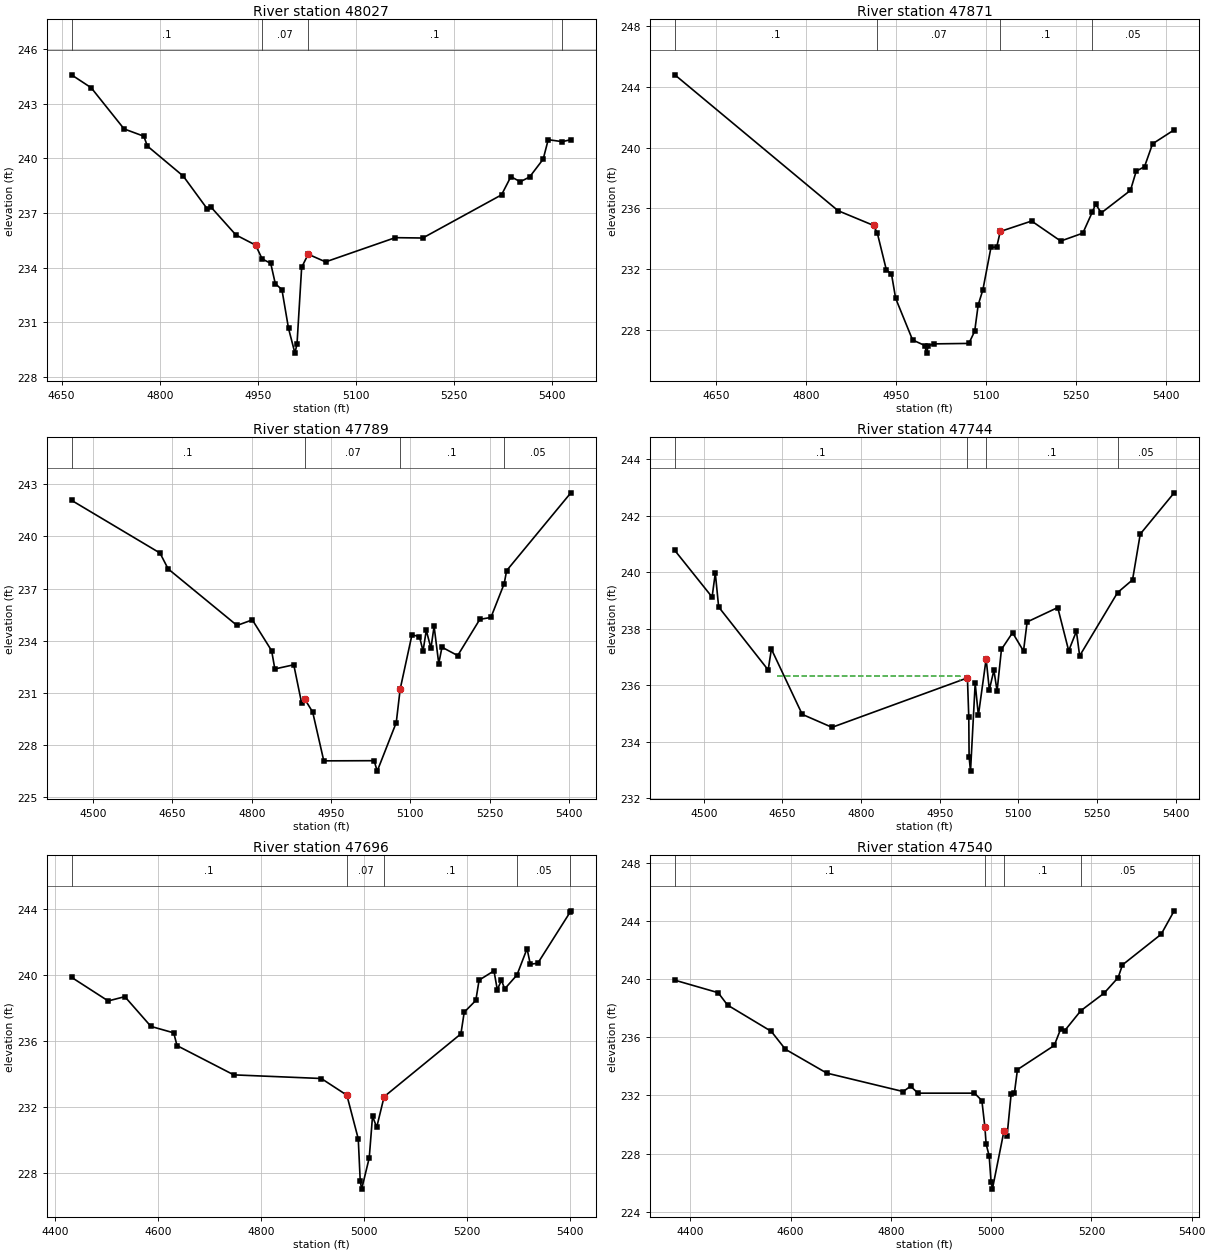
Type RM Length L Ch R = 1 ,48027   ,156,156,156
BEGIN DESCRIPTION:
BARBONE CREEK 91.0
END DESCRIPTION:
XS GIS Cut Line= 3
      2284545.22      13204786.8      2284503.34      13204399.1
      2284261.53     13204114.12
#Sta/Elev= 30
  4665.1  244.58  4695.2  243.87  4745.5  241.61  4775.7  241.21  4781.1  240.67
    4836  239.02  4872.9  237.21  4877.9  237.34  4916.5  235.79  4946.7  235.23
  4956.7  234.47  4969.8  234.23  4976.8  233.11  4986.9  232.79    4997  230.66
  5006.8   229.3    5010   229.8  5017.1  234.01  5027.1  234.73  5053.7  234.31
  5160.3  235.64  5202.3  235.62  5322.8  237.99  5337.1  238.99  5351.4  238.71
  5365.7  238.97  5386.5  239.95  5394.2  241.02  5415.7  240.91  5428.8  241.02
#Mann= 4 ,-1 , 0
  4665.1      .1       0  4956.7     .07       0  5027.1      .1       0
  5415.7     .05       0
Bank Sta=4946.7,5027.1
XS Rating Curve= 0 ,0
Exp/Cntr=0.3,0.1

Type RM Length L Ch R = 1 ,47871   ,82,82,82
BEGIN DESCRIPTION:
Mapping XS 92a4ec1d
END DESCRIPTION:
XS GIS Cut Line= 3
      2284716.01     13204798.39      2284698.65     13204498.93
      2284421.79     13204044.71
#Sta/Elev= 30
  4581.9  244.81  4853.9  235.85    4913  234.88  4919.4  234.35  4934.3  231.95
  4942.8  231.69  4949.8  230.07    4978  227.33  4998.4  226.96  5001.2  226.46
  5004.4  226.96  5013.8  227.07  5071.8   227.1  5081.5  227.91  5087.3  229.64
  5095.1  230.63  5108.6  233.43  5118.2  233.46  5124.1  234.48  5176.3  235.17
  5224.8  233.85  5261.6  234.37  5277.2  235.74  5282.9  236.28  5292.5  235.71
    5341  237.19  5350.6  238.46  5364.4  238.75  5377.8  240.26  5413.8  241.18
#Mann= 4 ,-1 , 0
  4581.9      .1       0  4919.4     .07       0  5124.1      .1       0
  5277.2     .05       0
Bank Sta=4913,5124.1
XS Rating Curve= 0 ,0
Exp/Cntr=0.3,0.1

Type RM Length L Ch R = 1 ,47789   ,45,45,45
XS GIS Cut Line= 3
      2284978.74     13204786.54      2284839.86      13204558.7
       2284453.9     13204001.44
#Sta/Elev= 30
  4459.1  242.07  4626.5  239.04  4641.9  238.13  4772.2  234.88  4801.2   235.2
  4837.7  233.43  4843.8  232.38  4879.6  232.62  4894.5  230.41  4900.6  230.64
  4915.4   229.9  4936.4   227.1  5031.6  227.11  5037.5  226.51  5073.5   229.3
  5080.9  231.22  5103.2  234.34  5117.4  234.24  5124.2  233.41  5130.3   234.6
  5139.1  233.57  5145.1  234.83  5153.9  232.69    5160  233.63  5189.7  233.15
  5231.6  235.23  5252.6  235.34  5277.7  237.28  5282.3  238.03  5403.8   242.5
#Mann= 4 ,-1 , 0
  4459.1      .1       0  4900.6     .07       0  5080.9      .1       0
  5277.7     .05       0
Bank Sta=4900.6,5080.9
XS Rating Curve= 0 ,0
Exp/Cntr=0.3,0.1

Type RM Length L Ch R = 1 ,47744   ,204,204,204
BEGIN DESCRIPTION:
BARBONE CREEK 90.0
END DESCRIPTION:
XS GIS Cut Line= 2
      2285037.22     13204755.04        2284486.     13203978.12
#Sta/Elev= 30
  4444.7  240.77  4515.8  239.12  4521.9  239.97  4528.3  238.77  4622.8  236.54
  4628.9  237.28  4687.7  234.97  4744.6  234.51  5002.9  236.26  5005.5  234.86
  5006.1  233.46  5008.8  232.96  5017.7  236.07  5023.8  234.93  5038.6  236.93
  5044.7  235.84  5053.4  236.53  5059.5   235.8  5067.8  237.27    5089  237.86
  5109.9  237.21  5116.8  238.24  5175.2  238.75  5196.1  237.22  5210.8  237.91
    5217  237.04  5289.4  239.28  5317.9  239.73  5332.6  241.35  5397.3  242.81
#Mann= 4 ,-1 , 0
  4444.7      .1       0  5002.9     .07       0  5038.6      .1       0
  5289.4     .05       0
#XS Ineff= 1 ,-1
 4639.42 4988.24  236.33
Permanent Ineff=
       T
Bank Sta=5002.9,5038.6
XS Rating Curve= 0 ,0
Exp/Cntr=0.3,0.1

Type RM Length L Ch R = 1 ,47696   ,156,156,156
XS GIS Cut Line= 3
      2285063.41     13204738.85      2284954.88     13204528.32
       2284502.3     13203952.31
#Sta/Elev= 30
  4432.5  239.84  4503.7  238.41    4536  238.67  4586.7  236.87    4631  236.48
  4637.3  235.71  4747.5  233.94  4917.4  233.72  4967.1  232.71  4989.2  230.07
    4993  227.53  4995.8  227.03  5010.5  228.92  5016.9  231.44    5025  230.77
  5039.4  232.62  5188.5  236.42  5194.9  237.73  5217.4  238.44  5223.8  239.67
  5252.7  240.23  5259.1  239.09  5267.2  239.66  5273.5  239.14  5297.3  239.98
  5316.9  241.57  5323.2  240.63  5337.7  240.69  5400.1  243.76  5401.9  243.86
#Mann= 5 ,-1 , 0
  4432.5      .1       0  4967.1     .07       0  5039.4      .1       0
  5297.3     .05       0  5400.1      .1       0
Bank Sta=4967.1,5039.4
XS Rating Curve= 0 ,0
Exp/Cntr=0.3,0.1

Type RM Length L Ch R = 1 ,47540   ,298,298,298
BEGIN DESCRIPTION:
Mapping XS 08292a52
END DESCRIPTION:
XS GIS Cut Line= 3
      2285089.26     13204750.62      2284980.77     13204320.98
      2284655.27     13203873.96
#Sta/Elev= 30
    4369  239.92  4455.4  239.06  4474.1  238.21  4561.4   236.4  4589.5  235.17
    4672  233.53  4824.6  232.26  4839.3  232.63    4854  232.15  4966.8  232.15
  4981.5  231.64  4987.5  229.83    4990  228.65  4996.1  227.83  4999.8  226.05
  5002.5  225.55  5025.5  229.53  5031.7  229.19  5039.9   232.1  5046.4  232.16
  5052.5  233.77  5125.9  235.43  5138.9  236.58  5146.8  236.45  5178.9  237.82
  5225.4  239.03  5253.4   240.1  5261.9  240.97  5339.2  243.08  5365.1  244.69
#Mann= 4 ,-1 , 0
    4369      .1       0  4987.5     .07       0  5025.5      .1       0
  5178.9     .05       0
Bank Sta=4987.5,5025.5
XS Rating Curve= 0 ,0
Exp/Cntr=0.3,0.1

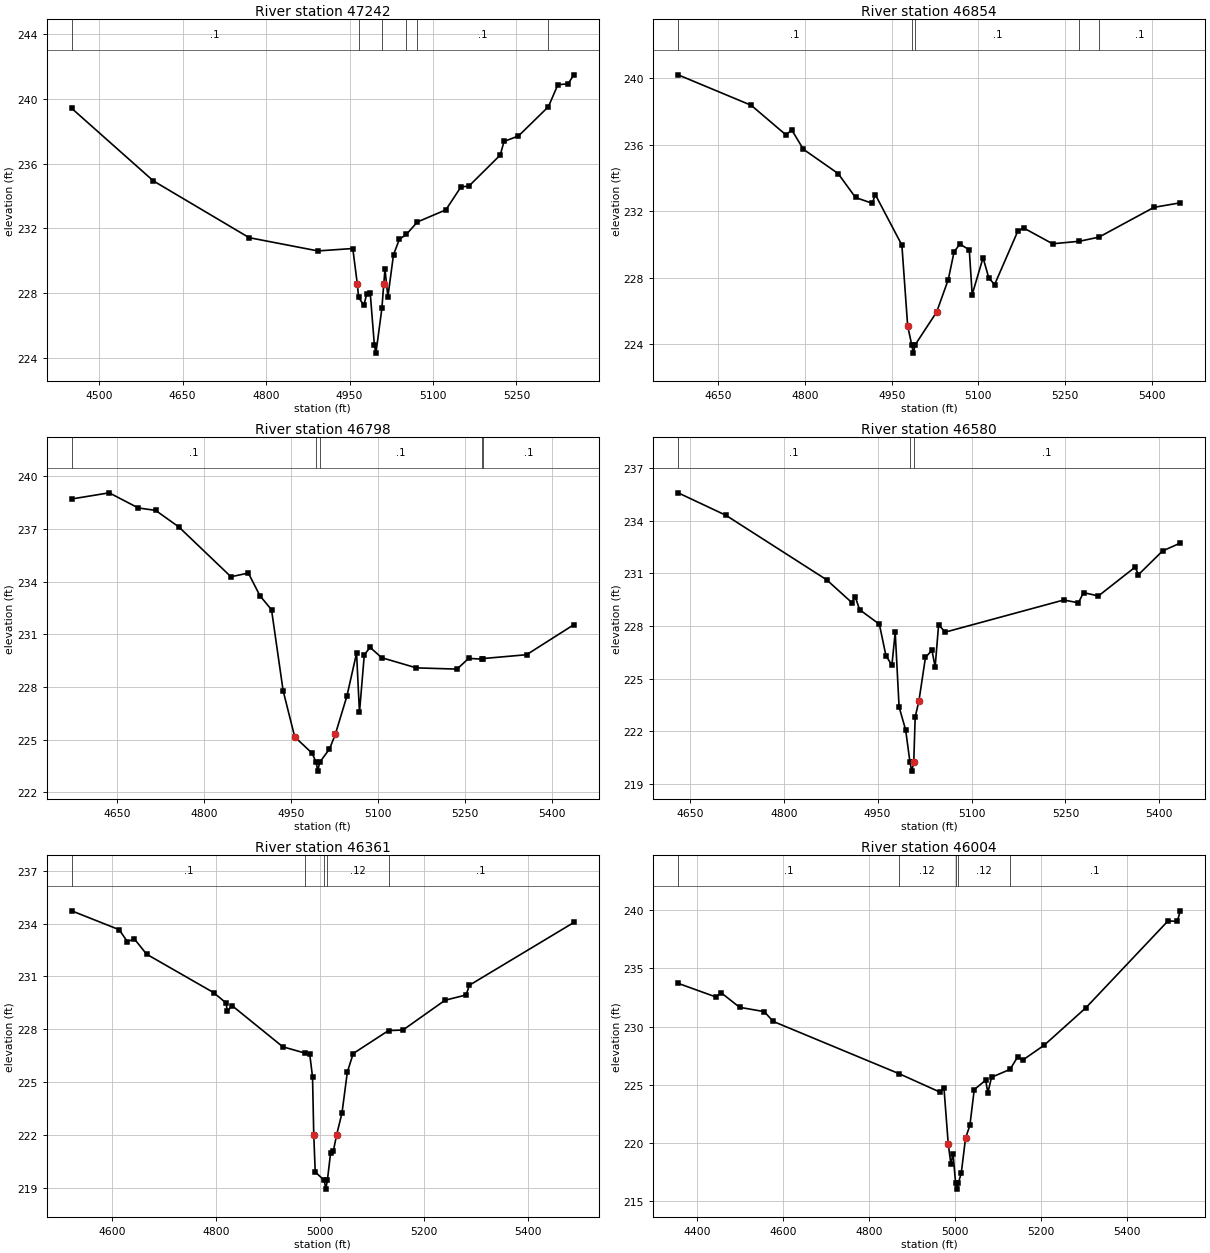
Type RM Length L Ch R = 1 ,47242   ,388,388,388
BEGIN DESCRIPTION:
Mapping XS 070b5056
END DESCRIPTION:
XS GIS Cut Line= 3
      2285227.13     13204681.87      2285167.23     13204309.43
      2285013.58     13203806.81
#Sta/Elev= 30
  4450.4  239.42  4597.3  234.93  4769.5  231.42  4893.1   230.6  4955.8  230.75
 4963.86  228.58  4966.3  227.73  4975.7  227.23  4980.9  227.95  4987.2  227.97
  4994.6  224.78  4997.4  224.28  5008.1  227.04  5011.5  228.56  5013.7  229.47
  5018.9  227.76    5029  230.36  5039.5  231.32  5052.1  231.62  5071.9  232.39
  5123.1  233.14  5150.1  234.55  5164.9  234.62  5220.9  236.53  5227.7  237.37
  5253.7  237.71  5307.5  239.52  5324.5  240.88  5342.7  240.93  5353.2  241.49
#Mann= 6 ,-1 , 0
  4450.4      .1       0  4966.3     .07       0  5008.1      .1       0
  5052.1     .16       0  5071.9      .1       0  5307.5     .05       0
Bank Sta=4963.86,5011.5
XS Rating Curve= 0 ,0
Exp/Cntr=0.3,0.1

Type RM Length L Ch R = 1 ,46854   ,56,56,56
BEGIN DESCRIPTION:
BARBONE CREEK 89.0
END DESCRIPTION:
XS GIS Cut Line= 3
      2285333.34     13204762.94      2285357.65     13204337.61
      2285329.87     13203896.61
#Sta/Elev= 30
    4581  240.19  4707.3  238.36  4767.4  236.58  4777.4  236.88  4797.4  235.72
  4857.5  234.26  4887.6  232.82  4916.6  232.47  4921.7     233  4967.7  229.96
  4977.7  225.11  4984.7  223.97  4987.5  223.47  4990.7  223.97  5027.8  225.94
  5047.9  227.89  5057.9  229.55  5067.9  230.02  5084.2  229.68  5089.2  226.99
    5108   229.2    5118  227.98    5128  227.59  5168.1   230.8  5178.1  230.99
  5228.2  230.04  5274.5  230.19  5308.4  230.44  5403.5  232.23  5448.9   232.5
#Mann= 5 ,-1 , 0
    4581      .1       0  4984.7     .07       0  4990.7      .1       0
  5274.5     .16       0  5308.4      .1       0
Bank Sta=4977.7,5027.8
XS Rating Curve= 0 ,0
Exp/Cntr=0.3,0.1

Type RM Length L Ch R = 1 ,46798   ,218,218,218
BEGIN DESCRIPTION:
BARBONE CREEK 88.0
END DESCRIPTION:
XS GIS Cut Line= 2
      2285416.67     13204771.62      2285409.73     13203905.34
#Sta/Elev= 30
  4572.2  238.71    4637  239.06    4687   238.2    4717  238.06    4757  237.12
    4847  234.28    4877  234.49    4897   233.2    4917   232.4    4937  227.79
    4957  225.16    4987  224.23    4994  223.71  4996.7  223.21    5000  223.71
    5017  224.47    5027   225.3    5047  227.48  5063.7  229.93  5068.7  226.55
    5077  229.83    5087  230.26    5107  229.67    5167  229.09    5237  229.02
    5257  229.63  5280.2  229.59  5281.4  229.62    5357  229.84  5438.5  231.55
#Mann= 5 ,-1 , 0
  4572.2      .1       0    4994     .07       0    5000      .1       0
  5280.2     .16       0  5281.4      .1       0
Bank Sta=4957,5027
XS Rating Curve= 0 ,0
Exp/Cntr=0.3,0.1

Type RM Length L Ch R = 1 ,46580   ,219,219,219
BEGIN DESCRIPTION:
Mapping XS b8b78e14
END DESCRIPTION:
XS GIS Cut Line= 3
      2285635.98     13204593.25      2285641.19     13204371.93
      2285461.49     13203819.82
#Sta/Elev= 30
  4631.4  235.58  4707.8   234.3  4868.6  230.63  4908.9  229.33  4914.2  229.67
  4921.2  228.93  4952.8   228.1  4963.3  226.31  4972.8  225.77  4978.1  227.64
  4984.3  223.39  4994.8  222.08  5001.7  220.24  5004.5  219.74  5007.7  220.24
    5010  222.82  5015.9  223.72  5026.4  226.21  5036.7  226.62  5041.9  225.68
  5047.4  228.07  5057.9  227.65  5247.2  229.48  5270.7  229.32  5278.8   229.9
  5302.6  229.71  5361.2  231.35  5366.5  230.92    5405  232.27  5433.4  232.72
#Mann= 3 ,-1 , 0
  4631.4      .1       0  5001.7     .07       0  5007.7      .1       0
Bank Sta=5007.7,5015.9
XS Rating Curve= 0 ,0
Exp/Cntr=0.3,0.1

Type RM Length L Ch R = 1 ,46361   ,357,357,357
BEGIN DESCRIPTION:
BARBONE CREEK 86.0
END DESCRIPTION:
XS GIS Cut Line= 4
       2285706.7      13204605.6      2285824.78     13204327.78
      2285762.28     13204095.14      2285592.43     13203706.93
#Sta/Elev= 30
  4521.8  234.72  4613.3  233.65  4629.1  232.97  4642.4  233.13  4666.1  232.26
  4795.2  230.08  4818.8   229.5  4821.5  229.03  4830.7  229.34  4928.2  227.01
  4971.3  226.65  4979.9  226.62  4985.4   225.3 4987.73  222.03  4990.6  219.91
    5008  219.44  5010.8  218.94    5014  219.44  5020.2  221.01  5025.4  221.09
  5031.7  222.01  5042.1  223.26  5052.4  225.58  5063.7  226.63  5131.6  227.93
  5159.4  227.96  5240.4  229.65    5281  229.95  5287.2   230.5  5488.3  234.06
#Mann= 5 ,-1 , 0
  4521.8      .1       0  4971.3     .12       0    5008     .07       0
    5014     .12       0  5131.6      .1       0
Bank Sta=4987.73,5031.7
XS Rating Curve= 0 ,0
Exp/Cntr=0.3,0.1

Type RM Length L Ch R = 1 ,46004   ,266,266,266
BEGIN DESCRIPTION:
Mapping XS e271a005
END DESCRIPTION:
XS GIS Cut Line= 4
      2285772.67     13204643.78        2286047.     13204317.36
      2286095.61       13203925.      2285974.69     13203600.23
#Sta/Elev= 30
  4355.7  233.72  4442.8  232.56  4456.2   232.9  4498.8  231.66    4556  231.29
  4576.8  230.45  4869.6  225.96    4964  224.39  4974.1  224.77  4984.1  219.93
  4990.2  218.21  4995.3  219.09  5001.3  216.54    5004  216.04  5007.3  216.54
  5014.4  217.41  5024.4  220.43  5034.5  221.52  5044.6  224.59  5071.2   225.4
  5076.2  224.32  5084.9  225.65  5127.9  226.33  5145.4  227.39  5157.2  227.12
  5207.5  228.41  5304.6  231.63  5495.6  239.09  5516.9  239.04    5524  239.95
#Mann= 5 ,-1 , 0
  4355.7      .1       0  4869.6     .12       0  5001.3     .07       0
  5007.3     .12       0  5127.9      .1       0
Bank Sta=4984.1,5024.4
XS Rating Curve= 0 ,0
Exp/Cntr=0.3,0.1

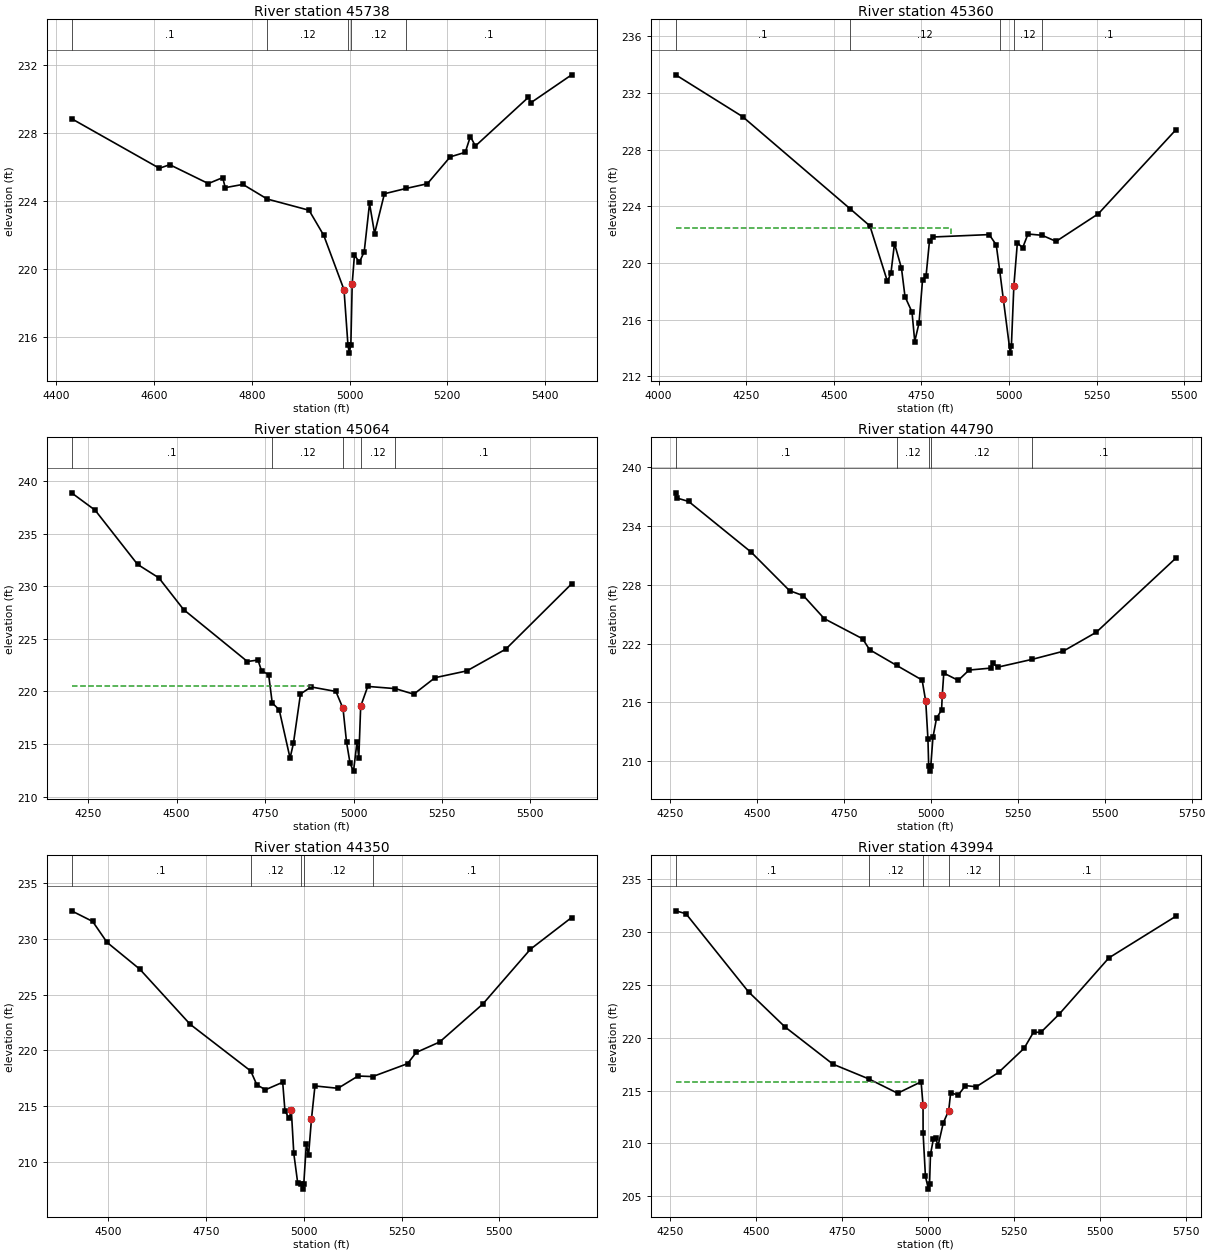
Type RM Length L Ch R = 1 ,45738   ,378,378,378
BEGIN DESCRIPTION:
Mapping XS f8e0b5d9
END DESCRIPTION:
XS GIS Cut Line= 3
      2286030.85     13204537.44      2286263.46     13204391.62
        2286444.     13203665.98
#Sta/Elev= 30
  4431.7  228.85  4611.3  225.93  4632.5  226.14  4711.3  225.03  4740.7  225.38
  4745.9  224.79  4782.1  224.98  4831.7  224.12  4917.2  223.46  4947.3  221.98
  4988.7  218.78  4996.7  215.55  4999.4  215.05  5002.7  215.55 5005.45  219.14
    5010  220.81  5020.3  220.41    5030  221.02  5040.9  223.86  5051.2  222.09
  5071.3  224.43  5115.2  224.74  5159.1  225.02  5205.8   226.6  5236.6  226.87
    5247   227.8  5257.3  227.24  5365.7  230.11  5370.8  229.79    5454  231.43
#Mann= 5 ,-1 , 0
  4431.7      .1       0  4831.7     .12       0  4996.7     .07       0
  5002.7     .12       0  5115.2      .1       0
Bank Sta=4988.7,5005.45
XS Rating Curve= 0 ,0
Exp/Cntr=0.3,0.1

Type RM Length L Ch R = 1 ,45360   ,296,296,296
BEGIN DESCRIPTION:
BARBONE CREEK 87.0
END DESCRIPTION:
XS GIS Cut Line= 3
      2286690.55      13205200.7      2286655.82     13204346.48
      2286600.26     13203777.01
#Sta/Elev= 30
  4048.6  233.28  4239.4  230.33    4546  223.83  4602.9  222.61  4652.9  218.69
  4662.9  219.28    4673  221.37    4693  219.62    4703  217.62    4723  216.53
  4730.8  214.45    4743  215.75    4753  218.76    4763  219.05    4773  221.58
    4783  221.83  4943.3     222  4963.4  221.27  4973.5  219.41  4983.5  217.46
  5003.4  213.63  5006.6  214.13  5013.7  218.38  5023.7  221.44  5038.6  221.05
  5053.9  222.04  5094.3  221.95  5134.2  221.52  5254.8  223.47  5475.7  229.39
#Mann= 5 ,-1 , 0
  4048.6      .1       0    4546     .12       0  4973.5     .07       0
  5013.7     .12       0  5094.3      .1       0
#XS Ineff= 2 , 0
       0 4834.55  222.48               0
Permanent Ineff=
       T       F
Bank Sta=4983.5,5013.7
XS Rating Curve= 0 ,0
Exp/Cntr=0.3,0.1

Type RM Length L Ch R = 1 ,45064   ,274,274,274
BEGIN DESCRIPTION:
BARBONE CREEK 85.0
END DESCRIPTION:
XS GIS Cut Line= 3
       2286933.6     13205183.33      2286891.93      13204356.9
      2286867.66     13203770.99
#Sta/Elev= 30
  4202.8   238.9  4269.4  237.25  4389.5  232.09  4449.6  230.81  4519.7  227.79
  4699.9  222.85  4729.9  222.99    4740  221.96    4760  221.61  4770.2  218.91
    4790  218.25  4820.6  213.66  4830.1  215.06  4850.1  219.76  4880.1  220.43
  4950.2     220  4970.3  218.39  4980.3  215.18  4990.3  213.16    5000  212.42
    5010   215.2    5015  213.71  5020.3  218.59  5040.3  220.48  5118.4  220.27
  5170.4  219.74  5230.5  221.31  5320.6  221.96  5430.7  224.03  5616.7  230.24
#Mann= 5 ,-1 , 0
  4202.8      .1       0  4770.2     .12       0  4970.3     .07       0
  5020.3     .12       0  5118.4      .1       0
#XS Ineff= 2 , 0
       0 4879.09  220.48               0
Permanent Ineff=
       T       F
Bank Sta=4970.3,5020.3
XS Rating Curve= 0 ,0
Exp/Cntr=0.3,0.1

Type RM Length L Ch R = 1 ,44790   ,440,440,440
BEGIN DESCRIPTION:
BARBONE CREEK 84.0
END DESCRIPTION:
XS GIS Cut Line= 3
      2287192.83     13205154.12      2287165.05     13204473.61
      2286960.19     13203744.42
#Sta/Elev= 30
  4265.8  237.38  4268.3  236.86  4303.1   236.5  4483.2  231.32  4593.3   227.4
  4633.4  226.88  4693.4  224.54  4803.5  222.49  4823.5  221.38  4901.1  219.78
  4974.7  218.28  4985.1  216.11  4991.4  212.27  4993.6  209.49  4996.3  208.99
  4999.6  209.49  5005.8  212.43  5016.2   214.4  5030.6  215.22 5032.73  216.78
    5037  218.99  5078.5  218.25  5109.7   219.3    5172   219.5  5177.3  219.99
  5192.8   219.6  5292.1   220.4  5379.8  221.21  5475.8  223.16  5704.3  230.71
#Mann= 5 ,-1 , 0
  4265.8      .1       0  4901.1     .12       0  4993.6     .07       0
  4999.6     .12       0  5292.1      .1       0
Bank Sta=4985.1,5032.73
XS Rating Curve= 0 ,0
Exp/Cntr=0.3,0.1

Type RM Length L Ch R = 1 ,44350   ,356,356,356
BEGIN DESCRIPTION:
BARBONE CREEK 83.0
END DESCRIPTION:
XS GIS Cut Line= 4
      2287641.93     13204780.47      2287614.15     13204502.73
      2287232.21     13203777.04      2287114.25     13203641.73
#Sta/Elev= 30
    4406  232.52  4459.9  231.57  4496.8  229.69  4580.5  227.29  4709.2  222.35
  4864.2  218.16  4879.8  216.92  4901.9  216.48  4945.9  217.15  4951.7  214.58
  4962.3  213.92    4968  214.62  4974.3  210.77  4984.4  208.09  4993.9  208.07
  4996.6  207.57  4999.9  208.07  5006.4  211.63    5012  210.59  5019.5  213.86
  5028.4  216.82  5087.3  216.61  5138.6  217.71    5176  217.66  5265.2  218.82
  5287.2  219.82  5347.2  220.76  5457.8  224.17  5579.4  229.08  5684.7  231.92
#Mann= 5 ,-1 , 0
    4406      .1       0  4864.2     .12       0  4993.9     .07       0
  4999.9     .12       0    5176      .1       0
Bank Sta=4968,5019.5
XS Rating Curve= 0 ,0
Exp/Cntr=0.3,0.1

Type RM Length L Ch R = 1 ,43994   ,513,513,513
BEGIN DESCRIPTION:
BARBONE CREEK 82.0
END DESCRIPTION:
XS GIS Cut Line= 4
      2287973.65     13204655.79      2287883.37     13204287.73
      2287431.99     13203509.95      2287258.37     13203475.23
#Sta/Elev= 30
  4265.6     232  4295.4  231.73  4477.5  224.34  4583.7  221.02  4723.2   217.5
  4827.1  216.11  4911.5  214.75  4979.8  215.83 4985.45   213.6  4985.6  210.99
  4992.4  206.88  5001.1  205.68  5004.4  206.18  5007.1  208.97  5015.6  210.42
  5022.9  210.53  5028.7  209.72  5044.4  211.95  5060.1   213.1  5065.9  214.81
  5087.4  214.56    5109  215.47  5140.5  215.36  5205.4  216.72  5279.6     219
  5306.9  220.52  5328.4  220.51  5381.4  222.22  5526.3  227.55  5720.9  231.48
#Mann= 5 ,-1 , 0
  4265.6      .1       0  4827.1     .12       0  4985.6     .07       0
  5060.1     .12       0  5205.4      .1       0
#XS Ineff= 2 , 0
            4970  215.84
Permanent Ineff=
       F       F
Bank Sta=4985.45,5060.1
XS Rating Curve= 0 ,0
Exp/Cntr=0.3,0.1

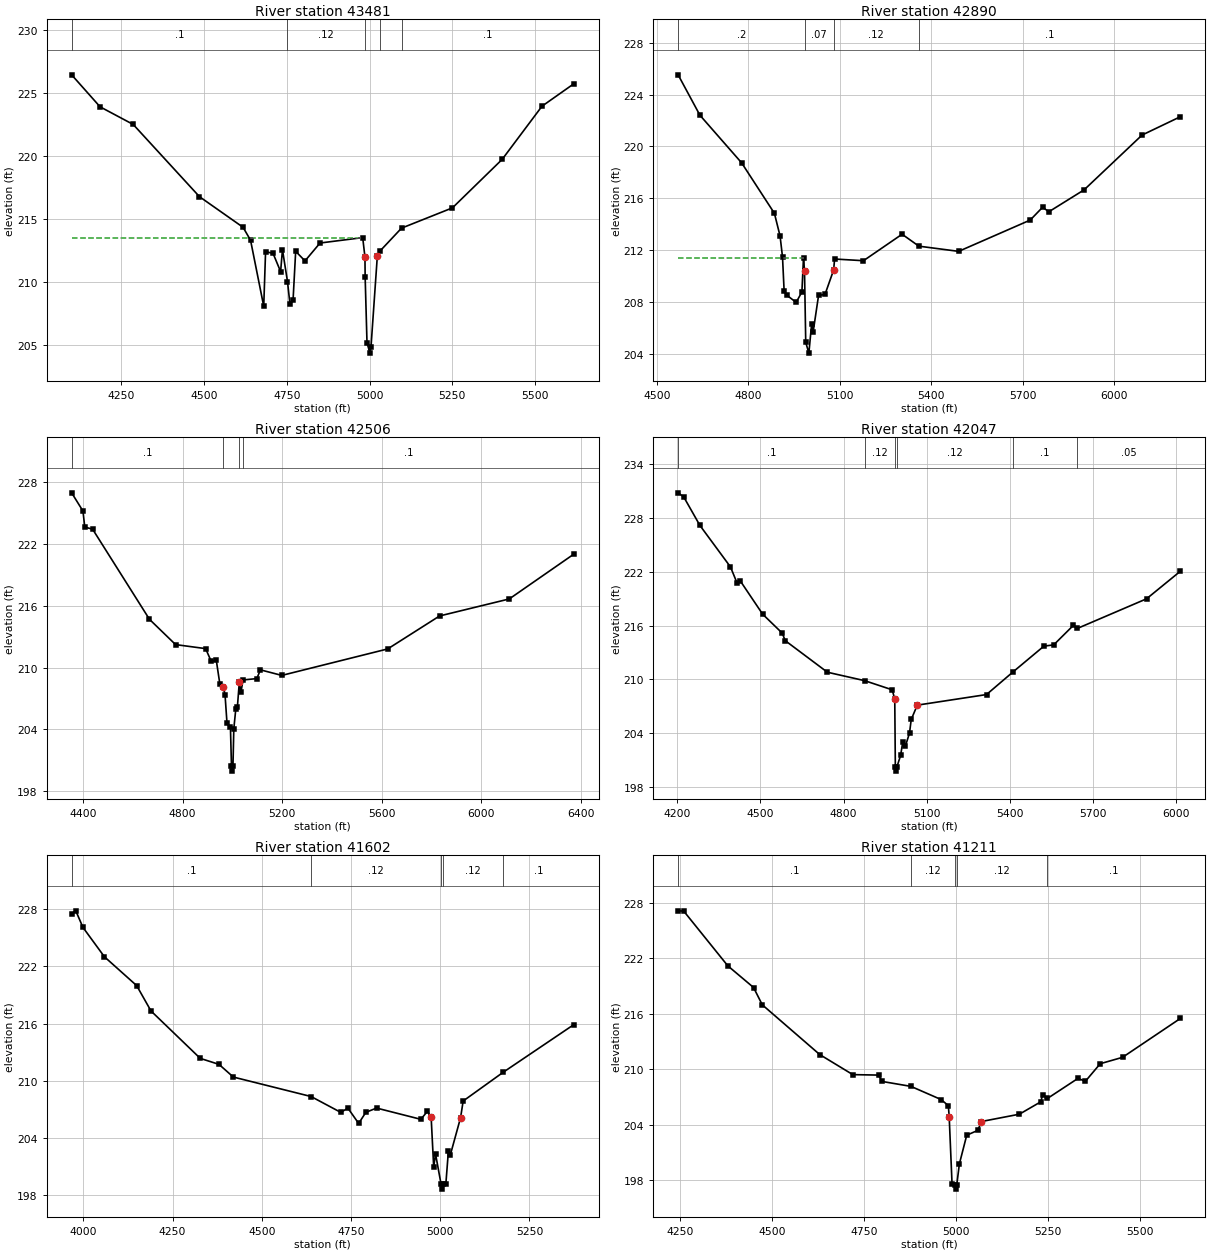
Type RM Length L Ch R = 1 ,43481   ,591,591,591
BEGIN DESCRIPTION:
BARBONE CREEK 81.0
END DESCRIPTION:
XS GIS Cut Line= 4
      2288221.79     13204502.75       2288207.9     13204068.71
      2287902.35     13203426.34      2287531.79     13203398.64
#Sta/Elev= 30
  4099.8  226.48  4185.7  223.94  4285.8  222.54  4485.9  216.81  4617.6  214.38
  4640.3  213.35  4680.1  208.11  4685.7  212.45  4708.4   212.3  4731.1  210.86
  4736.7   212.6  4751.9  210.07  4759.4  208.27  4768.7  208.59  4776.6  212.47
  4804.8  211.71  4850.2  213.13  4979.1  213.56 4985.91  212.02  4986.5  210.44
  4992.1  205.21    5001  204.39  5004.2  204.89  5023.4  212.13    5032  212.51
  5096.4  214.31  5250.2  215.92  5400.5  219.77  5520.8  223.99    5617  225.77
#Mann= 5 ,-1 , 0
  4099.8      .1       0  4751.9     .12       0 4985.91     .07       0
    5032     .12       0  5096.4      .1       0
#XS Ineff= 2 , 0
         4978.75  213.56
Permanent Ineff=
       F       F
Bank Sta=4985.91,5023.4
XS Rating Curve= 0 ,0
Exp/Cntr=0.3,0.1

Type RM Length L Ch R = 1 ,42890   ,384,384,384
BEGIN DESCRIPTION:
BARBONE CREEK 80.0
END DESCRIPTION:
XS GIS Cut Line= 3
       2288520.4     13204304.81      2288221.79     13203395.09
      2287544.68     13203259.67
#Sta/Elev= 30
  4569.3  225.52  4640.8  222.41  4777.7  218.74  4885.3  214.85  4903.9   213.1
  4911.9  211.48  4917.2  208.85    4925  208.56  4956.6  207.99  4975.5  208.79
  4980.8  211.44 4984.09   210.4  4988.1  204.91  4998.4  204.08  5007.4  206.32
  5012.6  205.74  5030.2  208.53  5051.3   208.6 5079.55  210.48  5082.9  211.33
  5177.6   211.2  5304.3  213.24  5359.4  212.32  5489.9  211.92  5724.7  214.33
  5765.5  215.32  5785.9  214.97  5901.7  216.66  6091.8  220.88  6217.3  222.29
#Mann= 4 ,-1 , 0
  4569.3      .2       0 4984.09     .07       0 5079.55     .12       0
  5359.4      .1       0
#XS Ineff= 2 , 0
         4980.89  211.44 5305.36          213.22
Permanent Ineff=
       F       F
Bank Sta=4984.09,5079.55
XS Rating Curve= 0 ,0
Exp/Cntr=0.3,0.1

Type RM Length L Ch R = 1 ,42506   ,459,459,459
BEGIN DESCRIPTION:
BARBONE CREEK 79.0
END DESCRIPTION:
XS GIS Cut Line= 4
      2288964.85     13204287.47      2288864.15     13203940.23
      2288263.46     13203214.54      2287548.16     13203193.71
#Sta/Elev= 30
  4353.6  226.96  4399.1  225.19  4406.3  223.64  4437.9  223.43  4666.6  214.68
  4771.5  212.23  4892.3  211.84  4914.3  210.63  4935.3  210.69  4949.7  208.37
    4964  208.16  4970.5   207.3  4978.3  204.58  4992.1   204.2  4996.2  200.45
  4998.9  199.95  5002.2  200.45  5005.6  204.06  5013.5  205.95    5020  206.17
  5027.8  208.61  5034.3  207.61  5042.7   208.8  5098.1  208.93  5112.5  209.78
  5198.5  209.24  5624.4  211.81    5833  215.01  6113.1  216.66  6372.8  221.01
#Mann= 4 ,-1 , 0
  4353.6      .1       0    4964     .07       0  5027.8     .12       0
  5042.7      .1       0
Bank Sta=4964,5027.8
XS Rating Curve= 0 ,0
Exp/Cntr=0.3,0.1

Type RM Length L Ch R = 1 ,42047   ,445,445,445
BEGIN DESCRIPTION:
BARBONE CREEK 78.0
END DESCRIPTION:
XS GIS Cut Line= 3
      2289187.71     13204346.81      2289037.72     13203546.85
      2288437.72     13202746.85
#Sta/Elev= 30
  4202.5  230.82  4222.8  230.36  4281.3  227.18  4391.5  222.56  4416.1  220.71
  4426.3  221.03  4507.7  217.29  4578.9  215.16  4589.1  214.34  4741.7  210.81
  4876.2  209.87  4975.7  208.85    4985  207.82  4987.1  200.28  4989.9  199.78
  4993.1  200.28  5006.2  201.54  5013.9  203.03  5023.7   202.6  5038.3  204.03
  5044.5  205.54  5066.4  207.14  5316.4  208.32  5411.2  210.82  5523.7  213.72
  5559.1  213.86  5629.9  216.03  5644.2  215.69  5894.5     219  6016.4  222.07
#Mann= 6 ,-1 , 0
  4202.5      .1       0  4876.2     .12       0  4987.1     .07       0
  4993.1     .12       0  5411.2      .1       0  5644.2     .05       0
Bank Sta=4985,5066.4
XS Rating Curve= 0 ,0
Exp/Cntr=0.3,0.1

Type RM Length L Ch R = 1 ,41602   ,391,391,391
BEGIN DESCRIPTION:
BARBONE CREEK 77.0
END DESCRIPTION:
XS GIS Cut Line= 4
      2289272.85     13204268.46      2289197.18      13203360.4
      2289265.75     13203085.59      2289278.77     13202872.93
#Sta/Elev= 30
    3967  227.53  3978.6  227.82  3998.7  226.08  4058.9     223  4149.2  219.98
  4189.4  217.32  4327.4  212.35    4380  211.72  4420.2  210.39    4638  208.35
  4721.2  206.69  4741.3  207.13  4771.4  205.53  4791.5  206.69  4821.6  207.14
  4945.6  205.96  4964.3   206.8  4974.6  206.16  4981.7  200.95  4986.9  202.32
  5002.5  199.14  5005.3  198.64  5008.5  199.14  5015.8  199.18    5023  202.68
  5028.2  202.21  5057.1  206.14  5064.3  207.88  5176.4  210.89  5374.5  215.89
#Mann= 5 ,-1 , 0
    3967      .1       0    4638     .12       0  5002.5     .07       0
  5008.5     .12       0  5176.4      .1       0
Bank Sta=4974.6,5057.1
XS Rating Curve= 0 ,0
Exp/Cntr=0.3,0.1

Type RM Length L Ch R = 1 ,41211   ,491,491,491
BEGIN DESCRIPTION:
BARBONE CREEK 76.0
END DESCRIPTION:
XS GIS Cut Line= 3
      2289369.05     13204272.18      2289382.94     13203411.11
      2289459.27     13202911.49
#Sta/Elev= 30
  4244.1  227.12  4259.4  227.09  4379.4  221.17  4449.4  218.83  4473.1  216.96
  4629.5  211.58  4719.5  209.41  4789.5  209.36  4799.5  208.67  4877.6  208.14
  4959.5  206.72  4979.5  206.06 4981.82  204.81  4989.5  197.63  4996.5  197.53
  4999.3  197.03  5002.5  197.53  5009.5  199.76  5029.5  202.86  5059.5  203.38
  5069.5  204.34  5172.7  205.13    5231  206.47  5236.2  207.26    5249  206.83
  5332.1     209  5352.4  208.69  5392.8  210.59  5453.5  211.28  5610.7  215.48
#Mann= 5 ,-1 , 0
  4244.1      .1       0  4877.6     .12       0  4996.5     .07       0
  5002.5     .12       0    5249      .1       0
Bank Sta=4981.82,5069.5
XS Rating Curve= 0 ,0
Exp/Cntr=0.3,0.1

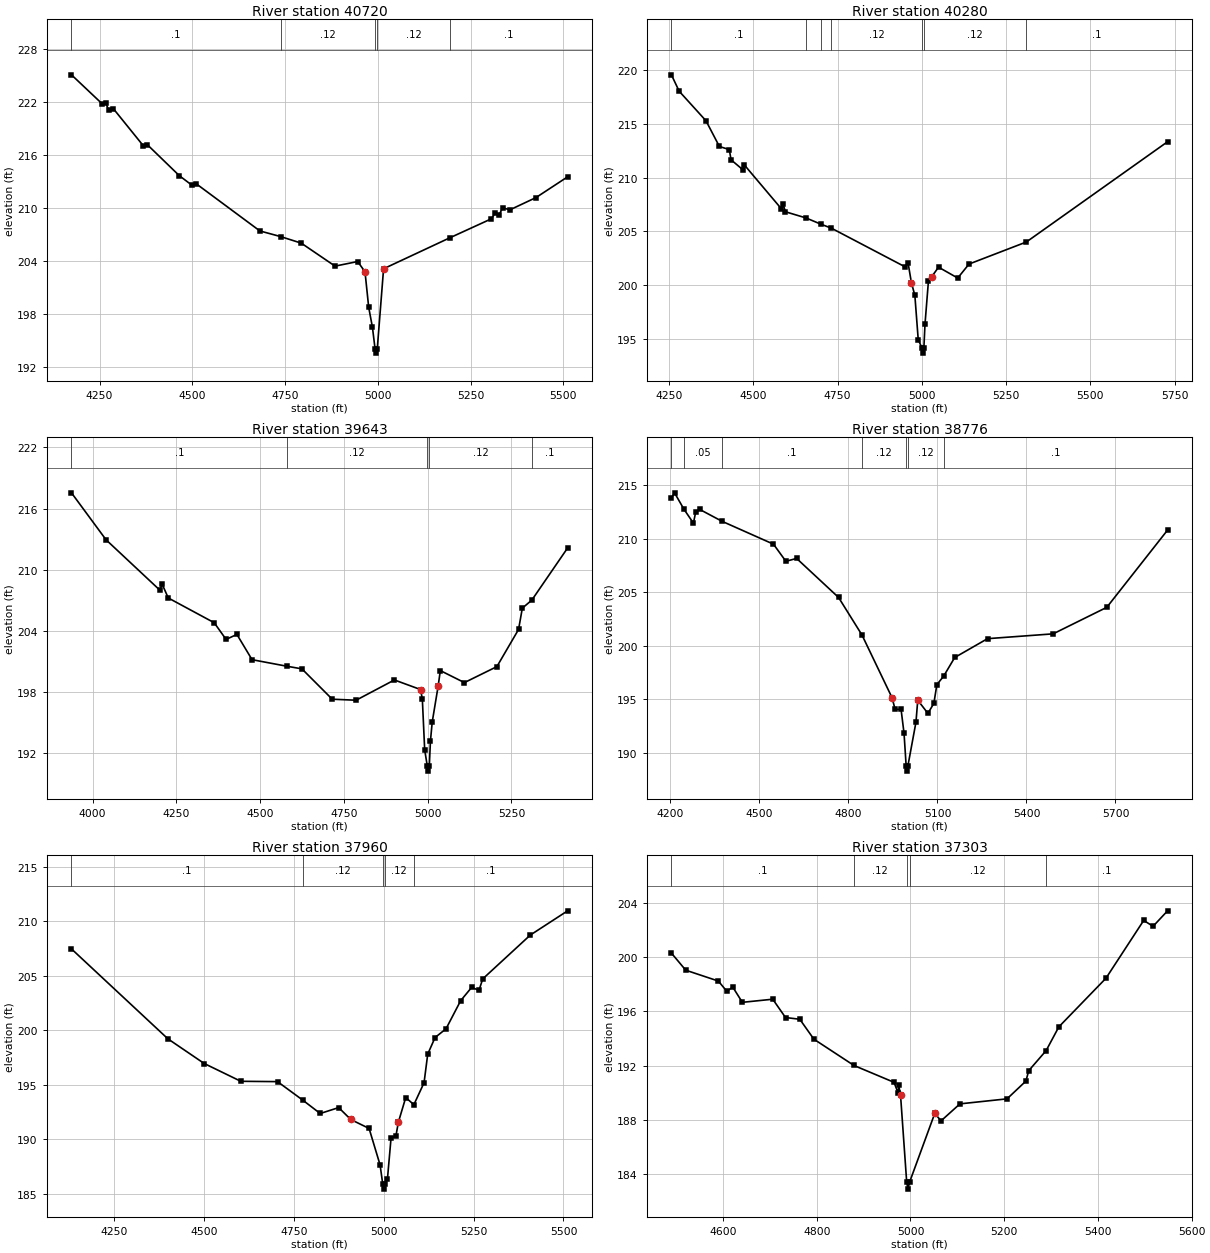
Type RM Length L Ch R = 1 ,40720   ,440,440,440
BEGIN DESCRIPTION:
BARBONE CREEK 75.0
END DESCRIPTION:
XS GIS Cut Line= 3
      2289556.55     13204258.33      2289678.08     13203501.39
      2289639.88      13202931.9
#Sta/Elev= 30
  4174.4   225.1  4256.9  221.82    4267  221.92  4274.3  221.08  4287.3  221.26
  4368.3  217.04  4378.5  217.19  4465.1  213.66    4500  212.55  4510.1  212.76
  4682.3  207.39  4738.2  206.75  4793.7  206.01  4884.9   203.4  4945.8  203.92
  4965.6  202.76  4975.6  198.72  4985.7  196.45  4992.7  194.03  4995.4  193.53
  4998.7  194.03  5015.7   203.1  5195.2  206.63  5306.4  208.77  5315.7  209.38
  5326.4  209.15  5336.5  210.01  5356.5  209.79  5426.7  211.18  5511.8  213.53
#Mann= 5 ,-1 , 0
  4174.4      .1       0  4738.2     .12       0  4992.7     .07       0
  4998.7     .12       0  5195.2      .1       0
Bank Sta=4965.6,5015.7
XS Rating Curve= 0 ,0
Exp/Cntr=0.3,0.1

Type RM Length L Ch R = 1 ,40280   ,637,637,637
BEGIN DESCRIPTION:
BARBONE CREEK 74.0
END DESCRIPTION:
XS GIS Cut Line= 4
      2290006.51      13204183.3      2290114.15     13203787.46
      2290037.77     13202978.43      2289885.52      13202781.2
#Sta/Elev= 30
  4257.1  219.55    4280  218.03  4359.6  215.28  4399.4  212.89  4428.8   212.6
    4434  211.65  4468.6  210.74  4473.8  211.16  4582.7  207.12  4587.9  207.55
  4595.4  206.82    4656  206.25  4699.6  205.68    4732  205.29  4949.2  201.72
  4959.2  202.06  4969.3  200.19  4979.3  199.06  4989.3  194.94  5000.1  194.18
  5002.8  193.68  5006.1  194.18  5009.4  196.37  5019.5  200.34  5029.5  200.79
  5049.6  201.67  5106.5  200.66    5140  201.96  5310.1  204.01  5729.1  213.33
#Mann= 7 ,-1 , 0
  4257.1      .1       0    4656     .12       0  4699.6      .1       0
    4732     .12       0  5000.1     .07       0  5006.1     .12       0
  5310.1      .1       0
Bank Sta=4969.3,5029.5
XS Rating Curve= 0 ,0
Exp/Cntr=0.3,0.1

Type RM Length L Ch R = 1 ,39643   ,867,867,867
BEGIN DESCRIPTION:
BARBONE CREEK 73.0
END DESCRIPTION:
XS GIS Cut Line= 2
       2290173.2     13204145.05      2290724.91     13202770.97
#Sta/Elev= 30
  3937.1  217.54  4040.3  212.93  4201.7  207.96  4207.1  208.62  4225.9  207.22
    4363  204.79  4398.5  203.15  4430.8  203.64    4476  201.16  4581.1  200.51
  4624.8  200.26  4715.3  197.28  4786.5  197.18  4900.8  199.17  4978.8  198.23
  4984.2   197.3  4991.2  192.31    4999  190.72  5001.7  190.22    5005  190.72
  5008.4  193.18  5013.7  195.04 5031.36  198.56  5037.9  200.09  5109.7  198.91
  5206.7  200.48  5271.4  204.13  5282.6  206.22    5311  207.01  5417.8  212.13
#Mann= 5 ,-1 , 0
  3937.1      .1       0  4581.1     .12       0    4999     .07       0
    5005     .12       0    5311      .1       0
Bank Sta=4978.8,5031.36
XS Rating Curve= 0 ,0
Exp/Cntr=0.3,0.1

Type RM Length L Ch R = 1 ,38776   ,816,816,816
BEGIN DESCRIPTION:
BARBONE CREEK 72.0
END DESCRIPTION:
XS GIS Cut Line= 3
      2290585.22     13204339.03      2291019.22     13203835.59
       2290919.4     13202833.03
#Sta/Elev= 30
  4203.4  213.79  4213.9  214.27  4245.3  212.75  4277.5  211.44  4285.2  212.47
  4298.7  212.72  4373.9  211.61  4547.4  209.47  4589.2  207.87  4625.3  208.14
  4766.8  204.49  4845.7  200.98  4947.2  195.11  4957.3  194.03  4977.4  194.03
  4987.4  191.79  4994.5  188.76  4997.2  188.26  5000.5  188.76  5027.6  192.84
  5033.6  194.89  5067.8  193.66  5087.9  194.59    5098  196.34    5121  197.14
  5158.2  198.88  5268.8  200.64  5489.9  201.09  5670.8  203.57  5875.6  210.79
#Mann= 7 ,-1 , 0
  4203.4      .1       0  4245.3     .05       0  4373.9      .1       0
  4845.7     .12       0  4994.5     .07       0  5000.5     .12       0
    5121      .1       0
Bank Sta=4947.2,5033.6
XS Rating Curve= 0 ,0
Exp/Cntr=0.3,0.1

Type RM Length L Ch R = 1 ,37960   ,657,657,657
BEGIN DESCRIPTION:
BARBONE CREEK 71.0
END DESCRIPTION:
XS GIS Cut Line= 3
      2291586.38     13204082.63      2291537.77     13203728.43
      2291339.86     13202724.99
#Sta/Elev= 30
  4131.3  207.45  4399.6  199.21  4500.6  196.95  4602.5  195.32  4704.5  195.29
  4774.1  193.61  4823.3  192.37  4874.7  192.91  4908.3  191.82  4959.3     191
  4989.9  187.65  4997.1  185.94  4999.8  185.44  5003.1  185.94  5010.3  186.36
  5020.4  190.14  5033.7  190.28  5040.8  191.58  5061.2  193.83  5083.9  193.18
  5112.2  195.19  5122.4  197.81  5142.8  199.33  5173.3  200.13  5214.1  202.71
  5244.7  203.93  5265.1  203.65  5275.3   204.7  5407.8  208.72  5511.6  210.94
#Mann= 5 ,-1 , 0
  4131.3      .1       0  4774.1     .12       0  4997.1     .07       0
  5003.1     .12       0  5083.9      .1       0
Bank Sta=4908.3,5040.8
XS Rating Curve= 0 ,0
Exp/Cntr=0.3,0.1

Type RM Length L Ch R = 1 ,37303   ,496,496,496
BEGIN DESCRIPTION:
BARBONE CREEK 70.0
END DESCRIPTION:
XS GIS Cut Line= 3
       2291846.8     13203884.65      2291902.35     13203631.21
      2291982.21     13202836.07
#Sta/Elev= 30
    4490   200.3  4520.6  199.04  4590.1  198.24  4608.3  197.48  4620.8   197.8
  4641.3  196.67  4706.2   196.9  4733.4  195.55  4763.9  195.42    4794  193.95
  4879.6  192.01  4964.9  190.77 4974.09  189.95  4974.9  190.56 4978.86  189.82
    4992  183.39  4994.8  182.89    4998  183.39  5051.8  188.47  5065.4  187.93
  5105.6  189.18  5206.1  189.55  5246.3  190.86  5252.4  191.63  5289.5  193.11
  5316.6  194.86  5417.2  198.45  5497.6  202.71  5517.7  202.28  5548.6  203.42
#Mann= 5 ,-1 , 0
    4490      .1       0  4879.6     .12       0    4992     .07       0
    4998     .12       0  5289.5      .1       0
Bank Sta=4978.86,5051.8
XS Rating Curve= 0 ,0
Exp/Cntr=0.3,0.1