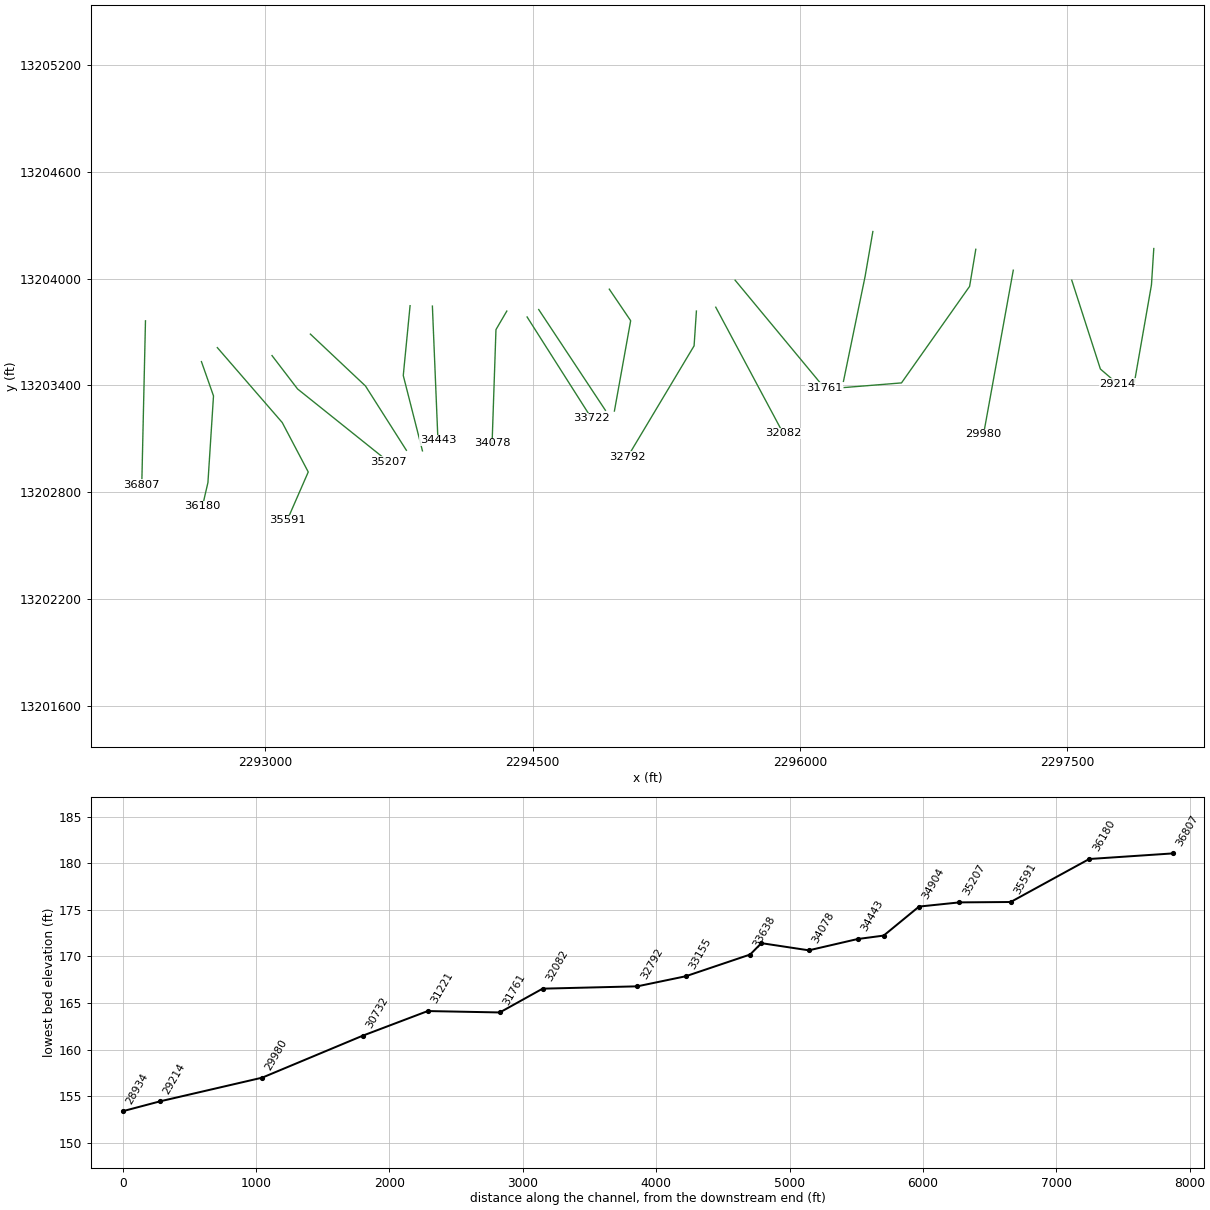
HEC-RAS study BARBONE CREEK.prj: BARBONE CREEK Base Level Engineering

--- BARBONE CREEK.g01 (geometry) --- (continued)

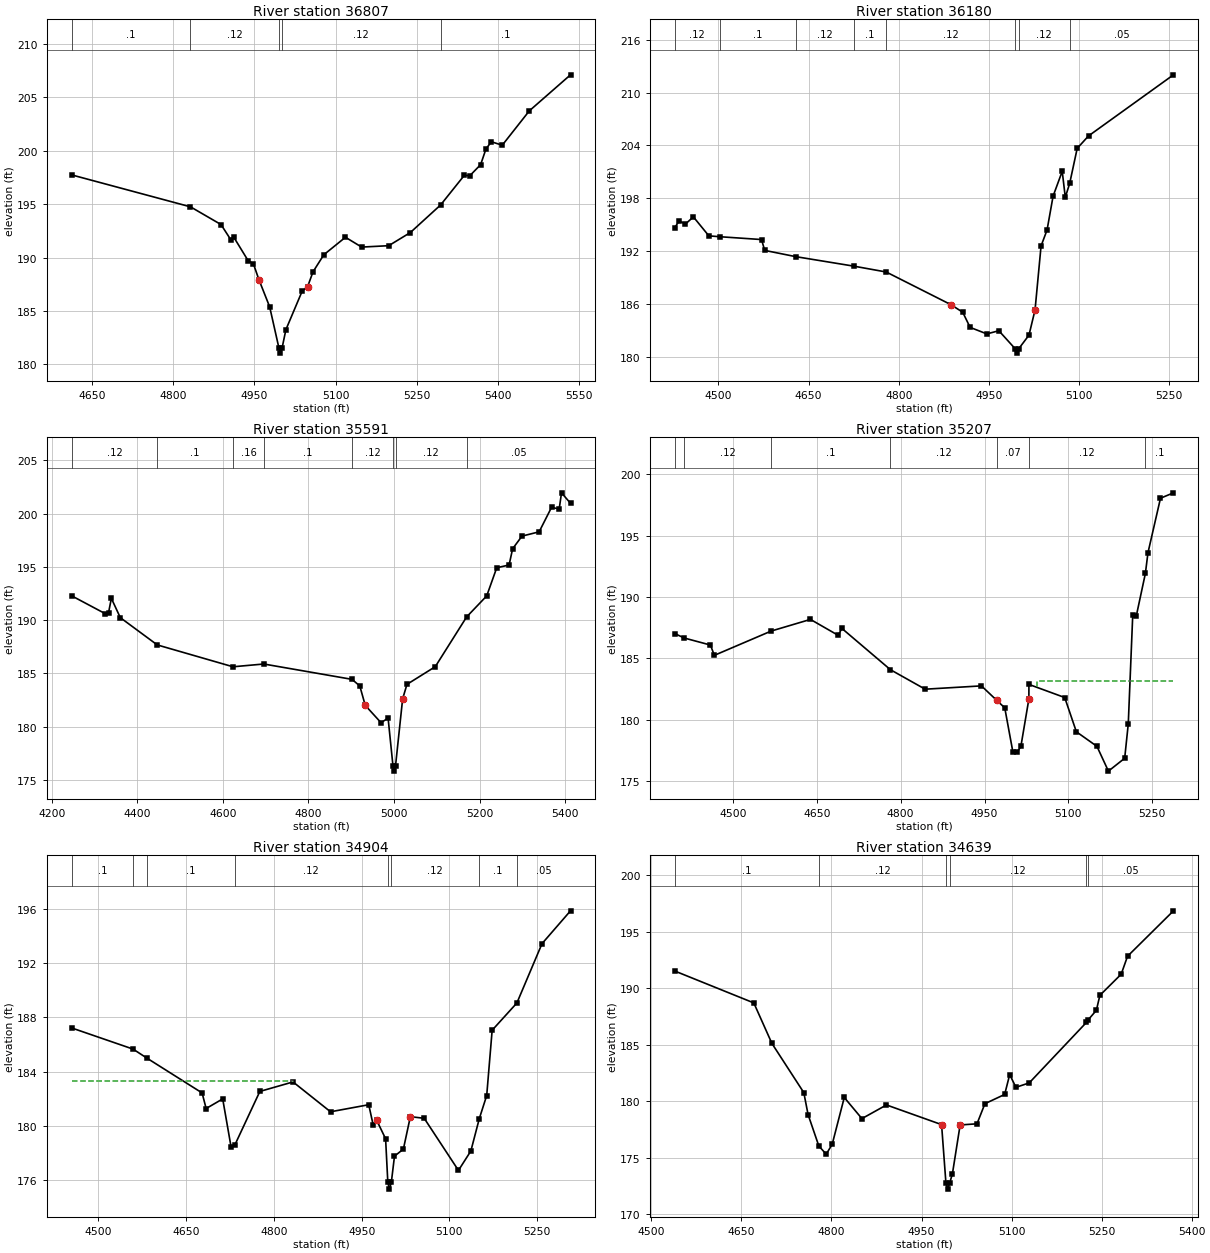
Type RM Length L Ch R = 1 ,36807   ,627,627,627
BEGIN DESCRIPTION:
BARBONE CREEK 69.0
END DESCRIPTION:
XS GIS Cut Line= 2
      2292329.43      13203763.1      2292308.63     13202840.74
#Sta/Elev= 30
  4611.9  197.74  4831.7  194.75  4888.2  193.09  4906.4  191.66  4911.4  191.94
  4938.2  189.72  4948.2   189.4  4958.2  187.94  4978.2  185.38  4995.2  181.55
    4998  181.05  5001.2  181.55  5008.2  183.25  5038.3  186.86  5048.3  187.27
  5058.3  188.66  5078.3  190.26  5118.3   191.9  5148.3  190.98  5198.3  191.11
  5238.3  192.34  5294.2  194.92  5338.3  197.71  5348.1  197.65  5368.3   198.7
  5378.3  200.19  5388.3  200.84  5408.3  200.52  5458.4  203.74  5534.5  207.11
#Mann= 5 ,-1 , 0
  4611.9      .1       0  4831.7     .12       0  4995.2     .07       0
  5001.2     .12       0  5294.2      .1       0
Bank Sta=4958.2,5048.3
XS Rating Curve= 0 ,0
Exp/Cntr=0.3,0.1

Type RM Length L Ch R = 1 ,36180   ,589,589,589
BEGIN DESCRIPTION:
BARBONE CREEK 68.0
END DESCRIPTION:
XS GIS Cut Line= 4
      2292643.24     13203533.96      2292710.94     13203341.28
      2292679.69      13202854.3      2292648.78     13202720.33
#Sta/Elev= 30
  4427.2  194.64  4434.7  195.44  4445.3  195.09  4458.5   195.9  4484.2  193.75
  4502.5  193.65  4571.8  193.33  4577.1   192.1  4628.8  191.39  4725.6  190.31
  4779.2  189.65  4886.4  185.96  4906.4  185.09  4918.7  183.37  4946.5  182.63
  4966.5  182.99  4993.6  180.95  4996.4  180.45  4999.6  180.95  5016.6  182.49
  5026.7  185.35  5036.7   192.6  5046.7  194.42  5056.7  198.25  5071.9  201.07
    5077  198.12  5084.3   199.7  5096.8  203.67  5115.6  205.08  5256.9  212.01
#Mann= 8 ,-1 , 0
  4427.2     .12       0  4502.5      .1       0  4628.8     .12       0
  4725.6      .1       0  4779.2     .12       0  4993.6     .07       0
  4999.6     .12       0  5084.3     .05       0
Bank Sta=4886.4,5026.7
XS Rating Curve= 0 ,0
Exp/Cntr=0.3,0.1

Type RM Length L Ch R = 1 ,35591   ,384,384,384
BEGIN DESCRIPTION:
BARBONE CREEK 67.0
END DESCRIPTION:
XS GIS Cut Line= 4
       2292732.4     13203612.65      2293096.48     13203191.49
      2293242.31     13202913.71      2293124.25     13202642.87
#Sta/Elev= 30
  4246.5  192.29  4325.2  190.61  4332.8   190.7  4339.4  192.05  4360.3  190.24
  4446.7  187.68  4623.7  185.63  4695.6  185.89  4901.8  184.45    4920  183.83
  4932.7  182.01  4969.7  180.38  4986.1  180.82  4997.5  176.34  5000.2  175.84
  5003.5  176.34 5020.11  182.62  5030.2  183.98  5096.4  185.64  5169.7  190.31
  5216.6  192.28    5240  194.92  5268.9  195.18  5277.1   196.7    5299  197.89
  5339.1  198.29    5368  200.58    5386  200.44  5391.4  201.95  5412.4  200.97
#Mann= 8 ,-1 , 0
  4246.5     .12       0  4446.7      .1       0  4623.7     .16       0
  4695.6      .1       0  4901.8     .12       0  4997.5     .07       0
  5003.5     .12       0  5169.7     .05       0
Bank Sta=4932.7,5020.11
XS Rating Curve= 0 ,0
Exp/Cntr=0.3,0.1

Type RM Length L Ch R = 1 ,35207   ,303,303,303
BEGIN DESCRIPTION:
BARBONE CREEK 66.0
END DESCRIPTION:
XS GIS Cut Line= 3
      2293039.09     13203567.81       2293182.3     13203380.34
      2293694.03     13202969.91
#Sta/Elev= 30
  4395.9  187.02  4413.4  186.65    4460  186.08    4467  185.24  4568.6  187.22
  4638.8  188.17  4688.5  186.87  4694.9  187.44  4781.8  184.07  4843.9  182.48
  4944.5  182.75  4972.1  181.56  4986.2  180.96  5000.6  177.39  5008.5  177.36
    5015  177.81 5029.31  181.68  5029.4  182.87  5093.4   181.8  5114.2  179.01
    5151  177.82  5171.5   175.8  5200.6  176.85    5207  179.65    5215  188.54
  5221.4  188.46  5237.6  191.92  5242.2   193.6  5264.6  198.05  5287.8  198.49
#Mann= 7 ,-1 , 0
  4395.9     .16       0  4413.4     .12       0  4568.6      .1       0
  4781.8     .12       0  4972.1     .07       0  5029.4     .12       0
  5237.6      .1       0
#XS Ineff= 2 , 0
       0                 5044.05       0  183.13
Permanent Ineff=
       F       T
Bank Sta=4972.1,5029.31
XS Rating Curve= 0 ,0
Exp/Cntr=0.3,0.1

Type RM Length L Ch R = 1 ,34904   ,265,265,265
BEGIN DESCRIPTION:
Mapping XS e395aa46
END DESCRIPTION:
XS GIS Cut Line= 3
      2293254.34     13203688.51      2293563.37     13203396.83
      2293792.52     13203035.75
#Sta/Elev= 30
  4454.3  187.23  4559.3  185.67  4582.8  185.01  4677.3  182.44  4684.2  181.29
  4712.5     182  4726.7  178.49  4732.9  178.57    4776  182.55  4832.7  183.25
  4896.8  181.05  4962.1  181.57  4969.7  180.07  4975.6  180.43  4990.9  179.06
  4994.7  175.85  4997.4  175.35  5000.7  175.85  5006.1  177.78  5021.3   178.3
  5033.2  180.69  5056.9  180.57  5115.4  176.73  5136.6  178.16    5151  180.54
  5163.7  182.25    5173  187.06  5215.3  189.07  5258.2  193.44  5306.9  195.86
#Mann= 8 ,-1 , 0
  4454.3      .1       0  4559.3     .12       0  4582.8      .1       0
  4732.9     .12       0  4994.7     .07       0  5000.7     .12       0
    5151      .1       0  5215.3     .05       0
#XS Ineff= 2 , 0
       0 4832.39  183.29               0
Permanent Ineff=
       T       F
Bank Sta=4975.6,5033.2
XS Rating Curve= 0 ,0
Exp/Cntr=0.3,0.1

Type RM Length L Ch R = 1 ,34639   ,196,196,196
BEGIN DESCRIPTION:
BARBONE CREEK 65.0
END DESCRIPTION:
XS GIS Cut Line= 3
      2293813.38     13203848.24      2293775.18     13203455.86
      2293882.77     13203032.45
#Sta/Elev= 30
  4538.6  191.55  4670.6  188.72  4700.7  185.14  4753.9  180.78    4761  178.84
  4778.9  176.06  4791.2  175.33  4801.2  176.21  4821.3  180.35  4850.7  178.48
  4891.6  179.69  4983.4  177.95  4990.7  172.74  4993.5  172.24  4996.7  172.74
  5001.5  173.61  5014.3  177.92  5042.4  178.02  5055.6   179.8  5088.5  180.62
  5096.9  182.38  5107.2  181.25  5129.4  181.64  5224.8     187  5227.6  187.22
  5241.3  188.07  5247.1  189.39  5282.6  191.26  5293.2  192.85  5369.7  196.87
#Mann= 6 ,-1 , 0
  4538.6      .1       0  4778.9     .12       0  4990.7     .07       0
  4996.7     .12       0  5224.8      .1       0  5227.6     .05       0
Bank Sta=4983.4,5014.3
XS Rating Curve= 0 ,0
Exp/Cntr=0.3,0.1

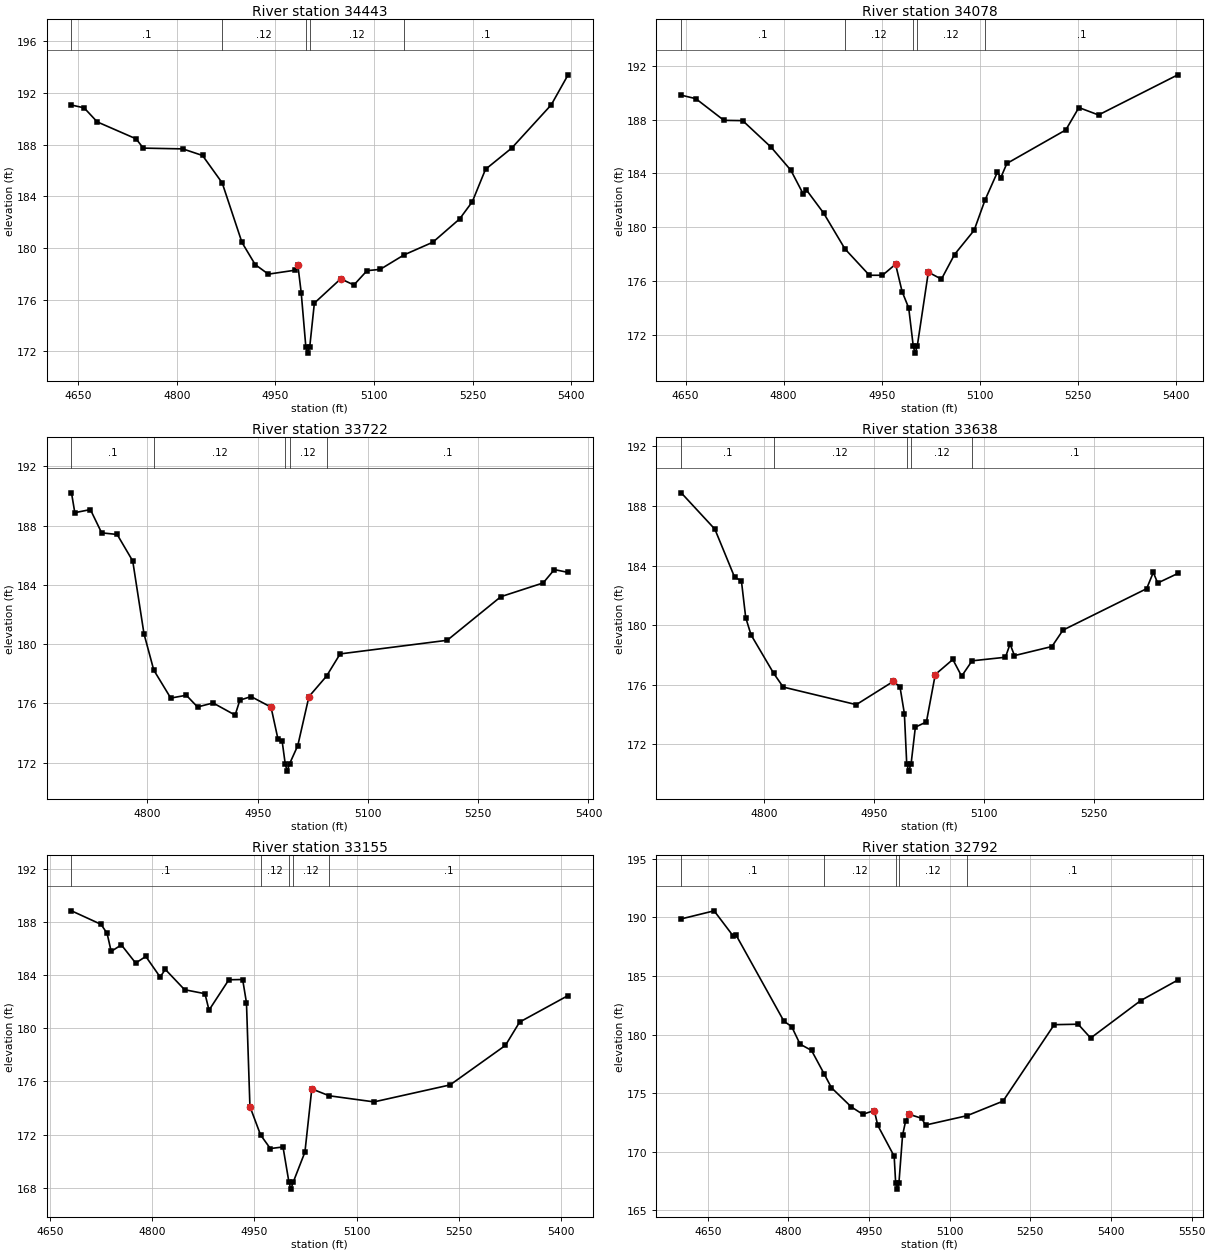
Type RM Length L Ch R = 1 ,34443   ,365,365,365
BEGIN DESCRIPTION:
Mapping XS 62927bda
END DESCRIPTION:
XS GIS Cut Line= 2
      2293938.49     13203845.97      2293969.72     13203091.31
#Sta/Elev= 30
  4639.8  191.06  4658.9  190.85  4678.9  189.76    4738  188.45    4749  187.73
  4809.1  187.67  4839.1  187.16    4869  185.04  4899.1  180.43  4919.2  178.72
  4939.2  177.98  4979.1  178.28  4984.1  178.67  4989.2  176.54  4996.2  172.37
    4999  171.87  5002.2  172.37  5009.2  175.74  5049.3  177.62  5069.3  177.14
  5089.3  178.25  5109.3  178.35  5145.6  179.47  5189.4  180.45  5230.1  182.25
  5249.4  183.58  5269.5  186.09  5309.5  187.74  5369.5  191.08  5395.1   193.4
#Mann= 5 ,-1 , 0
  4639.8      .1       0    4869     .12       0  4996.2     .07       0
  5002.2     .12       0  5145.6      .1       0
Bank Sta=4984.1,5049.3
XS Rating Curve= 0 ,0
Exp/Cntr=0.3,0.1

Type RM Length L Ch R = 1 ,34078   ,356,356,356
BEGIN DESCRIPTION:
BARBONE CREEK 64.0
END DESCRIPTION:
XS GIS Cut Line= 3
      2294355.84     13203817.95      2294295.08     13203713.79
      2294273.38     13203075.75
#Sta/Elev= 30
  4643.4  189.81  4665.7  189.55  4708.7  187.94  4737.3  187.92  4780.9  185.94
  4810.9  184.24  4829.7  182.49  4834.7  182.78    4861  181.06  4893.6   178.4
    4931  176.44    4951  176.44    4971  177.26    4981  175.23  4991.1  174.01
  4998.1  171.16  5000.8  170.66  5004.1  171.16  5021.1  176.67  5041.1  176.15
  5061.1  177.98  5091.1  179.78  5107.7  182.02  5126.8  184.11  5131.8  183.68
  5141.1  184.74  5231.2  187.23  5251.2  188.89  5281.2  188.34  5402.4  191.32
#Mann= 5 ,-1 , 0
  4643.4      .1       0  4893.6     .12       0  4998.1     .07       0
  5004.1     .12       0  5107.7      .1       0
Bank Sta=4971,5021.1
XS Rating Curve= 0 ,0
Exp/Cntr=0.3,0.1

Type RM Length L Ch R = 1 ,33722   ,84,84,84
BEGIN DESCRIPTION:
Mapping XS 1fc600c9
END DESCRIPTION:
XS GIS Cut Line= 2
      2294469.74     13203784.81      2294831.72     13203214.49
#Sta/Elev= 30
  4696.8  190.21  4701.3  188.87  4722.5  189.08  4737.8  187.51  4758.9   187.4
  4780.1  185.61  4795.4   180.7  4808.7  178.25  4831.8  176.36    4853  176.55
  4868.2  175.76  4889.4  176.03  4919.4  175.21  4925.8  176.22  4941.1  176.46
  4968.2  175.75  4977.5  173.63  4983.4  173.43  4987.5  171.93  4990.2  171.43
  4993.5  171.93  5004.6  173.15  5019.8  176.46  5043.7  177.84  5062.2  179.34
  5207.9  180.26  5280.8   183.2  5338.4  184.13  5353.6  185.03  5372.3  184.84
#Mann= 5 ,-1 , 0
  4696.8      .1       0  4808.7     .12       0  4987.5     .07       0
  4993.5     .12       0  5043.7      .1       0
Bank Sta=4968.2,5019.8
XS Rating Curve= 0 ,0
Exp/Cntr=0.3,0.1

Type RM Length L Ch R = 1 ,33638   ,483,483,483
BEGIN DESCRIPTION:
BARBONE CREEK 63.0
END DESCRIPTION:
XS GIS Cut Line= 2
      2294534.85     13203826.47      2294908.81     13203260.33
#Sta/Elev= 30
  4686.5  188.88  4732.5  186.44  4759.6   183.2  4768.7  182.99  4774.6  180.51
  4781.9  179.35  4812.7  176.78  4825.8  175.85  4925.7  174.67  4976.3  176.23
  4985.4  175.86  4991.4  174.07  4994.6  170.71  4997.4  170.21  5000.6  170.71
  5006.4  173.16  5021.5  173.51  5033.6  176.69  5057.6   177.7  5069.6  176.58
  5083.9  177.61  5129.5  177.85  5135.8  178.74  5141.8  177.96    5193  178.57
  5208.1  179.67  5322.4  182.45  5331.5  183.54  5337.5  182.83    5365  183.47
#Mann= 5 ,-1 , 0
  4686.5      .1       0  4812.7     .12       0  4994.6     .07       0
  5000.6     .12       0  5083.9      .1       0
Bank Sta=4976.3,5033.6
XS Rating Curve= 0 ,0
Exp/Cntr=0.3,0.1

Type RM Length L Ch R = 1 ,33155   ,363,363,363
BEGIN DESCRIPTION:
BARBONE CREEK 62.0
END DESCRIPTION:
XS GIS Cut Line= 3
      2294930.67     13203941.07      2295050.47     13203763.97
      2294959.33      13203256.2
#Sta/Elev= 30
  4681.1  188.87  4724.5  187.85  4733.4  187.17  4739.4  185.81  4754.4   186.3
  4775.4  184.93  4790.3  185.43  4811.3  183.88    4819  184.45  4847.3  182.92
  4877.2  182.62  4883.2  181.38  4912.3  183.67  4932.6  183.69  4938.2  181.94
  4943.3  174.11  4958.9  171.97  4973.3  170.94  4991.9  171.06  5000.7  168.38
  5003.5  167.88  5006.7  168.38  5024.1  170.67  5034.2  175.44  5059.8  174.92
  5125.7  174.46  5237.4  175.74  5318.7  178.72  5339.6  180.48  5410.8  182.48
#Mann= 5 ,-1 , 0
  4681.1      .1       0  4958.9     .12       0  5000.7     .07       0
  5006.7     .12       0  5059.8      .1       0
Bank Sta=4943.3,5034.2
XS Rating Curve= 0 ,0
Exp/Cntr=0.3,0.1

Type RM Length L Ch R = 1 ,32792   ,710,710,710
BEGIN DESCRIPTION:
BARBONE CREEK 61.0
END DESCRIPTION:
XS GIS Cut Line= 3
      2295419.21     13203817.96      2295406.19     13203622.64
      2295032.94     13202997.67
#Sta/Elev= 30
  4600.6  189.87  4661.8  190.56  4697.6  188.39  4702.6  188.49  4791.7  181.13
    4806  180.68  4821.6  179.18    4843  178.64  4866.2  176.66    4880  175.46
  4916.9  173.82  4938.3  173.19  4959.7  173.51  4966.2  172.24  4996.7  169.61
  4999.5   167.3  5002.3   166.8  5005.5   167.3  5012.3   171.4  5018.1  172.63
  5024.4  173.19  5047.7  172.85  5055.1  172.27  5132.3  173.07  5199.1  174.31
  5294.4  180.84  5338.9  180.88  5362.2   179.7  5455.4   182.9  5524.3  184.65
#Mann= 5 ,-1 , 0
  4600.6      .1       0  4866.2     .12       0  4999.5     .07       0
  5005.5     .12       0  5132.3      .1       0
Bank Sta=4959.7,5024.4
XS Rating Curve= 0 ,0
Exp/Cntr=0.3,0.1

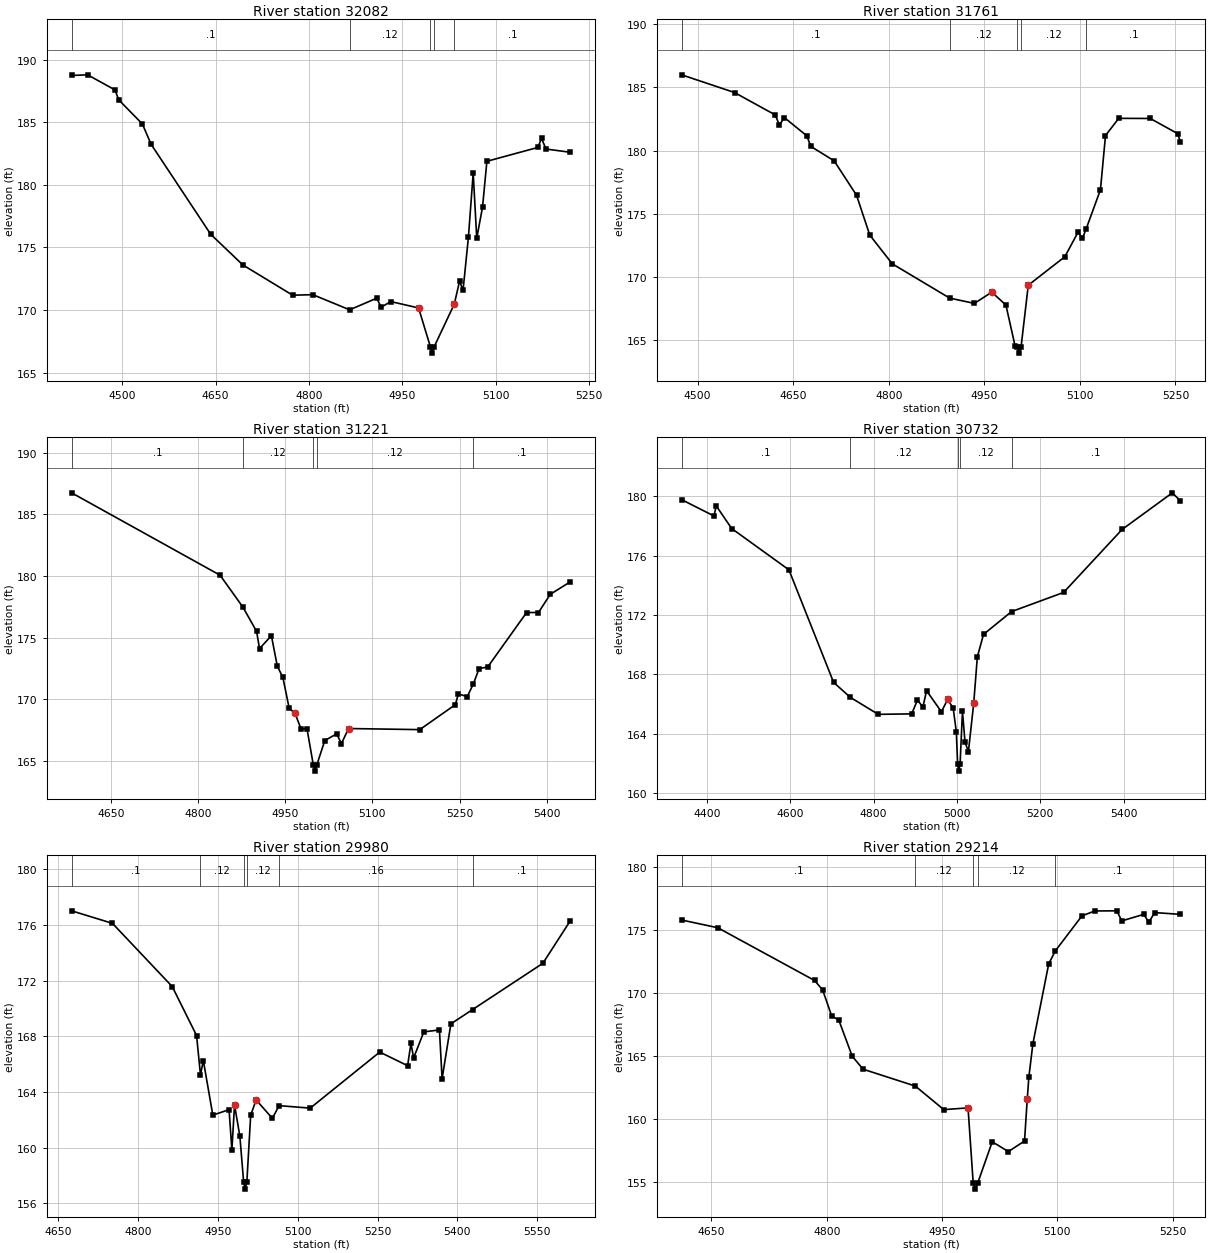
Type RM Length L Ch R = 1 ,32082   ,321,321,321
BEGIN DESCRIPTION:
BARBONE CREEK 60.0
END DESCRIPTION:
XS GIS Cut Line= 2
      2295527.74     13203839.62      2295905.33     13203132.18
#Sta/Elev= 30
  4418.5  188.74  4444.3  188.79  4488.4  187.58  4494.1   186.8  4532.3  184.86
  4546.3  183.24  4642.1  176.05  4693.7   173.6  4773.8  171.18  4806.4  171.22
  4865.5  170.01    4909  170.94  4916.1  170.22  4931.7  170.67  4976.3  170.16
  4995.3  167.05    4998  166.55  5001.3  167.05  5033.7  170.47  5042.2   172.3
  5047.8  171.58  5056.4  175.81  5064.1  180.94  5069.8  175.73  5079.1  178.22
  5086.1  181.88  5168.2  182.99  5173.9  183.72  5181.1  182.86  5220.4   182.6
#Mann= 5 ,-1 , 0
  4418.5      .1       0  4865.5     .12       0  4995.3     .07       0
  5001.3     .12       0  5033.7      .1       0
Bank Sta=4976.3,5033.7
XS Rating Curve= 0 ,0
Exp/Cntr=0.3,0.1

Type RM Length L Ch R = 1 ,31761   ,540,540,540
BEGIN DESCRIPTION:
BARBONE CREEK 59.0
END DESCRIPTION:
XS GIS Cut Line= 2
      2295636.23     13203991.55      2296135.36     13203388.26
#Sta/Elev= 30
  4474.9     186  4557.9   184.6  4621.8  182.83  4628.3  182.03  4636.1  182.62
  4671.3  181.18  4677.7  180.34  4714.3   179.2  4749.4  176.48  4770.2  173.33
  4805.5  171.06  4895.6  168.35  4934.4  167.93  4961.7  168.82  4983.9   167.8
  4998.2  164.58  5001.7   164.5  5004.4     164  5007.7   164.5    5019  169.37
  5076.4  171.62  5097.2  173.57    5104  173.08  5109.7   173.8  5132.3  176.92
  5140.2   181.2    5161  182.56  5210.5  182.55  5253.5  181.35  5257.9  180.69
#Mann= 5 ,-1 , 0
  4474.9      .1       0  4895.6     .12       0  5001.7     .07       0
  5007.7     .12       0  5109.7      .1       0
Bank Sta=4961.7,5019
XS Rating Curve= 0 ,0
Exp/Cntr=0.3,0.1

Type RM Length L Ch R = 1 ,31221   ,489,489,489
BEGIN DESCRIPTION:
BARBONE CREEK 58.0
END DESCRIPTION:
XS GIS Cut Line= 3
      2296408.79     13204264.99      2296365.39     13204013.27
      2296243.86     13203422.98
#Sta/Elev= 30
  4582.5  186.75  4837.9  180.06  4877.3  177.46  4900.7   175.5  4905.8   174.1
  4926.2  175.15  4936.4  172.66  4945.9  171.77  4956.8  169.25    4967  168.83
  4977.2  167.57  4987.4   167.6  4998.3  164.65  5001.1  164.15  5004.3  164.65
    5018  166.63  5038.5  167.18  5046.6  166.38  5058.9  167.61  5181.4  167.52
  5242.7  169.55  5247.8  170.42  5263.1   170.2  5273.7  171.24  5283.5  172.48
  5298.2   172.6  5365.2  177.03  5385.6  177.03    5406  178.51  5440.6  179.53
#Mann= 5 ,-1 , 0
  4582.5      .1       0  4877.3     .12       0  4998.3     .07       0
  5004.3     .12       0  5273.7      .1       0
Bank Sta=4967,5058.9
XS Rating Curve= 0 ,0
Exp/Cntr=0.3,0.1

Type RM Length L Ch R = 1 ,30732   ,752,752,752
BEGIN DESCRIPTION:
BARBONE CREEK 57.0
END DESCRIPTION:
XS GIS Cut Line= 4
      2296986.05     13204165.17      2296951.33     13203956.84
      2296569.38     13203414.31      2296248.24     13203388.27
#Sta/Elev= 30
  4339.3  179.76    4417  178.66  4422.1  179.35  4459.3  177.82  4596.7  175.04
  4703.9  167.47  4744.1  166.46    4811  165.32  4891.2  165.35  4905.1  166.28
  4918.2  165.81  4926.9  166.91  4962.6  165.49  4977.4  166.32  4990.8  165.75
  4998.3  164.16  5001.4     162  5004.2   161.5  5007.4     162  5013.1  165.52
  5019.2  163.45  5027.4  162.82  5040.1  166.07  5048.8  169.19  5063.6   170.7
  5130.8  172.23  5255.8  173.52  5396.3  177.76  5516.7  180.22  5536.2  179.67
#Mann= 5 ,-1 , 0
  4339.3      .1       0  4744.1     .12       0  5001.4     .07       0
  5007.4     .12       0  5130.8      .1       0
Bank Sta=4977.4,5040.1
XS Rating Curve= 0 ,0
Exp/Cntr=0.3,0.1

Type RM Length L Ch R = 1 ,29980   ,766,766,766
BEGIN DESCRIPTION:
BARBONE CREEK 56.0
END DESCRIPTION:
XS GIS Cut Line= 2
       2297196.3      13204047.8      2297029.64     13203125.94
#Sta/Elev= 30
  4675.4  177.01  4752.1  176.11  4864.3  171.57  4910.1  168.05  4917.4  165.22
  4922.8  166.25  4940.6  162.33  4971.1  162.72  4976.4  159.82  4981.4  163.06
  4991.4  160.81  4998.5  157.51  5001.3  157.01  5004.5  157.51  5011.7  162.31
  5021.9  163.42  5052.4   162.1  5065.2  163.01  5123.5  162.83  5254.1  166.86
  5306.4  165.88  5312.7  167.49  5317.7  166.44  5336.9  168.31  5366.2  168.45
  5371.2  164.94  5387.7  168.89  5428.3  169.91  5560.5  173.24  5612.2  176.31
#Mann= 6 ,-1 , 0
  4675.4      .1       0  4917.4     .12       0  4998.5     .07       0
  5004.5     .12       0  5065.2     .16       0  5428.3      .1       0
Bank Sta=4981.4,5021.9
XS Rating Curve= 0 ,0
Exp/Cntr=0.3,0.1

Type RM Length L Ch R = 1 ,29214   ,280,280,280
BEGIN DESCRIPTION:
BARBONE CREEK 55.0
END DESCRIPTION:
XS GIS Cut Line= 3
      2297524.26     13203991.53      2297684.84     13203492.43
      2297779.21     13203410.92
#Sta/Elev= 30
  4611.3  175.83  4658.2  175.22  4784.3  171.03  4794.8  170.27  4806.4  168.23
  4815.8  167.88  4833.2  165.02  4847.3  163.99  4915.3  162.65  4952.4  160.78
  4983.9  160.92  4990.6  154.97  4993.4  154.47  4996.6  154.97  5015.4  158.23
  5036.4  157.45  5057.4  158.29 5060.97  161.64    5063  163.35  5068.3  166.02
  5088.9  172.36  5097.6  173.39  5132.1  176.16  5148.9  176.55  5177.4  176.56
    5184  175.76  5212.5  176.28  5219.1  175.66  5226.8  176.42  5260.3  176.28
#Mann= 5 ,-1 , 0
  4611.3      .1       0  4915.3     .12       0  4990.6     .07       0
  4996.6     .12       0  5097.6      .1       0
Bank Sta=4983.9,5060.97
XS Rating Curve= 0 ,0
Exp/Cntr=0.3,0.1

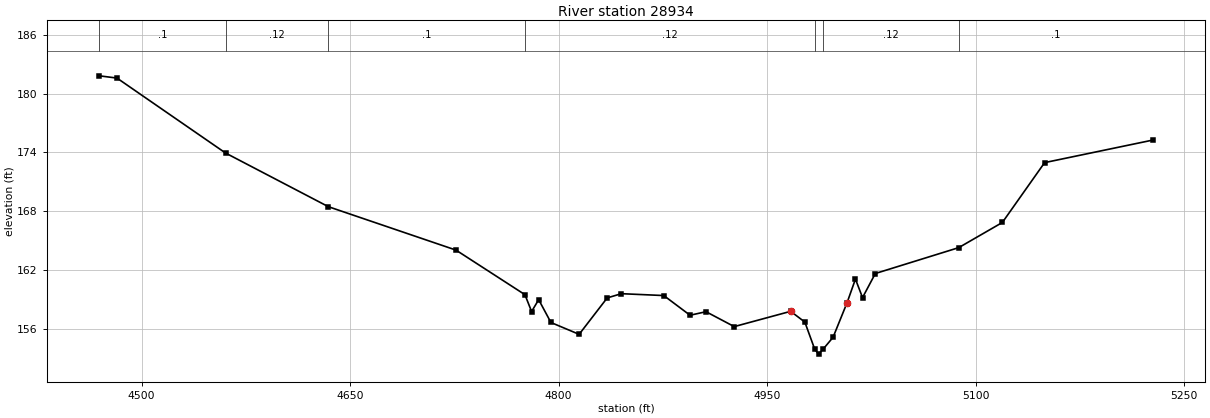
Type RM Length L Ch R = 1 ,28934   ,593,593,593
BEGIN DESCRIPTION:
BARBONE CREEK 54.0
END DESCRIPTION:
XS GIS Cut Line= 3
      2297984.31      13204169.5      2297971.29     13203965.52
      2297876.09     13203420.26
#Sta/Elev= 30
  4469.6  181.82  4482.3  181.59  4560.4  173.94  4634.4  168.46  4726.2  164.03
  4775.8  159.48  4780.6  157.76  4785.7  158.97  4794.5  156.64  4814.8  155.43
    4835  159.15  4845.2  159.58  4875.7  159.39  4894.6  157.38  4906.1  157.74
  4926.4  156.22    4967  157.78  4977.2  156.68  4984.3  153.91  4987.1  153.41
  4990.3  153.91  4997.5  155.13  5007.6  158.67  5013.6  161.07  5018.7  159.18
  5027.9  161.64  5087.9  164.28  5119.3  166.85  5149.7  172.96  5227.5  175.26
#Mann= 7 ,-1 , 0
  4469.6      .1       0  4560.4     .12       0  4634.4      .1       0
  4775.8     .12       0  4984.3     .07       0  4990.3     .12       0
  5087.9      .1       0
Bank Sta=4967,5007.6
XS Rating Curve= 0 ,0
Exp/Cntr=0.3,0.1