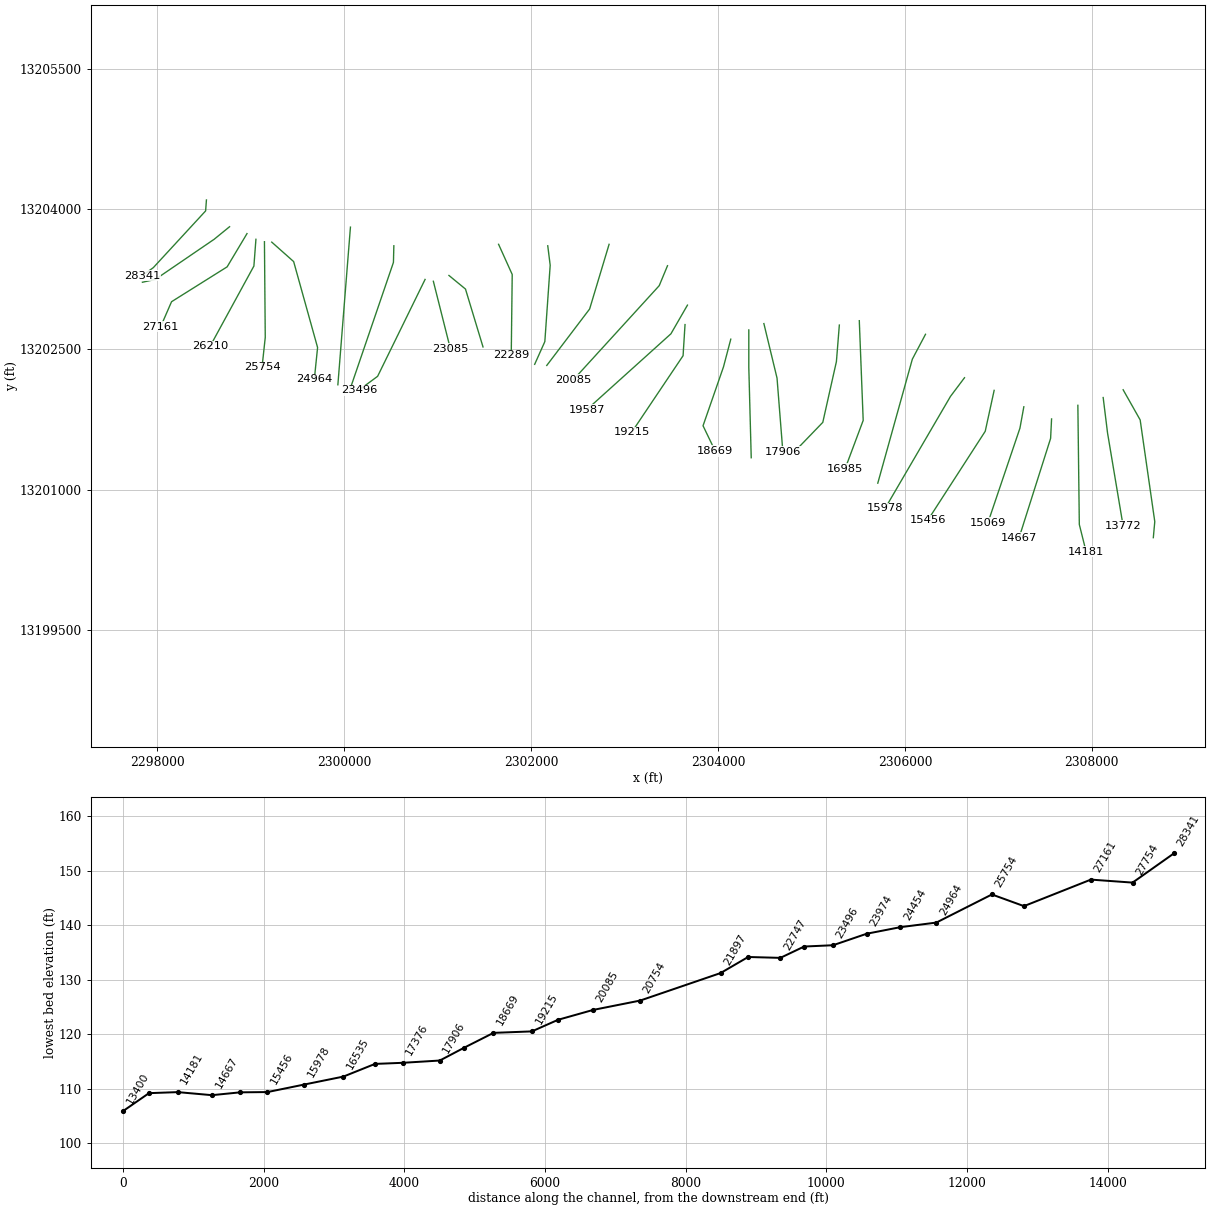
HEC-RAS study BARBONE CREEK.prj: BARBONE CREEK Base Level Engineering

--- BARBONE CREEK.g01 (geometry) --- (continued)

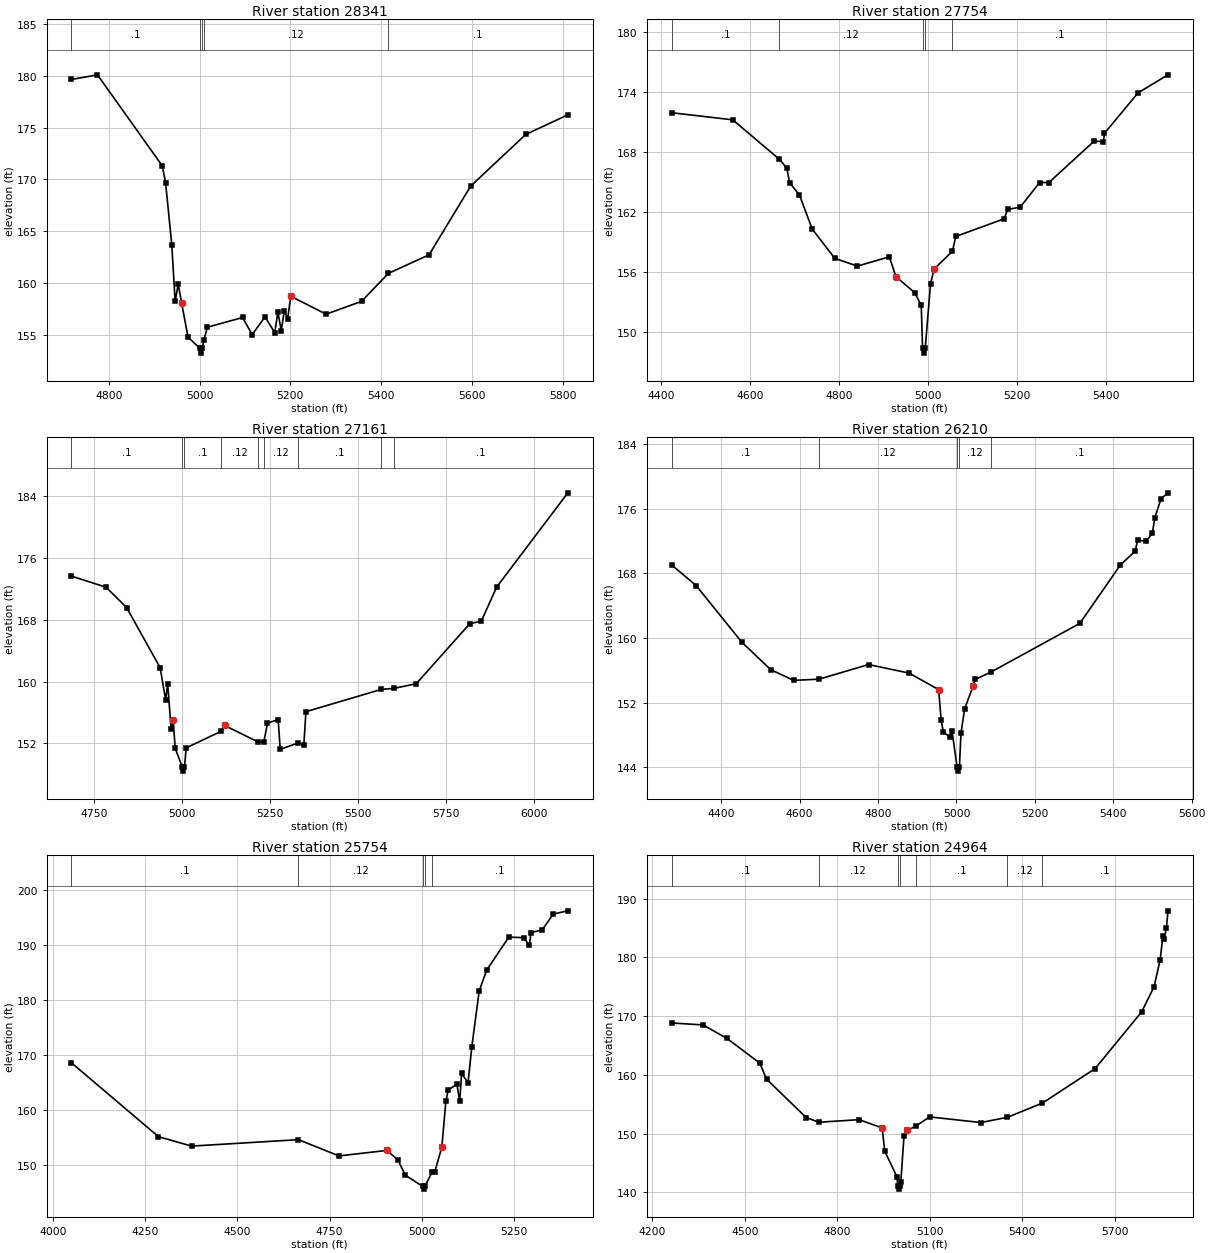
Type RM Length L Ch R = 1 ,28341   ,587,587,587
BEGIN DESCRIPTION:
BARBONE CREEK 53.0
END DESCRIPTION:
XS GIS Cut Line= 4
      2298526.85     13204100.11      2298518.17     13203982.88
      2297958.27     13203375.24      2297836.71     13203288.41
#Sta/Elev= 30
    4718  179.64  4775.2  180.09    4918   171.3  4925.3  169.66  4938.9  163.69
  4946.3  158.21  4953.1  159.87  4960.5  158.08  4974.7  154.76    5000  153.72
  5002.8  153.22    5006  153.72  5009.6  154.46  5017.2  155.72  5094.9  156.66
  5115.9  155.01  5144.2  156.71  5165.8   155.2  5172.6  157.22    5180  155.38
  5186.8  157.33  5194.1  156.52  5200.9  158.71  5278.9  156.98  5356.9  158.22
    5416  160.92  5505.5  162.71  5597.3  169.35  5718.5  174.33  5811.2  176.23
#Mann= 5 ,-1 , 0
    4718      .1       0    5000     .07       0    5006      .1       0
  5009.6     .12       0    5416      .1       0
Bank Sta=4960.5,5200.9
XS Rating Curve= 0 ,0
Exp/Cntr=0.3,0.1

Type RM Length L Ch R = 1 ,27754   ,593,593,593
BEGIN DESCRIPTION:
BARBONE CREEK 52.0
END DESCRIPTION:
XS GIS Cut Line= 4
      2298774.26     13203813.62      2298609.31     13203679.06
      2297979.97     13203249.38      2297841.94     13203219.18
#Sta/Elev= 30
    4424   171.9  4561.5  171.19  4666.4  167.24  4683.1  166.36  4689.2  164.91
  4711.4  163.68    4740  160.28  4790.8  157.34  4841.7  156.56  4913.5  157.49
  4928.4  155.51  4970.3  153.92  4985.3  152.64  4988.3  148.36  4991.1  147.86
  4994.3  148.36  5006.2  154.79  5014.2  156.27  5055.4  158.05  5063.1  159.53
  5171.6  161.29  5179.7  162.23  5207.9  162.46  5251.5  164.92  5272.4  164.92
  5374.1  169.06    5395  169.01  5397.2  169.83  5472.9  173.89  5540.2  175.69
#Mann= 5 ,-1 , 0
    4424      .1       0  4666.4     .12       0  4988.3     .07       0
  4994.3     .12       0  5055.4      .1       0
Bank Sta=4928.4,5014.2
XS Rating Curve= 0 ,0
Exp/Cntr=0.3,0.1

Type RM Length L Ch R = 1 ,27161   ,951,951,951
BEGIN DESCRIPTION:
BARBONE CREEK 51.0
END DESCRIPTION:
XS GIS Cut Line= 4
      2298960.86     13203739.81       2298748.2     13203383.93
      2298153.59     13203010.66      2298036.46      13202741.7
#Sta/Elev= 30
  4685.7  173.64  4783.9  172.21  4842.2  169.58  4937.6  161.79  4953.1  157.65
    4959  159.69  4968.7  153.89  4974.5  155.08  4980.4  151.35  5000.7  148.91
  5003.4  148.41  5006.7  148.91  5011.5  151.42  5111.8  153.58  5120.8  154.32
  5215.5  152.19  5232.2  152.21  5242.5  154.62  5272.8  155.08  5278.7  151.23
  5329.3  152.05  5345.8  151.84  5351.7   156.1  5566.1  158.99  5601.1  159.11
  5665.1  159.72  5817.4   167.5  5849.6   167.8  5893.8  172.24  6095.7  184.42
#Mann= 9 ,-1 , 0
  4685.7      .1       0  5000.7     .07       0  5006.7      .1       0
  5111.8     .12       0  5215.5      .1       0  5232.2     .12       0
  5329.3      .1       0  5566.1     .12       0  5601.1      .1       0
Bank Sta=4974.5,5120.8
XS Rating Curve= 0 ,0
Exp/Cntr=0.3,0.1

Type RM Length L Ch R = 1 ,26210   ,456,456,456
BEGIN DESCRIPTION:
Mapping XS 2385cf18
END DESCRIPTION:
XS GIS Cut Line= 3
      2299056.36     13203679.05      2299034.66     13203392.61
       2298565.9      13202533.2
#Sta/Elev= 30
  4273.4  169.06  4335.8  166.51  4452.5  159.49  4526.3  156.09    4585  154.77
  4649.4  154.92  4775.8  156.73  4879.2  155.67  4954.5  153.63  4960.9  149.87
  4966.5  148.39  4982.7  147.79  4988.7  148.52  5001.5  144.04  5004.3  143.54
  5007.5  144.04  5011.5  148.22  5020.7  151.24  5042.5  154.07  5048.2   154.9
  5088.8  155.82  5314.9  161.83  5418.4  169.07  5455.7  170.74  5462.1  172.14
  5483.9  171.96    5500  173.03  5505.7  174.86  5521.9  177.25  5539.6  177.98
#Mann= 5 ,-1 , 0
  4273.4      .1       0  4649.4     .12       0  5001.5     .07       0
  5007.5     .12       0  5088.8      .1       0
Bank Sta=4954.5,5042.5
XS Rating Curve= 0 ,0
Exp/Cntr=0.3,0.1

Type RM Length L Ch R = 1 ,25754   ,790,790,790
BEGIN DESCRIPTION:
BARBONE CREEK 50.0
END DESCRIPTION:
XS GIS Cut Line= 3
      2299147.51     13203652.97      2299156.19     13202628.72
      2299121.47     13202307.58
#Sta/Elev= 30
  4049.5  168.58  4285.6  155.19  4375.6  153.48  4665.6  154.65  4775.6   151.7
  4905.6   152.7  4935.7  150.95  4955.7  148.21  5002.7  146.18  5005.4  145.68
  5008.7  146.18    5028  148.72  5035.7  148.82 5054.77  153.29  5065.7  161.58
  5072.2  163.68  5095.8  164.68  5103.4  161.57  5108.5  166.69    5126  164.94
    5136   171.4  5156.1  181.58  5176.2  185.35  5236.6  191.37  5276.8  191.28
    5292   189.9  5297.1   192.2  5327.1  192.67  5357.3  195.56  5396.8  196.14
#Mann= 5 ,-1 , 0
  4049.5      .1       0  4665.6     .12       0  5002.7     .07       0
  5008.7     .12       0    5028      .1       0
Bank Sta=4905.6,5054.77
XS Rating Curve= 0 ,0
Exp/Cntr=0.3,0.1

Type RM Length L Ch R = 1 ,24964   ,510,510,510
BEGIN DESCRIPTION:
BARBONE CREEK 49.0
END DESCRIPTION:
XS GIS Cut Line= 4
      2299225.63     13203648.68      2299460.01     13203440.35
      2299716.09     13202520.21      2299681.37     13202181.78
#Sta/Elev= 30
  4263.2  168.84  4365.1   168.5  4442.8   166.2    4549  161.99  4570.8  159.27
  4699.3  152.72  4740.7  151.92  4871.1  152.36 4945.57  150.95  4954.1  146.96
  4993.8   142.6    4996  141.02  4998.7  140.52    5002  141.02    5006  141.74
  5016.4  149.57  5026.8  150.53  5054.1  151.24  5099.4  152.83  5265.5  151.87
  5351.5  152.76  5465.3  155.19  5635.8  161.06  5786.6  170.72  5826.8  174.99
  5846.9  179.65  5855.4   183.6  5860.4  183.23    5867   185.1  5872.1  187.95
#Mann= 7 ,-1 , 0
  4263.2      .1       0  4740.7     .12       0    4996     .07       0
    5002     .12       0  5054.1      .1       0  5351.5     .12       0
  5465.3      .1       0
Bank Sta=4945.57,5026.8
XS Rating Curve= 0 ,0
Exp/Cntr=0.3,0.1

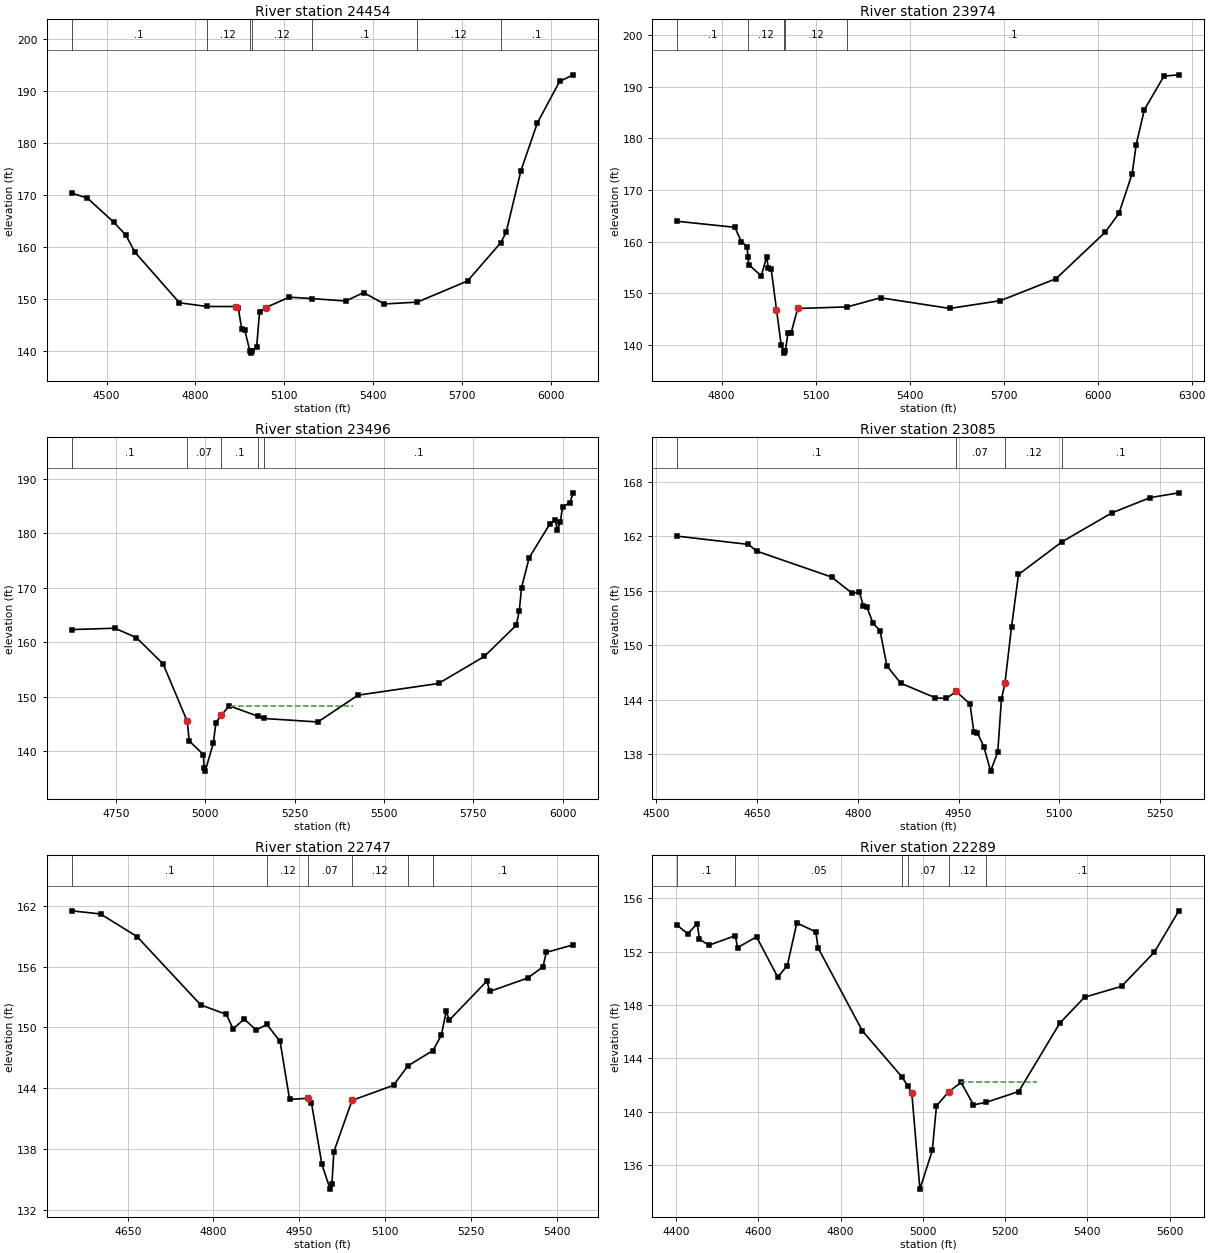
Type RM Length L Ch R = 1 ,24454   ,480,480,480
BEGIN DESCRIPTION:
BARBONE CREEK 48.0
END DESCRIPTION:
XS GIS Cut Line= 2
      2300067.65     13203809.29      2299933.13     13202121.34
#Sta/Elev= 30
  4382.2  170.44  4434.8   169.5  4525.1   164.8  4565.2  162.35  4595.3  159.11
  4745.8  149.37  4837.7  148.65  4936.4  148.64  4944.6  148.34  4956.5  144.29
  4966.5   144.1  4983.5  140.18  4986.3  139.68  4989.5  140.18  5006.6  140.77
  5016.6  147.68  5036.7  148.42    5117  150.44  5192.2  150.17  5307.6   149.7
  5367.8  151.31    5438  149.13  5549.2  149.49  5718.9  153.55  5830.9  160.89
  5849.3  162.91  5899.4  174.78  5954.7  183.92  6029.8  191.91  6075.5  193.19
#Mann= 7 ,-1 , 0
  4382.2      .1       0  4837.7     .12       0  4983.5     .07       0
  4989.5     .12       0  5192.2      .1       0  5549.2     .12       0
  5830.9      .1       0
Bank Sta=4936.4,5036.7
XS Rating Curve= 0 ,0
Exp/Cntr=0.3,0.1

Type RM Length L Ch R = 1 ,23974   ,478,478,478
BEGIN DESCRIPTION:
BARBONE CREEK 47.0
END DESCRIPTION:
XS GIS Cut Line= 3
      2300532.06     13203609.57      2300527.72     13203431.67
      2300067.66     13202086.21
#Sta/Elev= 30
  4659.1  163.96  4842.2   162.8  4863.3  160.03  4881.3  159.06  4884.3   157.1
  4886.6  155.59  4926.7  153.41  4943.9   157.1  4949.2  154.93  4958.4  154.69
  4975.2   146.9  4990.1  140.11  4997.7  138.97  5000.4  138.47  5003.7  138.97
  5011.8  142.38  5021.8  142.38  5043.1   147.1  5201.2  147.41  5307.2  149.17
  5528.1  147.11    5690  148.62  5867.2  152.86  6023.8  161.83  6068.1   165.5
  6110.4  173.19    6123  178.77    6149  185.51  6211.6  192.03    6259  192.28
#Mann= 5 ,-1 , 0
  4659.1      .1       0  4884.3     .12       0  4997.7     .07       0
  5003.7     .12       0  5201.2      .1       0
Bank Sta=4975.2,5043.1
XS Rating Curve= 0 ,0
Exp/Cntr=0.3,0.1

Type RM Length L Ch R = 1 ,23496   ,411,411,411
BEGIN DESCRIPTION:
BARBONE CREEK 46.0
END DESCRIPTION:
XS GIS Cut Line= 3
      2300866.24     13203249.33      2300358.45     13202212.05
      2300158.77     13202064.47
#Sta/Elev= 30
  4626.1  162.33  4746.8  162.58    4807  160.86  4881.8  156.03  4949.3  145.52
  4954.9   141.9  4994.4   139.4  4996.9  136.86  4999.7  136.36  5022.4   141.5
  5029.7  145.28  5044.9  146.64  5067.4  148.34  5148.4   146.4  5163.9  146.02
    5315  145.38  5427.5   150.3  5652.6  152.44    5781  157.41  5870.3  163.14
  5878.7  165.78  5884.9     170  5906.3   175.5  5964.3  181.72  5978.9  182.45
  5985.2  180.64  5993.3  182.04  5999.8  184.84  6020.6  185.61  6029.3  187.42
#Mann= 5 ,-1 , 0
  4626.1      .1       0  4949.3     .07       0  5044.9      .1       0
  5148.4     .12       0  5163.9      .1       0
#XS Ineff= 1 ,-1
 5072.86 5412.86  148.24
Permanent Ineff=
       T
Bank Sta=4949.3,5044.9
XS Rating Curve= 0 ,0
Exp/Cntr=0.3,0.1

Type RM Length L Ch R = 1 ,23085   ,338,338,338
BEGIN DESCRIPTION:
BARBONE CREEK 45.0
END DESCRIPTION:
XS GIS Cut Line= 2
       2300954.8     13203229.41       2301137.1     13202505.41
#Sta/Elev= 30
  4531.4  161.99  4637.2  161.08  4649.2  160.35  4760.9  157.49  4791.8  155.69
  4802.2  155.84  4808.4  154.32  4813.6  154.16  4822.8  152.39  4833.1  151.58
  4843.4   147.7    4864   145.8  4915.6  144.19  4931.7  144.12  4945.7  144.84
  4946.5  144.89  4967.1  143.51  4972.8  140.45    4978  140.36  4987.8  138.79
  4997.8  136.12  5008.4  138.21  5013.9  144.04  5019.1  145.77    5029  152.04
  5039.3  157.77  5104.1  161.37  5178.3  164.55  5235.3  166.23    5278  166.76
#Mann= 4 ,-1 , 0
  4531.4      .1       0  4945.7     .07       0  5019.1     .12       0
  5104.1      .1       0
Bank Sta=4946.5,5019.1
XS Rating Curve= 0 ,0
Exp/Cntr=0.3,0.1

Type RM Length L Ch R = 1 ,22747   ,458,458,458
BEGIN DESCRIPTION:
BARBONE CREEK 44.0
END DESCRIPTION:
XS GIS Cut Line= 3
      2301121.46     13203291.91      2301298.55     13203146.08
      2301486.04     13202526.32
#Sta/Elev= 30
  4552.1  161.51  4602.5   161.2  4666.3  158.97  4777.7  152.22  4822.5  151.29
  4834.3  149.86  4853.8  150.83  4874.7  149.74  4893.4   150.3  4916.5  148.62
  4933.1   142.9  4966.1  143.01  4971.3  142.58  4989.6   136.5    5004  134.04
  5007.2  134.54  5010.5  137.73  5042.4   142.8    5115  144.29  5139.9   146.2
  5183.9  147.72  5198.6  149.24  5207.1  151.63  5212.3  150.71  5278.2  154.58
  5283.4  153.56  5349.3  154.87  5376.2  155.97  5382.2  157.41    5429  158.15
#Mann= 6 ,-1 , 0
  4552.1      .1       0  4893.4     .12       0  4966.1     .07       0
  5042.4     .12       0  5139.9     .05       0  5183.9      .1       0
Bank Sta=4966.1,5042.4
XS Rating Curve= 0 ,0
Exp/Cntr=0.3,0.1

Type RM Length L Ch R = 1 ,22289   ,392,392,392
BEGIN DESCRIPTION:
BARBONE CREEK 43.0
END DESCRIPTION:
XS GIS Cut Line= 3
      2301652.71     13203625.25      2301798.55     13203302.33
      2301788.13     13202437.72
#Sta/Elev= 30
  4403.2  153.98  4428.2  153.34  4451.3  154.11  4456.8  152.94  4479.9  152.49
  4544.1  153.21  4549.3  152.31  4595.5  153.12  4647.2   150.1  4670.4  150.97
  4693.5  154.16  4739.7  153.49  4745.2  152.29    4853  146.06  4948.7  142.63
    4963  141.94    4973  141.43  4992.8   134.2    5023  137.11    5033  140.44
    5063  141.51    5093   142.2    5123  140.52  5153.9  140.71    5233  141.52
    5333  146.65    5393  148.59  5483.1  149.41  5563.1  151.98  5622.2  155.07
#Mann= 6 ,-1 , 0
  4403.2      .1       0  4544.1     .05       0  4948.7     .12       0
    4963     .07       0    5063     .12       0  5153.9      .1       0
#XS Ineff= 1 ,-1
  5092.5 5276.25  142.26
Permanent Ineff=
       T
Bank Sta=4973,5063
XS Rating Curve= 0 ,0
Exp/Cntr=0.3,0.1

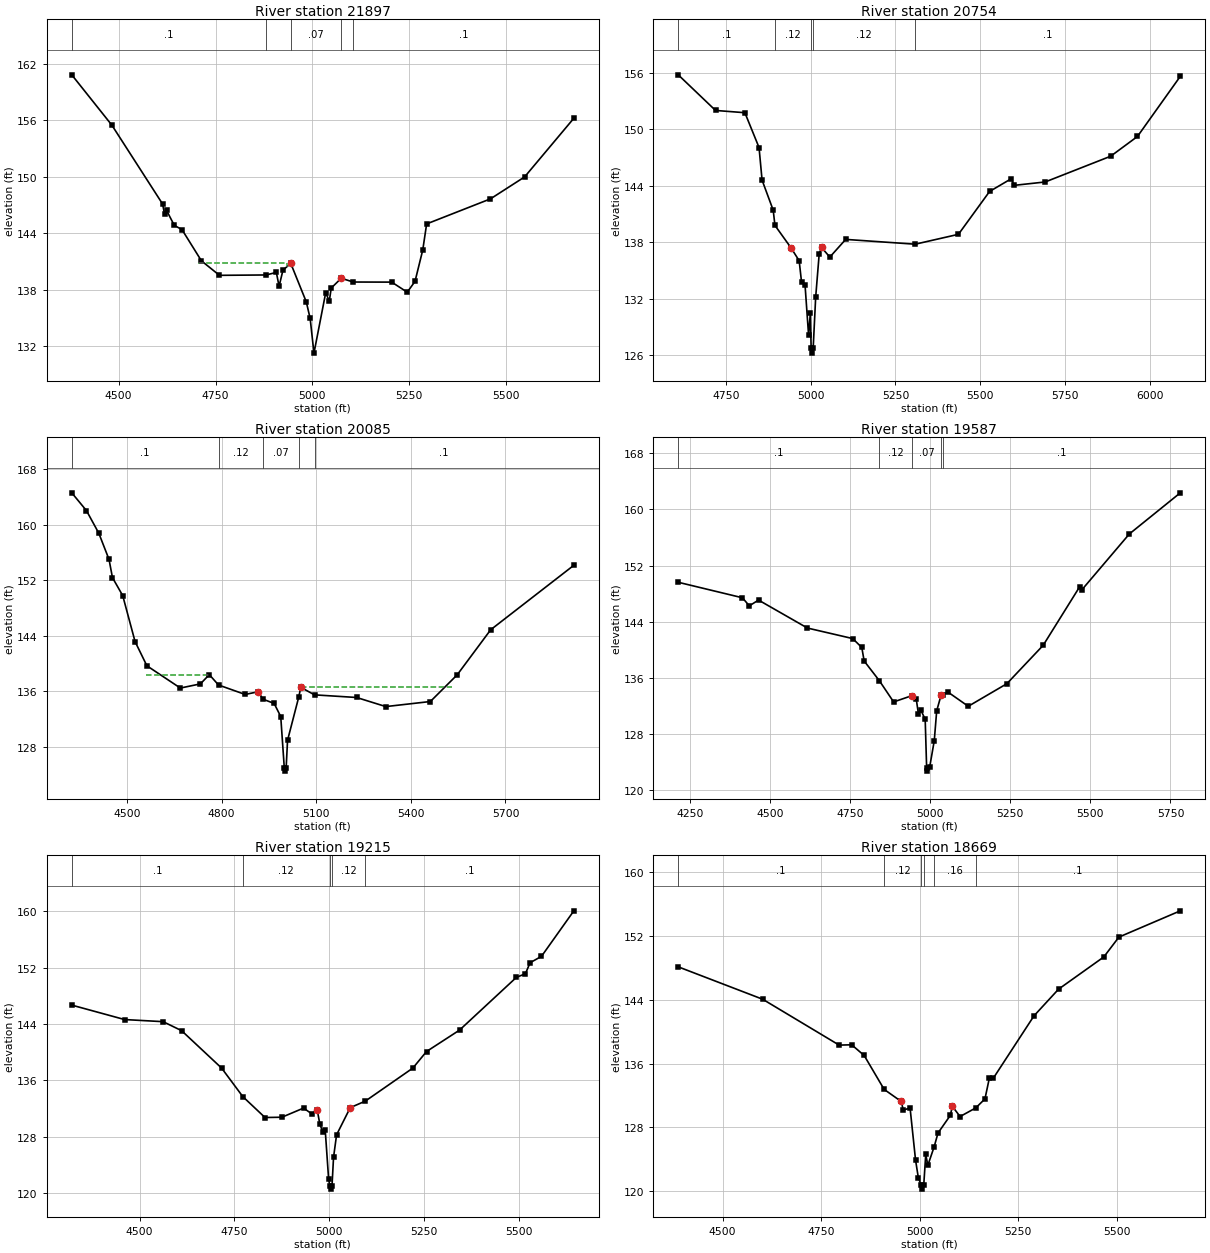
Type RM Length L Ch R = 1 ,21897   ,1143,1143,1143
BEGIN DESCRIPTION:
BARBONE CREEK 42.0
END DESCRIPTION:
XS GIS Cut Line= 4
      2302178.76     13203609.65       2302204.8     13203401.29
      2302147.51     13202583.58      2302038.83     13202340.35
#Sta/Elev= 30
  4378.9   160.8  4482.5  155.45  4613.4  147.08  4618.5  145.99  4623.5  146.41
  4643.5  144.82  4663.5  144.36  4713.6  141.05  4760.2  139.51  4880.7  139.55
    4907  139.82  4914.1  138.35  4924.1  140.06  4944.2  140.78  4984.3  136.69
  4994.3  134.93  5004.1  131.25  5034.4  137.66  5043.7  136.77  5048.7  138.16
  5074.5   139.2  5105.6   138.8  5204.8  138.79  5244.9  137.72    5265  138.87
    5285  142.21    5295  144.97  5459.8  147.63  5547.9  149.96    5675  156.19
#Mann= 5 ,-1 , 0
  4378.9      .1       0  4880.7     .12       0  4944.2     .07       0
  5074.5     .12       0  5105.6      .1       0
#XS Ineff= 1 ,-1
 4705.71 4934.29  140.77
Permanent Ineff=
       T
Bank Sta=4944.2,5074.5
XS Rating Curve= 0 ,0
Exp/Cntr=0.3,0.1

Type RM Length L Ch R = 1 ,20754   ,669,669,669
BEGIN DESCRIPTION:
BARBONE CREEK 41.0
END DESCRIPTION:
XS GIS Cut Line= 3
      2302835.02     13203625.27      2302626.68     13202932.54
      2302168.36     13202328.39
#Sta/Elev= 30
  4608.9  155.81    4719  152.02  4805.6  151.78  4847.4  148.07  4856.3  144.61
  4889.2   141.4  4894.3  139.79  4941.4  137.42  4965.8  136.03  4972.7  133.79
  4983.2  133.41  4993.6  128.09  4998.8  130.48  5001.1   126.7  5003.8   126.2
  5007.1   126.7  5014.5  132.15  5024.9  136.76  5031.8  137.44  5056.3  136.42
  5103.1   138.3  5308.2  137.79  5435.8  138.84  5527.7   143.4  5591.9  144.76
  5600.1  144.05  5691.7  144.41  5885.1  147.15  5964.1  149.25  6090.6  155.65
#Mann= 5 ,-1 , 0
  4608.9      .1       0  4894.3     .12       0  5001.1     .07       0
  5007.1     .12       0  5308.2      .1       0
Bank Sta=4941.4,5031.8
XS Rating Curve= 0 ,0
Exp/Cntr=0.3,0.1

Type RM Length L Ch R = 1 ,20085   ,498,498,498
BEGIN DESCRIPTION:
BARBONE CREEK 40.0
END DESCRIPTION:
XS GIS Cut Line= 3
      2303459.99     13203396.04      2303371.47     13203182.54
      2302454.83     13202177.36
#Sta/Elev= 30
  4325.3  164.58  4371.8  162.02    4411  158.76  4443.4  154.98  4454.3  152.36
  4486.8  149.77  4525.9  143.15  4563.4  139.66  4669.5  136.45    4733  137.05
  4761.3  138.38  4790.5  136.89  4874.8  135.53  4916.8  135.92  4930.9  134.85
  4966.7  134.24  4987.7  132.34  4998.9  124.98  5001.6  124.48  5004.9  124.98
  5009.3  128.92  5044.4  135.09  5051.3  136.55  5094.8  135.47  5228.2  135.09
  5320.8  133.78    5462  134.51  5547.1  138.36  5653.2  144.85  5916.8  154.14
#Mann= 5 ,-1 , 0
  4325.3      .1       0  4790.5     .12       0  4930.9     .07       0
  5044.4     .12       0  5094.8      .1       0
#XS Ineff= 2 ,-1
    4560 4760.89  138.39 5059.82 5529.11   136.6
Permanent Ineff=
       T       T
Bank Sta=4916.8,5051.3
XS Rating Curve= 0 ,0
Exp/Cntr=0.3,0.1

Type RM Length L Ch R = 1 ,19587   ,372,372,372
BEGIN DESCRIPTION:
BARBONE CREEK 39.0
END DESCRIPTION:
XS GIS Cut Line= 3
      2303673.53     13202974.17      2303496.47     13202666.91
      2302595.42     13201854.41
#Sta/Elev= 30
  4212.8  149.61  4413.2   147.4  4434.7  146.25  4463.6  147.07  4616.3  143.08
  4757.6  141.58    4786  140.31  4793.4  138.38    4841  135.56  4885.4  132.54
  4942.2  133.43  4956.2  132.91  4963.1  130.76  4969.8  131.43    4984  130.06
  4988.5  123.17  4991.2  122.67  4998.2  123.29  5012.4  127.03  5019.9  131.27
  5034.1  133.58  5038.6  133.52    5055  133.95  5118.5  131.92    5239  135.14
  5352.5  140.62    5466  148.94  5472.8  148.51  5621.5   156.5  5780.7  162.37
#Mann= 5 ,-1 , 0
  4212.8      .1       0    4841     .12       0  4942.2     .07       0
  5034.1     .12       0  5038.6      .1       0
Bank Sta=4942.2,5034.1
XS Rating Curve= 0 ,0
Exp/Cntr=0.3,0.1

Type RM Length L Ch R = 1 ,19215   ,546,546,546
BEGIN DESCRIPTION:
BARBONE CREEK 38.0
END DESCRIPTION:
XS GIS Cut Line= 3
      2303647.51     13202765.89      2303626.68     13202432.54
      2303075.35     13201610.74
#Sta/Elev= 30
  4321.2  146.67  4460.5  144.62    4562  144.32  4610.8  143.04  4716.2  137.73
  4772.1  133.68  4830.6  130.71  4875.2  130.75  4932.3  132.05  4953.3  131.25
  4968.3  131.79  4975.1  129.79  4983.3   128.6  4989.3  128.97  4998.3     122
  5001.3  121.04    5004  120.54  5007.3  121.04  5011.3  125.06  5019.3  128.25
  5055.3  132.11  5095.1  133.04  5220.4  137.73  5256.4  140.08  5343.4  143.12
  5493.5  150.62    5517  151.12  5529.5  152.69  5559.5   153.6  5644.8  160.06
#Mann= 5 ,-1 , 0
  4321.2      .1       0  4772.1     .12       0  5001.3     .07       0
  5007.3     .12       0  5095.1      .1       0
Bank Sta=4968.3,5055.3
XS Rating Curve= 0 ,0
Exp/Cntr=0.3,0.1

Type RM Length L Ch R = 1 ,18669   ,416,416,416
BEGIN DESCRIPTION:
BARBONE CREEK 37.0
END DESCRIPTION:
XS GIS Cut Line= 4
       2304137.1     13202609.65      2304058.97     13202312.74
      2303840.22     13201682.54      2303970.38      13201411.8
#Sta/Elev= 30
  4387.3  148.13  4601.6  144.07  4795.8  138.32  4827.6  138.36  4859.3  137.02
    4910  132.77  4953.3  131.26  4958.6  130.17  4975.8  130.45  4989.7  123.92
  4996.9  121.66  5004.5  120.77  5007.3  120.27  5010.5  120.77  5015.6  124.62
  5020.9  123.25  5036.9  125.57  5046.7   127.3  5077.8   129.5  5083.1  130.64
  5102.8  129.37  5142.6  130.45  5165.9  131.58  5176.9  134.15  5187.5   134.2
  5290.4  141.99  5352.7  145.33  5467.6  149.37    5506  151.86  5661.8  155.15
#Mann= 6 ,-1 , 0
  4387.3      .1       0    4910     .12       0  5004.5     .07       0
  5010.5     .12       0  5036.9     .16       0  5142.6      .1       0
Bank Sta=4953.3,5083.1
XS Rating Curve= 0 ,0
Exp/Cntr=0.3,0.1

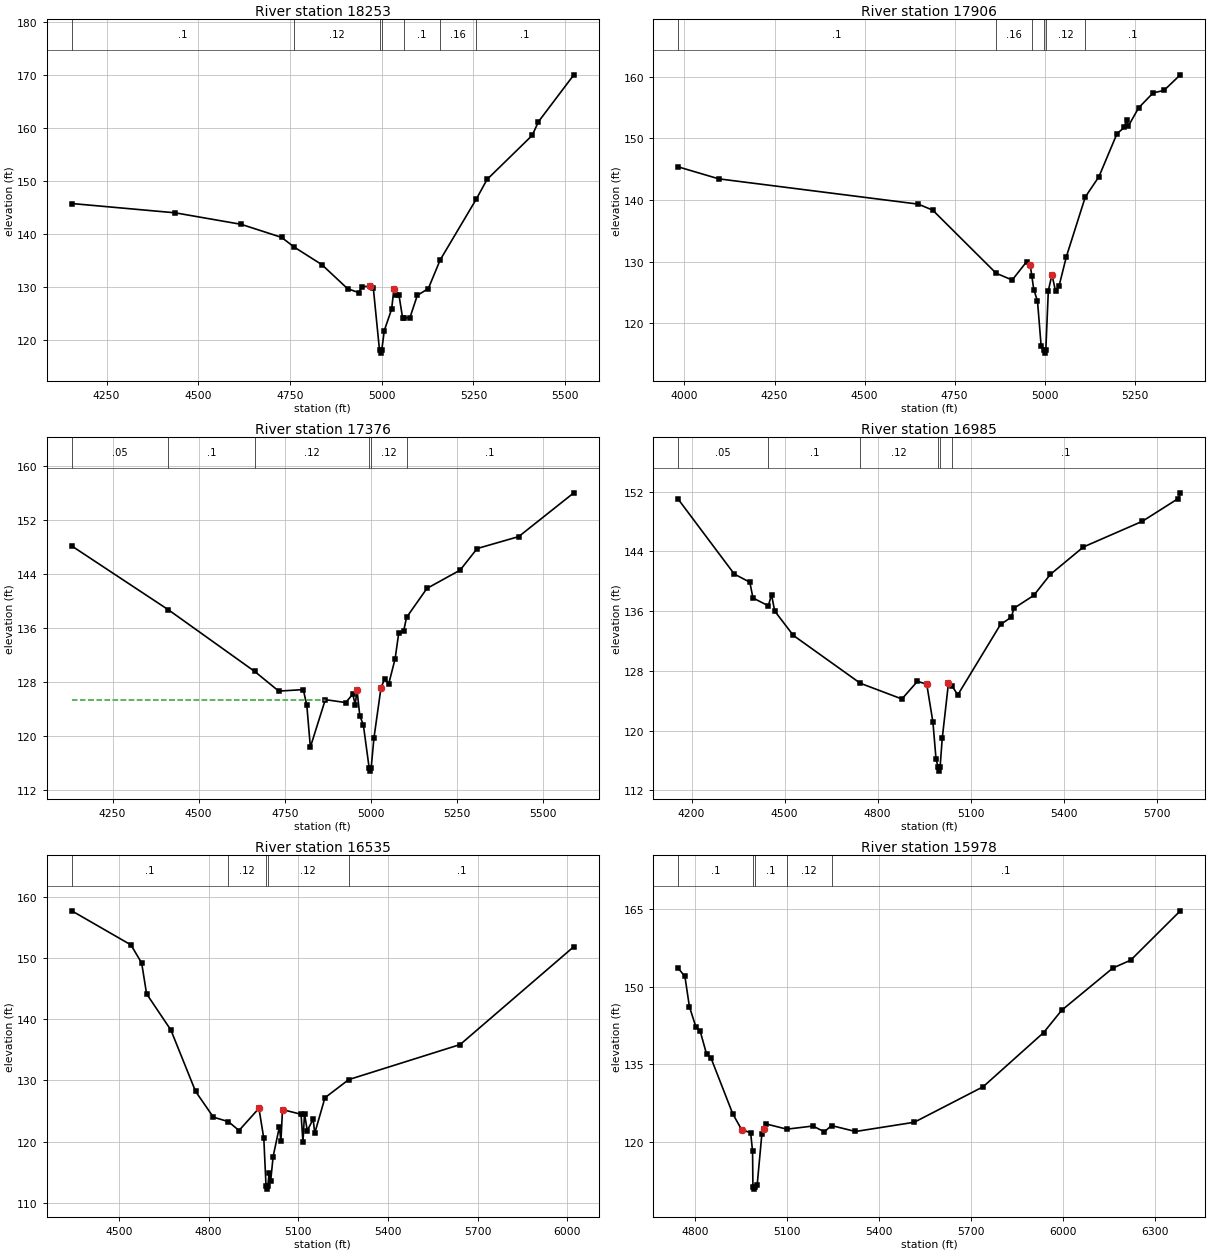
Type RM Length L Ch R = 1 ,18253   ,347,347,347
BEGIN DESCRIPTION:
BARBONE CREEK 36.0
END DESCRIPTION:
XS GIS Cut Line= 3
       2304329.8     13202708.58       2304329.8     13202312.74
       2304355.8     13201340.32
#Sta/Elev= 30
  4155.2  145.76  4436.9  144.01  4616.9  141.84    4727  139.38  4762.3  137.51
    4837  134.23    4907   129.7  4937.1  128.97  4947.1   130.1  4967.1  130.14
  4977.1  129.88  4994.1  118.05  4996.8  117.55  5000.1  118.05  5007.1  121.81
  5027.1  125.84  5033.2   129.6  5038.2  128.44  5047.1  128.49  5057.1  124.14
  5060.7  124.17  5077.1  124.26  5097.1  128.44  5127.1  129.72  5159.5  135.13
  5258.2  146.63  5287.2   150.3  5410.4  158.62  5427.2  161.18  5523.8  170.03
#Mann= 7 ,-1 , 0
  4155.2      .1       0  4762.3     .12       0  4994.1     .07       0
  5000.1     .12       0  5060.7      .1       0  5159.5     .16       0
  5258.2      .1       0
Bank Sta=4967.1,5033.2
XS Rating Curve= 0 ,0
Exp/Cntr=0.3,0.1

Type RM Length L Ch R = 1 ,17906   ,530,530,530
BEGIN DESCRIPTION:
BARBONE CREEK 35.0
END DESCRIPTION:
XS GIS Cut Line= 3
      2304491.27     13202776.24      2304631.88     13202192.95
      2304694.36     13201401.61
#Sta/Elev= 30
  3982.7  145.38  4095.2  143.44    4649  139.34  4689.1  138.37  4865.2  128.14
  4909.8  127.04  4949.9  130.01    4960  129.42  4964.1  127.76  4969.7  125.49
    4980  123.64  4990.1  116.39  4997.1  115.69  4999.8  115.19  5003.1  115.69
  5010.1   125.3  5020.2  127.91  5030.2   125.2  5040.2  126.14  5060.3  130.85
  5112.7   140.5  5150.6  143.79  5200.7  150.76  5220.8  151.77  5227.2  153.01
  5232.2  151.99  5260.9  154.96    5301  157.37  5331.1  157.77  5376.5   160.3
#Mann= 6 ,-1 , 0
  3982.7      .1       0  4865.2     .16       0  4964.1     .12       0
  4997.1     .07       0  5003.1     .12       0  5112.7      .1       0
Bank Sta=4960,5020.2
XS Rating Curve= 0 ,0
Exp/Cntr=0.3,0.1

Type RM Length L Ch R = 1 ,17376   ,391,391,391
BEGIN DESCRIPTION:
BARBONE CREEK 34.0
END DESCRIPTION:
XS GIS Cut Line= 4
      2305298.55     13202760.62       2305267.3     13202370.04
      2305121.47     13201718.99      2304845.44     13201432.56
#Sta/Elev= 30
  4131.8  148.19  4412.1  138.72  4662.7  129.56  4732.3  126.65  4803.6  126.87
  4813.8  124.53  4824.1  118.33  4867.5  125.38  4926.6  124.95  4947.1  126.19
  4954.3  124.64  4959.4  126.79  4967.6  122.98  4977.8  121.64  4994.6  115.27
  4997.4  114.77  5000.6  115.27  5008.5  119.66    5029  127.13  5039.3  128.42
  5051.2  127.68    5070  131.44  5080.3   135.2  5094.6  135.53  5103.2  137.59
  5162.3  141.89  5258.7  144.61  5308.1  147.81  5428.5  149.58  5588.6  156.08
#Mann= 6 ,-1 , 0
  4131.8     .05       0  4412.1      .1       0  4662.7     .12       0
  4994.6     .07       0  5000.6     .12       0  5103.2      .1       0
#XS Ineff= 2 , 0
         4866.36  125.39
Permanent Ineff=
       F       F
Bank Sta=4959.4,5029
XS Rating Curve= 0 ,0
Exp/Cntr=0.3,0.1

Type RM Length L Ch R = 1 ,16985   ,450,450,450
BEGIN DESCRIPTION:
BARBONE CREEK 33.0
END DESCRIPTION:
XS GIS Cut Line= 3
      2305512.09     13202807.55      2305553.76     13201739.83
      2305361.05      13201224.2
#Sta/Elev= 30
    4157  150.98  4337.8  140.96  4387.9  139.87  4397.9  137.76  4447.6  136.71
  4457.9  138.21  4467.9  136.02    4528  132.75    4744  126.34  4878.2  124.23
  4928.3  126.59  4958.3  126.22  4978.3  121.12  4988.3  116.18  4995.3  115.07
  4998.1  114.57  5001.3  115.07  5008.3  118.95  5028.4  126.37  5039.1  126.03
  5058.4  124.78  5196.2  134.21  5231.3  135.19  5239.4  136.38  5303.4   138.1
  5356.8  140.91  5463.6  144.59  5653.7  148.03  5769.5  151.08    5776  151.84
#Mann= 6 ,-1 , 0
    4157     .05       0  4447.6      .1       0    4744     .12       0
  4995.3     .07       0  5001.3     .12       0  5039.1      .1       0
Bank Sta=4958.3,5028.4
XS Rating Curve= 0 ,0
Exp/Cntr=0.3,0.1

Type RM Length L Ch R = 1 ,16535   ,557,557,557
BEGIN DESCRIPTION:
BARBONE CREEK 32.0
END DESCRIPTION:
XS GIS Cut Line= 3
      2306220.42      13202661.7       2306079.8     13202396.08
      2305710.01     13201067.95
#Sta/Elev= 30
  4342.1  157.67  4539.9  152.11  4575.9  149.15  4592.3  144.12  4673.6  138.21
    4756  128.21  4815.6  123.99  4865.8  123.26  4901.4  121.81  4968.1  125.43
  4984.4  120.51  4991.8  112.74  4994.5  112.24  4997.8  112.74  5002.3   114.9
  5007.5  113.64  5015.5  117.54  5036.3  122.35  5041.7  120.13  5046.9  125.22
    5109  124.46  5115.3  119.91  5120.5  124.55  5129.7   121.8  5149.5  123.66
  5154.7  121.36  5188.9  127.16  5268.5  130.12    5641  135.84  6021.3  151.82
#Mann= 5 ,-1 , 0
  4342.1      .1       0  4865.8     .12       0  4991.8     .07       0
  4997.8     .12       0  5268.5      .1       0
Bank Sta=4968.1,5046.9
XS Rating Curve= 0 ,0
Exp/Cntr=0.3,0.1

Type RM Length L Ch R = 1 ,15978   ,522,522,522
BEGIN DESCRIPTION:
BARBONE CREEK 31.0
END DESCRIPTION:
XS GIS Cut Line= 3
       2306637.7     13202196.82      2306487.72     13201996.85
      2305787.72     13200796.86
#Sta/Elev= 30
  4744.2  153.57    4766  152.02  4780.6  146.17  4801.5  142.27    4816  141.36
  4836.9   136.9  4851.5  136.14  4922.3  125.36  4951.5  122.27  4980.6  121.72
  4986.9   118.1    4988  111.28  4990.8  110.78    4994  111.28    5002  111.63
  5017.3  121.52  5023.5  122.52  5029.3  123.44  5098.6   122.4  5183.9  123.01
  5221.2  121.89  5244.6   123.1  5322.9  121.95  5514.7  123.74  5739.6  130.62
  5937.3  141.13    5996  145.44  6163.4  153.64  6221.3  155.15  6383.4  164.72
#Mann= 5 ,-1 , 0
  4744.2      .1       0    4988     .07       0    4994      .1       0
  5098.6     .12       0  5244.6      .1       0
Bank Sta=4951.5,5023.5
XS Rating Curve= 0 ,0
Exp/Cntr=0.3,0.1

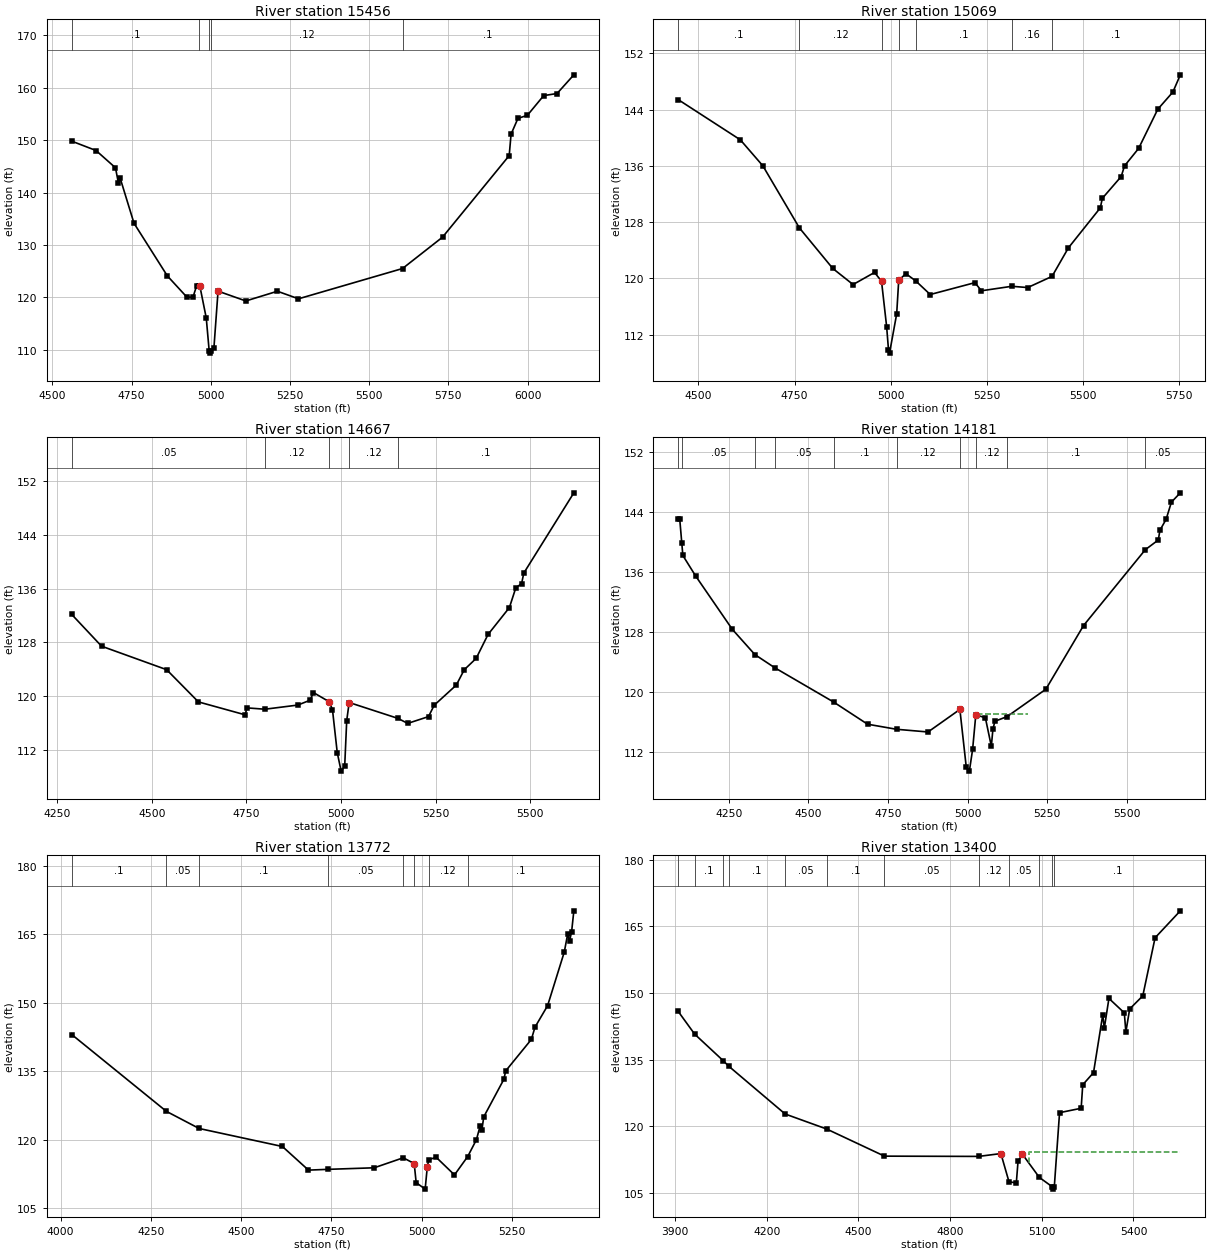
Type RM Length L Ch R = 1 ,15456   ,387,387,387
BEGIN DESCRIPTION:
BARBONE CREEK 30.0
END DESCRIPTION:
XS GIS Cut Line= 3
      2306954.99     13202061.73       2306859.5     13201623.35
      2306243.21     13200668.53
#Sta/Elev= 30
  4561.2  149.78  4637.8     148  4699.2  144.71  4708.6  141.76  4713.7  142.79
  4757.7  134.14    4863  124.11  4924.4  120.08  4943.7  120.02  4955.1  122.18
  4963.8  122.25  4965.3  122.26  4985.8  116.09  4994.9   109.9  4997.7   109.4
  5000.9   109.9  5009.9  110.33    5023  121.21  5110.7  119.34  5210.4  121.19
    5277  119.75  5605.5  125.52  5731.7  131.49  5942.2  147.03  5948.1  151.11
  5969.8  154.12  5999.6  154.71  6051.1  158.46  6093.3  158.86  6146.3  162.42
#Mann= 5 ,-1 , 0
  4561.2      .1       0  4963.8     .12       0  4994.9     .07       0
  5000.9     .12       0  5605.5      .1       0
Bank Sta=4965.3,5023
XS Rating Curve= 0 ,0
Exp/Cntr=0.3,0.1

Type RM Length L Ch R = 1 ,15069   ,402,402,402
BEGIN DESCRIPTION:
BARBONE CREEK 29.0
END DESCRIPTION:
XS GIS Cut Line= 3
      2307272.51     13201885.67      2307230.84     13201656.49
      2306887.27     13200641.39
#Sta/Elev= 30
  4447.7  145.42  4609.1   139.7  4667.6     136  4762.5  127.17  4849.2   121.4
    4902  119.11  4957.8  120.83  4975.9  119.58  4989.2  113.13    4994  109.85
  4996.7  109.35  5015.3  114.93  5020.6  119.71  5039.2  120.66  5065.1  119.61
  5102.5  117.69  5218.7  119.38  5235.4  118.22  5314.4  118.86  5355.8  118.68
    5419  120.27  5461.5  124.33  5544.4  130.02  5549.7  131.38  5598.7  134.48
  5607.3  135.99    5644  138.48  5693.7  144.05    5733   146.5  5752.3  148.95
#Mann= 7 ,-1 , 0
  4447.7      .1       0  4762.5     .12       0  4975.9     .07       0
  5020.6     .12       0  5065.1      .1       0  5314.4     .16       0
    5419      .1       0
Bank Sta=4975.9,5020.6
XS Rating Curve= 0 ,0
Exp/Cntr=0.3,0.1

Type RM Length L Ch R = 1 ,14667   ,486,486,486
BEGIN DESCRIPTION:
BARBONE CREEK 28.0
END DESCRIPTION:
XS GIS Cut Line= 3
      2307569.38     13201755.45      2307558.97     13201547.12
      2307220.82     13200480.64
#Sta/Elev= 30
  4288.2  132.16  4366.9  127.44    4539  123.94    4623  119.14  4746.3  117.22
  4751.6  118.25  4798.7  118.05  4885.9  118.67  4918.2  119.39  4927.2  120.53
  4969.2  119.15  4977.5  117.96  4990.1  111.57  5000.4  108.83  5009.8  109.59
  5015.1  116.36  5021.6  119.05  5150.3  116.69  5176.4  115.94  5231.4  116.95
  5246.3  118.64  5304.9  121.65  5325.8  123.93  5357.3  125.62  5388.8  129.19
  5445.2  133.19  5462.2  136.14  5477.5  136.76  5483.2  138.32  5615.6  150.28
#Mann= 5 ,-1 , 0
  4288.2     .05       0  4798.7     .12       0  4969.2     .07       0
  5021.6     .12       0  5150.3      .1       0
Bank Sta=4969.2,5021.6
XS Rating Curve= 0 ,0
Exp/Cntr=0.3,0.1

Type RM Length L Ch R = 1 ,14181   ,409,409,409
BEGIN DESCRIPTION:
BARBONE CREEK 27.0
END DESCRIPTION:
XS GIS Cut Line= 3
      2307850.63      13201901.3      2307866.26     13200625.24
      2307939.18     13200333.58
#Sta/Elev= 30
  4091.2  143.07  4095.9  143.07  4102.3  139.89  4105.7   138.2  4145.7  135.47
  4261.1  128.33  4331.9  124.96  4394.8  123.19  4579.2  118.62  4685.7  115.66
  4776.8  114.98  4875.7  114.62  4975.7  117.63  4995.7  109.95  5005.5  109.39
  5015.7  112.29  5025.7   116.9  5055.7  116.53  5074.5  112.72  5079.5  115.01
  5085.7  116.05  5124.2  116.68  5245.7  120.33  5364.1  128.84    5558  138.97
  5598.9  140.27    5604  141.57  5623.4  143.03  5640.1  145.33    5668  146.57
#Mann= 10 ,-1 , 0
  4091.2      .1       0  4102.3     .05       0  4331.9      .1       0
  4394.8     .05       0  4579.2      .1       0  4776.8     .12       0
  4975.7     .07       0  5025.7     .12       0  5124.2      .1       0
    5558     .05       0
#XS Ineff= 1 ,-1
    5035 5189.29  117.07
Permanent Ineff=
       T
Bank Sta=4975.7,5025.7
XS Rating Curve= 0 ,0
Exp/Cntr=0.3,0.1

Type RM Length L Ch R = 1 ,13772   ,372,372,372
BEGIN DESCRIPTION:
BARBONE CREEK 26.0
END DESCRIPTION:
XS GIS Cut Line= 3
      2308121.47     13201984.62      2308168.34     13201604.41
      2308334.82     13200610.75
#Sta/Elev= 30
  4030.7  143.03  4292.8  126.22  4383.5  122.47  4614.1  118.53  4686.3  113.36
  4740.7  113.53  4868.3  113.87  4948.8  116.06  4979.1   114.8  4984.6  110.62
  5009.5   109.2 5015.45  114.12  5019.7  115.66    5040  116.17  5090.7  112.31
  5127.4  116.34  5151.5  120.03  5161.5  122.95  5166.6  122.17  5171.8  125.02
  5227.3  133.21  5232.6  135.08  5303.6  141.96  5313.7  144.65  5348.6  149.35
  5394.8  161.09  5404.2  165.03  5409.3  163.49  5415.1  165.52  5421.3  170.11
#Mann= 8 ,-1 , 0
  4030.7      .1       0  4292.8     .05       0  4383.5      .1       0
  4740.7     .05       0  4948.8     .12       0  4979.1     .06       0
  5019.7     .12       0  5127.4      .1       0
#XS Ineff= 1 ,-1
 5035.71 5177.14  115.94
Permanent Ineff=
       T
Bank Sta=4979.1,5015.45
XS Rating Curve= 0 ,0
Exp/Cntr=0.3,0.1

Type RM Length L Ch R = 1 ,13400   ,460,460,460
BEGIN DESCRIPTION:
BARBONE CREEK 25.0
END DESCRIPTION:
XS GIS Cut Line= 4
      2308335.02     13202067.93       2308517.3     13201745.04
      2308673.55     13200656.49      2308657.92     13200484.59
#Sta/Elev= 30
  3910.1  145.85  3963.7  140.76  4056.9   134.8  4075.3  133.54    4260  122.78
    4396   119.4    4585   113.3  4893.1  113.24    4966  113.88  4992.5  107.54
  5016.5  107.27  5022.2   112.2  5036.7  113.71  5091.9  108.51  5134.8  106.38
  5137.5  105.88  5140.8  106.38    5158  123.08  5228.7  124.07  5233.9  129.36
  5269.1  132.08  5299.4   145.1  5304.4  142.08  5319.6  148.78  5369.9  145.54
    5375  141.24  5387.5  146.41  5430.4  149.36  5470.6  162.42  5553.2  168.49
#Mann= 12 ,-1 , 0
  3910.1     .05       0  3963.7      .1       0  4056.9     .05       0
  4075.3      .1       0    4260     .05       0    4396      .1       0
    4585     .05       0  4893.1     .12       0  4992.5     .05       0
  5091.9      .1       0  5134.8    .035       0  5140.8      .1       0
#XS Ineff= 2 , 0
       0                 5056.93       0  114.28
Permanent Ineff=
       F       T
Bank Sta=4966,5036.7
XS Rating Curve= 0 ,0
Exp/Cntr=0.3,0.1