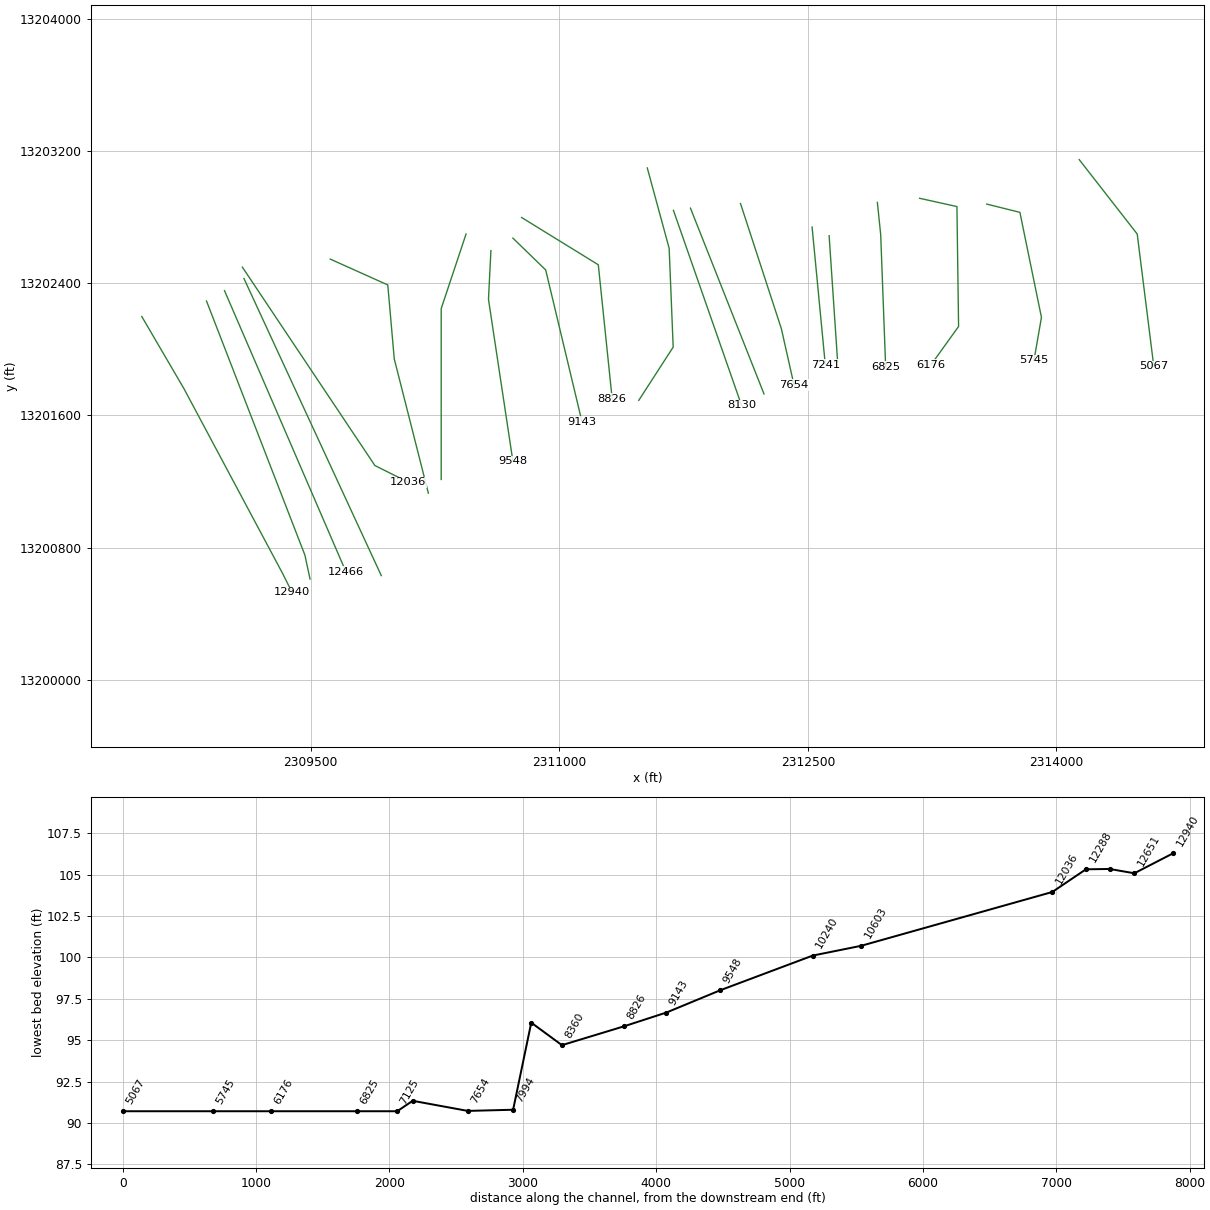
HEC-RAS study BARBONE CREEK.prj: BARBONE CREEK Base Level Engineering

--- BARBONE CREEK.g01 (geometry) --- (continued)

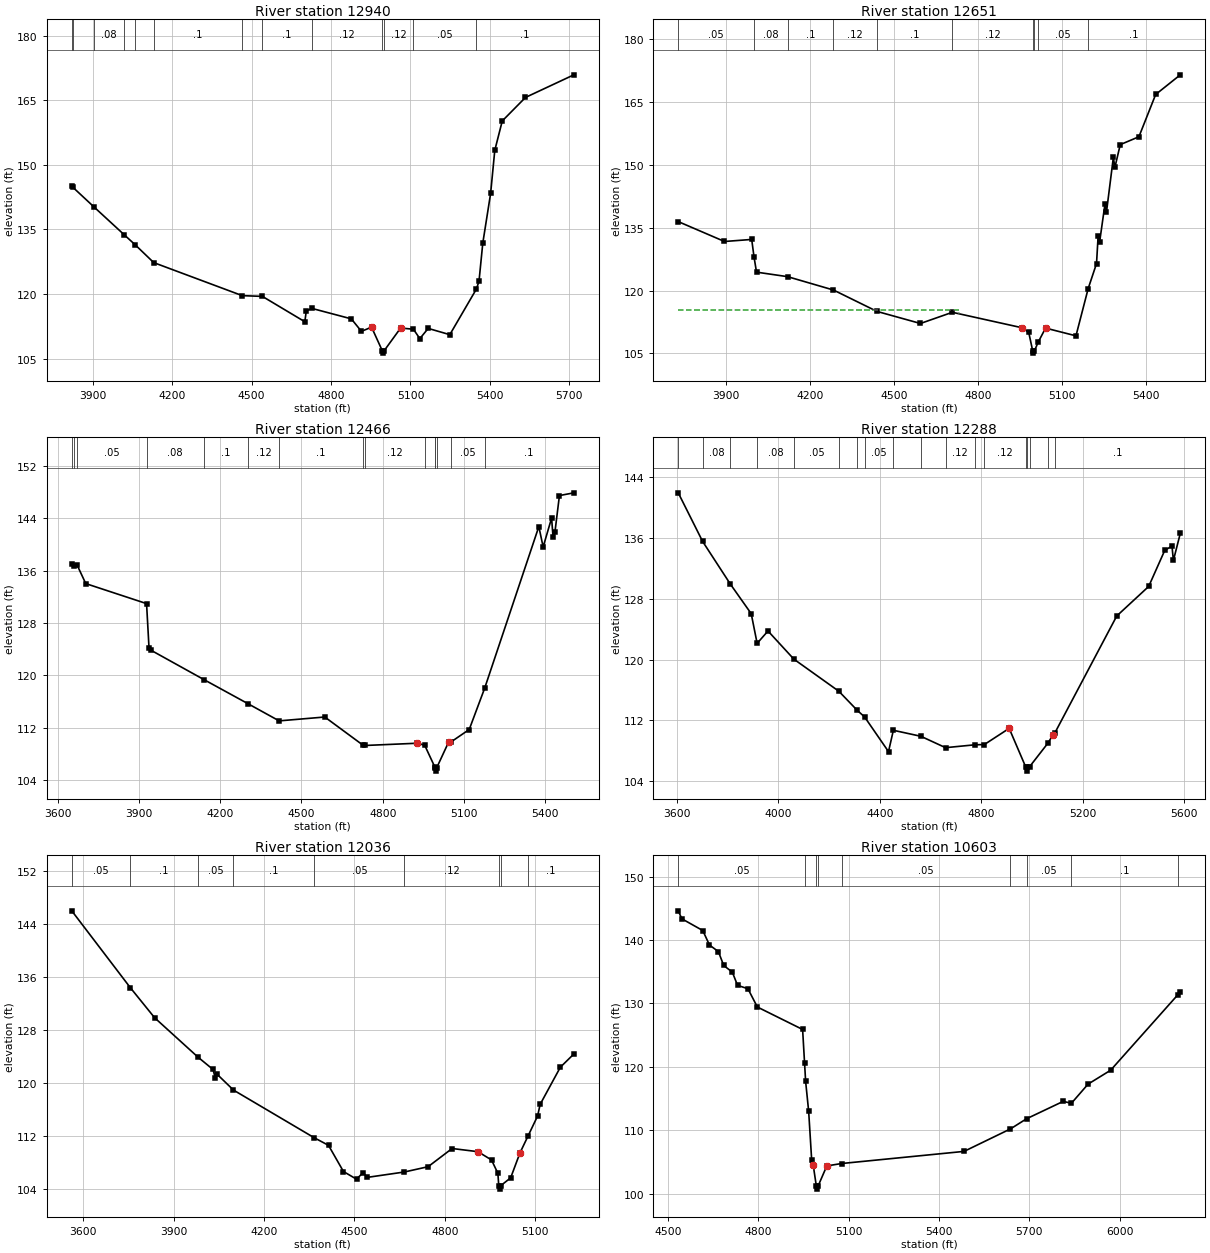
Type RM Length L Ch R = 1 ,12940   ,289,289,289
BEGIN DESCRIPTION:
BARBONE CREEK 24.0
END DESCRIPTION:
XS GIS Cut Line= 4
      2308480.84     13202198.16      2308736.05     13201760.66
       2309329.8     13200646.08      2309387.02     13200531.65
#Sta/Elev= 30
  3820.2  144.99  3823.5  144.85  3905.1  140.18  4017.5  133.82  4060.6   131.4
    4130   127.3  4464.6  119.63  4540.5  119.46  4700.9  113.57  4706.5  116.11
    4728  116.66  4876.6  114.24  4914.8  111.34  4953.1  112.31    4994  106.78
  4996.8  106.28    5000  106.78  5062.9  112.11  5111.3  111.83  5135.5  109.65
  5167.1  112.02  5248.8  110.57  5349.1  121.15  5359.1  122.97  5373.4  131.83
    5403  143.38  5418.7  153.37    5447  160.21  5534.8  165.67  5717.5  170.92
#Mann= 13 ,-1 , 0
  3820.2     .05       0  3823.5      .1       0  3905.1     .08       0
  4017.5      .1       0  4060.6     .08       0    4130      .1       0
  4464.6     .12       0  4540.5      .1       0    4728     .12       0
    4994     .07       0    5000     .12       0  5111.3     .05       0
  5349.1      .1       0
Bank Sta=4953.1,5062.9
XS Rating Curve= 0 ,0
Exp/Cntr=0.3,0.1

Type RM Length L Ch R = 1 ,12651   ,185,185,185
BEGIN DESCRIPTION:
BARBONE CREEK 23.0
END DESCRIPTION:
XS GIS Cut Line= 3
      2308871.46     13202291.93      2309465.22     13200755.45
      2309496.22     13200610.75
#Sta/Elev= 30
  3728.6  136.49    3894  131.74  3991.3  132.23  3999.5  128.08  4008.5  124.42
  4119.6  123.34  4283.6  120.15  4439.3  115.04  4594.6  112.16  4708.7  114.83
  4957.2  111.15  4981.8  110.04  4996.1  105.58  4998.8  105.08  5002.1  105.58
  5015.2  107.65    5042  111.06  5150.7  109.21  5194.4   120.5  5224.2  126.47
  5229.9  132.96  5235.2  131.58  5254.5  140.72  5259.8  138.76  5284.4  151.83
  5289.8  149.41    5309  154.87  5375.8  156.75  5435.7  166.85  5523.8  171.54
#Mann= 10 ,-1 , 0
  3728.6     .05       0  3999.5     .08       0  4119.6      .1       0
  4283.6     .12       0  4439.3      .1       0  4708.7     .12       0
  4996.1     .07       0  5002.1     .12       0  5015.2     .05       0
  5194.4      .1       0
#XS Ineff= 2 , 0
         4732.29   115.4
Permanent Ineff=
       F       F
Bank Sta=4957.2,5042
XS Rating Curve= 0 ,0
Exp/Cntr=0.3,0.1

Type RM Length L Ch R = 1 ,12466   ,178,178,178
BEGIN DESCRIPTION:
Mapping XS 2bf38ee4
END DESCRIPTION:
XS GIS Cut Line= 2
      2308980.16     13202354.25      2309713.68     13200652.84
#Sta/Elev= 30
  3652.5  137.01  3662.5  136.68  3672.1  136.84  3704.1     134  3928.5  130.94
  3937.5  124.21  3943.7  123.84  4139.7  119.34  4301.6  115.67  4417.8  113.02
  4586.2  113.61  4726.5  109.33  4734.7  109.26  4925.6   109.6  4954.7  109.31
  4992.5  105.95  4993.1  105.84  4995.9  105.34  4999.1  105.84  5043.2  109.78
  5053.4  109.84  5119.2   111.7  5176.1     118  5376.1  142.71    5392   139.6
  5423.2  144.01  5428.6  141.08  5435.6   141.9  5452.1  147.45  5505.3  147.87
#Mann= 15 ,-1 , 0
  3652.5     .05       0  3662.5     .08       0  3672.1     .05       0
  3928.5     .08       0  4139.7      .1       0  4301.6     .12       0
  4417.8      .1       0  4726.5     .08       0  4734.7     .12       0
  4954.7     .05       0  4992.5     .12       0  4993.1     .07       0
  4999.1     .12       0  5053.4     .05       0  5176.1      .1       0
Bank Sta=4925.6,5043.2
XS Rating Curve= 0 ,0
Exp/Cntr=0.3,0.1

Type RM Length L Ch R = 1 ,12288   ,252,252,252
BEGIN DESCRIPTION:
Mapping XS 50de5f05
END DESCRIPTION:
XS GIS Cut Line= 2
      2309097.36       13202428.       2309926.2     13200631.47
#Sta/Elev= 30
  3605.6  141.98  3701.8  135.57  3811.1  129.95  3893.2  126.06  3916.5  122.15
  3959.3  123.78  4061.3  120.07  4238.6  115.84  4311.5  113.31  4339.9  112.46
  4434.2  107.89  4453.3   110.7  4561.7  109.91    4659  108.41  4775.4  108.79
  4811.8  108.82  4909.7  110.95  4975.5  105.82  4978.2  105.32  4981.5  105.82
  4990.1   105.9    5062  108.99  5082.6  110.11  5089.4  110.33  5333.7  125.76
  5459.5  129.65  5522.8   134.4  5551.3  134.97  5556.8  133.07  5584.1  136.65
#Mann= 18 ,-1 , 0
  3605.6     .05       0  3701.8     .08       0  3811.1      .1       0
  3916.5     .08       0  4061.3     .05       0  4238.6     .08       0
  4311.5      .1       0  4339.9     .05       0  4453.3     .08       0
  4561.7     .05       0    4659     .12       0  4775.4     .08       0
  4811.8     .12       0  4975.5     .07       0  4981.5     .12       0
  4990.1     .08       0    5062     .12       0  5089.4      .1       0
Bank Sta=4909.7,5082.6
XS Rating Curve= 0 ,0
Exp/Cntr=0.3,0.1

Type RM Length L Ch R = 1 ,12036   ,1433,1433,1433
BEGIN DESCRIPTION:
BARBONE CREEK 22.0
END DESCRIPTION:
XS GIS Cut Line= 3
      2309087.73     13202496.84      2309887.72     13201296.85
      2310087.71     13201196.86
#Sta/Elev= 30
  3562.2  146.01  3756.9  134.37  3837.1  129.85  3980.9   123.9  4030.9  122.03
  4038.4  120.73  4044.4  121.31  4098.7  118.92  4366.8  111.71    4414  110.57
  4463.6  106.61  4507.1  105.45  4528.2  106.43  4543.2  105.73  4665.9  106.54
  4744.5  107.34  4824.1  110.09  4909.8  109.61  4954.8  108.36  4975.9  106.35
  4978.9  104.45  4981.6  103.95  4984.9  104.45  5018.4  105.66  5049.1  109.41
  5075.3  111.91  5107.8  115.01  5116.2  116.76  5183.3  122.38    5228  124.37
#Mann= 9 ,-1 , 0
  3562.2     .05       0  3756.9      .1       0  3980.9     .05       0
  4098.7      .1       0  4366.8     .05       0  4665.9     .12       0
  4978.9     .07       0  4984.9     .12       0  5075.3      .1       0
Bank Sta=4909.8,5049.1
XS Rating Curve= 0 ,0
Exp/Cntr=0.3,0.1

Type RM Length L Ch R = 1 ,10603   ,363,363,363
BEGIN DESCRIPTION:
BARBONE CREEK 21.0
END DESCRIPTION:
XS GIS Cut Line= 4
       2309618.2     13202545.22       2309965.4     13202388.97
      2310004.46     13201941.93      2310210.16     13201129.97
#Sta/Elev= 30
  4534.1  144.59  4546.2  143.33  4615.6  141.48  4637.8   139.2  4667.4  138.16
  4685.1  135.97  4713.7  134.92    4731  132.84  4765.5   132.3  4796.8  129.42
  4947.1  125.88  4953.6  120.55  4957.1  117.68  4967.2  112.96  4977.2  105.26
 4982.39  104.45  4992.6   101.2  4995.3   100.7  4998.6   101.2  5027.4  104.36
  5076.8  104.74  5483.1  106.65  5637.3   110.2  5690.8   111.8  5812.4  114.54
  5839.6  114.24  5894.9  117.26  5969.8  119.45  6192.8  131.34  6201.2  131.73
#Mann= 9 ,-1 , 0
  4534.1     .05       0  4953.6      .1       0  4992.6     .07       0
  4998.6      .1       0  5076.8     .05       0  5637.3     .12       0
  5690.8     .05       0  5839.6      .1       0  6192.8     .05       0
Bank Sta=4982.39,5027.4
XS Rating Curve= 0 ,0
Exp/Cntr=0.3,0.1

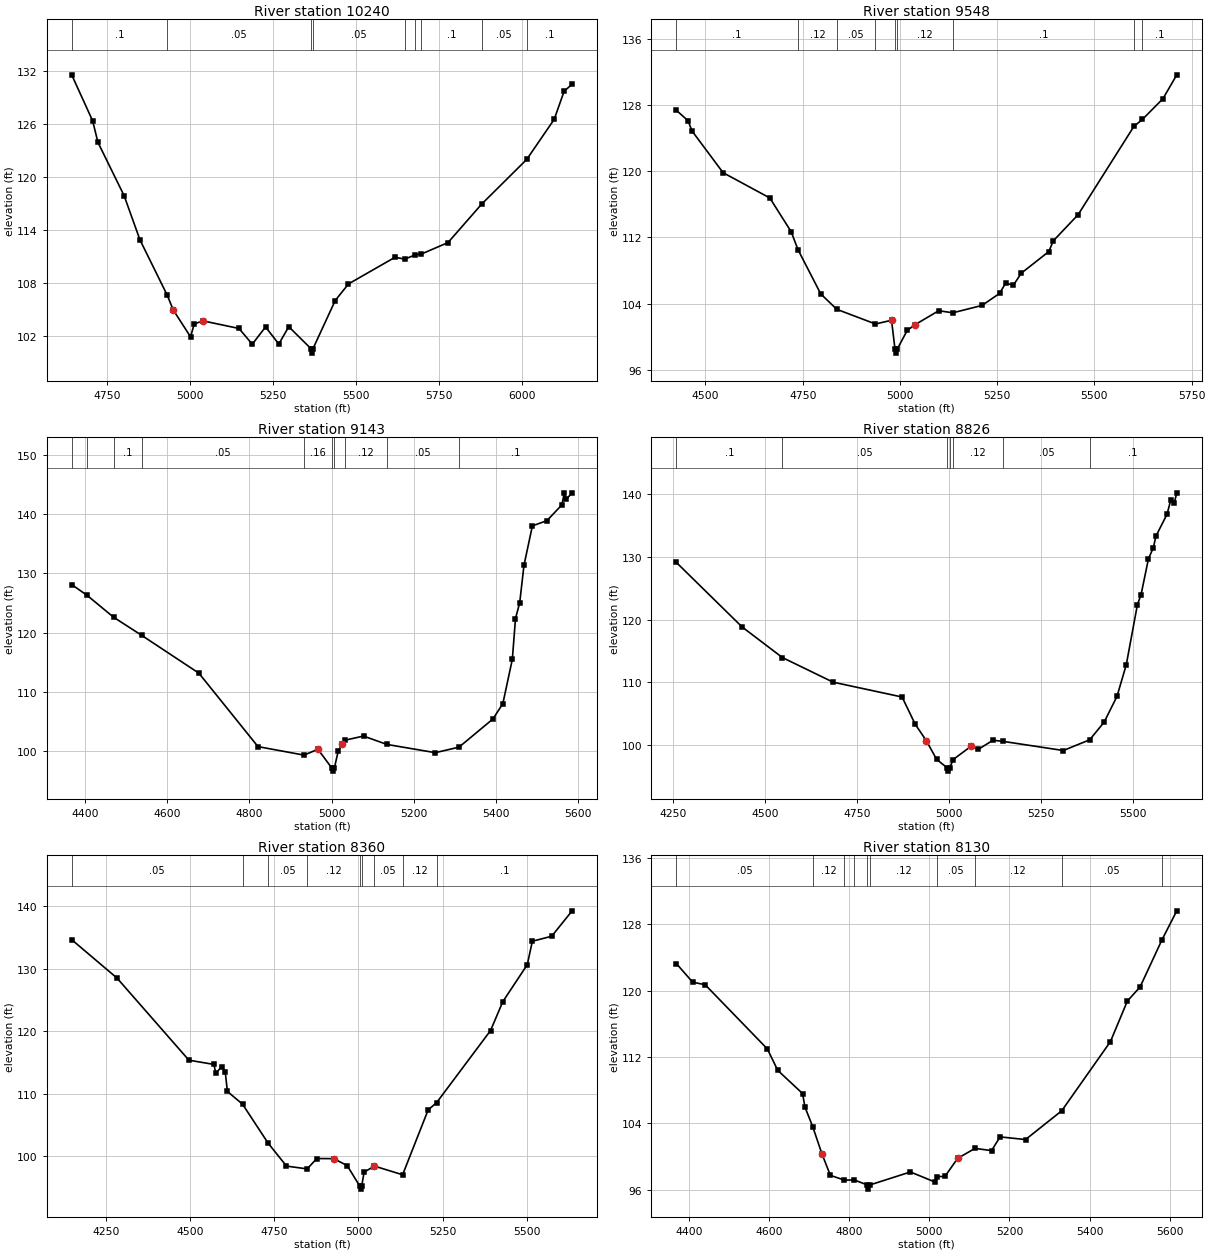
Type RM Length L Ch R = 1 ,10240   ,692,692,692
BEGIN DESCRIPTION:
BARBONE CREEK 20.0
END DESCRIPTION:
XS GIS Cut Line= 3
      2310437.71     13202696.84      2310287.72     13202245.75
      2310287.72     13201212.72
#Sta/Elev= 30
  4643.4   131.6  4706.6  126.39  4722.5  123.96  4801.5  117.92  4849.1  112.93
  4931.6  106.65  4949.4     105  5001.7  101.95  5012.7  103.41  5039.1  103.76
  5147.7   102.9  5187.7  101.12  5227.7  103.07  5267.7  101.14  5297.7   103.1
  5364.7  100.61  5367.4  100.11  5370.7  100.61  5437.7  106.06  5477.7  107.94
  5617.7  110.95  5648.1  110.75  5679.1  111.24  5697.3  111.32  5777.7  112.62
  5879.1  116.97    6015  122.03  6097.7  126.56  6127.7  129.74  6151.8  130.54
#Mann= 9 ,-1 , 0
  4643.4      .1       0  4931.6     .05       0  5364.7     .03       0
  5370.7     .05       0  5648.1      .1       0  5679.1     .05       0
  5697.3      .1       0  5879.1     .05       0    6015      .1       0
Bank Sta=4949.4,5039.1
XS Rating Curve= 0 ,0
Exp/Cntr=0.3,0.1

Type RM Length L Ch R = 1 ,9548    ,405,405,405
BEGIN DESCRIPTION:
BARBONE CREEK 19.0
END DESCRIPTION:
XS GIS Cut Line= 3
      2310587.72      13202596.9      2310573.04     13202302.17
      2310720.56      13201321.6
#Sta/Elev= 30
  4425.1  127.35  4455.2  126.08  4465.2  124.86  4545.3  119.81  4665.4  116.76
  4720.2  112.69  4738.1  110.49  4796.4  105.17  4837.6  103.31  4937.1  101.54
  4978.4  101.99  4987.2   98.52    4990   98.02  4993.2   98.52  5018.8  100.77
  5039.1  101.46  5099.7  103.14    5136  102.89    5211  103.78  5256.1  105.23
  5271.6  106.46  5291.9  106.24  5312.1  107.68  5382.9  110.29  5394.1  111.57
  5458.1  114.74  5601.5   125.4  5623.3  126.24  5676.1  128.74  5711.8  131.63
#Mann= 9 ,-1 , 0
  4425.1      .1       0  4738.1     .12       0  4837.6     .05       0
  4937.1     .12       0  4987.2     .07       0  4993.2     .12       0
    5136      .1       0  5601.5     .05       0  5623.3      .1       0
Bank Sta=4978.4,5039.1
XS Rating Curve= 0 ,0
Exp/Cntr=0.3,0.1

Type RM Length L Ch R = 1 ,9143    ,317,317,317
BEGIN DESCRIPTION:
BARBONE CREEK 18.0
END DESCRIPTION:
XS GIS Cut Line= 3
       2310720.4     13202672.14      2310918.34     13202479.41
       2311137.1     13201562.72
#Sta/Elev= 30
  4367.1  128.11  4403.9  126.33  4469.3   122.6  4537.8  119.54  4676.8  113.18
  4820.8   100.8  4932.9   99.37  4966.8  100.35  5000.8   97.17  5003.5   96.67
  5006.8   97.17  5016.1  100.03  5026.4  101.31  5033.8   101.9  5077.8  102.58
  5134.7  101.17  5252.6   99.78  5310.3  100.71    5393  105.46  5417.1  108.05
  5440.2  115.52  5447.9  122.39  5458.2  125.08  5468.5  131.34    5489     138
  5524.4  138.88    5561  141.55  5566.5  143.49  5571.7  142.51  5585.8  143.57
#Mann= 10 ,-1 , 0
  4367.1      .1       0  4403.9     .05       0  4469.3      .1       0
  4537.8     .05       0  4932.9     .16       0  5000.8     .07       0
  5006.8     .16       0  5033.8     .12       0  5134.7     .05       0
  5310.3      .1       0
Bank Sta=4966.8,5026.4
XS Rating Curve= 0 ,0
Exp/Cntr=0.3,0.1

Type RM Length L Ch R = 1 ,8826    ,466,466,466
BEGIN DESCRIPTION:
BARBONE CREEK 17.0
END DESCRIPTION:
XS GIS Cut Line= 3
      2310772.72     13202796.94      2311235.73     13202510.97
      2311319.41     13201700.38
#Sta/Elev= 30
  4259.9  129.15  4438.5  118.85  4548.1  113.96  4685.6  110.04  4872.9  107.67
  4908.8   103.3  4938.9  100.69  4966.8   97.71  4996.2   96.34    4999   95.84
  5002.2   96.34  5011.5   97.68  5059.6   99.78  5079.7   99.31  5119.9  100.77
    5147  100.59  5310.9   99.13  5382.4  100.84  5421.5  103.64  5456.6  107.77
  5481.8  112.82    5512  122.39    5522  124.03  5542.1  129.74  5555.5  131.52
  5562.2  133.33  5592.4  136.83  5602.4  139.05  5612.5  138.71    5619  140.26
#Mann= 7 ,-1 , 0
  4259.9      .1       0  4548.1     .05       0  4996.2     .03       0
  5002.2     .05       0  5011.5     .12       0    5147     .05       0
  5382.4      .1       0
Bank Sta=4938.9,5059.6
XS Rating Curve= 0 ,0
Exp/Cntr=0.3,0.1

Type RM Length L Ch R = 1 ,8360    ,230,230,230
BEGIN DESCRIPTION:
Mapping XS be223646
END DESCRIPTION:
XS GIS Cut Line= 4
      2311531.37     13203096.45      2311663.32     13202610.33
      2311687.62     13202013.11      2311479.84     13201691.05
#Sta/Elev= 30
  4149.2  134.65  4283.5  128.51  4496.9  115.35  4571.4  114.67  4576.5  113.23
  4594.3  114.33  4604.7  113.49  4611.2  110.34    4656  108.31  4731.9  102.07
  4786.5   98.39  4847.7   97.94  4876.6    99.6  4926.6   99.58  4966.6   98.47
  5003.7    95.2  5006.4    94.7  5009.7    95.2  5016.7   97.42  5045.2   98.32
  5046.7    98.4    5131      97  5206.8  107.39  5231.7  108.54  5391.9   120.1
  5428.2  124.72  5500.8  130.64  5515.9   134.4  5573.3   135.2  5633.9  139.27
#Mann= 9 ,-1 , 0
  4149.2     .05       0    4656     .12       0  4731.9     .05       0
  4847.7     .12       0  5003.7     .07       0  5009.7     .12       0
  5045.2     .05       0    5131     .12       0  5231.7      .1       0
Bank Sta=4926.6,5046.7
XS Rating Curve= 0 ,0
Exp/Cntr=0.3,0.1

Type RM Length L Ch R = 1 ,8130    ,136,136,136
BEGIN DESCRIPTION:
BARBONE CREEK 16.0
END DESCRIPTION:
XS GIS Cut Line= 2
      2311689.15     13202839.85      2312100.32     13201660.36
#Sta/Elev= 30
  4368.7  123.27  4409.4  121.02  4440.5  120.72  4595.9  112.97  4621.7  110.39
  4683.8  107.59  4689.6  105.97  4709.1  103.59  4731.9  100.34  4753.1   97.72
  4788.4   97.14  4812.7   97.17  4845.4   96.56  4848.2   96.06  4851.4   96.56
  4952.9   98.13    5015    96.9  5019.9   97.57  5039.1   97.59  5070.8   99.77
    5114  100.97  5155.5  100.71  5176.7  102.36  5240.3  102.04  5330.6  105.51
  5452.1  113.85  5494.4  118.74  5526.2  120.45  5580.7  126.12  5617.8  129.63
#Mann= 10 ,-1 , 0
  4368.7     .05       0  4709.1     .12       0  4788.4      .1       0
  4812.7     .12       0  4845.4     .07       0  4851.4     .12       0
  5019.9     .05       0    5114     .12       0  5330.6     .05       0
  5580.7      .1       0
Bank Sta=4731.9,5070.8
XS Rating Curve= 0 ,0
Exp/Cntr=0.3,0.1

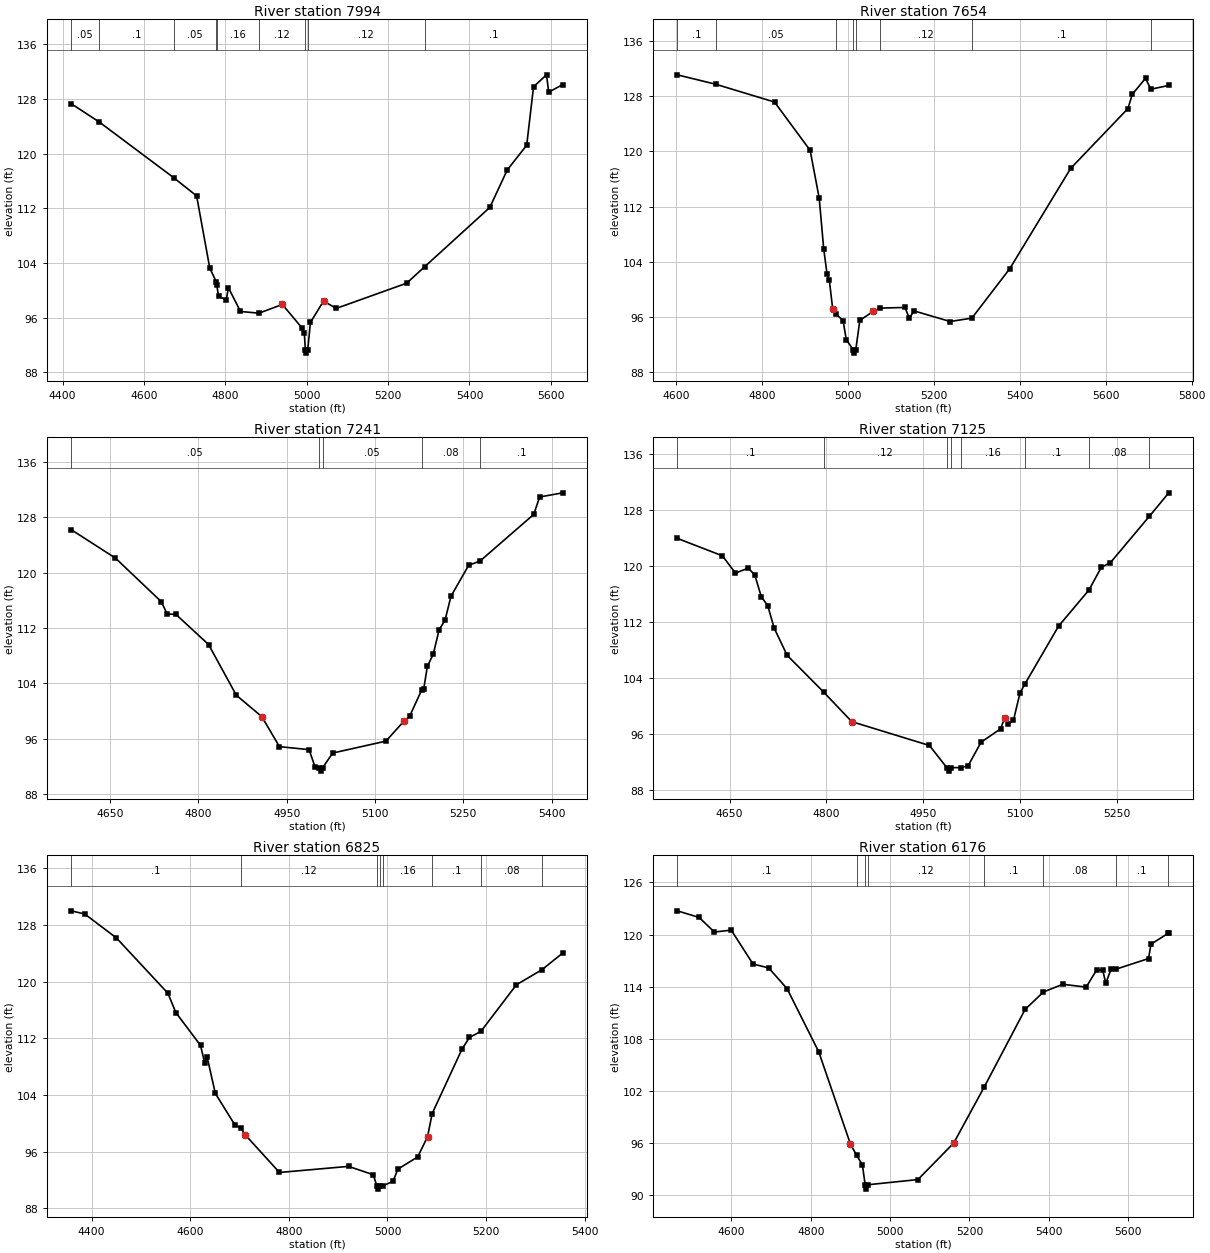
Type RM Length L Ch R = 1 ,7994    ,340,340,340
BEGIN DESCRIPTION:
BARBONE CREEK 15.0
END DESCRIPTION:
XS GIS Cut Line= 2
      2311791.78     13202853.42      2312235.56      13201730.1
#Sta/Elev= 30
  4421.4  127.32  4490.5  124.63  4672.7  116.51  4729.5  113.82  4761.8  103.26
  4777.7  101.25  4779.1  100.75  4783.3   99.15  4802.2   98.57  4807.6  100.37
  4837.3    96.9  4882.8   96.65  4940.1   97.93  4987.6   94.55  4994.2   93.73
  4996.6    91.3  4999.4    90.8  5002.6    91.3  5009.1   95.29  5041.3   98.42
  5072.7   97.35  5245.7  101.04  5290.4  103.48  5449.9  112.13  5492.9  117.63
  5540.6  121.24  5557.4   129.8  5589.3  131.55  5594.7  129.01  5629.2  130.13
#Mann= 9 ,-1 , 0
  4421.4     .05       0  4490.5      .1       0  4672.7     .05       0
  4777.7      .1       0  4779.1     .16       0  4882.8     .12       0
  4996.6     .07       0  5002.6     .12       0  5290.4      .1       0
Bank Sta=4940.1,5041.3
XS Rating Curve= 0 ,0
Exp/Cntr=0.3,0.1

Type RM Length L Ch R = 1 ,7654    ,413,413,413
BEGIN DESCRIPTION:
Mapping XS eb17c9c9
END DESCRIPTION:
XS GIS Cut Line= 3
      2312093.87     13202881.16       2312340.4     13202124.22
      2312416.78     13201783.97
#Sta/Elev= 30
  4601.9  131.12  4691.7  129.75  4828.4  127.17  4911.4  120.16  4932.5  113.22
    4943  105.86  4950.8  102.19  4956.1  101.29    4964    97.1  4970.7   96.45
    4988   95.46  4995.6   92.68  5011.7   91.23  5014.4   90.73  5017.7   91.23
  5027.1   95.48  5058.7   96.81  5073.7   97.26  5132.3   97.36  5142.3   95.79
  5153.3   96.86  5237.5   95.32  5288.1   95.81  5376.3  102.98  5518.3  117.55
  5651.5  126.22  5661.7  128.28  5692.5  130.62  5704.8  129.03  5746.7  129.58
#Mann= 8 ,-1 , 0
  4601.9      .1       0  4691.7     .05       0  4970.7     .16       0
  5011.7     .07       0  5017.7     .16       0  5073.7     .12       0
  5288.1      .1       0  5704.8     .05       0
Bank Sta=4964,5058.7
XS Rating Curve= 0 ,0
Exp/Cntr=0.3,0.1

Type RM Length L Ch R = 1 ,7241    ,116,116,116
BEGIN DESCRIPTION:
BARBONE CREEK 14.0
END DESCRIPTION:
XS GIS Cut Line= 2
      2312525.81     13202739.08      2312605.34     13201907.78
#Sta/Elev= 30
    4584  126.18  4659.1  122.08  4736.9   115.8    4747  114.02  4761.8  113.96
  4817.3  109.61  4864.5  102.29  4907.7   99.21  4937.8   94.87  4988.1   94.44
  4998.1   91.97  5005.2   91.84  5007.9   91.34  5011.2   91.84  5028.2   93.95
  5118.7   95.67  5148.8   98.51  5158.8   99.23  5179.5  103.07  5182.8  103.14
    5189  106.45    5199   108.2  5209.1  111.75  5219.1  113.13  5229.2  116.58
  5259.3  121.05  5278.5  121.65  5369.8  128.39  5379.8   130.9  5419.1   131.5
#Mann= 5 ,-1 , 0
    4584     .05       0  5005.2     .04       0  5011.2     .05       0
  5179.5     .08       0  5278.5      .1       0
Bank Sta=4907.7,5148.8
XS Rating Curve= 0 ,0
Exp/Cntr=0.3,0.1

Type RM Length L Ch R = 1 ,7125    ,300,300,300
BEGIN DESCRIPTION:
BARBONE CREEK 13.0
END DESCRIPTION:
XS GIS Cut Line= 2
      2312628.59     13202686.73      2312679.69     13201926.65
#Sta/Elev= 30
  4568.8  123.93  4638.8  121.44  4658.9  118.98  4678.9  119.68    4689   118.7
    4699  115.61    4709  114.33    4719  111.12  4739.1  107.24  4795.6     102
  4839.3   97.77  4959.6   94.37  4986.6   91.21  4989.4   90.71  4992.6   91.21
  5009.2   91.21  5019.7    91.5  5039.7   94.84  5069.8   96.74  5076.2   98.27
  5081.2   97.38  5089.9   97.96  5099.9  101.84    5108  103.21    5160  111.43
  5206.9  116.56  5225.9  119.78  5240.2  120.47  5300.5  127.08  5330.6  130.43
#Mann= 8 ,-1 , 0
  4568.8      .1       0  4795.6     .12       0  4986.6     .07       0
  4992.6     .12       0  5009.2     .16       0    5108      .1       0
  5206.9     .08       0  5300.5      .1       0
Bank Sta=4839.3,5076.2
XS Rating Curve= 0 ,0
Exp/Cntr=0.3,0.1

Type RM Length L Ch R = 1 ,6825    ,649,649,649
BEGIN DESCRIPTION:
BARBONE CREEK 12.0
END DESCRIPTION:
XS GIS Cut Line= 3
       2312919.8     13202887.89       2312939.8     13202692.92
       2312969.8     13201892.88
#Sta/Elev= 30
  4358.8  129.97  4386.2  129.52  4450.3  126.15  4554.8  118.34  4570.9  115.62
  4620.9  110.99  4629.3  108.54  4634.3  109.36  4650.9  104.22    4691   99.72
  4702.7   99.35    4711   98.41    4781   93.06  4921.1   93.92  4971.2   92.74
  4978.2   91.21  4980.9   90.71  4984.2   91.21  4991.9   91.21  5011.2   91.82
  5021.2   93.54  5061.2   95.25  5081.2   98.09  5090.6  101.37  5151.3  110.49
  5166.3  112.11  5189.4  112.96  5261.4  119.54    5313  121.65  5355.4  124.02
#Mann= 8 ,-1 , 0
  4358.8      .1       0  4702.7     .12       0  4978.2     .07       0
  4984.2     .12       0  4991.9     .16       0  5090.6      .1       0
  5189.4     .08       0    5313      .1       0
Bank Sta=4711,5081.2
XS Rating Curve= 0 ,0
Exp/Cntr=0.3,0.1

Type RM Length L Ch R = 1 ,6176    ,431,431,431
BEGIN DESCRIPTION:
BARBONE CREEK 11.0
END DESCRIPTION:
XS GIS Cut Line= 4
      2313174.84     13202912.91       2313399.8     13202862.92
       2313409.8     13202137.92      2313244.79      13201907.9
#Sta/Elev= 30
  4463.6  122.73  4518.7  121.97  4557.1  120.29  4599.7  120.51  4654.5  116.61
    4694  116.16  4740.1  113.79  4820.1  106.51  4900.1   95.88  4915.6    94.6
  4930.1   93.51  4937.1   91.21  4939.9   90.71  4943.1   91.21  5070.1   91.81
  5160.2   96.01  5237.5  102.49  5340.2  111.39  5386.3  113.39  5435.1  114.28
    5494  113.95    5521  115.97  5535.8  115.89  5543.5   114.4  5556.7  116.01
  5568.1     116  5651.2  117.24  5657.3  118.89  5700.2  120.13  5702.2  120.13
#Mann= 8 ,-1 , 0
  4463.6      .1       0  4915.6     .12       0  4937.1     .07       0
  4943.1     .12       0  5237.5      .1       0  5386.3     .08       0
  5568.1      .1       0  5700.2     .05       0
Bank Sta=4900.1,5160.2
XS Rating Curve= 0 ,0
Exp/Cntr=0.3,0.1

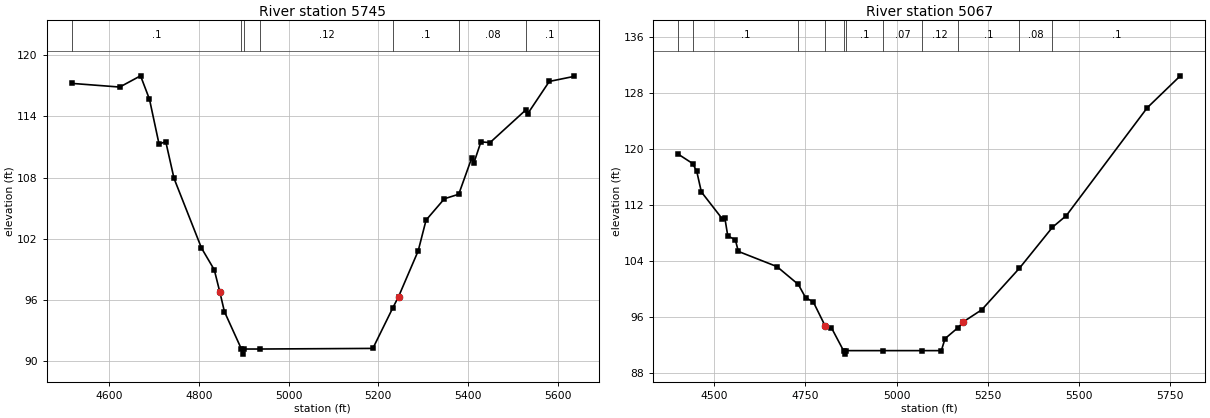
Type RM Length L Ch R = 1 ,5745    ,678,678,678
BEGIN DESCRIPTION:
BARBONE CREEK 10.0
END DESCRIPTION:
XS GIS Cut Line= 4
      2313579.79     13202877.92       2313779.8     13202827.92
       2313909.8     13202192.92       2313864.8     13201932.92
#Sta/Elev= 30
  4517.2  117.23    4624  116.87  4670.4  117.97  4690.3  115.67  4711.6  111.28
  4726.5  111.53  4744.9  107.93  4806.1   101.1  4834.6   98.97  4846.9    96.8
  4857.2   94.87    4895   91.21  4897.7   90.71    4901   91.21  4936.4   91.21
  5187.8   91.27  5232.5   95.27    5245   96.34  5288.7  100.82  5306.3  103.84
  5347.1  105.93    5379  106.37  5408.1  109.94  5413.1  109.48  5428.4   111.5
  5448.7  111.43  5528.7  114.64  5532.7  114.26  5580.7  117.42  5635.4  117.91
#Mann= 7 ,-1 , 0
  4517.2      .1       0    4895     .07       0    4901      .1       0
  4936.4     .12       0  5232.5      .1       0    5379     .08       0
  5528.7      .1       0
Bank Sta=4846.9,5245
XS Rating Curve= 0 ,0
Exp/Cntr=0.3,0.1

Type RM Length L Ch R = 1 ,5067    ,470,470,470
BEGIN DESCRIPTION:
BARBONE CREEK 9.0
END DESCRIPTION:
XS GIS Cut Line= 3
      2314137.69     13203146.89      2314487.72     13202696.85
      2314587.73     13201896.81
#Sta/Elev= 30
  4401.5  119.26  4441.2  117.92  4452.2  116.82  4464.9  113.87  4522.8  109.99
  4529.1  110.21  4537.3  107.59  4558.1  107.03  4566.2  105.38  4672.1  103.21
  4730.7  100.66  4750.8   98.76  4771.7   98.17  4804.5   94.71  4821.4   94.48
  4854.6   91.21  4857.4   90.71  4860.6   91.21  4962.9   91.21  5069.1   91.21
  5122.8   91.21  5132.9   92.92  5168.9   94.51  5183.3   95.33  5233.7   97.05
  5336.9  102.98  5427.5  108.83  5465.4  110.49  5687.2  125.89  5777.9  130.45
#Mann= 11 ,-1 , 0
  4401.5     .05       0  4441.2      .1       0  4730.7     .12       0
  4804.5      .1       0  4854.6     .07       0  4860.6      .1       0
  4962.9     .07       0  5069.1     .12       0  5168.9      .1       0
  5336.9     .08       0  5427.5      .1       0
Bank Sta=4804.5,5183.3
XS Rating Curve= 0 ,0
Exp/Cntr=0.3,0.1