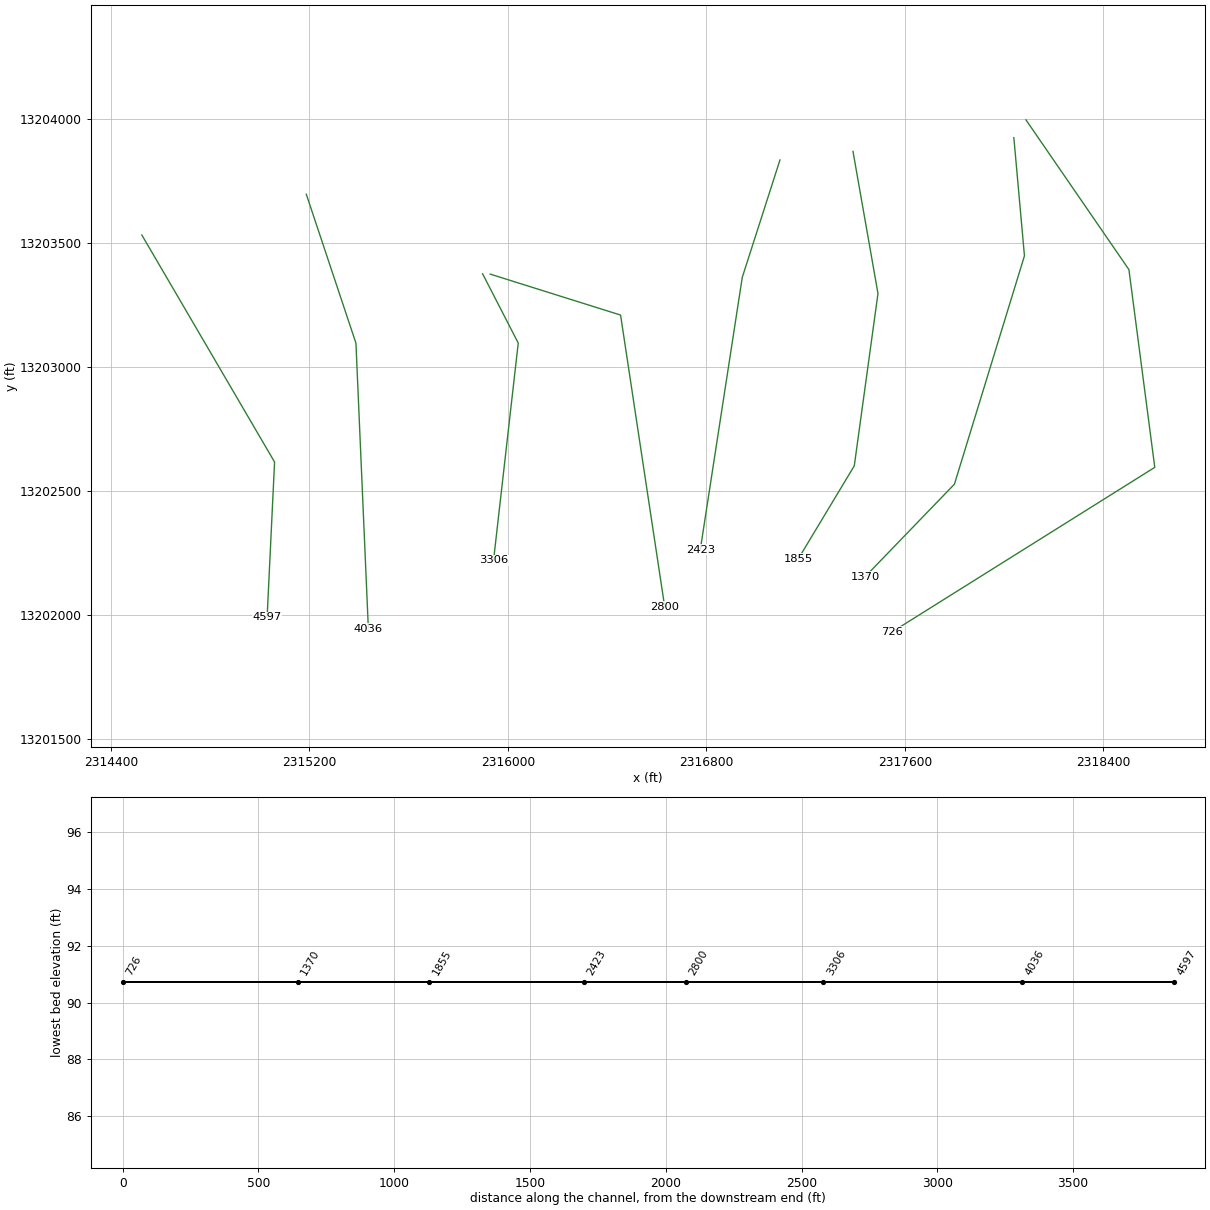
HEC-RAS study BARBONE CREEK.prj: BARBONE CREEK Base Level Engineering

--- BARBONE CREEK.g01 (geometry) --- (continued)

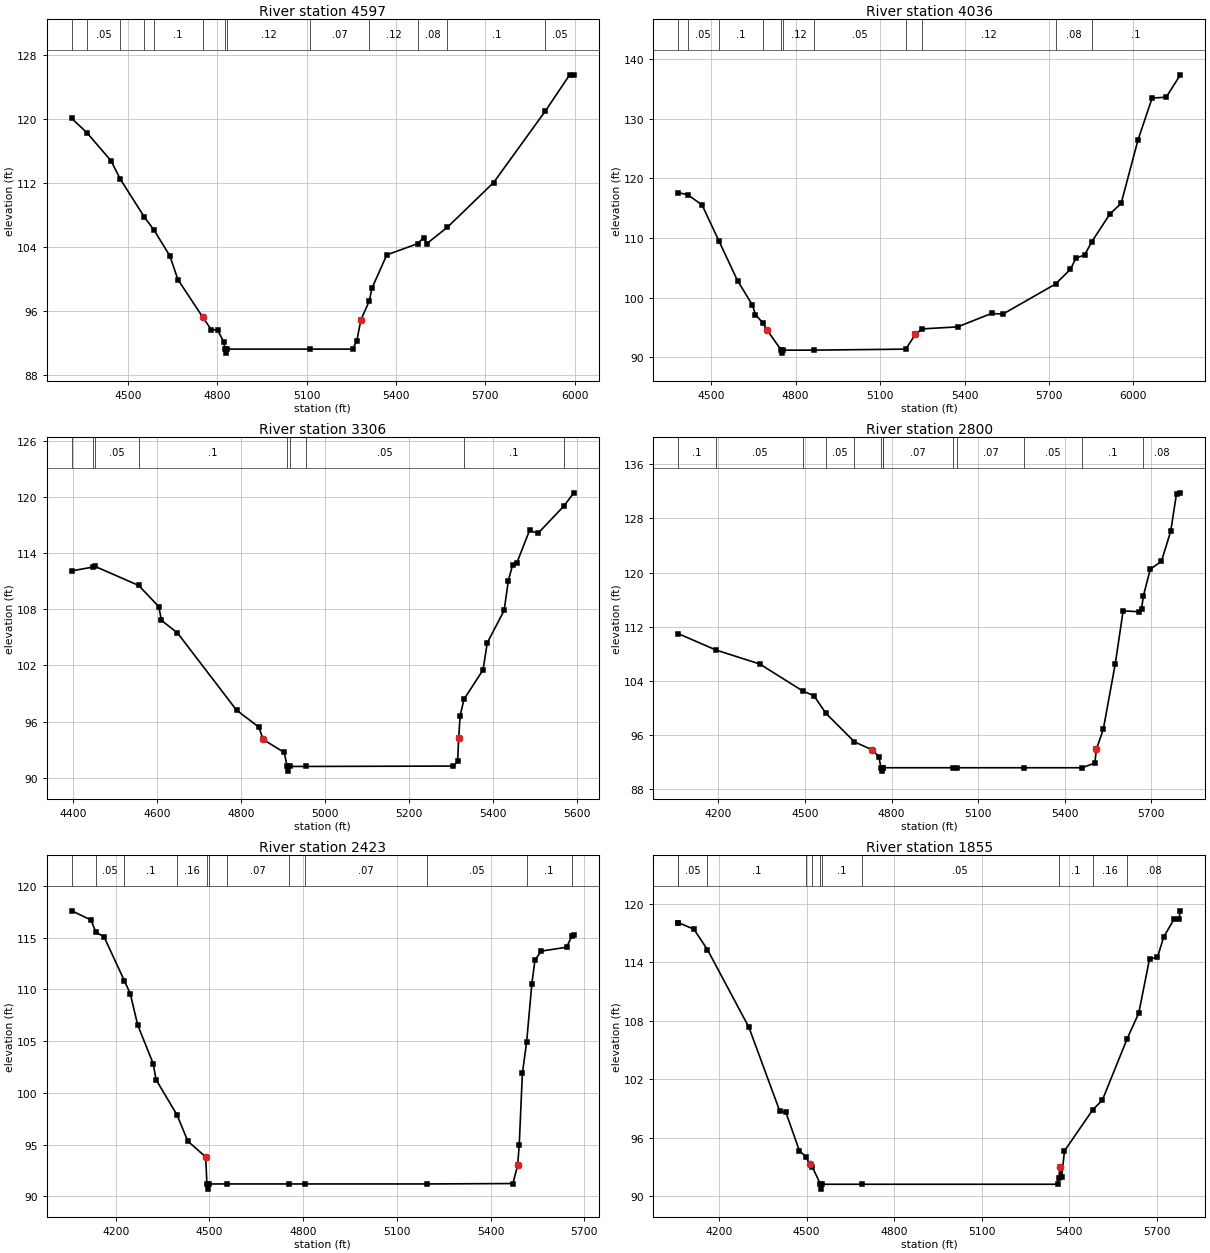
Type RM Length L Ch R = 1 ,4597    ,561,561,561
BEGIN DESCRIPTION:
BARBONE CREEK 8.0
END DESCRIPTION:
XS GIS Cut Line= 3
      2314524.81     13203532.91       2315059.8     13202617.92
       2315029.8     13201992.96
#Sta/Elev= 30
  4311.9  120.04  4362.6  118.26  4443.5  114.76  4475.1  112.44  4555.2  107.74
  4587.6  106.11    4641  102.88  4668.3    99.9  4750.8   95.25  4779.9   93.66
  4801.4   93.59  4822.8   92.06  4825.6   91.21  4828.4   90.71  4831.6   91.21
    5113   91.21  5255.1   91.21  5268.8   92.24  5282.4   94.85  5311.1   97.26
  5319.5   98.81  5369.5  102.99  5473.9   104.4    5493  105.16    5503  104.37
    5573  106.44  5728.2  112.03  5902.1  120.98  5983.6  125.49  5997.5  125.49
#Mann= 13 ,-1 , 0
  4311.9      .1       0  4362.6     .05       0  4475.1      .1       0
  4555.2     .05       0  4587.6      .1       0  4750.8     .12       0
  4825.6     .07       0  4831.6     .12       0    5113     .07       0
  5311.1     .12       0  5473.9     .08       0    5573      .1       0
  5902.1     .05       0
Bank Sta=4750.8,5282.4
XS Rating Curve= 0 ,0
Exp/Cntr=0.3,0.1

Type RM Length L Ch R = 1 ,4036    ,730,730,730
BEGIN DESCRIPTION:
BARBONE CREEK 7.0
END DESCRIPTION:
XS GIS Cut Line= 3
      2315187.71     13203696.89      2315387.72     13203096.85
      2315437.72     13201946.83
#Sta/Elev= 30
    4383  117.58  4416.2  117.27  4467.4  115.55  4526.9  109.57  4593.9  102.83
  4646.6   98.77  4657.1   97.17  4683.4   95.78  4699.3   94.52    4749   91.21
  4751.7   90.71    4755   91.21    4865   91.21  5191.2   91.38  5225.7   93.87
  5249.8   94.77  5375.8   95.11  5495.9   97.36    5536   97.24  5723.4  102.29
  5776.2  104.75  5796.2  106.65  5826.3  107.13  5851.4  109.32  5916.3  114.01
  5956.4   115.8  6016.4  126.45  6066.5  133.45  6116.5  133.59  6166.6  137.34
#Mann= 11 ,-1 , 0
    4383      .1       0  4416.2     .05       0  4526.9      .1       0
  4683.4     .12       0    4749    .033       0    4755     .12       0
    4865     .05       0  5191.2     .07       0  5249.8     .12       0
  5723.4     .08       0  5851.4      .1       0
Bank Sta=4699.3,5225.7
XS Rating Curve= 0 ,0
Exp/Cntr=0.3,0.1

Type RM Length L Ch R = 1 ,3306    ,506,506,506
BEGIN DESCRIPTION:
BARBONE CREEK 6.0
END DESCRIPTION:
XS GIS Cut Line= 3
      2315898.09     13203376.48      2316041.79     13203097.31
      2315942.26     13202222.04
#Sta/Elev= 30
  4397.7  112.09  4447.6  112.49  4452.8  112.57  4557.1  110.53  4604.9  108.26
    4611  106.81  4649.3  105.46  4789.8   97.22    4843   95.41    4853   94.09
  4903.4    92.7  4910.4   91.21  4913.2   90.71  4916.4   91.21  4955.2   91.21
  5305.9   91.25    5316   91.74 5318.41   94.21    5322   96.63  5331.2   98.39
  5376.4  101.51  5386.5   104.4  5426.7  107.87  5436.8  111.06  5446.8  112.72
  5456.9  112.93  5487.1  116.41  5507.2  116.09  5568.7     119  5592.6  120.42
#Mann= 9 ,-1 , 0
  4397.7     .05       0  4447.6      .1       0  4452.8     .05       0
  4557.1      .1       0  4910.4    .033       0  4916.4      .1       0
  4955.2     .05       0  5331.2      .1       0  5568.7     .08       0
Bank Sta=4853,5318.41
XS Rating Curve= 0 ,0
Exp/Cntr=0.3,0.1

Type RM Length L Ch R = 1 ,2800    ,377,377,377
BEGIN DESCRIPTION:
BARBONE CREEK 5.0
END DESCRIPTION:
XS GIS Cut Line= 3
      2315928.93     13203375.09      2316454.12     13203210.16
      2316632.07     13202033.92
#Sta/Elev= 30
  4060.7     111  4191.1  108.59  4343.1  106.52  4492.5  102.53  4531.1  101.83
  4572.4   99.25  4671.5   95.03  4733.2   93.84  4756.1   92.84  4763.2   91.21
    4766   90.71  4769.2   91.21    4771   91.21  5013.7   91.21  5027.6   91.21
  5260.2   91.21  5460.6   91.21  5504.5    91.9 5510.08   93.97  5533.8   96.86
  5575.3  106.53  5602.6  114.36  5656.2  114.24  5666.3  114.63  5672.9  116.57
  5696.7  120.51  5735.2  121.66  5767.5  126.11  5787.7  131.67  5800.8  131.78
#Mann= 13 ,-1 , 0
  4060.7      .1       0  4191.1     .05       0  4492.5      .1       0
  4572.4     .05       0  4671.5     .16       0  4763.2     .07       0
  4769.2     .16       0    4771     .07       0  5013.7     .12       0
  5027.6     .07       0  5260.2     .05       0  5460.6      .1       0
  5672.9     .08       0
Bank Sta=4733.2,5510.08
XS Rating Curve= 0 ,0
Exp/Cntr=0.3,0.1

Type RM Length L Ch R = 1 ,2423    ,568,568,568
BEGIN DESCRIPTION:
BARBONE CREEK 4.0
END DESCRIPTION:
XS GIS Cut Line= 3
      2317096.49     13203835.18      2316944.57     13203362.07
      2316775.29     13202263.94
#Sta/Elev= 30
  4058.9   117.6  4120.2  116.72  4136.3  115.53  4162.2  115.09  4227.3  110.85
  4246.2   109.6    4270  106.57  4319.7  102.83  4328.9  101.28  4396.2   97.87
  4430.5   95.35  4487.8   93.82  4491.7   91.21  4494.5   90.71  4497.7   91.21
  4555.5   91.21  4753.8   91.21  4805.4   91.21  5196.1   91.21  5471.7   91.25
  5486.9   93.01  5491.9   94.93  5502.1   101.9  5515.7  104.93  5532.4  110.55
  5542.5  112.86  5562.8  113.71  5643.7  114.08  5660.4  115.15  5666.9  115.24
#Mann= 12 ,-1 , 0
  4058.9     .16       0  4136.3     .05       0  4227.3      .1       0
  4396.2     .16       0  4491.7     .07       0  4497.7     .16       0
  4555.5     .07       0  4753.8     .05       0  4805.4     .07       0
  5196.1     .05       0  5515.7      .1       0  5660.4     .08       0
Bank Sta=4487.8,5486.9
XS Rating Curve= 0 ,0
Exp/Cntr=0.3,0.1

Type RM Length L Ch R = 1 ,1855    ,485,485,485
BEGIN DESCRIPTION:
BARBONE CREEK 3.0
END DESCRIPTION:
XS GIS Cut Line= 4
      2317390.73     13203869.76      2317491.44     13203296.96
      2317395.96     13202602.52      2317170.45     13202227.92
#Sta/Elev= 30
  4060.6  118.09  4060.7  118.09  4114.3  117.41  4160.5  115.32  4302.6  107.34
  4408.8   98.69  4429.1   98.62  4475.5   94.66  4498.2   94.02  4510.3   93.34
  4519.9   92.98  4547.9   91.21  4550.7   90.71  4553.9   91.21  4688.4   91.21
  5361.4   91.21  5363.8   91.83  5368.1   92.94  5373.9   91.92  5383.6   94.64
  5481.2   98.89  5513.2   99.84  5598.6  106.18    5638  108.79  5674.9  114.35
  5702.1  114.52  5723.5  116.62  5760.4  118.51  5775.9  118.49  5780.4   119.3
#Mann= 11 ,-1 , 0
  4060.6      .1       0  4060.7     .05       0  4160.5      .1       0
  4498.2     .16       0  4519.9      .1       0  4547.9    .033       0
  4553.9      .1       0  4688.4     .05       0  5363.8      .1       0
  5481.2     .16       0  5598.6     .08       0
Bank Sta=4510.3,5368.1
XS Rating Curve= 0 ,0
Exp/Cntr=0.3,0.1

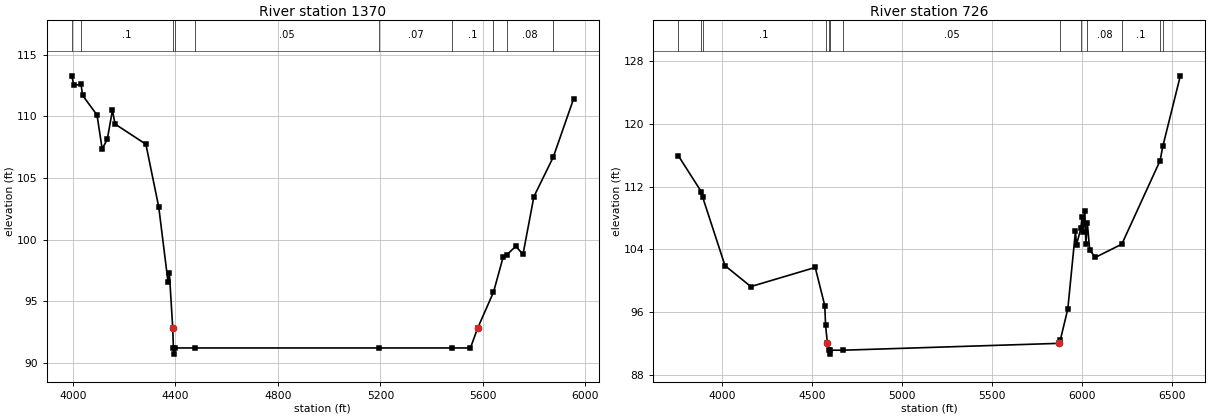
Type RM Length L Ch R = 1 ,1370    ,644,644,644
BEGIN DESCRIPTION:
BARBONE CREEK 2.0
END DESCRIPTION:
XS GIS Cut Line= 4
      2318039.01     13203925.04      2318081.72     13203448.87
       2317799.6     13202528.73      2317439.39      13202155.5
#Sta/Elev= 30
  3995.1  113.29  4003.3  112.53  4031.3  112.59  4037.5   111.7  4093.7  110.11
  4113.8  107.36  4133.8  108.14  4153.9   110.5    4164  109.38  4284.4  107.74
  4334.6  102.65  4371.1   96.53  4376.1   97.29  4389.2   92.85  4391.9   91.21
  4394.6   90.71  4397.9   91.21  4475.4   91.21  5194.3   91.21  5479.1   91.21
  5551.3   91.21  5579.6   92.82  5641.4   95.74  5678.7   98.56  5693.4   98.77
  5728.3   99.46  5756.6   98.81  5799.1  103.49  5874.8   106.7  5954.3  111.44
#Mann= 10 ,-1 , 0
  3995.1     .08       0  4031.3      .1       0  4391.9    .033       0
  4397.9      .1       0  4475.4     .05       0  5194.3     .07       0
  5479.1      .1       0  5641.4     .16       0  5693.4     .08       0
  5874.8      .1       0
Bank Sta=4389.2,5579.6
XS Rating Curve= 0 ,0
Exp/Cntr=0.3,0.1

Type RM Length L Ch R = 1 ,726     ,0,0,0
BEGIN DESCRIPTION:
BARBONE CREEK 1.0
END DESCRIPTION:
XS GIS Cut Line= 4
      2318087.73     13203996.85      2318502.73     13203393.32
      2318606.89     13202596.44      2317548.71      13201933.5
#Sta/Elev= 30
  3758.6  115.89  3885.3  111.35  3893.6  110.61    4017  101.95  4160.4   99.29
  4517.7  101.72  4570.7   96.86  4575.1   94.36 4585.44   92.07  4595.4   91.21
  4598.2   90.71  4601.4   91.21  4674.4   91.21  5870.9   92.08  5877.6    92.5
  5919.1   96.45  5961.5  106.29  5967.4  104.61  5991.4  106.68  5998.1  108.13
    6004  106.22  6013.4  108.95  6019.3  104.71  6027.6  107.34  6040.5  103.96
  6071.1  102.99  6218.8  104.68  6431.2  115.29  6446.2   117.1  6543.4  126.06
#Mann= 13 ,-1 , 0
  3758.6      .1       0  3885.3     .08       0  3893.6      .1       0
  4575.1     .07       0  4595.4    .033       0  4601.4     .07       0
  4674.4     .05       0  5877.6     .08       0  5991.4      .1       0
  6027.6     .08       0  6218.8      .1       0  6431.2     .08       0
  6446.2      .1       0
Bank Sta=4585.44,5870.9
XS Rating Curve= 0 ,0
Exp/Cntr=0.3,0.1

Chan Stop Cuts=-1
Use User Specified Reach Order=0
Composite Channel Slope=5