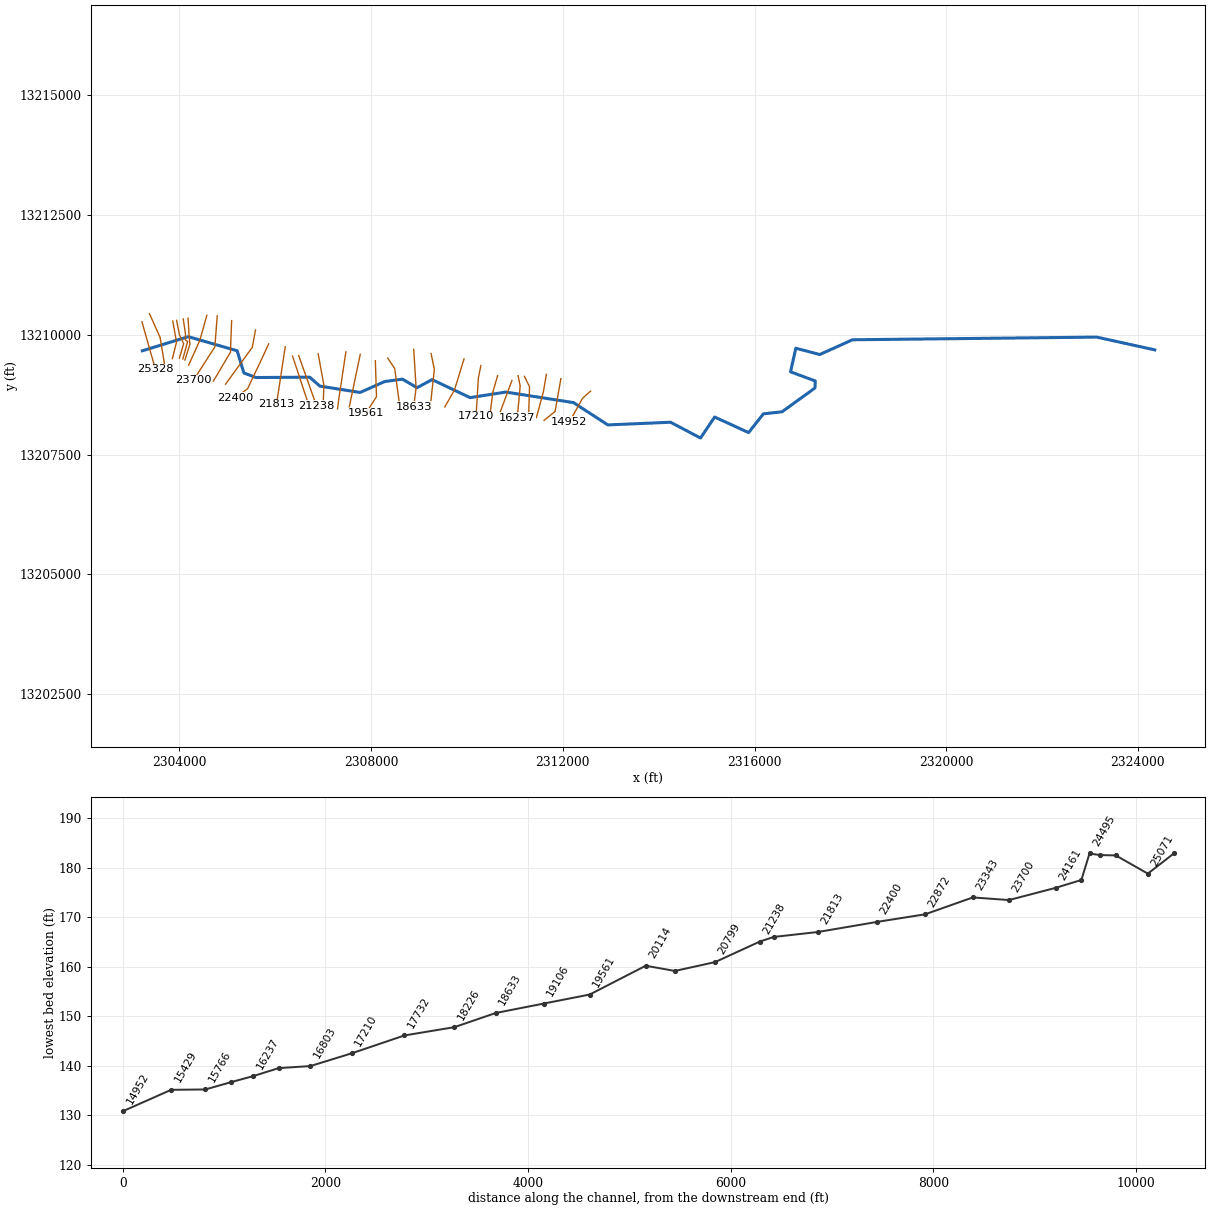
--- CHARQUITAS CREEK.prj (project) ---

Proj Title=CHARQUITAS CREEK Base Level Engineering
Current Plan=p01
Default Exp/Contr=0.3,0.1
English Units
Geom File=g01
Flow File=f01
Plan File=p01
Y Axis Title=Elevation
X Axis Title(PF)=Main Channel Distance
X Axis Title(XS)=Station
BEGIN DESCRIPTION:
CHARQUITAS CREEK
END DESCRIPTION:
DSS Export Rating Curves= 0
DSS Export Rating Curve Sorted= 0
DSS Export Volume Flow Curves= 0
DXF OffsetX= 0
DXF OffsetY= 0
DXF ScaleX= 1
DXF ScaleY= 10

--- CHARQUITAS CREEK.p01 (plan) ---

Plan Title=Multiple Run
Short Identifier=Multiple
Geom File=g01
Flow File=f01
Subcritical Flow
K Sum by GR= 0
Std Step Tol= 0.01
Critical Tol= 0.01
Num of Std Step Trials= 20
Max Error Tol= 0.3
Flow Tol Ratio= 0.001
Split Flow NTrial= 30
Split Flow Tol= 0.02
Split Flow Ratio= 0.02
Log Output Level= 0
Friction Slope Method= 1
Unsteady Friction Slope Method= 2
Unsteady Bridges Friction Slope Method= 1
Parabolic Critical Depth
Global Vel Dist=  1 , 1 , 1
Global Log Level= 0
CheckData=True
Encroach Param= -1, 0, 0, 0
BEGIN DESCRIPTION:
Multiple Run
END DESCRIPTION:

--- CHARQUITAS CREEK.f01 (steady flow) ---

Flow Title=Multiple
Program Version=4.10
Number of Profiles= 7
Profile Names=10-year,25-year,50-year,1pct_min,100-year,1pct_plu,500-year
River Rch & RM=CHARQUITAS CREEK,Reach-1         ,25328
     482     666     816     730     987    1335    1452
River Rch & RM=CHARQUITAS CREEK,Reach-1         ,23700
    1267    1838    2327    2144    2900    3922    4525
Boundary for River Rch & Prof#=CHARQUITAS CREEK,Reach-1         , 1
Up Type= 0
Dn Type= 3
Dn Slope=0.0004
Boundary for River Rch & Prof#=CHARQUITAS CREEK,Reach-1         , 2
Up Type= 0
Dn Type= 3
Dn Slope=0.0004
Boundary for River Rch & Prof#=CHARQUITAS CREEK,Reach-1         , 3
Up Type= 0
Dn Type= 3
Dn Slope=0.0004
Boundary for River Rch & Prof#=CHARQUITAS CREEK,Reach-1         , 4
Up Type= 0
Dn Type= 3
Dn Slope=0.0004
Boundary for River Rch & Prof#=CHARQUITAS CREEK,Reach-1         , 5
Up Type= 0
Dn Type= 3
Dn Slope=0.0004
Boundary for River Rch & Prof#=CHARQUITAS CREEK,Reach-1         , 6
Up Type= 0
Dn Type= 3
Dn Slope=0.0004
Boundary for River Rch & Prof#=CHARQUITAS CREEK,Reach-1         , 7
Up Type= 0
Dn Type= 3
Dn Slope=0.0004
DSS Import GetInterval= 0
DSS Import GetPeak= 0
DSS Import FillOption= 0

--- CHARQUITAS CREEK.g01 (geometry) ---

Geom Title=Existing Conditions
Program Version=4.10

River Reach=CHARQUITAS CREEK,Reach-1
Reach XY= 30
      2303224.97     13209666.48      2304183.27     13209961.43
      2305202.49     13209667.26      2305343.39     13209204.93
      2305593.17     13209108.44      2306717.24     13209115.92
      2306928.91     13208929.62      2307768.91      13208796.8
      2308283.54     13209025.13      2308651.88     13209075.19
      2308957.55     13208896.49      2309271.92      13209065.2
      2310063.66     13208689.12      2310807.37     13208805.41
      2312222.17     13208585.15      2312938.99     13208119.85
      2314247.22     13208175.66      2314872.69     13207846.21
      2315167.89     13208284.47      2315876.62     13207959.66
      2316185.18     13208351.22      2316573.99     13208393.77
      2317261.19     13208890.33      2317268.24     13209035.81
      2316751.33     13209228.29      2316861.96     13209719.87
      2317360.93     13209588.59      2318044.33     13209896.48
      2323141.56     13209952.03      2324352.54     13209685.63

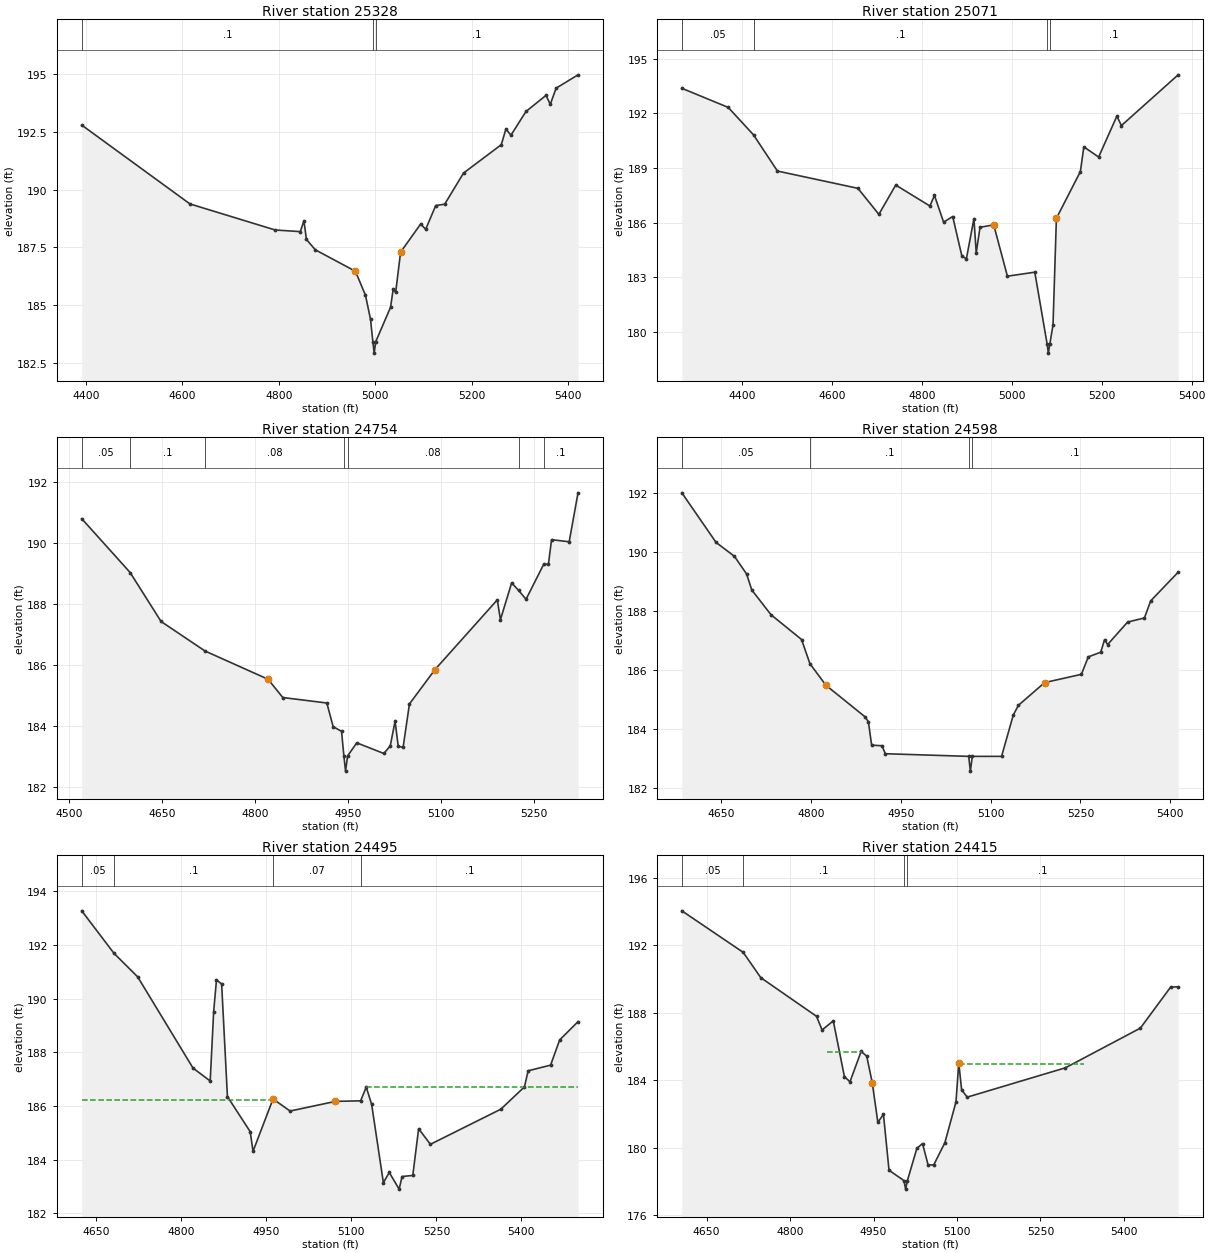
Type RM Length L Ch R = 1 ,25328   ,257,257,257
BEGIN DESCRIPTION:
CHARQUITAS CREEK 45.0
END DESCRIPTION:
XS GIS Cut Line= 2
      2303216.18     13210272.67      2303497.44     13209283.06
#Sta/Elev= 30
  4391.2   192.8  4615.6  189.38  4792.3  188.25  4844.3  188.18  4851.8  188.65
    4857  187.84  4875.5  187.39  4958.6  186.46  4979.4  185.42  4989.8  184.38
  4994.7  183.41  4997.4  182.91  5000.7  183.41  5031.4   184.9  5036.8  185.68
    5042  185.55  5052.2  187.29  5093.8  188.51  5104.2  188.28    5125  189.31
  5143.6  189.37  5182.7  190.72  5260.9  191.95  5270.5  192.63  5280.9  192.36
  5312.1  193.39  5353.7  194.09  5362.5   193.7  5374.5   194.4    5420  194.98
#Mann= 3 ,-1 , 0
  4391.2      .1       0  4994.7     .07       0  5000.7      .1       0
Bank Sta=4958.6,5052.2
XS Rating Curve= 0 ,0
Exp/Cntr=0.3,0.1

Type RM Length L Ch R = 1 ,25071   ,317,317,317
BEGIN DESCRIPTION:
Mapping XS 8f0bc09c
END DESCRIPTION:
XS GIS Cut Line= 3
      2303373.84     13210440.92      2303595.07     13209945.55
      2303686.45     13209392.48
#Sta/Elev= 30
  4266.9  193.38  4369.9  192.33  4426.2  190.82  4479.4  188.83  4658.3  187.88
  4704.8  186.45  4742.3  188.06  4818.2  186.91  4828.4  187.49  4848.7  186.02
  4868.9  186.33  4889.2  184.17  4899.3     184  4916.1  186.21  4921.2  184.34
  4929.7  185.74  4960.1  185.87  4990.5  183.05  5051.4  183.27  5078.8  179.32
  5081.5  178.82  5084.8  179.32  5091.9  180.37  5099.4  186.23  5152.7   188.8
  5160.4  190.16  5193.3   189.6  5233.8  191.85  5243.9  191.33    5370  194.12
#Mann= 4 ,-1 , 0
  4266.9     .05       0  4426.2      .1       0  5078.8     .07       0
  5084.8      .1       0
Bank Sta=4960.1,5099.4
XS Rating Curve= 0 ,0
Exp/Cntr=0.3,0.1

Type RM Length L Ch R = 1 ,24754   ,156,156,156
BEGIN DESCRIPTION:
CHARQUITAS CREEK 44.0
END DESCRIPTION:
XS GIS Cut Line= 3
      2303860.22     13210286.37      2303937.72     13209846.85
      2303851.74     13209502.94
#Sta/Elev= 30
  4519.8  190.81  4597.9  189.04  4647.8  187.43  4718.7  186.46  4820.5  185.53
  4844.2  184.93  4915.3  184.75  4925.5  183.97    4939  183.82  4942.8  183.01
  4945.5  182.51  4948.8  183.01  4963.6  183.44  5007.3  183.09  5017.6  183.34
  5025.4  184.15  5030.5  183.33  5038.3  183.29  5048.6  184.72  5089.8  185.85
  5190.3  188.14  5195.4  187.49  5213.5   188.7  5224.8  188.45  5236.7  188.16
  5265.2  189.31  5272.8  189.31  5277.9  190.12  5306.3  190.05  5320.6  191.66
#Mann= 7 ,-1 , 0
  4519.8     .05       0  4597.9      .1       0  4718.7     .08       0
  4942.8     .07       0  4948.8     .08       0  5224.8     .05       0
  5265.2      .1       0
Bank Sta=4820.5,5089.8
XS Rating Curve= 0 ,0
Exp/Cntr=0.3,0.1

Type RM Length L Ch R = 1 ,24598   ,103,103,103
BEGIN DESCRIPTION:
Mapping XS 0997c95b
END DESCRIPTION:
XS GIS Cut Line= 4
      2303939.64      13210302.9      2303998.24     13210003.41
      2304087.21     13209814.61      2303998.23     13209512.94
#Sta/Elev= 30
  4584.6     192  4641.7  190.32  4672.3  189.85  4692.7  189.25  4701.3  188.71
  4733.4  187.87  4784.4  187.03  4798.4  186.21  4825.1  185.48  4889.8  184.42
  4895.9  184.25  4901.4  183.45  4918.7  183.43  4924.2  183.16  5063.4  183.07
  5066.2  182.57  5069.4  183.07  5118.3  183.07  5137.8  184.47  5146.4   184.8
  5190.1  185.57  5251.5  185.85    5263  186.44  5283.8   186.6  5290.1  187.02
  5295.3  186.86  5328.6  187.62  5356.7  187.76  5367.2  188.34    5413  189.31
#Mann= 4 ,-1 , 0
  4584.6     .05       0  4798.4      .1       0  5063.4     .07       0
  5069.4      .1       0
Bank Sta=4825.1,5190.1
XS Rating Curve= 0 ,0
Exp/Cntr=0.3,0.1

Type RM Length L Ch R = 1 ,24495   ,80,80,80
BEGIN DESCRIPTION:
Mapping XS 23d8c18f
END DESCRIPTION:
XS GIS Cut Line= 5
      2304078.52     13210331.15       2304124.1     13210022.94
       2304124.1     13209892.74      2304169.68     13209860.18
      2304069.84     13209495.57
#Sta/Elev= 30
  4624.1  193.27  4680.9  191.69  4722.8  190.81  4820.5  187.41  4850.8  186.93
  4856.9  189.51  4861.9   190.7    4871  190.54  4881.2  186.35  4921.4  185.04
  4926.4  184.31  4961.7  186.26  4991.7  185.81  5071.9  186.17  5116.2  186.19
  5126.2   186.7  5135.7  186.06  5156.4  183.14  5166.8  183.52  5184.2   182.9
  5189.4  183.37  5208.3  183.41  5218.6  185.15  5239.4  184.57  5363.8  185.88
  5405.3  186.71  5411.9  187.31  5451.5  187.52  5467.5  188.46  5499.9  189.14
#Mann= 4 ,-1 , 0
  4624.1     .05       0  4680.9      .1       0  4961.7     .07       0
  5116.2      .1       0
#XS Ineff= 2 , 0
       0 4959.72  186.21 5126.39       0  186.69
Permanent Ineff=
       T       T
Bank Sta=4961.7,5071.9
XS Rating Curve= 0 ,0
Exp/Cntr=0.3,0.1

Type RM Length L Ch R = 1 ,24415   ,254,254,254
BEGIN DESCRIPTION:
CHARQUITAS CREEK 43.0
END DESCRIPTION:
XS GIS Cut Line= 4
      2304178.35     13210348.51      2304202.73     13209954.67
      2304217.42     13209803.76      2304113.26     13209473.94
#Sta/Elev= 30
  4605.4  194.03  4715.7  191.57  4747.3  190.07  4847.5  187.78  4857.5  186.97
  4877.6  187.51  4897.6  184.21  4907.6   183.9  4927.7   185.7  4937.7  185.42
  4947.7  183.84  4957.7   181.5  4967.8  181.97  4977.8  178.66  5004.8  178.04
  5007.6  177.54  5010.8  178.04  5027.9  179.96    5038  180.24    5048  178.98
  5058.1  178.97  5078.2  180.29  5098.2  182.71  5103.2  185.03  5108.3  183.42
  5118.4  182.99    5295  184.73  5429.6  187.08    5484  189.51  5497.5  189.53
#Mann= 4 ,-1 , 0
  4605.4     .05       0  4715.7      .1       0  5004.8     .07       0
  5010.8      .1       0
#XS Ineff= 2 ,-1
 4866.67 4928.47  185.69 5103.47 5328.47  184.95
Permanent Ineff=
       T       T
Bank Sta=4947.7,5103.2
XS Rating Curve= 0 ,0
Exp/Cntr=0.3,0.1

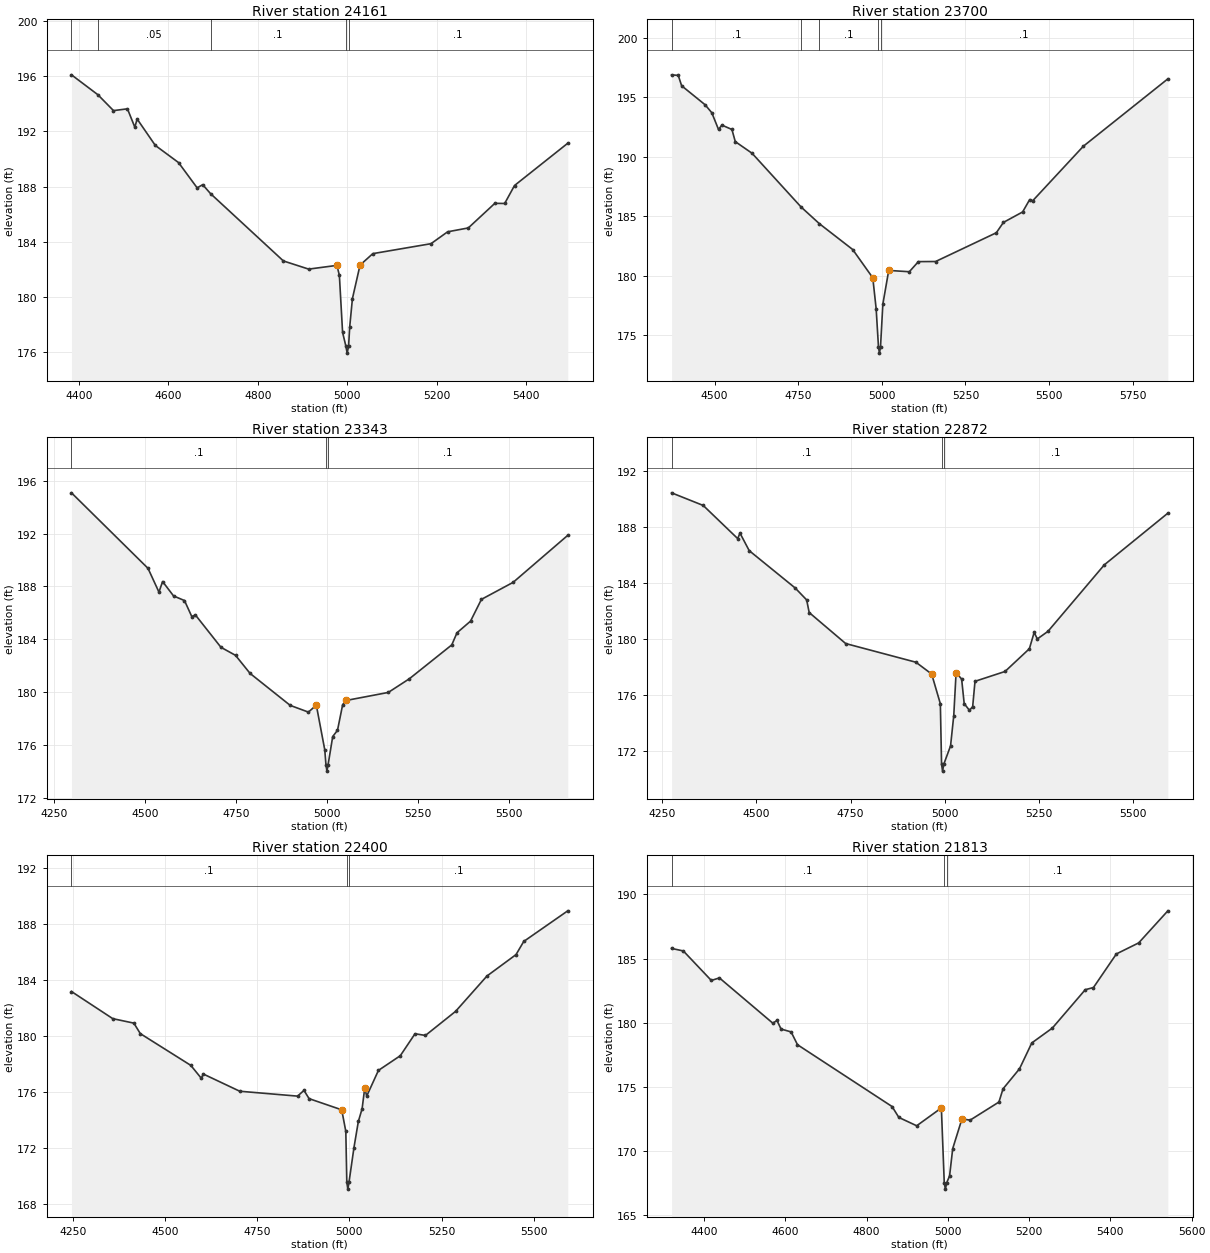
Type RM Length L Ch R = 1 ,24161   ,461,461,461
BEGIN DESCRIPTION:
Mapping XS 89674e07
END DESCRIPTION:
XS GIS Cut Line= 3
       2304571.4     13210407.22      2304422.31     13209878.21
      2304191.44     13209368.37
#Sta/Elev= 30
  4383.7  196.09  4442.7  194.65  4477.6   193.5  4508.8  193.63  4525.3   192.3
  4530.5  192.89  4571.1  190.98    4623  189.74  4664.6  187.91    4677  188.14
  4694.6  187.49  4857.4  182.62  4913.9  182.03    4977   182.3  4982.5  181.58
  4989.7  177.45  4997.1  176.45  4999.9  175.95  5003.1  176.45  5005.6  177.85
  5011.7   179.9  5028.7  182.32  5057.3  183.15  5187.3  183.87  5224.5  184.73
  5270.7  185.01    5330  186.79    5352  186.78    5374  188.08    5493  191.14
#Mann= 5 ,-1 , 0
  4383.7      .1       0  4442.7     .05       0  4694.6      .1       0
  4997.1     .07       0  5003.1      .1       0
Bank Sta=4977,5028.7
XS Rating Curve= 0 ,0
Exp/Cntr=0.3,0.1

Type RM Length L Ch R = 1 ,23700   ,357,357,357
BEGIN DESCRIPTION:
CHARQUITAS CREEK 42.0
END DESCRIPTION:
XS GIS Cut Line= 3
      2304787.72     13210396.83      2304737.72     13209746.85
       2304287.7     13209046.82
#Sta/Elev= 30
  4371.1   196.9  4391.1  196.85  4401.2  195.98  4471.4  194.38  4491.4  193.71
  4511.5   192.3  4521.5  192.67  4551.6   192.3  4561.6  191.28  4611.8   190.3
  4758.3  185.78  4813.2  184.37  4912.7   182.2  4972.8  179.82  4982.9  177.22
  4989.9  173.98  4992.7  173.48  4995.9  173.98  5002.9   177.6  5020.5  180.44
  5082.1  180.33  5109.2  181.18  5160.7  181.19  5342.3  183.61  5363.5  184.48
  5420.9  185.36    5442   186.4    5451   186.3  5602.5  190.89  5855.2  196.56
#Mann= 5 ,-1 , 0
  4371.1      .1       0  4758.3     .05       0  4813.2      .1       0
  4989.9     .07       0  4995.9      .1       0
Bank Sta=4972.8,5020.5
XS Rating Curve= 0 ,0
Exp/Cntr=0.3,0.1

Type RM Length L Ch R = 1 ,23343   ,471,471,471
BEGIN DESCRIPTION:
CHARQUITAS CREEK 41.0
END DESCRIPTION:
XS GIS Cut Line= 3
      2305087.72     13210296.84      2305063.95     13209637.09
       2304706.3     13209032.89
#Sta/Elev= 30
  4298.4  195.09  4508.5  189.37  4538.5  187.57  4548.5  188.37  4578.6  187.28
  4608.6  186.93  4628.6  185.72  4638.6  185.84  4708.7  183.39  4748.7  182.78
  4788.7  181.41  4898.8  178.99  4948.8  178.48  4970.5  179.01  4993.7  175.62
  4996.9  174.51  4999.6  174.01  5002.9  174.51  5015.5  176.63  5028.6   177.1
  5042.8  179.04  5051.8  179.36    5168  179.97  5226.1  181.01  5342.3  183.57
  5356.7  184.49  5393.8  185.37  5423.7  187.02  5510.8  188.31  5660.7  191.87
#Mann= 3 ,-1 , 0
  4298.4      .1       0  4996.9     .07       0  5002.9      .1       0
Bank Sta=4970.5,5051.8
XS Rating Curve= 0 ,0
Exp/Cntr=0.3,0.1

Type RM Length L Ch R = 1 ,22872   ,472,472,472
BEGIN DESCRIPTION:
CHARQUITAS CREEK 40.0
END DESCRIPTION:
XS GIS Cut Line= 3
      2305586.21     13210099.41      2305518.88     13209738.74
      2304960.97      13208969.2
#Sta/Elev= 30
  4274.8  190.43  4358.8  189.53  4450.3  187.17  4456.4  187.56  4480.9  186.31
  4602.9  183.65  4633.4   182.8  4640.1   181.9    4737  179.69  4923.4  178.36
  4965.2  177.52  4988.3   175.4  4991.5   171.1  4994.2   170.6  4997.5   171.1
  5015.4   172.4  5023.9  174.56  5030.1  177.62  5044.8  177.16  5051.6  175.41
  5065.6  174.93  5074.1   175.2  5080.3     177    5160   177.7  5224.6  179.32
  5237.3  180.48  5245.8  180.02    5274  180.56  5423.6   185.3  5592.2  188.98
#Mann= 3 ,-1 , 0
  4274.8      .1       0  4991.5     .07       0  4997.5      .1       0
Bank Sta=4965.2,5030.1
XS Rating Curve= 0 ,0
Exp/Cntr=0.3,0.1

Type RM Length L Ch R = 1 ,22400   ,587,587,587
BEGIN DESCRIPTION:
CHARQUITAS CREEK 39.0
END DESCRIPTION:
XS GIS Cut Line= 4
      2305860.37      13209810.9      2305764.17     13209599.26
      2305422.69     13208877.83      2305172.65     13208685.49
#Sta/Elev= 30
  4246.1   183.2  4358.1  181.26  4415.3  180.94  4432.8  180.19  4569.7  177.92
  4598.1     177  4603.7   177.3  4702.5  176.07  4859.4  175.72  4876.7  176.13
  4890.6  175.54  4979.1  174.74  4990.2   173.2  4992.9  169.57  4995.7  169.07
  4998.9  169.57  5012.3  172.04  5024.2  173.91  5034.4  174.82  5041.4  176.27
    5047  175.73  5078.7  177.56    5138  178.61  5177.9  180.18  5206.2  180.06
  5287.9  181.78  5373.1  184.31  5451.9  185.84  5472.8  186.78  5592.2  188.97
#Mann= 3 ,-1 , 0
  4246.1      .1       0  4992.9     .07       0  4998.9      .1       0
Bank Sta=4979.1,5041.4
XS Rating Curve= 0 ,0
Exp/Cntr=0.3,0.1

Type RM Length L Ch R = 1 ,21813   ,437,437,437
BEGIN DESCRIPTION:
CHARQUITAS CREEK 38.0
END DESCRIPTION:
XS GIS Cut Line= 2
      2306206.65     13209753.19      2306023.88     13208545.95
#Sta/Elev= 30
  4320.4  185.79  4349.4  185.59  4418.2  183.29  4438.1  183.49  4569.5  179.96
  4579.7  180.17  4589.8   179.5  4614.5  179.28  4630.2  178.28  4862.9  173.46
  4879.6  172.61  4923.5  171.96  4984.2  173.35  4991.3  167.52  4994.1  167.02
  4997.3  167.52  5004.4  168.05  5012.1  170.18  5034.8  172.49    5055   172.4
  5125.8  173.81  5135.9  174.84  5176.4   176.4  5206.7  178.42  5257.3  179.58
  5338.2  182.57  5358.4  182.74  5414.8  185.36  5469.7  186.22  5541.4  188.72
#Mann= 3 ,-1 , 0
  4320.4      .1       0  4991.3     .07       0  4997.3      .1       0
Bank Sta=4984.2,5034.8
XS Rating Curve= 0 ,0
Exp/Cntr=0.3,0.1

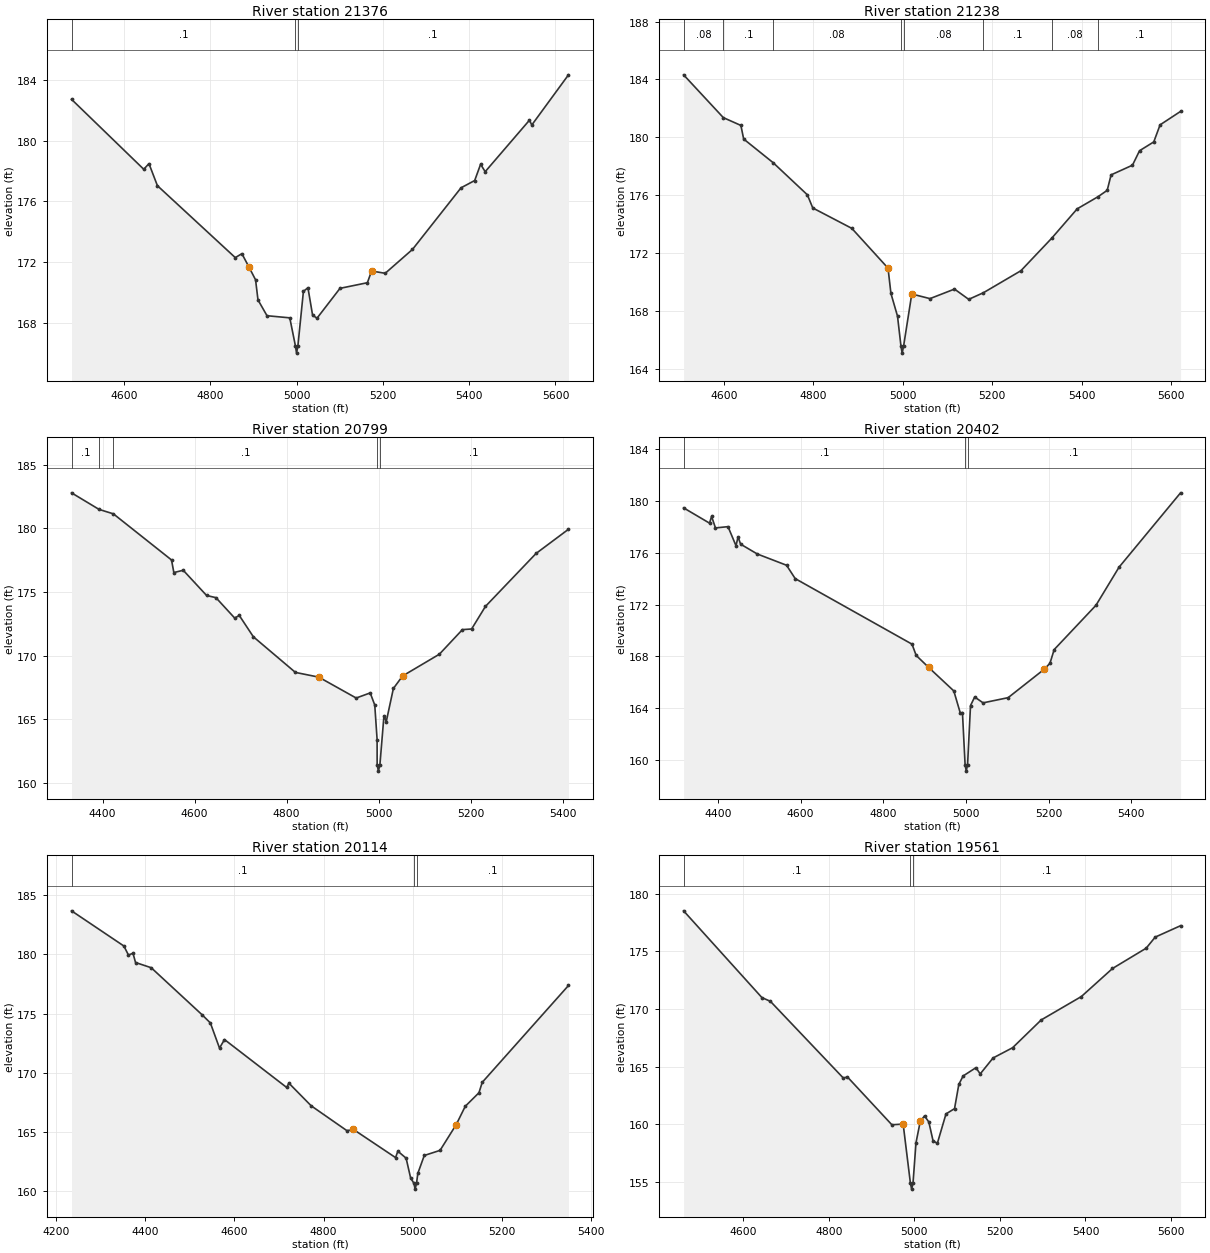
Type RM Length L Ch R = 1 ,21376   ,138,138,138
BEGIN DESCRIPTION:
CHARQUITAS CREEK 37.0
END DESCRIPTION:
XS GIS Cut Line= 2
      2306359.08     13209557.27      2306720.22     13208463.45
#Sta/Elev= 30
  4478.3  182.71  4645.7  178.11  4657.8  178.48  4677.4  177.03  4857.9   172.3
  4873.2  172.56  4889.4  171.69  4904.9  170.84  4910.5  169.52  4931.4  168.48
  4984.2  168.34  4997.1  166.52  4999.9  166.02  5003.1  166.52  5015.8  170.08
  5026.3  170.32  5037.1  168.51  5047.4  168.32  5100.6  170.28  5164.1  170.65
  5173.8  171.42  5205.4  171.27  5268.6  172.84  5381.1  176.89  5412.8  177.37
  5426.5  178.44  5437.1  177.95  5539.8  181.34  5545.1  181.02  5630.2  184.32
#Mann= 3 ,-1 , 0
  4478.3      .1       0  4997.1     .07       0  5003.1      .1       0
Bank Sta=4889.4,5173.8
XS Rating Curve= 0 ,0
Exp/Cntr=0.3,0.1

Type RM Length L Ch R = 1 ,21238   ,439,439,439
BEGIN DESCRIPTION:
CHARQUITAS CREEK 36.0
END DESCRIPTION:
XS GIS Cut Line= 2
      2306487.57     13209567.64       2306858.6     13208520.43
#Sta/Elev= 30
  4510.3  184.32  4599.1  181.36  4638.4  180.82  4644.6  179.88  4710.6  178.24
    4787  176.02  4799.1  175.11  4886.4   173.7  4967.3  170.95  4973.8   169.2
  4988.5  167.63  4996.2  165.57  4998.9  165.07  5002.2  165.57  5020.4  169.16
  5061.1  168.84  5115.9   169.5  5147.7  168.79  5180.7  169.25  5264.4  170.77
    5333  173.01  5390.2  175.05  5436.8  175.89  5457.3  176.33    5466   177.4
  5513.8  178.07  5529.6  179.07  5561.4  179.68  5575.5  180.86  5621.3  181.79
#Mann= 8 ,-1 , 0
  4510.3     .08       0  4599.1      .1       0  4710.6     .08       0
  4996.2     .07       0  5002.2     .08       0  5180.7      .1       0
    5333     .08       0  5436.8      .1       0
Bank Sta=4967.3,5020.4
XS Rating Curve= 0 ,0
Exp/Cntr=0.3,0.1

Type RM Length L Ch R = 1 ,20799   ,397,397,397
BEGIN DESCRIPTION:
CHARQUITAS CREEK 35.0
END DESCRIPTION:
XS GIS Cut Line= 3
      2306893.82      13209605.8      2307013.33     13208949.09
      2306997.98     13208536.37
#Sta/Elev= 30
  4332.5  182.79  4392.3  181.49  4423.5  181.14  4549.9  177.52    4555  176.53
  4575.4  176.71  4626.2  174.73  4646.5  174.56  4687.2  172.96  4697.3  173.16
  4727.8  171.49  4819.3  168.69  4870.1  168.32  4951.4  166.68  4981.9  167.08
  4991.8  166.13  4996.9  163.42    4997  161.44  4999.7  160.94    5003  161.44
  5011.8  165.29  5016.8  164.83  5032.3  167.43  5052.3  168.41  5132.3  170.12
  5182.4  172.05  5202.4   172.1  5232.4  173.87  5342.5  178.03    5413  179.93
#Mann= 5 ,-1 , 0
  4332.5      .1       0  4392.3     .05       0  4423.5      .1       0
    4997     .07       0    5003      .1       0
Bank Sta=4870.1,5052.3
XS Rating Curve= 0 ,0
Exp/Cntr=0.3,0.1

Type RM Length L Ch R = 1 ,20402   ,288,288,288
BEGIN DESCRIPTION:
Mapping XS 939fe742
END DESCRIPTION:
XS GIS Cut Line= 3
      2307472.12      13209643.1      2307315.88     13208601.46
      2307298.51     13208453.87
#Sta/Elev= 30
  4317.2  179.47  4379.9  178.29  4384.9  178.81  4394.3  177.92  4424.6  178.02
  4443.9  176.55    4449  177.23    4455  176.67  4495.4  175.91  4566.2  175.04
  4587.1  174.01  4869.6  168.95  4879.7  168.08    4910  167.15  4970.7  165.34
  4986.6  163.61  4991.6  163.67    4998  159.65  5000.8  159.15    5004  159.65
  5011.1  164.21  5021.2  164.87  5041.5  164.42  5102.1  164.82  5188.8     167
  5203.2  167.47  5213.4  168.53  5314.5  171.95  5370.3  174.89  5519.1  180.63
#Mann= 3 ,-1 , 0
  4317.2      .1       0    4998     .07       0    5004      .1       0
Bank Sta=4910,5188.8
XS Rating Curve= 0 ,0
Exp/Cntr=0.3,0.1

Type RM Length L Ch R = 1 ,20114   ,553,553,553
BEGIN DESCRIPTION:
CHARQUITAS CREEK 34.0
END DESCRIPTION:
XS GIS Cut Line= 2
      2307772.29     13209591.97      2307543.51     13208500.08
#Sta/Elev= 30
  4234.3  183.68  4351.9  180.71  4362.1  179.95  4372.3   180.1    4378  179.32
  4413.2  178.88  4527.7   174.9    4546  174.22  4566.5   172.1  4577.7  172.82
  4717.2  168.78  4722.3  169.14  4772.3  167.23  4852.6  165.13    4867  165.24
  4961.7  162.86  4966.9   163.4  4985.4  162.81  4995.6  161.13  5002.8   160.7
  5005.6   160.2  5008.8   160.7  5011.7  161.53  5026.2  163.04  5061.6  163.47
  5097.8  165.64  5118.2  167.19  5148.9  168.33  5156.3  169.21  5349.9  177.38
#Mann= 3 ,-1 , 0
  4234.3      .1       0  5002.8     .07       0  5008.8      .1       0
Bank Sta=4867,5097.8
XS Rating Curve= 0 ,0
Exp/Cntr=0.3,0.1

Type RM Length L Ch R = 1 ,19561   ,455,455,455
BEGIN DESCRIPTION:
CHARQUITAS CREEK 33.0
END DESCRIPTION:
XS GIS Cut Line= 3
      2308087.17     13209459.79      2308111.22      13208709.5
      2307889.98     13208363.22
#Sta/Elev= 30
  4460.7  178.51  4643.7  170.99  4663.7  170.66  4833.8  164.02  4843.8   164.1
  4947.5  159.96  4973.9  160.02  4990.9  154.88  4993.7  154.38  4996.9  154.88
  5003.9   158.4  5013.9  160.26  5023.9  160.73  5033.9   160.2  5043.9  158.55
  5053.9  158.36    5074   160.9    5094  161.36    5104  163.46    5114  164.19
    5144  164.91    5154  164.37    5184  165.75  5229.7  166.64  5296.6  169.05
  5390.5  171.08  5463.2  173.51  5541.9  175.27    5563  176.23  5622.3  177.22
#Mann= 3 ,-1 , 0
  4460.7      .1       0  4990.9     .07       0  4996.9      .1       0
Bank Sta=4973.9,5013.9
XS Rating Curve= 0 ,0
Exp/Cntr=0.3,0.1

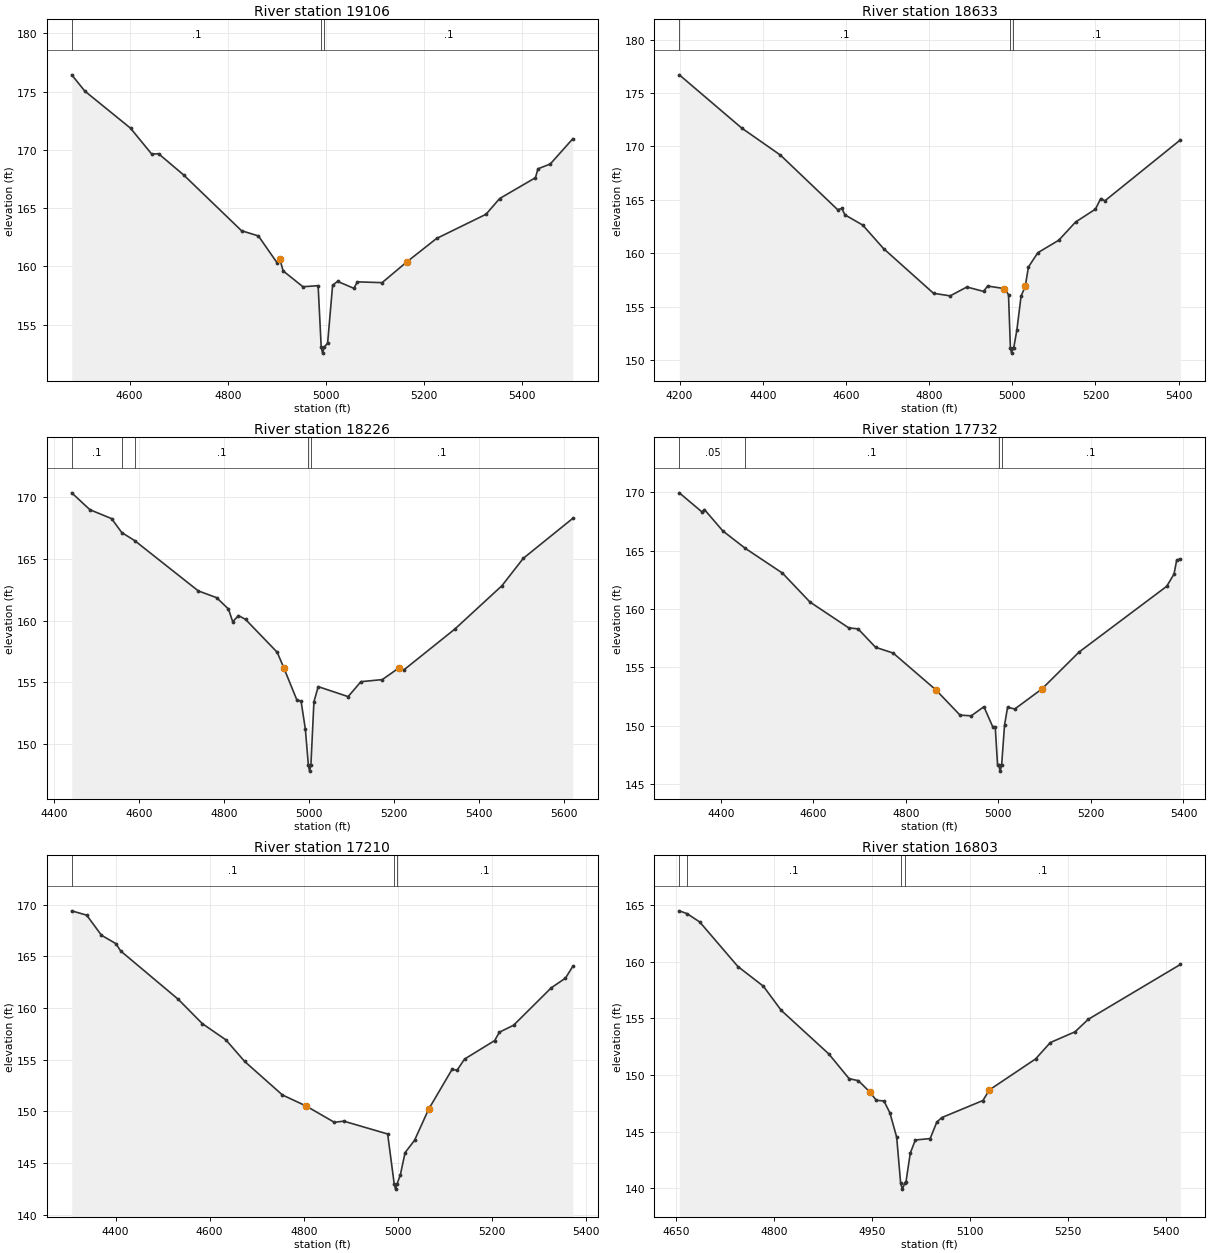
Type RM Length L Ch R = 1 ,19106   ,473,473,473
BEGIN DESCRIPTION:
CHARQUITAS CREEK 32.0
END DESCRIPTION:
XS GIS Cut Line= 3
       2308346.9     13209512.66      2308491.17     13209296.26
      2308592.13     13208541.47
#Sta/Elev= 30
    4482  176.44  4508.8  175.04  4601.9  171.86  4645.2  169.63    4659  169.67
  4710.1  167.85  4828.2  163.06  4862.6  162.61  4901.3  160.27  4906.3  160.64
    4913  159.61  4953.4  158.25  4984.4  158.34  4990.7  153.05  4993.5  152.55
  4996.7  153.05  5003.8  153.42  5013.9  158.37    5024  158.71  5057.4  158.11
  5064.3  158.67  5114.8   158.6  5165.2  160.38  5225.8  162.39  5326.7  164.47
  5354.5  165.82  5427.5  167.61  5432.6  168.37  5457.8  168.79  5503.6  170.95
#Mann= 3 ,-1 , 0
    4482      .1       0  4990.7     .07       0  4996.7      .1       0
Bank Sta=4906.3,5165.2
XS Rating Curve= 0 ,0
Exp/Cntr=0.3,0.1

Type RM Length L Ch R = 1 ,18633   ,407,407,407
BEGIN DESCRIPTION:
CHARQUITAS CREEK 31.0
END DESCRIPTION:
XS GIS Cut Line= 3
      2308887.72     13209696.86      2308937.72     13208896.85
      2308887.72     13208496.83
#Sta/Elev= 30
  4199.4   176.7  4349.7  171.71  4442.4  169.19  4580.1  164.08  4590.2  164.19
  4597.7  163.59  4640.3  162.64  4690.4  160.44  4810.6  156.25  4850.7  156.01
  4890.7  156.84  4930.8  156.43  4940.8  156.93  4980.9  156.69  4990.9  156.13
  4995.5  151.15  4998.2  150.65  5001.5  151.15  5003.5  151.15    5011  152.81
  5021.1  155.98  5031.2  156.91  5038.8  158.71  5061.4  160.05  5111.8  161.22
  5152.1  162.92    5200  164.13  5212.6  165.12  5222.7  164.91  5404.1  170.61
#Mann= 3 ,-1 , 0
  4199.4      .1       0  4995.5     .07       0  5001.5      .1       0
Bank Sta=4980.9,5031.2
XS Rating Curve= 0 ,0
Exp/Cntr=0.3,0.1

Type RM Length L Ch R = 1 ,18226   ,494,494,494
BEGIN DESCRIPTION:
CHARQUITAS CREEK 30.0
END DESCRIPTION:
XS GIS Cut Line= 3
      2309251.07      13209608.9      2309318.41     13209277.02
      2309227.12     13208441.04
#Sta/Elev= 30
  4441.8  170.35  4484.7  168.98  4535.7  168.26  4559.6  167.13  4589.9  166.48
  4739.8   162.4    4783  161.85  4810.8  160.93  4820.8   159.9  4834.4   160.4
    4851  160.09  4925.7  157.42  4941.6  156.12  4971.7  153.57  4981.8  153.45
  4991.9  151.18  4998.9  148.29  5001.7  147.79  5004.9  148.29    5012  153.41
  5022.1  154.64  5092.5  153.83  5122.6  155.04  5172.9  155.21  5213.2  156.18
  5223.2  155.98  5343.9  159.31  5454.6  162.82  5504.9  165.04  5621.4  168.28
#Mann= 5 ,-1 , 0
  4441.8      .1       0  4559.6     .05       0  4589.9      .1       0
  4998.9     .07       0  5004.9      .1       0
Bank Sta=4941.6,5213.2
XS Rating Curve= 0 ,0
Exp/Cntr=0.3,0.1

Type RM Length L Ch R = 1 ,17732   ,522,522,522
BEGIN DESCRIPTION:
CHARQUITAS CREEK 29.0
END DESCRIPTION:
XS GIS Cut Line= 3
      2309937.73     13209496.88      2309737.72     13208846.85
      2309537.73     13208496.87
#Sta/Elev= 30
  4310.1  169.96  4359.2  168.32  4364.4  168.53  4404.3  166.69  4453.2  165.19
  4533.1  163.08  4592.6   160.6  4676.3  158.39  4696.6   158.3  4734.5  156.72
  4772.4  156.23  4864.6  153.08    4917  150.91  4941.2  150.85  4968.6  151.63
  4987.6  149.92  4993.1  149.92  4998.1  146.63  5000.9  146.61  5003.6  146.11
  5006.9  146.61  5013.2  150.05  5019.7  151.57  5035.5  151.44  5093.9  153.15
  5174.5  156.32  5363.8  161.95  5379.6     163  5385.4   164.2  5393.3   164.3
#Mann= 4 ,-1 , 0
  4310.1     .05       0  4453.2      .1       0  5000.9     .07       0
  5006.9      .1       0
Bank Sta=4864.6,5093.9
XS Rating Curve= 0 ,0
Exp/Cntr=0.3,0.1

Type RM Length L Ch R = 1 ,17210   ,407,407,407
BEGIN DESCRIPTION:
CHARQUITAS CREEK 28.0
END DESCRIPTION:
XS GIS Cut Line= 3
      2310289.93     13209358.77      2310237.03     13209099.07
      2310188.96     13208301.25
#Sta/Elev= 30
    4307  169.39  4338.8  168.97  4370.2  167.03  4400.8  166.22    4411  165.51
  4533.5  160.83  4584.3  158.49  4634.4  156.92  4674.4  154.83  4754.6  151.59
  4804.7  150.53  4864.8  148.95  4884.8  149.06  4978.1  147.82    4992  142.99
  4994.8  142.49    4998  142.99    5005  143.86  5015.1  146.02  5035.1   147.2
  5065.1  150.21  5115.2  154.09  5125.3  153.97  5141.4  155.06  5205.4  156.85
  5215.4  157.66  5245.5  158.33  5325.6  161.95  5355.7  162.88  5371.3  164.02
#Mann= 3 ,-1 , 0
    4307      .1       0    4992     .07       0    4998      .1       0
Bank Sta=4804.7,5065.1
XS Rating Curve= 0 ,0
Exp/Cntr=0.3,0.1

Type RM Length L Ch R = 1 ,16803   ,312,312,312
BEGIN DESCRIPTION:
CHARQUITAS CREEK 27.0
END DESCRIPTION:
XS GIS Cut Line= 3
      2310637.71     13209146.82      2310537.72     13208796.85
      2310487.72     13208396.84
#Sta/Elev= 30
  4654.9  164.51  4666.8  164.26  4686.1  163.53  4744.6  159.59  4783.6  157.85
  4810.9  155.72  4883.7  151.87  4914.9  149.68  4929.2   149.5  4946.1  148.53
  4956.5  147.77  4968.2  147.71  4977.3  146.66  4987.7  144.51  4993.8  140.42
  4996.5  139.92  4999.8  140.42    5002  140.59  5008.5   143.1  5016.3  144.26
    5039  144.39  5049.1  145.84  5056.7  146.24  5119.7  147.75  5129.7  148.69
  5200.3  151.42  5222.9  152.87  5260.7  153.82  5280.9  154.92    5422  159.77
#Mann= 4 ,-1 , 0
  4654.9     .05       0  4666.8      .1       0  4993.8     .07       0
  4999.8      .1       0
Bank Sta=4946.1,5129.7
XS Rating Curve= 0 ,0
Exp/Cntr=0.3,0.1

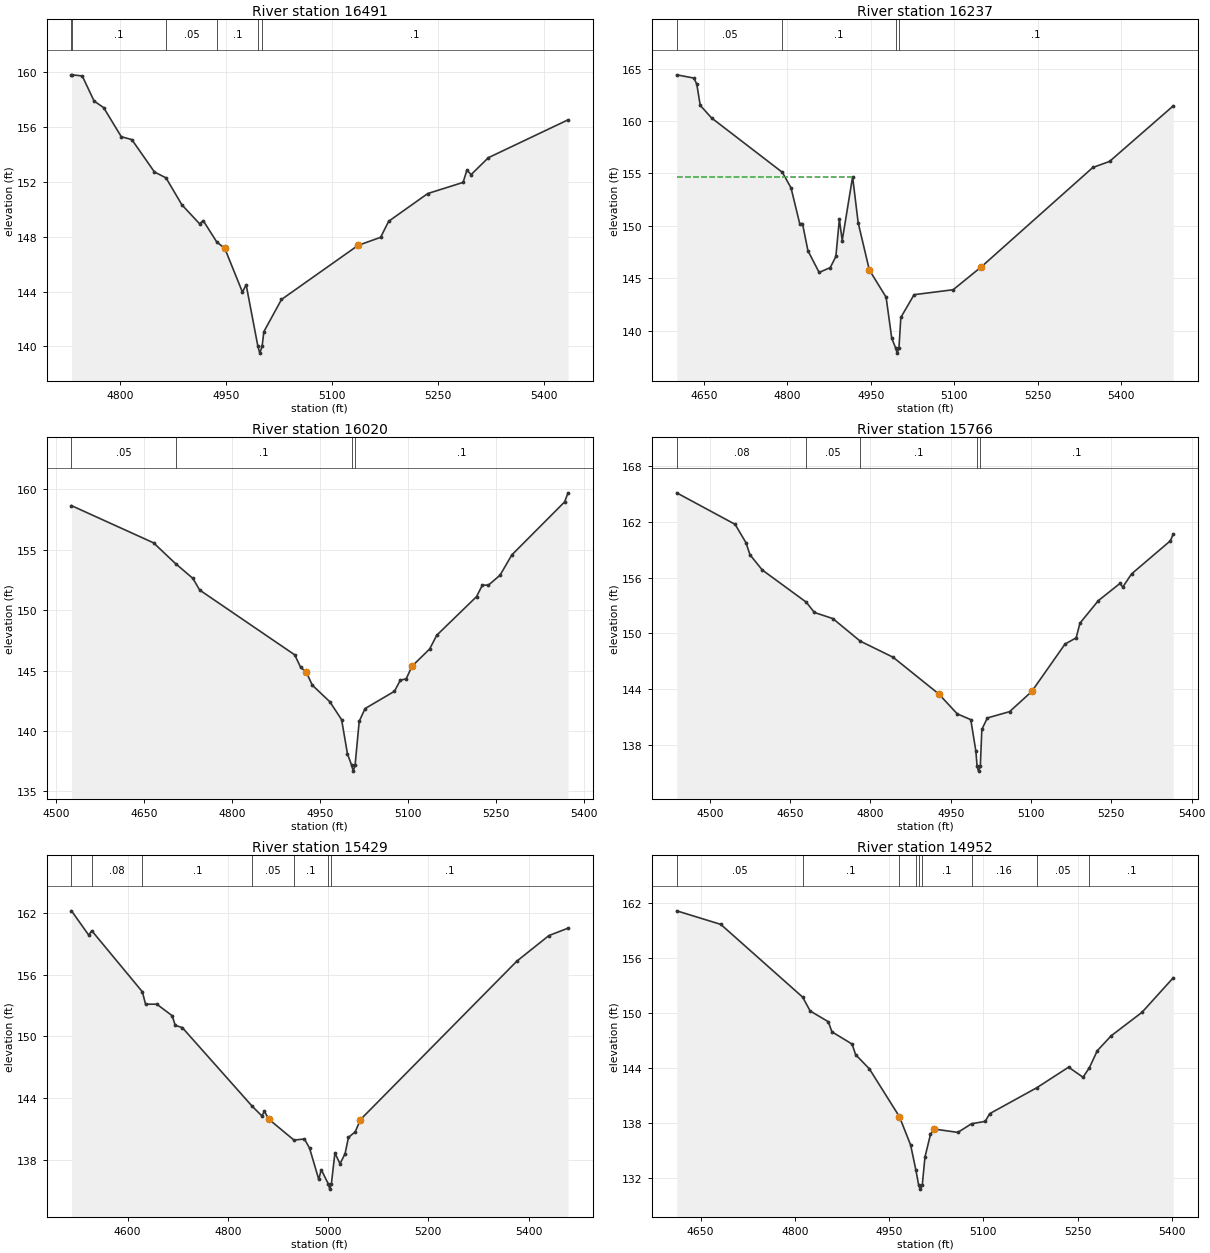
Type RM Length L Ch R = 1 ,16491   ,254,254,254
BEGIN DESCRIPTION:
CHARQUITAS CREEK 26.0
END DESCRIPTION:
XS GIS Cut Line= 2
      2310937.73     13209046.88      2310692.57     13208388.33
#Sta/Elev= 30
  4730.9  159.79  4731.3  159.79  4746.1  159.71  4762.9  157.88  4776.4   157.4
  4801.4  155.28  4816.3  155.07  4848.3  152.71  4864.7  152.28  4887.1  150.32
  4912.1  148.94  4917.4  149.16  4936.6   147.6  4947.8  147.15  4972.8  143.96
  4978.1  144.49  4994.7  140.01  4997.4  139.51  5000.7  140.01  5003.1  141.07
  5028.1  143.42  5136.4  147.36  5168.4  147.95  5179.8  149.12  5235.1  151.14
  5285.1  151.95  5290.5  152.84  5296.5  152.52  5320.8  153.75  5433.6  156.51
#Mann= 6 ,-1 , 0
  4730.9     .05       0  4731.3      .1       0  4864.7     .05       0
  4936.6      .1       0  4994.7     .07       0  5000.7      .1       0
Bank Sta=4947.8,5136.4
XS Rating Curve= 0 ,0
Exp/Cntr=0.3,0.1

Type RM Length L Ch R = 1 ,16237   ,217,217,217
BEGIN DESCRIPTION:
Mapping XS 810ad0f4
END DESCRIPTION:
XS GIS Cut Line= 3
      2311065.87     13209148.37      2311109.28     13208931.32
      2311048.52     13208262.92
#Sta/Elev= 30
  4601.4   164.4  4632.4  164.09  4637.5  163.51  4643.7  161.49  4664.1  160.29
  4791.3  155.11  4806.9  153.63  4822.5  150.22  4827.5  150.22  4837.3  147.64
  4857.4  145.57  4877.4  146.03  4887.5  147.09  4893.8  150.64  4898.9  148.61
  4917.6  154.68  4927.6   150.3  4947.7   145.8  4977.8  143.21  4987.9  139.31
  4994.9  138.38  4997.7  137.88  5000.9  138.38  5004.3  141.28  5028.1  143.45
  5098.3  143.92  5148.5  146.08  5349.4  155.57  5379.5  156.15  5493.9  161.44
#Mann= 4 ,-1 , 0
  4601.4     .05       0  4791.3      .1       0  4994.9     .07       0
  5000.9      .1       0
#XS Ineff= 2 , 0
       0 4916.67  154.68               0
Permanent Ineff=
       T       F
Bank Sta=4947.7,5148.5
XS Rating Curve= 0 ,0
Exp/Cntr=0.3,0.1

Type RM Length L Ch R = 1 ,16020   ,254,254,254
BEGIN DESCRIPTION:
CHARQUITAS CREEK 25.0
END DESCRIPTION:
XS GIS Cut Line= 3
      2311198.91     13209132.77      2311304.74     13208916.31
      2311285.53     13208311.06
#Sta/Elev= 30
  4526.4  158.65  4666.3  155.57  4703.8  153.85  4733.3  152.63    4745  151.66
  4906.9   146.3  4916.9  145.28  4926.9  144.84  4936.9  143.79  4966.9  142.41
  4986.9  140.93  4996.9   138.1  5003.9  137.17  5006.7  136.67  5009.9  137.17
  5016.9  140.79  5026.9  141.85    5077  143.28    5087   144.2    5097  144.31
    5107  145.36    5137  146.78  5149.1  147.92    5217  151.12    5227  152.08
    5237  152.06    5257  152.89  5277.1  154.57  5367.1  158.96  5372.9  159.71
#Mann= 4 ,-1 , 0
  4526.4     .05       0  4703.8      .1       0  5003.9     .07       0
  5009.9      .1       0
Bank Sta=4926.9,5107
XS Rating Curve= 0 ,0
Exp/Cntr=0.3,0.1

Type RM Length L Ch R = 1 ,15766   ,337,337,337
BEGIN DESCRIPTION:
Mapping XS 2c5dda23
END DESCRIPTION:
XS GIS Cut Line= 3
      2311656.15     13209174.37      2311595.39     13208818.47
      2311447.87     13208271.77
#Sta/Elev= 30
  4438.3  165.13  4547.4  161.74  4567.7  159.76  4575.1  158.47  4598.1  156.83
  4680.2  153.37  4695.4  152.26    4730   151.6  4780.9  149.18  4842.5  147.44
  4927.6   143.5  4962.3  141.35  4987.5  140.73  4997.1  137.32  4999.3  135.69
    5002  135.19  5005.3  135.69  5008.2  139.68  5018.5  140.91    5060  141.59
  5101.4  143.76  5163.5  148.86  5184.3  149.53  5191.4  151.11  5225.7  153.53
  5266.1  155.38  5271.3  154.99  5287.8  156.41  5360.3  159.97  5365.6  160.69
#Mann= 5 ,-1 , 0
  4438.3     .08       0  4680.2     .05       0  4780.9      .1       0
  4999.3     .07       0  5005.3      .1       0
Bank Sta=4927.6,5101.4
XS Rating Curve= 0 ,0
Exp/Cntr=0.3,0.1

Type RM Length L Ch R = 1 ,15429   ,477,477,477
BEGIN DESCRIPTION:
CHARQUITAS CREEK 24.0
END DESCRIPTION:
XS GIS Cut Line= 3
      2311958.83     13209084.62       2311838.6     13208401.69
      2311607.73     13208214.11
#Sta/Elev= 30
  4487.9  162.25  4522.2  159.89  4528.4  160.31  4629.3  154.36  4635.7  153.15
  4658.2  153.15  4688.7  152.03    4695  151.08    4709  150.87  4848.5   143.2
  4867.8  142.26  4872.9  142.71  4881.6  141.94  4931.9   139.9  4952.7  140.01
  4962.9  139.13  4981.3  136.08  4986.4  137.01  5000.5  135.62  5003.2  135.12
  5006.5  135.62  5013.6  138.64  5023.8  137.59  5033.9  138.58  5040.6  140.16
  5054.2  140.71  5064.4  141.89  5376.8  157.35  5440.7  159.84  5478.8  160.56
#Mann= 7 ,-1 , 0
  4487.9      .1       0  4528.4     .08       0  4629.3      .1       0
  4848.5     .05       0  4931.9      .1       0  5000.5     .07       0
  5006.5      .1       0
Bank Sta=4881.6,5064.4
XS Rating Curve= 0 ,0
Exp/Cntr=0.3,0.1

Type RM Length L Ch R = 1 ,14952   ,346,346,346
BEGIN DESCRIPTION:
CHARQUITAS CREEK 23.0
END DESCRIPTION:
XS GIS Cut Line= 3
      2312579.25     13208824.92      2312410.93     13208675.83
      2312137.19     13208181.18
#Sta/Elev= 30
  4612.1  161.16  4682.3  159.68  4812.6  151.74  4824.5  150.23  4853.4  149.06
  4859.1  147.96  4891.2  146.62  4896.9  145.46  4918.7  143.92  4966.6  138.69
  4984.4   135.6  4992.8  132.86    4997  131.29  4999.7  130.79    5003  131.29
  5007.2  134.29    5016  136.77  5021.7  137.35  5059.5  136.98  5081.4  137.93
  5103.1  138.18  5110.1  139.02  5185.3  141.86  5235.8   144.1  5258.7     143
  5268.8  144.03  5281.5   145.9  5303.5  147.52  5352.7  150.09  5402.3  153.85
#Mann= 9 ,-1 , 0
  4612.1     .05       0  4812.6      .1       0  4966.6     .16       0
  4992.8      .1       0    4997     .07       0    5003      .1       0
  5081.4     .16       0  5185.3     .05       0  5268.8      .1       0
Bank Sta=4966.6,5021.7
XS Rating Curve= 0 ,0
Exp/Cntr=0.3,0.1