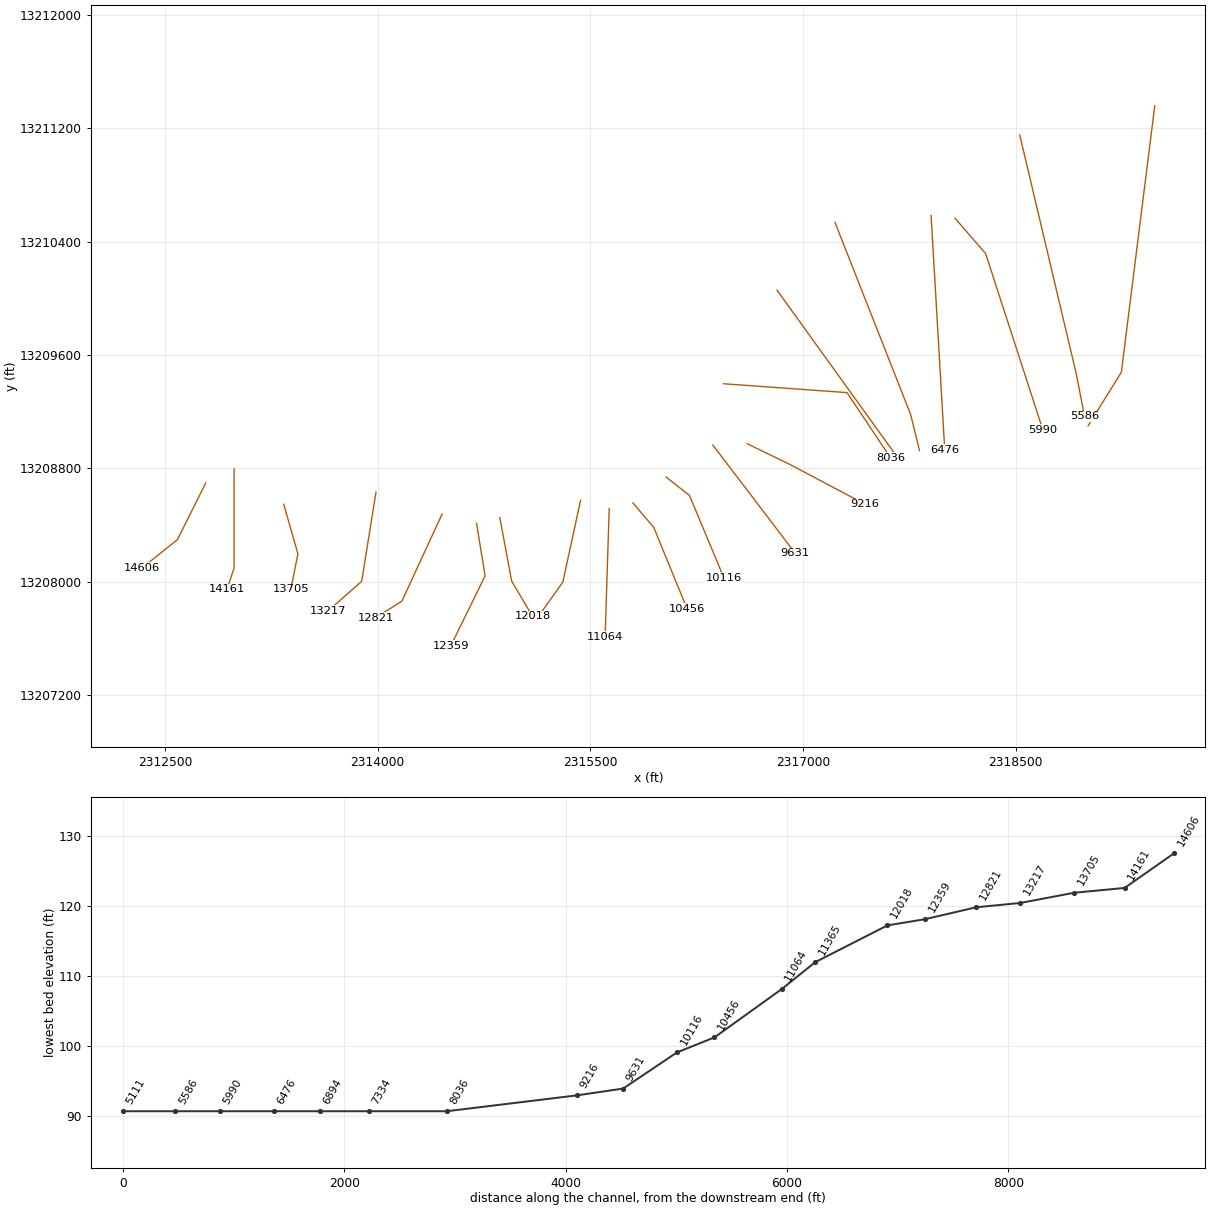
HEC-RAS study CHARQUITAS CREEK.prj: CHARQUITAS CREEK Base Level Engineering

--- CHARQUITAS CREEK.g01 (geometry) --- (continued)

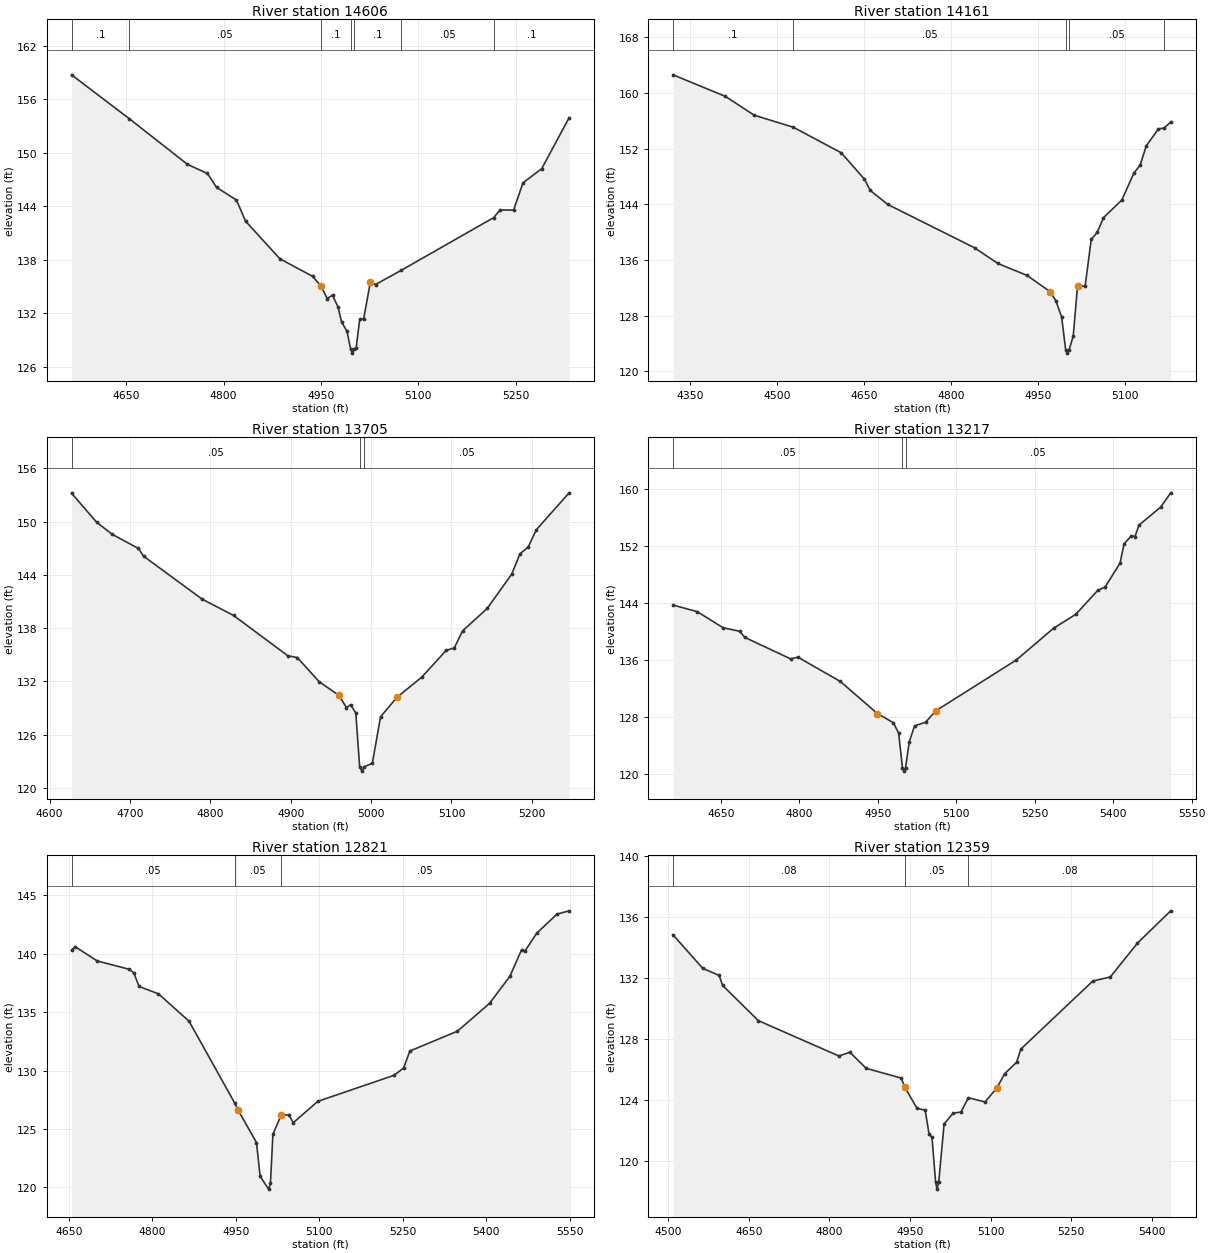
Type RM Length L Ch R = 1 ,14606   ,445,445,445
BEGIN DESCRIPTION:
CHARQUITAS CREEK 22.0
END DESCRIPTION:
XS GIS Cut Line= 3
       2312787.7     13208696.81      2312587.72     13208296.85
      2312337.74     13208096.87
#Sta/Elev= 30
  4565.4  158.76  4654.4  153.84  4744.2  148.71    4775  147.69    4789  146.13
  4819.7  144.71  4833.7  142.34  4886.8  138.11  4937.1  136.15  4950.5  135.01
  4959.5  133.66  4967.8  134.03  4976.2  132.72  4981.8  131.03  4990.2  129.96
  4995.6  128.03  4998.3  127.53  5001.6  128.03  5004.2  128.07  5009.8  131.35
  5015.8  131.35  5026.2  135.51  5034.2  135.23  5073.7  136.82  5216.4  142.74
  5226.3   143.6  5247.1  143.58  5261.5  146.64  5290.3  148.22  5332.7  153.95
#Mann= 7 ,-1 , 0
  4565.4      .1       0  4654.4     .05       0  4950.5      .1       0
  4995.6     .07       0  5001.6      .1       0  5073.7     .05       0
  5216.4      .1       0
Bank Sta=4950.5,5026.2
XS Rating Curve= 0 ,0
Exp/Cntr=0.3,0.1

Type RM Length L Ch R = 1 ,14161   ,456,456,456
BEGIN DESCRIPTION:
CHARQUITAS CREEK 21.0
END DESCRIPTION:
XS GIS Cut Line= 3
      2312987.72     13208796.86      2312987.72     13208096.85
      2312937.73     13207946.88
#Sta/Elev= 30
    4320  162.61    4410  159.52    4460   156.8  4527.5  155.07    4610   151.4
    4650  147.61    4660     146    4690  143.98    4840  137.74    4880  135.49
    4930  133.79    4970  131.45    4980  130.15    4990  127.81    4997   123.1
  4999.8   122.6    5003   123.1    5010  125.02  5017.5  132.29  5030.5  132.19
  5041.1  138.94  5051.6  139.99  5062.2  142.07  5093.8  144.61  5114.9  148.52
  5125.4  149.61    5136  152.39    5157  154.85  5166.5  154.95  5178.1  155.81
#Mann= 5 ,-1 , 0
    4320      .1       0  4527.5     .05       0    4997    .035       0
    5003     .05       0  5166.5     .08       0
Bank Sta=4970,5017.5
XS Rating Curve= 0 ,0
Exp/Cntr=0.3,0.1

Type RM Length L Ch R = 1 ,13705   ,488,488,488
BEGIN DESCRIPTION:
CHARQUITAS CREEK 20.0
END DESCRIPTION:
XS GIS Cut Line= 3
      2313337.72     13208546.87      2313437.72     13208196.85
      2313387.71     13207946.82
#Sta/Elev= 30
  4627.4   153.2  4658.6  149.93  4678.1  148.56  4710.6  146.98  4717.1   146.1
  4789.9  141.27  4828.9  139.44  4896.5  134.89  4908.2   134.7  4935.5  131.97
  4960.2  130.43  4969.3  129.06  4974.5  129.39    4981  128.46  4985.8  122.41
  4988.6  121.91  4991.8  122.41  5001.6  122.79  5011.8  128.03  5032.2  130.22
  5062.8  132.47  5093.4   135.5  5103.6  135.79  5113.8  137.69  5144.4  140.22
    5175  144.09  5185.2  146.37  5195.4  147.13  5205.6  149.09  5246.4  153.24
#Mann= 3 ,-1 , 0
  4627.4     .05       0  4985.8    .035       0  4991.8     .05       0
Bank Sta=4960.2,5032.2
XS Rating Curve= 0 ,0
Exp/Cntr=0.3,0.1

Type RM Length L Ch R = 1 ,13217   ,396,396,396
BEGIN DESCRIPTION:
CHARQUITAS CREEK 19.0
END DESCRIPTION:
XS GIS Cut Line= 3
      2313988.46     13208632.56      2313887.45      13208002.5
      2313652.28     13207796.12
#Sta/Elev= 30
  4558.9   143.7  4605.2  142.77  4654.5  140.52  4686.2  140.03  4696.3  139.16
  4783.5  136.17  4797.6   136.4  4878.6     133  4949.5   128.5  4979.9  127.23
    4990  125.77  4997.2  120.95  4999.9  120.45  5003.2  120.95  5010.3  124.56
  5020.4  126.78  5041.6   127.3  5060.9  128.89  5214.9  136.01    5286  140.45
  5328.7  142.41  5370.5  145.75  5384.7  146.23  5413.2  149.59  5420.8  152.27
    5435  153.41  5441.7  153.29  5449.3  154.89    5491  157.43  5509.9  159.41
#Mann= 3 ,-1 , 0
  4558.9     .05       0  4997.2    .035       0  5003.2     .05       0
Bank Sta=4949.5,5060.9
XS Rating Curve= 0 ,0
Exp/Cntr=0.3,0.1

Type RM Length L Ch R = 1 ,12821   ,462,462,462
BEGIN DESCRIPTION:
CHARQUITAS CREEK 18.0
END DESCRIPTION:
XS GIS Cut Line= 3
        2314455.     13208478.68      2314171.22     13207863.02
      2313988.43     13207747.58
#Sta/Elev= 30
  4654.7  140.31  4661.2  140.61  4700.7  139.39  4758.5  138.67  4766.8  138.36
  4775.9   137.2  4810.9  136.57  4865.9  134.22  4947.6  127.24    4954  126.61
    4987  123.83  4993.6  120.93  5008.8  119.84  5012.1  120.34  5016.5  124.53
  5031.1  126.15    5045  126.22  5053.1  125.53  5097.2  127.36  5234.1  129.59
  5251.3  130.21  5262.6  131.67  5348.1  133.37  5405.7  135.75  5442.2  138.06
  5463.4  140.35  5469.3  140.23  5490.5  141.76    5527   143.4  5548.8  143.68
#Mann= 3 ,-1 , 0
  4654.7     .05       0  4947.6     .05       0  5031.1     .05       0
Bank Sta=4954,5031.1
XS Rating Curve= 0 ,0
Exp/Cntr=0.3,0.1

Type RM Length L Ch R = 1 ,12359   ,341,341,341
BEGIN DESCRIPTION:
CHARQUITAS CREEK 17.0
END DESCRIPTION:
XS GIS Cut Line= 3
      2314697.63     13208411.42      2314758.05     13208041.33
      2314515.32     13207546.77
#Sta/Elev= 30
  4509.1  134.83  4564.4  132.63  4594.8  132.17  4601.3  131.51  4667.8   129.2
  4817.7  126.88    4838  127.13  4868.4  126.07  4933.6  125.43  4940.4  124.82
  4962.9  123.45  4978.2  123.32  4985.4  121.76  4990.9  121.54  4997.5  118.64
  5000.2  118.14  5003.5  118.64  5013.4  122.42  5030.3  123.13    5045   123.2
  5058.4  124.14  5089.6  123.86  5111.9   124.8  5125.9  125.71  5148.3  126.47
  5156.4  127.34  5290.1   131.8  5322.7  132.07  5373.2  134.29    5435  136.41
#Mann= 3 ,-1 , 0
  4509.1     .08       0  4940.4     .05       0  5058.4     .08       0
Bank Sta=4940.4,5111.9
XS Rating Curve= 0 ,0
Exp/Cntr=0.3,0.1

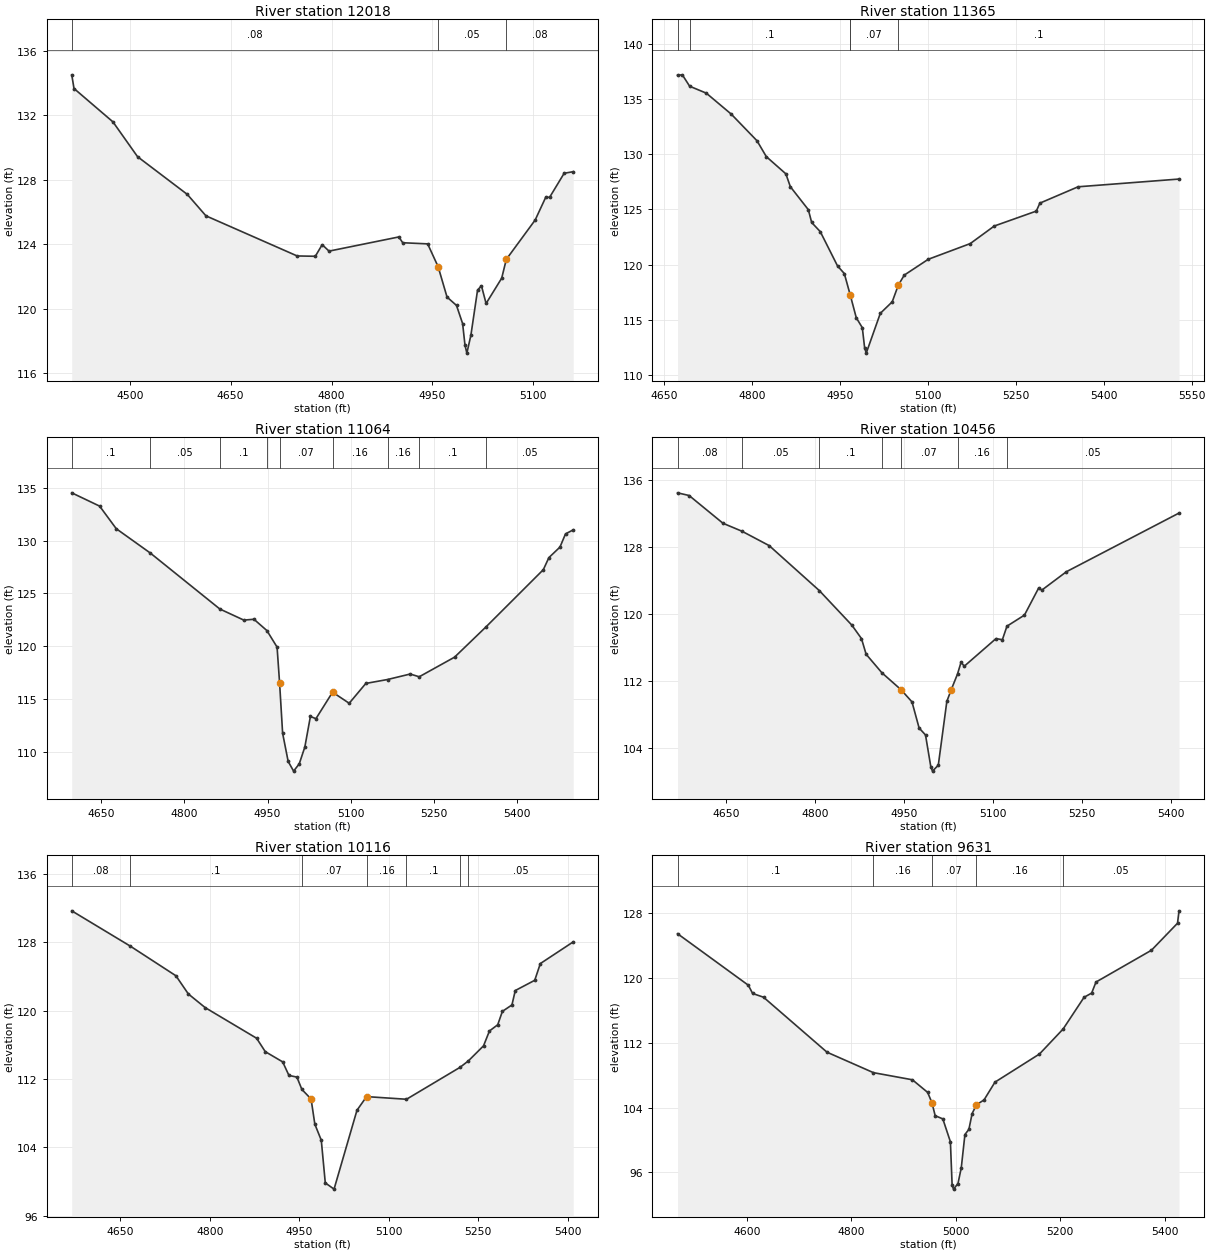
Type RM Length L Ch R = 1 ,12018   ,653,653,653
BEGIN DESCRIPTION:
CHARQUITAS CREEK 16.0
END DESCRIPTION:
XS GIS Cut Line= 3
       2314861.7     13208453.07      2314945.03     13208005.15
      2315092.75     13207755.26
#Sta/Elev= 30
  4413.6  134.52    4417  133.67  4474.9   131.6  4511.5  129.44  4585.5   127.1
  4613.2  125.77  4748.9  123.28  4775.9  123.26  4786.1  123.98  4796.3  123.58
  4900.1  124.46  4905.9   124.1    4943  124.03  4958.6  122.61  4971.8  120.73
  4985.9  120.21    4995  119.08  4998.5  117.75  5001.3  117.25  5007.3  118.36
  5017.2  121.16    5023  121.43  5029.9  120.33  5053.1   121.9    5060  123.07
  5102.9  125.51  5118.6  126.92  5124.4  126.92    5146  128.41  5159.5  128.51
#Mann= 3 , 0 , 0
  4413.6     .08       0  4958.6     .05       0    5060     .08       0
Bank Sta=4958.6,5060
XS Rating Curve= 0 ,0
Exp/Cntr=0.3,0.1

Type RM Length L Ch R = 1 ,11365   ,301,301,301
BEGIN DESCRIPTION:
CHARQUITAS CREEK 15.0
END DESCRIPTION:
XS GIS Cut Line= 3
      2315431.32     13208574.87      2315306.26     13207997.69
      2315152.73     13207781.78
#Sta/Elev= 30
    4673  137.13  4681.2  137.17  4693.6  136.14  4722.1  135.51  4764.5  133.62
  4808.6   131.2  4824.4  129.77  4857.8  128.21  4865.4  127.05  4896.1  124.97
  4901.8  123.81  4916.5  122.98  4945.9  119.88  4957.5  119.19  4967.7  117.23
  4977.9  115.19  4988.2  114.29  4992.1  112.49  4994.9  111.99  5018.9  115.59
  5039.2  116.63  5049.6  118.14  5059.8  119.05  5100.7  120.48  5172.3   121.9
  5213.3  123.49    5285  124.84  5291.1  125.56  5356.3  127.04  5528.5  127.74
#Mann= 5 ,-1 , 0
    4673     .08       0  4693.6      .1       0  4967.7     .05       0
  4967.7     .07       0  5049.6      .1       0
Bank Sta=4967.7,5049.6
XS Rating Curve= 0 ,0
Exp/Cntr=0.3,0.1

Type RM Length L Ch R = 1 ,11064   ,608,608,608
BEGIN DESCRIPTION:
CHARQUITAS CREEK 14.0
END DESCRIPTION:
XS GIS Cut Line= 2
      2315633.31     13208517.09      2315604.46     13207612.95
#Sta/Elev= 30
  4596.7  134.53    4647  133.27    4677  131.13  4738.3  128.83  4863.9  123.52
  4907.1  122.47  4925.4  122.55  4948.7  121.48  4967.1  119.91 4971.67  116.49
  4977.1  111.75  4987.1  109.08  4996.9  108.16  5007.1  108.85  5017.2  110.45
  5027.2  113.34  5037.2  113.13  5067.2  115.64  5097.2  114.59  5127.2  116.47
  5166.3  116.84  5207.2  117.36  5223.5   117.1  5287.3  118.96  5344.6  121.86
  5447.4  127.25  5457.4  128.39  5477.4  129.39  5487.4  130.64  5501.3  131.02
#Mann= 9 ,-1 , 0
  4596.7      .1       0  4738.3     .05       0  4863.9      .1       0
  4948.7     .16       0 4971.67     .07       0  5067.2     .16       0
  5166.3     .16       0  5223.5      .1       0  5344.6     .05       0
Bank Sta=4971.67,5067.2
XS Rating Curve= 0 ,0
Exp/Cntr=0.3,0.1

Type RM Length L Ch R = 1 ,10456   ,340,340,340
BEGIN DESCRIPTION:
CHARQUITAS CREEK 13.0
END DESCRIPTION:
XS GIS Cut Line= 3
       2315800.1     13208556.76      2315947.64     13208383.18
      2316181.71     13207811.02
#Sta/Elev= 30
  4567.7  134.42  4587.2   134.1  4644.4  130.79  4676.5  129.84  4722.3  128.13
  4806.9  122.77  4861.8  118.65    4878  117.05  4885.8  115.19  4912.4  112.98
  4944.6  110.97  4963.2  109.51  4975.2   106.4    4986  105.57    4995  101.76
  4997.8  101.26  5007.6  101.97    5022  109.57  5029.2  110.93    5040  112.83
    5046  114.24  5051.4  113.76  5104.9  117.05  5115.7  116.92  5123.4  118.53
  5152.9  119.85  5176.9  123.08  5182.3  122.83  5223.7  125.02  5413.7  132.01
#Mann= 7 ,-1 , 0
  4567.7     .08       0  4676.5     .05       0  4806.9      .1       0
  4912.4     .16       0  4944.6     .07       0    5040     .16       0
  5123.4     .05       0
Bank Sta=4944.6,5029.2
XS Rating Curve= 0 ,0
Exp/Cntr=0.3,0.1

Type RM Length L Ch R = 1 ,10116   ,485,485,485
BEGIN DESCRIPTION:
CHARQUITAS CREEK 12.0
END DESCRIPTION:
XS GIS Cut Line= 3
      2316034.49     13208739.06      2316199.38     13208608.88
      2316442.42     13208027.31
#Sta/Elev= 30
  4568.8  131.71    4667  127.57  4743.4   124.1  4764.2  121.97  4792.4  120.37
  4878.6  116.78  4893.1  115.21  4922.3  114.01  4932.8  112.42  4946.1  112.23
  4954.5  110.78  4969.9  109.66  4976.2  106.71    4987  104.83  4993.7   99.83
  5008.4    99.1  5046.8  108.34  5062.9  109.94  5129.8  109.63  5219.5  113.37
  5233.4  114.12  5258.9  115.89  5268.8  117.63  5282.7  118.36  5290.5  119.93
  5306.5  120.68  5312.1  122.37  5344.7  123.57  5354.1  125.53  5409.2  128.07
#Mann= 7 ,-1 , 0
  4568.8     .08       0    4667      .1       0  4954.5     .07       0
  5062.9     .16       0  5129.8      .1       0  5219.5     .16       0
  5233.4     .05       0
Bank Sta=4969.9,5062.9
XS Rating Curve= 0 ,0
Exp/Cntr=0.3,0.1

Type RM Length L Ch R = 1 ,9631    ,415,415,415
BEGIN DESCRIPTION:
CHARQUITAS CREEK 11.0
END DESCRIPTION:
XS GIS Cut Line= 2
      2316364.34     13208964.43      2316945.46      13208200.8
#Sta/Elev= 30
  4467.7  125.44  4603.1  119.09  4611.4  118.07  4632.2  117.61  4753.7  110.83
  4842.5  108.31  4917.1  107.43  4946.2  105.88  4954.4  104.62  4960.7     103
  4975.3  102.61  4989.8   99.79  4993.1   94.45  4995.8   93.95  5004.3   94.64
  5010.6   96.57  5017.6  100.68  5025.2  101.32  5031.4  103.27  5039.7  104.35
  5054.2  104.95  5075.1  107.14  5160.3  110.61  5205.5  113.69  5245.6   117.6
  5260.1  118.12  5268.4  119.48  5374.5   123.4  5424.4  126.73  5427.3  128.26
#Mann= 5 ,-1 , 0
  4467.7      .1       0  4842.5     .16       0  4954.4     .07       0
  5039.7     .16       0  5205.5     .05       0
Bank Sta=4954.4,5039.7
XS Rating Curve= 0 ,0
Exp/Cntr=0.3,0.1

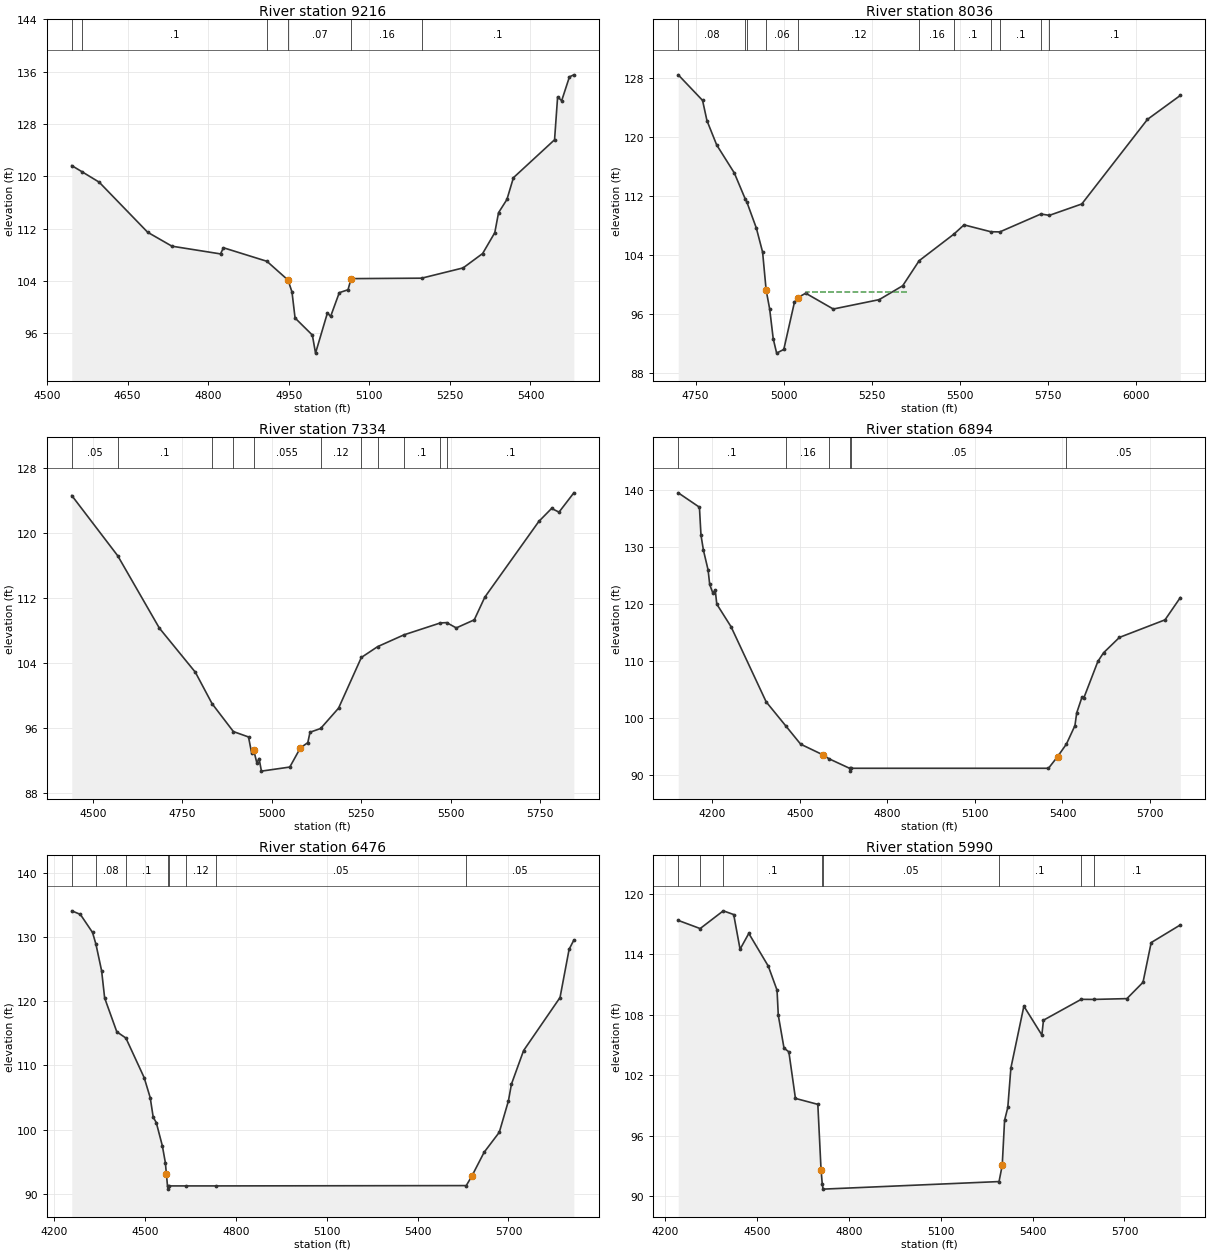
Type RM Length L Ch R = 1 ,9216    ,1180,1180,1180
BEGIN DESCRIPTION:
CHARQUITAS CREEK 10.0
END DESCRIPTION:
XS GIS Cut Line= 3
       2316606.5      13208973.9       2316902.7     13208830.61
      2317437.76     13208546.83
#Sta/Elev= 30
  4546.1  121.65  4565.2  120.71  4597.1  119.12  4687.4  111.46  4732.6  109.33
    4823  108.15  4828.5  109.09  4909.4  107.02  4948.7  104.15  4956.1  102.32
  4961.8   98.35    4994   95.74  4999.9   92.98  5022.1   99.14    5028   98.59
  5044.1  102.22  5060.4  102.67  5066.1  104.37  5197.5  104.44  5274.7  106.01
    5311  108.21  5333.6  111.39  5340.6  114.45  5356.2  116.47  5368.3   119.8
  5444.9   125.6  5450.6  132.17  5458.1  131.57  5472.6  135.22  5480.8  135.53
#Mann= 6 ,-1 , 0
  4546.1     .05       0  4565.2      .1       0  4909.4     .16       0
  4948.7     .07       0  5066.1     .16       0  5197.5      .1       0
Bank Sta=4948.7,5066.1
XS Rating Curve= 0 ,0
Exp/Cntr=0.3,0.1

Type RM Length L Ch R = 1 ,8036    ,702,702,702
BEGIN DESCRIPTION:
CHARQUITAS CREEK 9.0
END DESCRIPTION:
XS GIS Cut Line= 3
      2316438.94     13209397.51      2317310.48     13209335.01
      2317616.02      13208876.7
#Sta/Elev= 30
  4700.5  128.38  4769.5  124.92    4782  122.18  4809.6  118.89  4859.7  115.09
  4891.1  111.52  4894.9   111.2  4922.1  107.64  4939.9  104.38  4949.9   99.25
  4959.9   96.69    4970   92.66  4979.7   90.71    5000   91.21  5030.1   97.57
  5040.1   98.23  5062.2   98.82  5140.4   96.68  5270.7   97.95  5337.4   99.83
  5384.1  103.22  5482.7  106.82  5511.4  108.07  5587.5  107.14    5613  107.12
  5729.5  109.54  5753.6  109.36  5845.6   110.9  6031.9  122.35  6125.1  125.59
#Mann= 11 ,-1 , 0
  4700.5     .08       0  4891.1      .1       0  4894.9     .12       0
  4949.9     .06       0  5040.1     .12       0  5384.1     .16       0
  5482.7      .1       0  5587.5     .12       0    5613      .1       0
  5729.5     .16       0  5753.6      .1       0
#XS Ineff= 1 ,-1
 5064.29 5355.71   99.04
Permanent Ineff=
       T
Bank Sta=4949.9,5040.1
XS Rating Curve= 0 ,0
Exp/Cntr=0.3,0.1

Type RM Length L Ch R = 1 ,7334    ,440,440,440
BEGIN DESCRIPTION:
CHARQUITAS CREEK 8.0
END DESCRIPTION:
XS GIS Cut Line= 2
      2316817.43     13210057.24       2317636.9     13208918.31
#Sta/Elev= 30
  4441.4  124.58  4569.9  117.17  4686.1  108.29  4786.8  102.86  4833.5      99
  4893.1   95.57  4935.3   94.91  4943.9   92.97  4950.1   93.25  4958.6   91.72
  4964.8   92.26  4971.4   90.71  5050.7   91.21  5080.2   93.56    5101   94.21
  5107.2   95.49  5136.9   95.95    5187   98.45  5250.7  104.68  5296.2  106.01
  5369.9  107.46  5471.4  108.92  5489.1  108.96  5515.9  108.31  5566.2   109.3
  5595.7  112.09  5746.7   121.4  5782.3  122.99  5803.1  122.54  5844.5  124.91
#Mann= 11 ,-1 , 0
  4441.4     .05       0  4569.9      .1       0  4833.5     .16       0
  4893.1     .12       0  4950.1    .055       0  5136.9     .12       0
  5250.7      .1       0  5296.2     .12       0  5369.9      .1       0
  5471.4     .12       0  5489.1      .1       0
Bank Sta=4950.1,5080.2
XS Rating Curve= 0 ,0
Exp/Cntr=0.3,0.1

Type RM Length L Ch R = 1 ,6894    ,418,418,418
BEGIN DESCRIPTION:
CHARQUITAS CREEK 7.0
END DESCRIPTION:
XS GIS Cut Line= 3
      2317225.26     13210537.13      2317759.12     13209180.83
      2317821.63     13208925.97
#Sta/Elev= 30
  4083.6  139.46  4156.2  136.94  4161.5  132.06  4169.9  129.41  4185.9  125.94
  4191.4  123.41  4202.1  121.91  4210.3  122.44  4215.7  119.96  4264.5  116.01
  4384.8  102.85  4453.5   98.54    4503   95.43  4578.2   93.59  4600.7   92.86
  4670.5   91.21  4673.2   90.71  4676.5   91.21    5352   91.21    5383   93.24
  5413.4   95.45  5442.6   98.68  5448.7  100.92    5467  103.71  5472.4  103.44
  5521.1  109.92  5540.6  111.44  5594.9  114.13  5751.2  117.21  5803.6  121.11
#Mann= 6 ,-1 , 0
  4083.6      .1       0  4453.5     .16       0  4600.7     .07       0
  4670.5     .07       0  4676.5     .05       0  5413.4     .05       0
Bank Sta=4578.2,5383
XS Rating Curve= 0 ,0
Exp/Cntr=0.3,0.1

Type RM Length L Ch R = 1 ,6476    ,486,486,486
BEGIN DESCRIPTION:
CHARQUITAS CREEK 6.0
END DESCRIPTION:
XS GIS Cut Line= 2
      2317903.41     13210585.21      2317999.56      13208931.3
#Sta/Elev= 30
  4259.1  134.07  4287.5  133.51  4327.6   130.7  4338.9  128.86  4357.6  124.72
  4367.6  120.49  4407.7  115.22  4437.7  114.25  4497.9  108.09  4517.9  104.97
  4527.9  101.89  4537.9  101.09    4558   97.45    4568   94.81 4571.25   93.07
    4575   91.21  4577.7   90.71    4581   91.21  4635.3   91.21  4734.1   91.21
  5560.8   91.26  5579.7   92.78  5619.7   96.45  5669.8   99.57  5699.9  104.45
  5709.9  107.07    5750   112.3  5870.2  120.56  5900.2  128.08  5915.8  129.51
#Mann= 8 ,-1 , 0
  4259.1      .1       0  4338.9     .08       0  4437.7      .1       0
    4575     .07       0    4581      .1       0  4635.3     .12       0
  4734.1     .05       0  5560.8     .05       0
Bank Sta=4571.25,5579.7
XS Rating Curve= 0 ,0
Exp/Cntr=0.3,0.1

Type RM Length L Ch R = 1 ,5990    ,404,404,404
BEGIN DESCRIPTION:
CHARQUITAS CREEK 5.0
END DESCRIPTION:
XS GIS Cut Line= 3
      2318071.77     13210565.94      2318288.17     13210315.88
      2318691.91     13209071.01
#Sta/Elev= 30
    4243  117.37  4314.6  116.56  4390.1  118.32  4424.1  117.95  4444.9  114.51
  4473.4  116.08  4537.1  112.83  4565.6  110.45  4569.7  107.96  4588.4   104.7
  4604.2  104.33  4625.7   99.71  4698.8   99.12  4709.3   92.63  4713.3   91.21
  4716.1   90.71  5290.5   91.46 5300.89   93.07  5308.6   97.54  5319.1   98.81
  5329.2  102.73  5371.6  108.86  5430.3     106  5435.6  107.47  5558.9  109.54
  5599.2  109.53    5708  109.61  5760.6  111.23  5787.3  115.17  5882.4  116.92
#Mann= 8 ,-1 , 0
    4243      .1       0  4314.6     .08       0  4390.1      .1       0
  4713.3    .033       0  4716.1     .05       0  5290.5      .1       0
  5558.9     .08       0  5599.2      .1       0
Bank Sta=4709.3,5300.89
XS Rating Curve= 0 ,0
Exp/Cntr=0.3,0.1

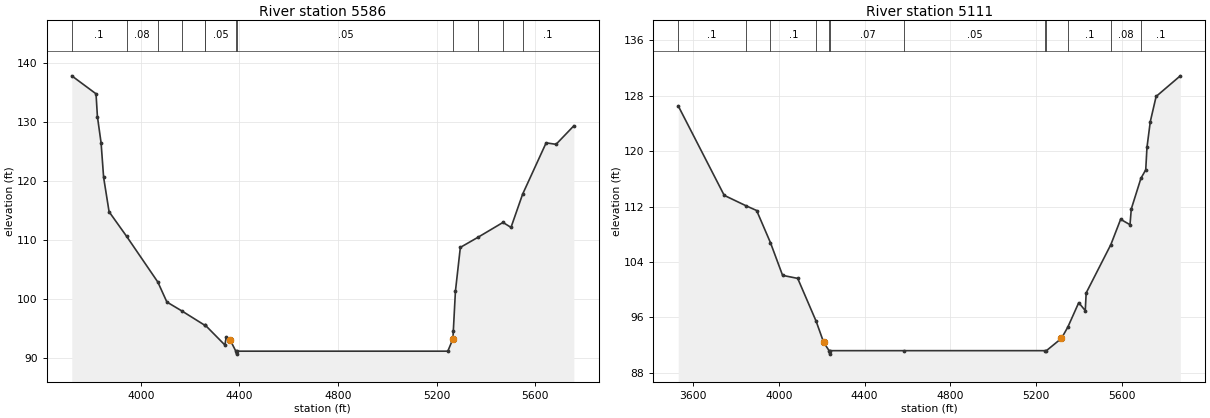
Type RM Length L Ch R = 1 ,5586    ,475,475,475
BEGIN DESCRIPTION:
CHARQUITAS CREEK 4.0
END DESCRIPTION:
XS GIS Cut Line= 3
      2318528.66     13211152.69      2318927.84     13209464.59
      2318985.55     13209166.38
#Sta/Elev= 30
  3719.1  137.88  3817.6  134.83  3823.2  130.98  3838.1  126.53  3848.4  120.67
  3870.6  114.84  3941.5  110.69  4068.6  102.92  4105.3   99.54  4166.8   98.01
  4259.6   95.59  4261.6    95.6  4340.8   92.25    4346   93.56  4362.2    93.1
  4385.2   91.21    4388   90.71  4391.2   91.21  5245.9   91.21  5266.5   93.29
  5268.2   94.63  5276.7  101.36  5296.7   108.8  5366.9  110.48  5469.8  113.03
  5502.4  112.19  5549.5  117.82    5645  126.52  5685.3  126.27  5757.5  129.41
#Mann= 12 ,-1 , 0
  3719.1      .1       0  3941.5     .08       0  4068.6      .1       0
  4166.8     .05       0  4259.6      .1       0  4261.6     .05       0
  4385.2    .033       0  4391.2     .05       0  5268.2     .08       0
  5366.9      .1       0  5469.8     .08       0  5549.5      .1       0
Bank Sta=4362.2,5266.5
XS Rating Curve= 0 ,0
Exp/Cntr=0.3,0.1

Type RM Length L Ch R = 1 ,5111    ,506,506,506
BEGIN DESCRIPTION:
CHARQUITAS CREEK 3.0
END DESCRIPTION:
XS GIS Cut Line= 3
      2319480.93     13211359.53      2319245.26     13209479.02
      2319010.45     13209100.45
#Sta/Elev= 30
    3531  126.54  3745.3  113.63    3848  112.11  3896.5  111.44  3960.9   106.8
  4017.5  102.08    4088  101.64    4174   95.45  4208.9   92.41  4234.3   91.21
    4237   90.71  4240.3   91.21    4585   91.21  5240.9   91.21  5247.4   91.21
  5317.5   92.98  5347.4   94.62  5398.2   98.14  5428.6   96.99  5432.8   99.54
    5548  106.53  5593.5  110.17  5637.2  109.39  5643.1  111.66  5688.1  116.09
  5710.5  117.31  5716.3  120.55  5731.7  124.26  5758.9   127.9  5871.7  130.88
#Mann= 12 ,-1 , 0
    3531      .1       0    3848     .08       0  3960.9      .1       0
    4174     .07       0  4234.3    .033       0  4240.3     .07       0
    4585     .05       0  5240.9      .1       0  5247.4     .08       0
  5347.4      .1       0    5548     .08       0  5688.1      .1       0
Bank Sta=4208.9,5317.5
XS Rating Curve= 0 ,0
Exp/Cntr=0.3,0.1