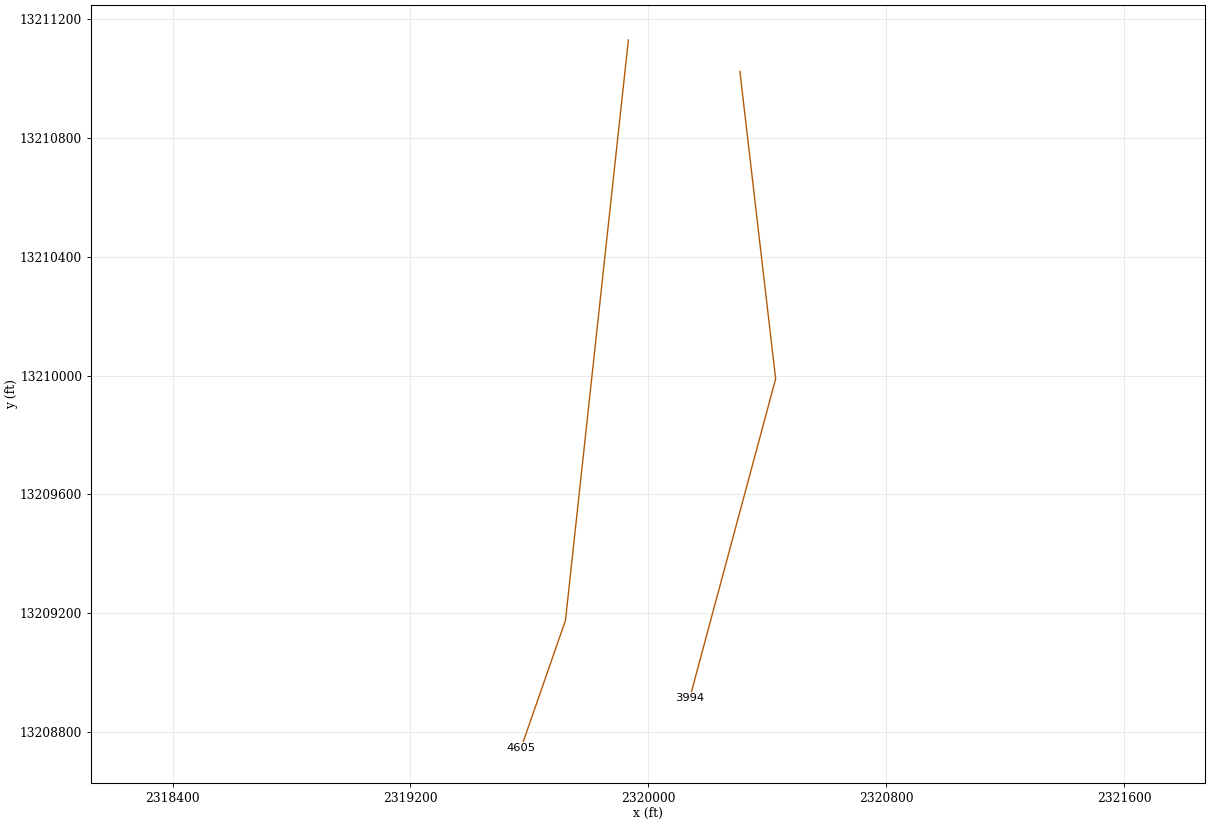
HEC-RAS study CHARQUITAS CREEK.prj: CHARQUITAS CREEK Base Level Engineering

--- CHARQUITAS CREEK.g01 (geometry) --- (continued)

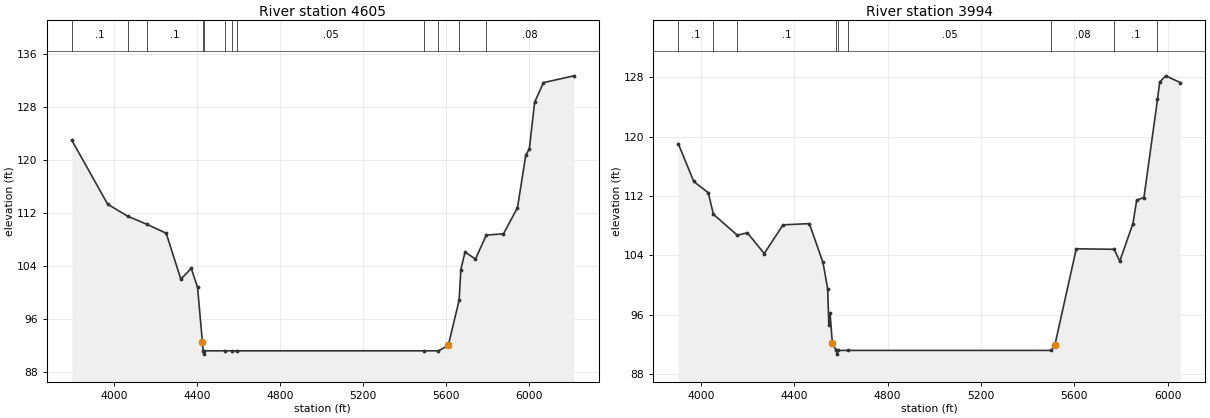
Type RM Length L Ch R = 1 ,4605    ,611,611,611
BEGIN DESCRIPTION:
CHARQUITAS CREEK 2.0
END DESCRIPTION:
XS GIS Cut Line= 3
      2319933.03     13211128.71      2319721.41     13209176.02
      2319572.51     13208748.53
#Sta/Elev= 30
  3797.8  123.03  3970.7  113.35  4067.1  111.54  4161.3  110.29  4252.3  108.97
  4322.7  102.03    4373  103.66  4403.2  100.79 4426.79   92.49  4430.4   91.21
  4433.1   90.71  4436.4   91.21  4534.5   91.21  4568.7   91.21  4592.8   91.21
  5493.1   91.21  5562.7   91.21  5610.2   92.02  5662.4   98.85  5670.6  103.47
  5690.7  106.13    5741  105.07  5793.3  108.69  5875.9  108.88  5943.3  112.83
  5983.4  120.79  6000.2  121.67  6025.8  128.75  6068.1  131.71  6214.6  132.74
#Mann= 12 ,-1 , 0
  3797.8      .1       0  4067.1     .08       0  4161.3      .1       0
  4430.4    .033       0  4436.4      .1       0  4534.5     .05       0
  4568.7      .1       0  4592.8     .05       0  5493.1      .1       0
  5562.7     .08       0  5662.4      .1       0  5793.3     .08       0
Bank Sta=4426.79,5610.2
XS Rating Curve= 0 ,0
Exp/Cntr=0.3,0.1

Type RM Length L Ch R = 1 ,3994    ,0,0,0
BEGIN DESCRIPTION:
CHARQUITAS CREEK 1.0
END DESCRIPTION:
XS GIS Cut Line= 3
      2320308.16     13211022.92      2320428.41     13209988.83
      2320139.84     13208916.33
#Sta/Elev= 30
  3902.5  119.05    3969  113.95  4031.5  112.43    4053  109.54  4155.9  106.71
  4198.6  107.05    4271  104.25  4351.6  108.11  4464.4  108.28  4522.7  103.05
  4542.9   99.52  4547.9   94.63    4553   96.28    4563   92.16  4580.1   91.21
  4582.9   90.71  4586.1   91.21    4628   91.21  5501.8   91.21 5516.96   91.99
  5608.4  104.89  5770.4  104.82  5794.8  103.22  5851.2  108.29  5867.3  111.45
  5898.3  111.78  5956.4  124.99  5965.9  127.33  5991.5  128.17  6054.2  127.26
#Mann= 9 ,-1 , 0
  3902.5      .1       0    4053     .08       0  4155.9      .1       0
  4580.1    .033       0  4586.1      .1       0    4628     .05       0
  5501.8     .08       0  5770.4      .1       0  5956.4     .08       0
Bank Sta=4563,5516.96
XS Rating Curve= 0 ,0
Exp/Cntr=0.3,0.1

Chan Stop Cuts=-1
Use User Specified Reach Order=0
Composite Channel Slope=5