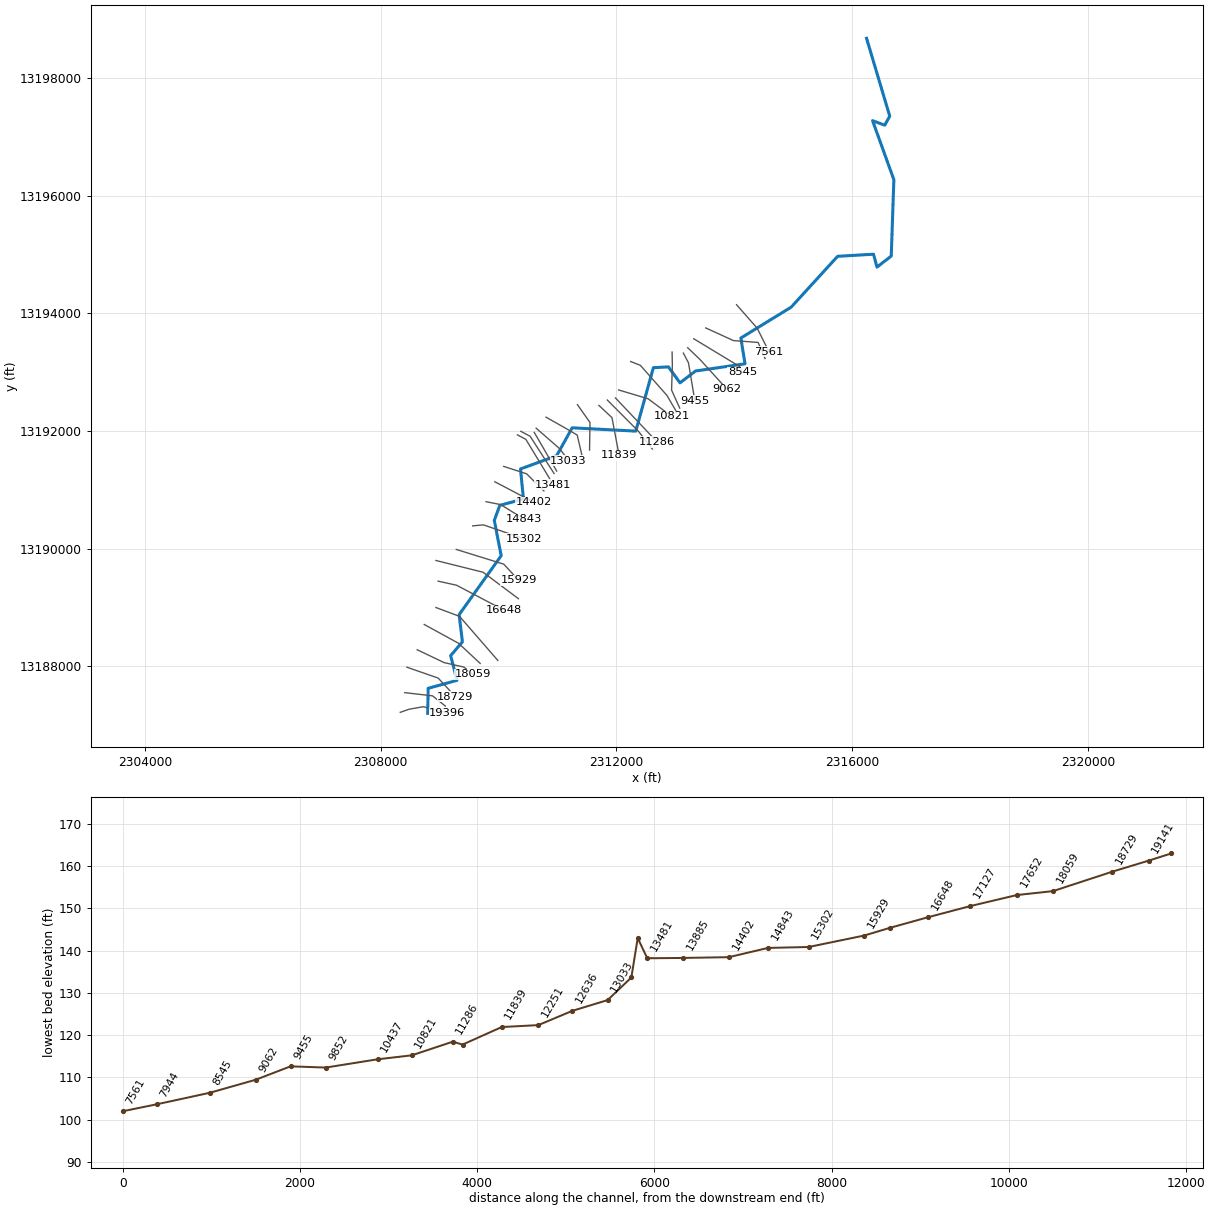
--- HOBBS HOLLOW.prj (project) ---

Proj Title=HOBBS HOLLOW Base Level Engineering
Current Plan=p01
Default Exp/Contr=0.3,0.1
English Units
Geom File=g01
Geom File=g02
Flow File=f01
Plan File=p01
Y Axis Title=Elevation
X Axis Title(PF)=Main Channel Distance
X Axis Title(XS)=Station
BEGIN DESCRIPTION:
HOBBS HOLLOW
END DESCRIPTION:
DSS Export Rating Curves= 0
DSS Export Rating Curve Sorted= 0
DSS Export Volume Flow Curves= 0
DXF OffsetX= 0
DXF OffsetY= 0
DXF ScaleX= 1
DXF ScaleY= 10

--- HOBBS HOLLOW.p01 (plan) ---

Plan Title=Multiple Run
Short Identifier=Multiple
Geom File=g01
Flow File=f01
Subcritical Flow
K Sum by GR= 0
Std Step Tol= 0.01
Critical Tol= 0.01
Num of Std Step Trials= 20
Max Error Tol= 0.3
Flow Tol Ratio= 0.001
Split Flow NTrial= 30
Split Flow Tol= 0.02
Split Flow Ratio= 0.02
Log Output Level= 0
Friction Slope Method= 1
Unsteady Friction Slope Method= 2
Unsteady Bridges Friction Slope Method= 1
Parabolic Critical Depth
Global Vel Dist=  1 , 1 , 1
Global Log Level= 0
CheckData=True
Encroach Param= -1, 0, 0, 0
BEGIN DESCRIPTION:
Multiple Run
END DESCRIPTION:

--- HOBBS HOLLOW.f01 (steady flow) ---

Flow Title=Multiple
Program Version=4.10
Number of Profiles= 7
Profile Names=10-year,25-year,50-year,1pct_min,100-year,1pct_plu,500-year
River Rch & RM=HOBBS HOLLOW,Reach-1         ,19396
     477     660     809     725     980    1325    1447
River Rch & RM=HOBBS HOLLOW,Reach-1         ,11396
     971    1389    1743    1593    2155    2914    3312
River Rch & RM=HOBBS HOLLOW,Reach-1         ,4528
    1183    1706    2151    1975    2671    3612    4141
Boundary for River Rch & Prof#=HOBBS HOLLOW,Reach-1         , 1
Up Type= 0
Dn Type= 3
Dn Slope=0.0004
Boundary for River Rch & Prof#=HOBBS HOLLOW,Reach-1         , 2
Up Type= 0
Dn Type= 3
Dn Slope=0.0004
Boundary for River Rch & Prof#=HOBBS HOLLOW,Reach-1         , 3
Up Type= 0
Dn Type= 3
Dn Slope=0.0004
Boundary for River Rch & Prof#=HOBBS HOLLOW,Reach-1         , 4
Up Type= 0
Dn Type= 3
Dn Slope=0.0004
Boundary for River Rch & Prof#=HOBBS HOLLOW,Reach-1         , 5
Up Type= 0
Dn Type= 3
Dn Slope=0.0004
Boundary for River Rch & Prof#=HOBBS HOLLOW,Reach-1         , 6
Up Type= 0
Dn Type= 3
Dn Slope=0.0004
Boundary for River Rch & Prof#=HOBBS HOLLOW,Reach-1         , 7
Up Type= 0
Dn Type= 3
Dn Slope=0.0004
DSS Import GetInterval= 0
DSS Import GetPeak= 0
DSS Import FillOption= 0

--- HOBBS HOLLOW.g01 (geometry) ---

Geom Title=Existing Conditions
Program Version=4.10

River Reach=HOBBS HOLLOW    ,Reach-1
Reach XY= 30
      2308797.72     13187196.86      2308805.43     13187623.13
      2309294.79     13187758.57      2309187.16     13188178.76
       2309386.6     13188412.78       2309330.6     13188875.67
      2310044.32     13189878.29       2309927.9     13190477.59
      2310020.91     13190734.66      2310421.95      13190842.3
      2310372.47     13191353.59      2310986.05     13191579.16
       2311248.9     13192053.06      2312327.72     13191996.86
      2312626.57     13193075.83      2312881.78     13193089.37
      2313078.14     13192818.01      2313341.68     13193019.06
      2314181.27      13193141.7      2314111.04     13193580.34
      2314963.94     13194104.58      2315752.58     13194969.76
      2316362.14     13195005.19      2316420.32     13194785.87
      2316662.35     13194974.22      2316706.72     13196272.21
      2316345.32      13197276.9      2316551.51      13197199.3
       2316636.5     13197353.67      2316243.55     13198676.47

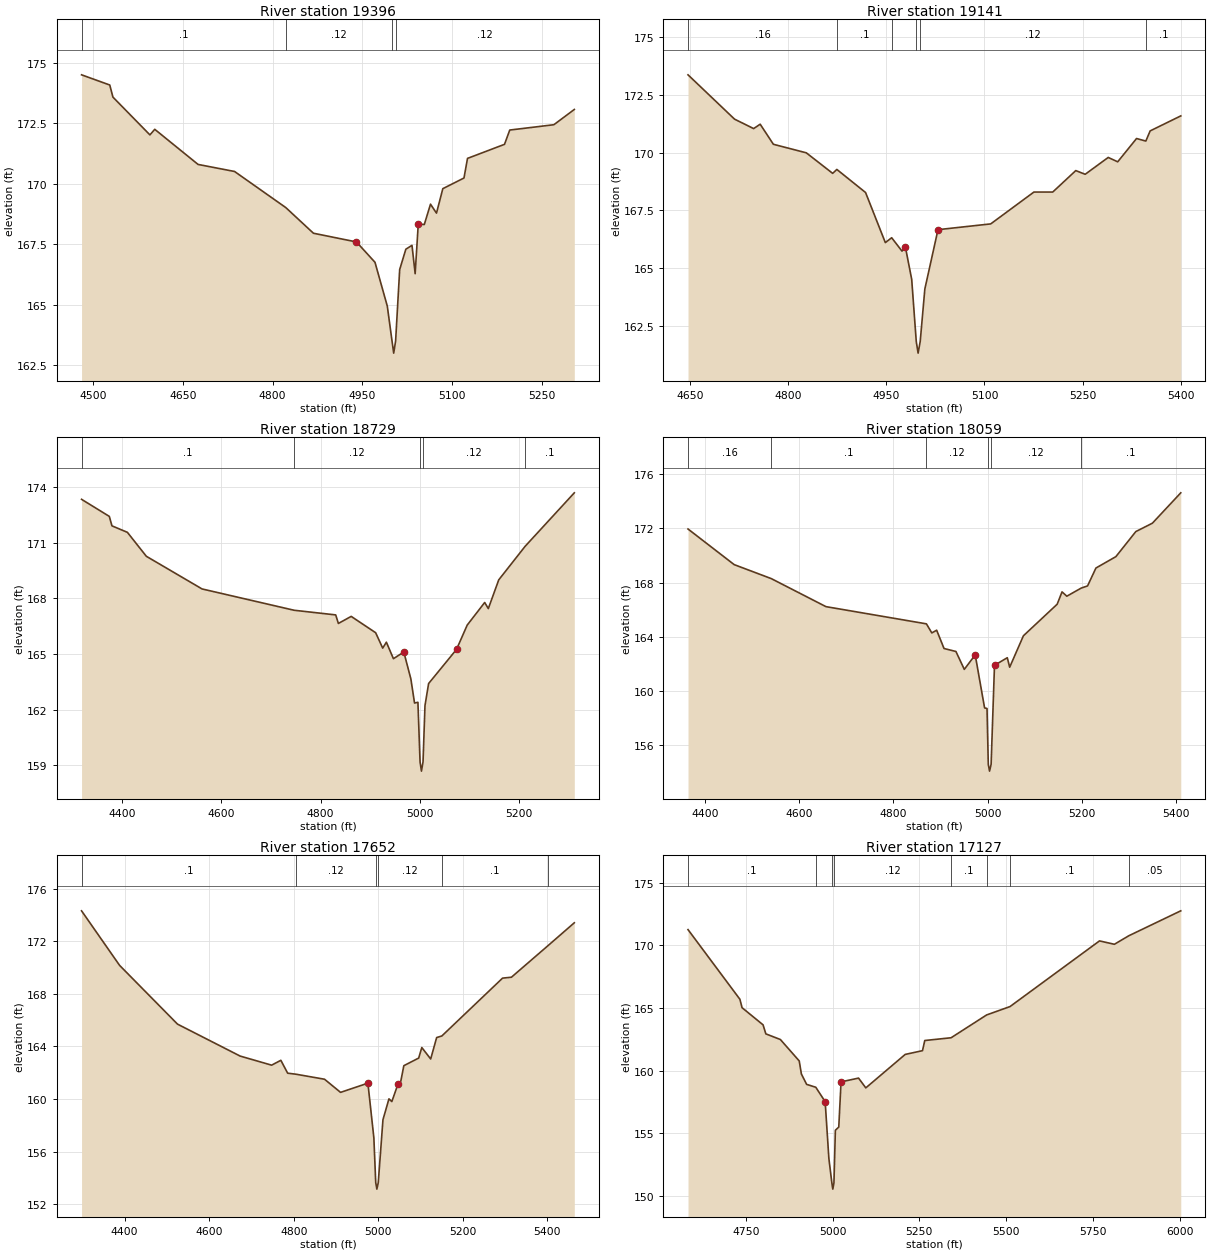
Type RM Length L Ch R = 1 ,19396   ,255,255,255
BEGIN DESCRIPTION:
HOBBS HOLLOW 39.0
END DESCRIPTION:
XS GIS Cut Line= 4
      2308332.24     13187214.71      2308479.82     13187266.79
      2308722.87     13187310.19      2309130.88     13187206.02
#Sta/Elev= 30
  4480.4   174.5  4527.6  174.08  4532.9  173.58  4594.8  172.02  4602.9  172.25
  4675.4   170.8  4736.4  170.51  4822.1  169.02  4868.4  167.96  4940.4   167.6
  4971.4  166.76    4992  164.95  4999.9  163.51  5002.7  163.01  5005.9  163.51
  5012.7  166.46    5023   167.3  5033.3  167.46  5038.6  166.29  5043.8  168.34
  5053.9  168.32  5064.3  169.16  5074.3  168.79  5084.9   169.8  5120.3  170.24
  5126.2  171.05  5188.1  171.63  5196.9  172.22  5270.7  172.44  5304.9  173.07
#Mann= 4 ,-1 , 0
  4480.4      .1       0  4822.1     .12       0  4999.9     .07       0
  5005.9     .12       0
Bank Sta=4940.4,5043.8
XS Rating Curve= 0 ,0
Exp/Cntr=0.3,0.1

Type RM Length L Ch R = 1 ,19141   ,412,412,412
BEGIN DESCRIPTION:
HOBBS HOLLOW 38.0
END DESCRIPTION:
XS GIS Cut Line= 3
      2308408.13     13187549.58      2308879.46      13187494.9
      2309097.35     13187321.11
#Sta/Elev= 30
  4646.9  173.37    4718  171.45  4747.2  171.04  4757.2  171.23  4777.4  170.36
  4827.7  169.99    4868   169.1  4874.4  169.27  4918.3  168.27  4948.5   166.1
  4958.2  166.31    4974  165.73    4979  165.93  4988.8  164.51  4995.8  161.81
  4998.6  161.31  5001.8  161.81  5008.9  164.09    5029  166.66  5109.6  166.91
  5175.6  168.29  5204.4  168.29  5239.6  169.22    5254  169.06  5289.2  169.79
  5303.7   169.6  5332.5  170.61  5346.7   170.5  5353.3  170.94  5400.1  171.59
#Mann= 6 ,-1 , 0
  4646.9     .16       0  4874.4      .1       0  4958.2     .12       0
  4995.8     .07       0  5001.8     .12       0  5346.7      .1       0
Bank Sta=4979,5029
XS Rating Curve= 0 ,0
Exp/Cntr=0.3,0.1

Type RM Length L Ch R = 1 ,18729   ,670,670,670
BEGIN DESCRIPTION:
Mapping XS 2cdf5fff
END DESCRIPTION:
XS GIS Cut Line= 3
      2308444.59     13187981.87      2308975.82     13187796.98
      2309267.51     13187481.85
#Sta/Elev= 30
  4318.7  173.33  4374.6  172.41  4379.9   171.9    4411  171.55  4449.1  170.26
  4561.2   168.5  4746.7  167.35  4830.3   167.1  4835.7  166.64  4861.5  167.02
  4910.7  166.14  4924.9  165.31  4932.3  165.63  4946.5  164.74  4967.4   165.1
  4981.6  163.65    4989  162.35  4995.8  162.39  5000.1  159.18  5002.9  158.68
  5006.1  159.18    5010  162.21  5017.3   163.4  5073.5  165.24    5095  166.55
  5130.2  167.77  5137.5  167.44  5158.5  168.99  5211.7   170.8  5310.6  173.68
#Mann= 5 ,-1 , 0
  4318.7      .1       0  4746.7     .12       0  5000.1     .07       0
  5006.1     .12       0  5211.7      .1       0
Bank Sta=4967.4,5073.5
XS Rating Curve= 0 ,0
Exp/Cntr=0.3,0.1

Type RM Length L Ch R = 1 ,18059   ,407,407,407
BEGIN DESCRIPTION:
HOBBS HOLLOW 37.0
END DESCRIPTION:
XS GIS Cut Line= 4
      2308619.09     13188278.73      2309077.38       13188060.
      2309410.71     13187984.48      2309565.48     13187860.67
#Sta/Elev= 30
  4363.1  171.95  4461.3  169.32  4540.1  168.29  4656.4  166.22    4870  164.95
  4881.5  164.28  4891.8  164.48  4907.5  163.13  4932.8  162.91  4950.6  161.59
  4973.8  162.66  4993.7  158.75  4998.9   158.7  5001.6  154.58  5004.3  154.08
  5007.6  154.58  5014.8  161.89    5042  162.45  5047.1  161.75  5076.3  164.07
  5148.1   166.4  5158.4  167.31  5168.6  166.99  5199.2  167.59  5212.7  167.75
  5230.5  169.07  5272.9  169.91  5315.3  171.76  5350.6  172.38  5410.9  174.62
#Mann= 6 ,-1 , 0
  4363.1     .16       0  4540.1      .1       0    4870     .12       0
  5001.6     .07       0  5007.6     .12       0  5199.2      .1       0
Bank Sta=4973.8,5014.8
XS Rating Curve= 0 ,0
Exp/Cntr=0.3,0.1

Type RM Length L Ch R = 1 ,17652   ,525,525,525
BEGIN DESCRIPTION:
HOBBS HOLLOW 36.0
END DESCRIPTION:
XS GIS Cut Line= 3
      2308738.87     13188708.42      2309322.17     13188388.13
      2309687.68     13188046.89
#Sta/Elev= 30
  4298.1  174.32  4388.1  170.17  4525.1   165.7  4673.3  163.27  4747.7  162.58
  4769.5  162.95  4785.6  161.97  4805.4  161.89  4872.8  161.51  4910.7  160.51
  4975.4  161.21  4989.5  157.05  4993.9  153.65  4996.6  153.15  4999.9  153.65
    5011  158.43  5025.2  160.02    5032  159.81  5046.2  161.11  5053.2  161.36
  5060.4  162.54  5095.5  163.12  5102.9  163.92  5123.9  163.05    5138  164.68
  5150.3   164.8  5293.9   169.2  5314.9  169.27    5401  171.66  5463.6  173.41
#Mann= 6 ,-1 , 0
  4298.1      .1       0  4805.4     .12       0  4993.9     .07       0
  4999.9     .12       0  5150.3      .1       0    5401     .05       0
Bank Sta=4975.4,5046.2
XS Rating Curve= 0 ,0
Exp/Cntr=0.3,0.1

Type RM Length L Ch R = 1 ,17127   ,479,479,479
BEGIN DESCRIPTION:
HOBBS HOLLOW 35.0
END DESCRIPTION:
XS GIS Cut Line= 3
      2308937.76     13188996.84      2309337.72     13188846.85
       2309987.7     13188096.88
#Sta/Elev= 30
  4583.6  171.25  4733.1  165.69  4739.3  165.02  4799.8  163.65  4807.8  162.93
  4849.7  162.48    4904  160.77  4910.2  159.73  4925.3   158.9  4951.7  158.67
  4978.7  157.52  4989.4  152.99    4998  151.04  5000.7  150.54    5004  151.04
  5008.1  155.24  5017.9  155.49  5024.5   159.1  5074.9   159.4  5095.8  158.62
  5209.3  161.29  5259.1  161.59  5265.7   162.4  5341.5  162.62  5443.8  164.44
  5511.3  165.11  5769.1  170.35  5811.9  170.08  5853.5  170.76  6003.2  172.75
#Mann= 8 ,-1 , 0
  4583.6      .1       0  4951.7     .12       0    4998     .07       0
    5004     .12       0  5341.5      .1       0  5443.8     .05       0
  5511.3      .1       0  5853.5     .05       0
Bank Sta=4978.7,5024.5
XS Rating Curve= 0 ,0
Exp/Cntr=0.3,0.1

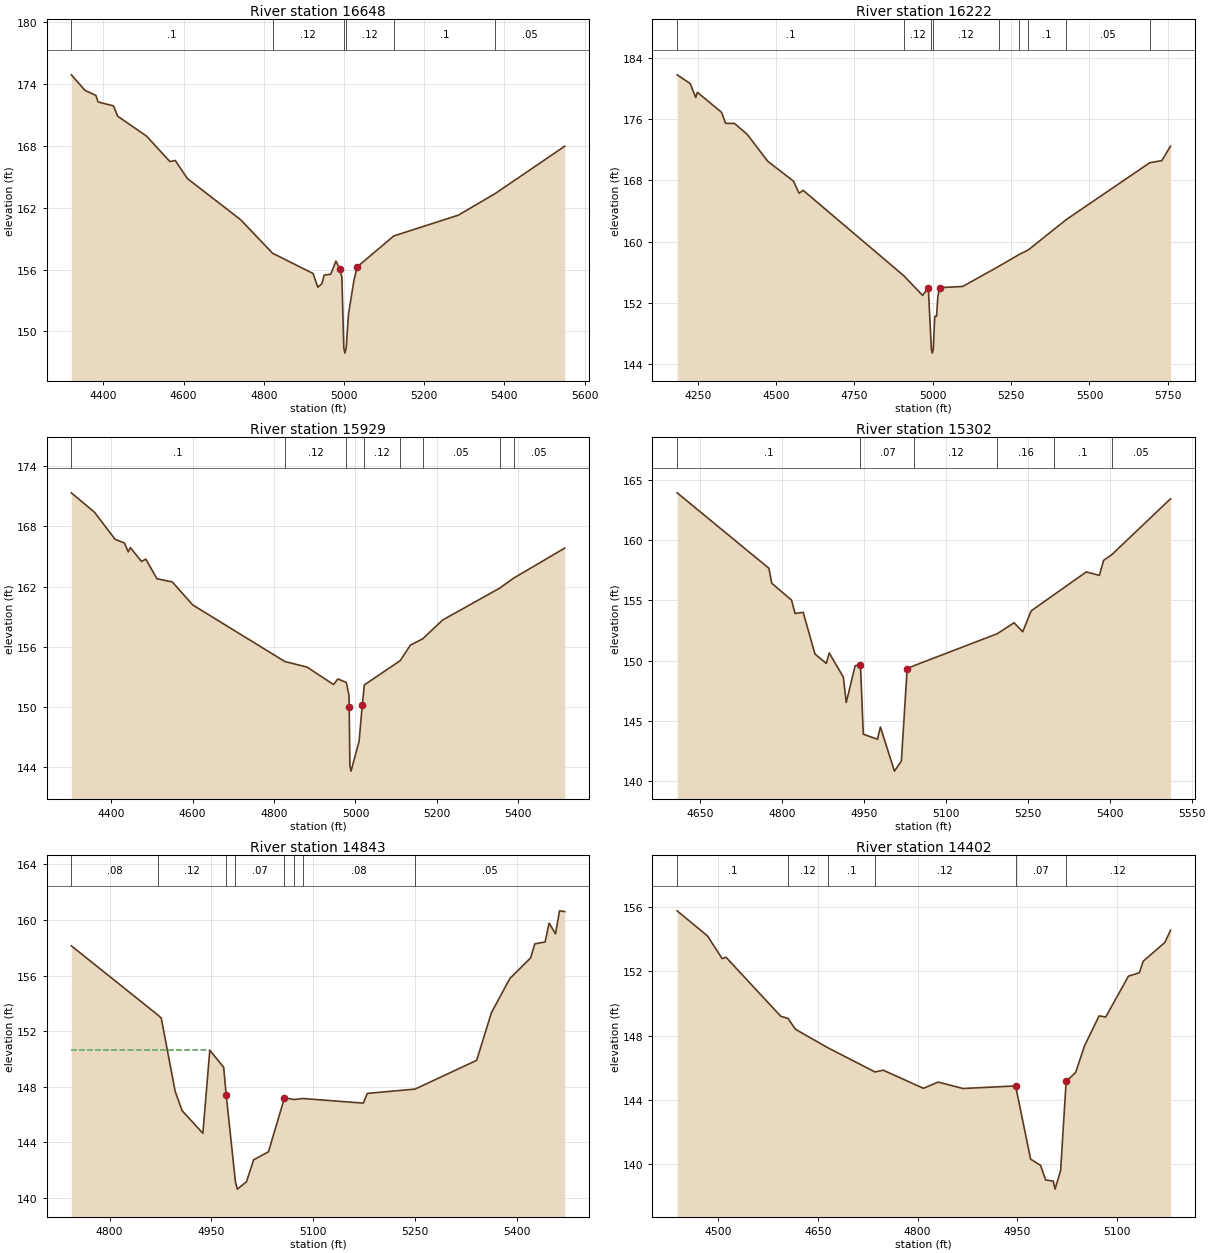
Type RM Length L Ch R = 1 ,16648   ,426,426,426
BEGIN DESCRIPTION:
HOBBS HOLLOW 34.0
END DESCRIPTION:
XS GIS Cut Line= 3
      2308974.64      13189445.6      2309287.11     13189376.17
      2310092.56     13188951.79
#Sta/Elev= 30
  4320.1  174.88    4354  173.38  4381.5  172.88  4386.7  172.25  4425.1  171.87
  4435.9  170.86  4507.6  168.94  4565.9  166.47  4579.4  166.57  4609.5  164.82
  4742.6  160.82  4821.9  157.58  4923.1  155.61  4934.8  154.28  4945.1  154.63
  4950.7  155.46  4967.1  155.54    4980  156.81  4989.2  156.07  4994.8  155.27
  4999.6  148.39  5002.3  147.89  5005.6  148.39  5011.2  151.65  5025.2  155.01
  5033.2  156.26  5124.1  159.25  5285.2  161.27  5377.4  163.37  5550.6  167.96
#Mann= 6 ,-1 , 0
  4320.1      .1       0  4821.9     .12       0  4999.6     .07       0
  5005.6     .12       0  5124.1      .1       0  5377.4     .05       0
Bank Sta=4989.2,5033.2
XS Rating Curve= 0 ,0
Exp/Cntr=0.3,0.1

Type RM Length L Ch R = 1 ,16222   ,293,293,293
BEGIN DESCRIPTION:
HOBBS HOLLOW 33.0
END DESCRIPTION:
XS GIS Cut Line= 3
       2308937.7     13189796.86      2309737.72     13189596.85
      2310337.68     13189146.88
#Sta/Elev= 30
  4184.3  181.82  4225.6  180.69  4243.6  178.85  4248.7  179.54  4326.1  176.91
  4338.9  175.47  4367.3  175.46  4408.5     174  4472.9  170.53  4555.4  167.91
  4573.4  166.32  4586.3  166.71  4907.3  155.54  4967.7  152.95  4985.8  153.97
  4995.6   145.9  4998.4   145.4  5001.6   145.9  5006.4  150.22  5012.1  150.22
  5016.2   152.8  5022.5  153.97  5095.4  154.12  5212.9  156.81  5276.6  158.33
  5304.5  158.89  5425.5  162.86  5692.2  170.31  5730.8  170.59  5758.9  172.49
#Mann= 9 ,-1 , 0
  4184.3      .1       0  4907.3     .12       0  4995.6     .07       0
  5001.6     .12       0  5212.9      .1       0  5276.6     .05       0
  5304.5      .1       0  5425.5     .05       0  5692.2      .1       0
Bank Sta=4985.8,5022.5
XS Rating Curve= 0 ,0
Exp/Cntr=0.3,0.1

Type RM Length L Ch R = 1 ,15929   ,627,627,627
BEGIN DESCRIPTION:
HOBBS HOLLOW 32.0
END DESCRIPTION:
XS GIS Cut Line= 3
      2309283.11     13189984.48       2310087.8     13189734.48
      2310337.79     13189463.66
#Sta/Elev= 30
  4302.5  171.36  4359.7  169.41  4409.6  166.73    4433  166.34  4442.2  165.46
  4447.4  165.89  4474.8   164.5  4485.3  164.74  4512.6  162.78  4550.4  162.46
  4600.5  160.16  4826.6  154.51  4881.2  153.95  4946.1  152.21  4956.8  152.77
  4977.5  152.42  4984.1  151.15 4984.58  150.01  4986.3  144.06  4989.1  143.56
  5008.9  146.55  5016.7  150.17  5021.9  152.18    5110   154.6  5134.6  156.14
  5165.1  156.78  5214.1  158.66  5353.7  161.83  5388.3  162.84  5513.7  165.84
#Mann= 8 ,-1 , 0
  4302.5      .1       0  4826.6     .12       0  4977.5     .07       0
  5021.9     .12       0    5110      .1       0  5165.1     .05       0
  5353.7      .1       0  5388.3     .05       0
Bank Sta=4984.58,5016.7
XS Rating Curve= 0 ,0
Exp/Cntr=0.3,0.1

Type RM Length L Ch R = 1 ,15302   ,459,459,459
BEGIN DESCRIPTION:
HOBBS HOLLOW 31.0
END DESCRIPTION:
XS GIS Cut Line= 3
      2309560.57     13190385.43      2309742.85     13190402.79
      2310423.51     13190168.67
#Sta/Elev= 30
  4608.5   163.9  4776.4  157.65  4781.6  156.41  4817.9  155.01  4824.2  153.91
  4839.1     154  4860.7  150.55  4881.4  149.77  4886.7  150.64  4912.6  148.64
  4917.9  146.53  4934.2  149.58  4943.9  149.67  4949.1  143.91  4975.1  143.49
  4980.4  144.51  5006.1  140.85  5018.8  141.69  5029.4  149.34  5042.8   149.6
  5194.2  152.23    5225  153.14  5240.9  152.39  5256.2  154.12    5299  155.49
  5357.2  157.35  5381.1  157.06  5388.9  158.31  5403.9  158.78  5511.4  163.41
#Mann= 6 ,-1 , 0
  4608.5      .1       0  4943.9     .07       0  5042.8     .12       0
  5194.2     .16       0    5299      .1       0  5403.9     .05       0
Bank Sta=4943.9,5029.4
XS Rating Curve= 0 ,0
Exp/Cntr=0.3,0.1

Type RM Length L Ch R = 1 ,14843   ,441,441,441
BEGIN DESCRIPTION:
HOBBS HOLLOW 30.0
END DESCRIPTION:
XS GIS Cut Line= 3
      2309787.77     13190796.85      2310037.72     13190746.85
      2310437.72     13190496.86
#Sta/Elev= 30
  4743.7  158.14    4871  153.17  4876.2  152.93  4896.6  147.67  4906.8  146.28
  4937.4  144.65  4947.6  150.63    4968   149.4  4971.7  147.44  4985.4  141.13
  4988.2  140.63  5001.6  141.16  5012.2  142.74    5034  143.32  5057.6   147.2
  5071.8  147.08    5085  147.15  5173.7  146.82  5179.6  147.52  5249.9  147.83
  5340.6   149.9  5362.4  153.34  5389.5  155.79  5420.2  157.28  5426.1  158.28
  5441.4  158.42  5447.3  159.78  5456.7     159  5462.6  160.66  5470.3  160.61
#Mann= 8 ,-1 , 0
  4743.7     .08       0    4871     .12       0  4971.7     .08       0
  4985.4     .07       0  5057.6     .08       0  5071.8     .12       0
    5085     .08       0  5249.9     .05       0
#XS Ineff= 2 , 0
       0 4947.78  150.66               0
Permanent Ineff=
       T       F
Bank Sta=4971.7,5057.6
XS Rating Curve= 0 ,0
Exp/Cntr=0.3,0.1

Type RM Length L Ch R = 1 ,14402   ,517,517,517
BEGIN DESCRIPTION:
HOBBS HOLLOW 29.0
END DESCRIPTION:
XS GIS Cut Line= 2
      2309936.72     13191135.54       2310594.2     13190789.91
#Sta/Elev= 30
  4437.9  155.78  4483.7  154.21  4505.7   152.8  4511.4  152.89  4593.9  149.21
  4604.7  149.08    4616   148.4  4664.7  147.25  4735.8  145.74  4748.2  145.85
  4808.7  144.72  4830.7  145.11  4868.3  144.71  4947.4  144.87    4970  140.31
    4985  139.92  4992.6  139.01  5004.1  138.94  5006.8  138.44  5015.2   139.6
  5023.5  145.15  5037.8  145.71  5051.2  147.37  5073.2  149.24    5083  149.16
  5117.3  151.71  5133.7  151.92  5139.5  152.64  5172.1  153.81  5180.7  154.57
#Mann= 6 ,-1 , 0
  4437.9      .1       0  4604.7     .12       0  4664.7      .1       0
  4735.8     .12       0  4947.4     .07       0  5023.5     .12       0
Bank Sta=4947.4,5023.5
XS Rating Curve= 0 ,0
Exp/Cntr=0.3,0.1

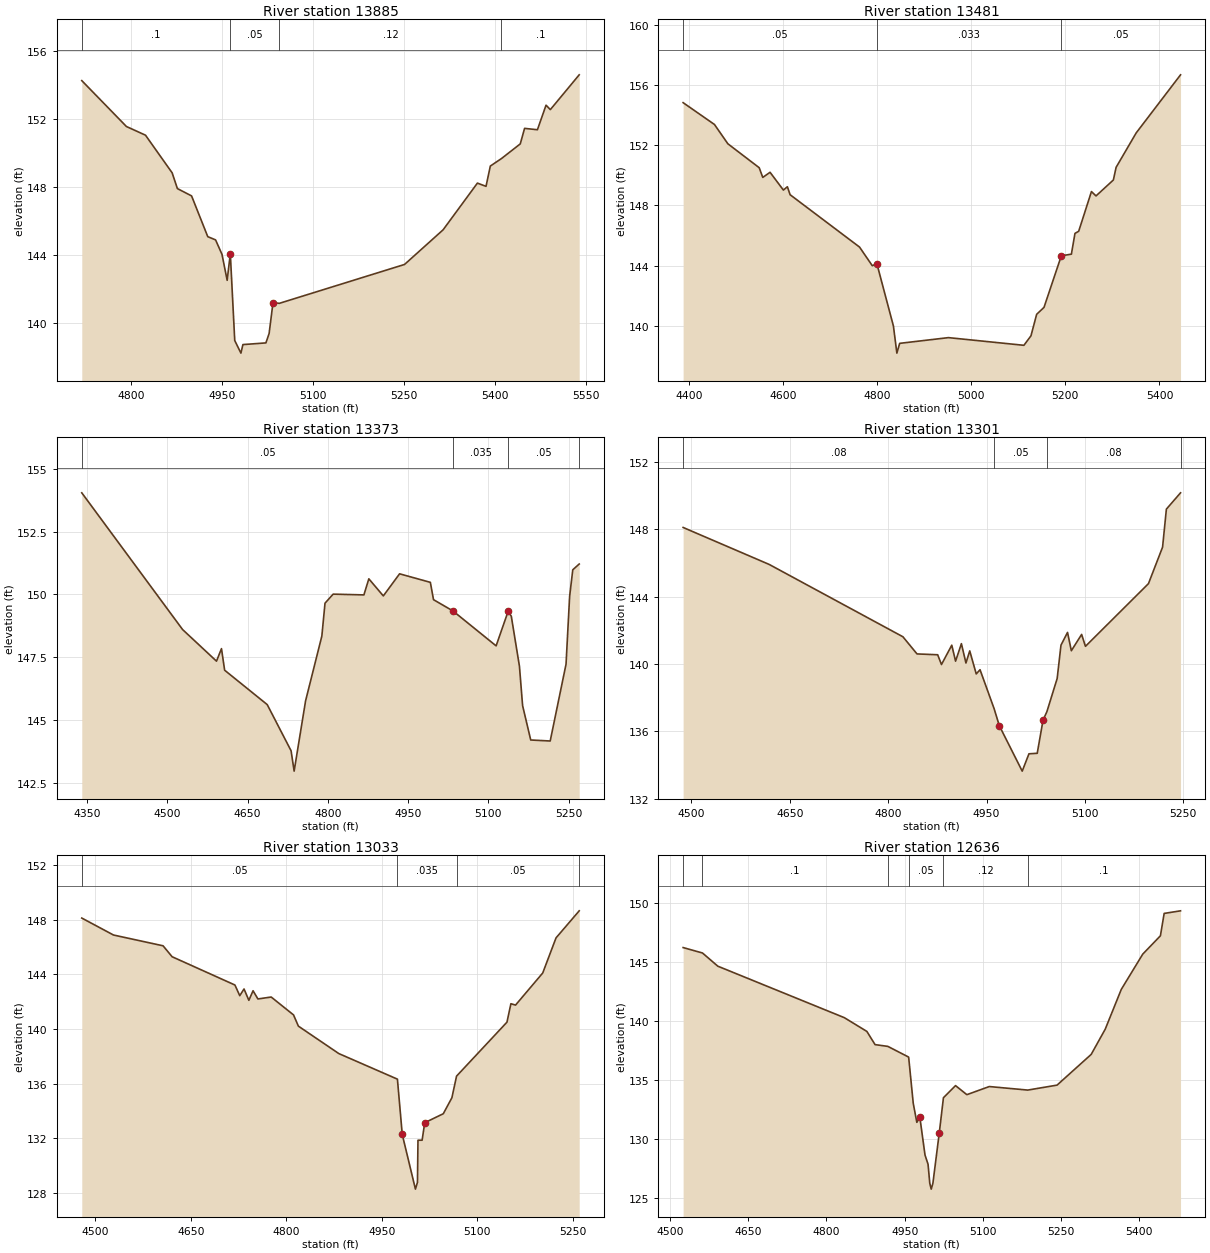
Type RM Length L Ch R = 1 ,13885   ,404,404,404
BEGIN DESCRIPTION:
HOBBS HOLLOW 28.0
END DESCRIPTION:
XS GIS Cut Line= 3
      2310087.75     13191396.85      2310475.82     13191270.94
       2310768.8     13190980.55
#Sta/Elev= 30
  4718.5  154.24  4792.1  151.55  4823.6  151.04  4867.6  148.83  4876.2  147.91
  4899.6  147.48  4926.3  145.09  4939.2   144.9  4949.8  144.05  4958.3  142.53
  4963.5  144.09  4970.8     139    4981  138.26  4984.3  138.76  5022.2  138.86
  5027.5  139.41  5033.9  141.22  5044.4  141.18  5250.9  143.46  5314.5  145.49
  5371.1  148.23  5385.3  148.04  5392.4  149.23  5410.8  149.67  5441.8  150.53
  5448.9  151.44  5470.1  151.36  5484.3   152.8  5491.4  152.54    5539  154.58
#Mann= 4 ,-1 , 0
  4718.5      .1       0  4963.5     .05       0  5044.4     .12       0
  5410.8      .1       0
Bank Sta=4963.5,5033.9
XS Rating Curve= 0 ,0
Exp/Cntr=0.3,0.1

Type RM Length L Ch R = 1 ,13481   ,108,108,108
BEGIN DESCRIPTION:
HOBBS HOLLOW 27.0
END DESCRIPTION:
XS GIS Cut Line= 4
     2310319.617    13191932.823      2310462.75     13191856.94
      2310852.82     13191212.03     2310916.881     13191088.69
#Sta/Elev= 30
    4388 154.8294454.552153.37964483.075152.09554549.627150.5051  4557.2  149.86
  4572.7   150.2    4601  149.02  4609.5  149.24  4615.3  148.71  4762.8  145.23
  4789.9  143.99  4799.6  144.13  4834.8  139.98  4842.1  138.18  4848.1  138.83
  4951.7  139.21    5112   138.7    5127  139.33  5139.1  140.76  5154.7  141.22
  5191.5  144.65  5212.9  144.76  5220.5  146.14  5228.4  146.28  5255.5  148.92
  5265.2  148.63  5302.1  149.69  5307.9  150.535350.673152.82295444.797  156.68
#Mann= 3 , 0 , 0
    4388     .05       0  4799.6    .033       0  5191.5     .05       0
Bank Sta=4799.6,5191.5
XS Rating Curve= 0 ,0
Exp/Cntr=0.3,0.1

Type RM Length L Ch R = 1 ,13373   ,72,72,72
BEGIN DESCRIPTION:
Mapping XS f2c6afef
END DESCRIPTION:
XS GIS Cut Line= 3
      2310377.97    13191993.294      2310535.72     13191908.95
      2310941.98     13191276.13
#Sta/Elev= 30
    4340154.0461  4528.4   148.6  4591.8  147.34  4601.1  147.84    4607  146.98
  4686.6  145.61  4731.2  143.77  4736.9  142.96  4758.3  145.76  4788.7  148.34
  4794.6  149.65  4809.8  150.01  4867.3  149.98  4876.5  150.62  4903.6  149.94
    4934  150.82  4991.5  150.48  4997.4  149.79  5033.8  149.34  5114.4  147.95
  5136.8  149.32  5142.8  149.13    5158  147.14  5163.9  145.57  5179.1   144.2
  5215.5  144.16  5245.1  147.22  5251.8  149.92  5257.7  150.98  5269.7  151.21
#Mann= 4 ,-1 , 0
    4340     .05       0  5033.8    .035       0  5136.8     .05       0
  5269.7      .1       0
#XS Ineff= 2 ,-1
 4406.67  4932.5  150.59 5138.19 5265.28  149.24
Permanent Ineff=
       T       T
Bank Sta=5033.8,5136.8
XS Rating Curve= 0 ,0
Exp/Cntr=0.3,0.1

Type RM Length L Ch R = 1 ,13301   ,268,268,268
BEGIN DESCRIPTION:
Mapping XS 2bba420b
END DESCRIPTION:
XS GIS Cut Line= 2
      2310606.05     13191974.03      2310986.24     13191317.81
#Sta/Elev= 30
  4487.3  148.12  4618.6  145.92  4822.4  141.62  4843.9   140.6  4875.4  140.55
  4881.2  139.97  4896.9  141.12  4902.7  140.17  4911.6  141.21  4918.5  140.06
  4924.3  140.78  4934.2  139.41    4940  139.66  4961.5  137.34  4969.4  136.33
  5004.3  133.63  5014.6  134.66  5027.2  134.69  5036.1  136.67  5041.9  137.16
  5057.6  139.14  5063.4  141.12  5073.4  141.88  5079.2  140.79  5094.9  141.76
  5100.7  141.05  5196.8  144.78  5218.3  146.95  5224.1  149.21  5245.7  150.18
#Mann= 4 ,-1 , 0
  4487.3     .08       0  4961.5     .05       0  5041.9     .08       0
  5245.7      .1       0
Bank Sta=4969.4,5036.1
XS Rating Curve= 0 ,0
Exp/Cntr=0.3,0.1

Type RM Length L Ch R = 1 ,13033   ,397,397,397
BEGIN DESCRIPTION:
HOBBS HOLLOW 26.0
END DESCRIPTION:
XS GIS Cut Line= 3
      2310637.71     13192046.87      2311037.72     13191696.85
       2311187.7     13191496.88
#Sta/Elev= 30
  4478.9  148.11  4528.7  146.87  4606.6  146.08  4620.8  145.28  4719.5  143.21
  4727.1  142.43  4733.8  142.92  4741.4  142.09    4748  142.79  4755.6  142.19
  4776.5  142.33  4811.6  141.02  4819.2   140.2  4882.8  138.19  4974.8  136.32
  4982.4  132.27  5003.1  128.27  5006.3  128.77  5007.1  131.85  5013.6  131.85
  5017.7  133.13  5046.9  133.79  5060.4  134.96  5067.7  136.54  5146.9  140.49
  5153.1  141.84  5160.4  141.74  5203.1  144.09    5224  146.66  5260.4  148.64
#Mann= 4 ,-1 , 0
  4478.9     .05       0  4974.8    .035       0  5067.7     .05       0
  5260.4      .1       0
Bank Sta=4982.4,5017.7
XS Rating Curve= 0 ,0
Exp/Cntr=0.3,0.1

Type RM Length L Ch R = 1 ,12636   ,385,385,385
BEGIN DESCRIPTION:
HOBBS HOLLOW 25.0
END DESCRIPTION:
XS GIS Cut Line= 4
      2310804.38      13192234.3      2311103.84     13192065.04
      2311333.87      13191930.5        2311412.     13191596.28
#Sta/Elev= 30
  4525.2  146.25  4562.3  145.79  4591.7  144.67  4834.2   140.3  4877.5  139.13
  4893.2  138.01  4917.7  137.86  4957.6  136.95  4966.4  133.03  4973.3  131.41
  4979.1  131.83    4989  128.63  4994.8  127.85  4998.1  126.24  5000.9  125.74
  5004.1  126.24  5016.3  130.51  5024.3   133.5  5047.5  134.53  5069.2  133.76
  5112.2  134.45  5185.9  134.15  5242.1  134.57  5307.6  137.18  5334.5  139.32
  5365.3   142.7  5406.4  145.69  5440.3  147.25  5447.5  149.15  5478.9  149.37
#Mann= 6 ,-1 , 0
  4525.2     .08       0  4562.3      .1       0  4917.7     .12       0
  4957.6     .05       0  5024.3     .12       0  5185.9      .1       0
Bank Sta=4979.1,5016.3
XS Rating Curve= 0 ,0
Exp/Cntr=0.3,0.1

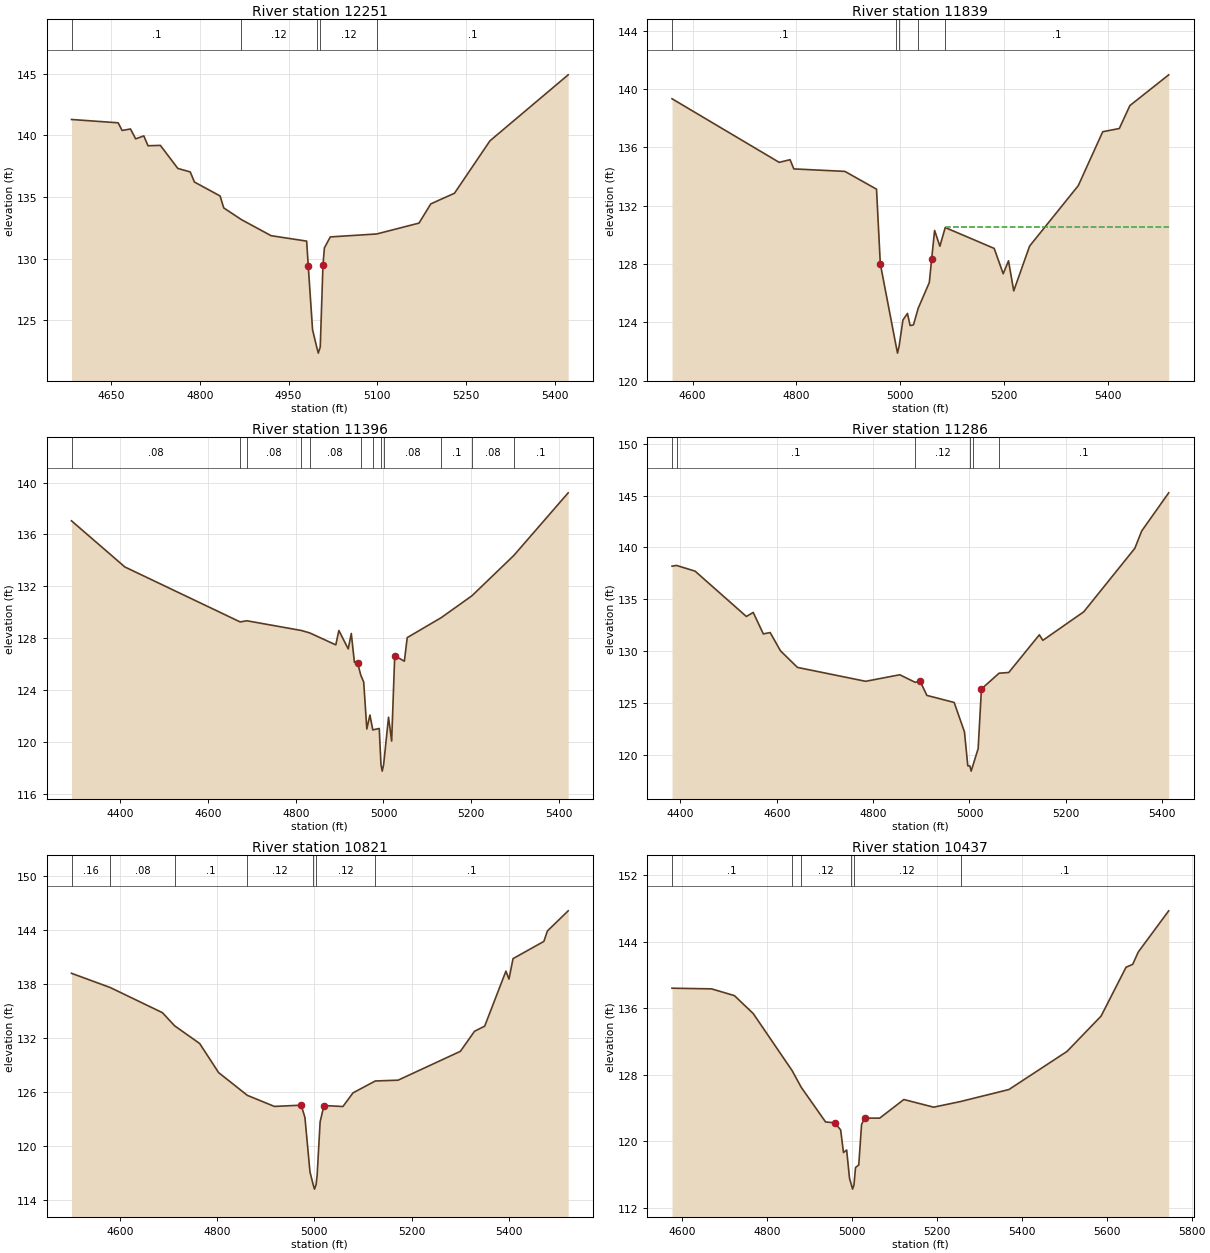
Type RM Length L Ch R = 1 ,12251   ,412,412,412
BEGIN DESCRIPTION:
HOBBS HOLLOW 24.0
END DESCRIPTION:
XS GIS Cut Line= 3
       2311337.7     13192446.88      2311551.34     13192143.34
      2311543.53     13191674.59
#Sta/Elev= 30
    4583  141.29  4661.9  141.02  4668.6   140.4  4682.8  140.52  4691.5  139.72
  4705.3  139.96  4712.4  139.16  4733.3  139.19  4762.9  137.32  4783.8  137.04
  4790.9  136.22  4834.3  135.09  4840.5  134.12  4870.5  133.17  4920.6  131.87
  4980.7  131.43 4983.43  129.42  4990.7  124.24  4997.7  122.85  5000.4  122.35
  5003.7  122.85 5008.29  129.49  5010.7  130.88  5020.7  131.77  5099.2  132.01
  5170.7  132.89  5190.7  134.45  5230.7  135.31  5290.7  139.56    5423  144.91
#Mann= 5 ,-1 , 0
    4583      .1       0  4870.5     .12       0  4997.7     .07       0
  5003.7     .12       0  5099.2      .1       0
Bank Sta=4983.43,5008.29
XS Rating Curve= 0 ,0
Exp/Cntr=0.3,0.1

Type RM Length L Ch R = 1 ,11839   ,443,443,443
BEGIN DESCRIPTION:
HOBBS HOLLOW 23.0
END DESCRIPTION:
XS GIS Cut Line= 3
       2311702.8     13192433.96      2311924.15     13192225.63
      2312045.67     13191583.29
#Sta/Elev= 30
  4560.3  139.34  4766.9  134.98  4787.9  135.16  4795.2  134.53  4893.6  134.36
  4954.6  133.14  4961.9  128.03  4992.3   122.4  4995.1   121.9  4998.3   122.4
  5005.5  124.17  5014.3  124.62  5019.4  123.79  5025.9  123.84  5034.9  124.97
  5056.4  126.74 5060.83  128.32  5066.6  130.31  5076.8  129.23  5087.1  130.51
  5181.5  129.08  5198.9  127.34  5209.1  128.23  5219.2  126.17  5249.8  129.24
  5343.6  133.38  5390.8  137.08  5422.8   137.3  5443.1  138.87    5518  140.98
#Mann= 5 ,-1 , 0
  4560.3      .1       0  4992.3     .07       0  4998.3      .1       0
  5034.9     .12       0  5087.1      .1       0
#XS Ineff= 2 , 0
       0                 5089.17       0  130.58
Permanent Ineff=
       F       T
Bank Sta=4961.9,5060.83
XS Rating Curve= 0 ,0
Exp/Cntr=0.3,0.1

Type RM Length L Ch R = 1 ,11396   ,110,110,110
BEGIN DESCRIPTION:
Mapping XS 732dd1f9
END DESCRIPTION:
XS GIS Cut Line= 3
      2311844.77     13192525.94      2312372.52     13191994.73
      2312608.62     13191692.65
#Sta/Elev= 30
  4288.8  137.05  4410.5  133.49  4673.3  129.25  4688.6  129.34  4812.7  128.59
  4832.1   128.4  4891.3  127.48  4898.3  128.59  4919.6  127.17  4926.6  128.36
  4933.7  126.14  4940.8  126.12  4948.1  125.16  4954.9  124.61    4962  120.99
  4969.1  122.07  4975.6  120.92  4990.3  121.03  4994.3  118.24  4997.1  117.74
  5000.3  118.24  5011.5   121.9  5018.6  120.06  5025.6  126.64  5047.6  126.22
  5054.1  128.04  5131.6  129.58  5201.7  131.27  5297.2  134.38    5421  139.21
#Mann= 12 ,-1 , 0
  4288.8     .08       0  4673.3      .1       0  4688.6     .08       0
  4812.7     .12       0  4832.1     .08       0  4948.1     .12       0
  4975.6     .08       0  4994.3     .07       0  5000.3     .08       0
  5131.6      .1       0  5201.7     .08       0  5297.2      .1       0
Bank Sta=4940.8,5025.6
XS Rating Curve= 0 ,0
Exp/Cntr=0.3,0.1

Type RM Length L Ch R = 1 ,11286   ,465,465,465
BEGIN DESCRIPTION:
HOBBS HOLLOW 22.0
END DESCRIPTION:
XS GIS Cut Line= 2
       2311983.6     13192560.73      2312691.44     13191811.25
#Sta/Elev= 30
  4382.6  138.19    4392  138.26  4430.5  137.71  4536.9  133.34  4551.1  133.73
  4572.1  131.66  4586.3  131.79  4607.7  130.03  4642.9  128.43  4784.5  127.09
  4855.3  127.72  4887.4  126.99  4897.4  127.11  4911.6  125.73  4968.2  125.05
  4989.6  122.21  4996.5  118.94  5000.8  118.93  5003.5  118.43  5006.8  118.93
    5018   120.6  5024.8  126.35  5061.4  127.87  5081.5  127.94    5145  131.57
  5152.3  131.04  5237.2  133.79  5343.2  139.91  5357.4  141.58  5413.5  145.26
#Mann= 6 ,-1 , 0
  4382.6     .08       0    4392      .1       0  4887.4     .12       0
  5000.8     .07       0  5006.8     .12       0  5061.4      .1       0
Bank Sta=4897.4,5024.8
XS Rating Curve= 0 ,0
Exp/Cntr=0.3,0.1

Type RM Length L Ch R = 1 ,10821   ,384,384,384
BEGIN DESCRIPTION:
HOBBS HOLLOW 21.0
END DESCRIPTION:
XS GIS Cut Line= 3
      2312037.69     13192696.86      2312537.72     13192546.85
      2312937.68     13192246.88
#Sta/Elev= 30
  4500.3   139.2  4579.9  137.62  4687.4  134.82  4712.5  133.36    4764  131.39
  4803.1  128.15  4862.2  125.62  4917.9  124.39  4972.8  124.53  4980.6  123.18
    4991  117.11  4997.6  115.69  5000.3  115.19  5003.6  115.69  5005.8  116.77
  5011.9  122.67  5019.7  124.49  5058.8  124.38  5079.6   125.9  5125.4  127.22
  5172.3  127.31  5300.5  130.52  5329.6  132.75  5350.5  133.32  5394.2  139.44
  5400.5  138.56  5408.8  140.83  5472.3  142.75  5479.6  143.91  5522.3  146.15
#Mann= 7 ,-1 , 0
  4500.3     .16       0  4579.9     .08       0  4712.5      .1       0
  4862.2     .12       0  4997.6     .07       0  5003.6     .12       0
  5125.4      .1       0
Bank Sta=4972.8,5019.7
XS Rating Curve= 0 ,0
Exp/Cntr=0.3,0.1

Type RM Length L Ch R = 1 ,10437   ,585,585,585
BEGIN DESCRIPTION:
HOBBS HOLLOW 20.0
END DESCRIPTION:
XS GIS Cut Line= 4
      2312241.02     13193180.48      2312405.92     13193115.39
      2312857.31     13192603.24      2313013.14     13192334.86
#Sta/Elev= 30
  4575.6  138.41  4668.8  138.33  4722.6  137.52    4767  135.36  4858.4  128.52
  4879.9  126.51  4937.5  122.33  4958.7  122.24  4972.9  121.38  4979.6  118.66
  4987.1  118.96  4993.8  115.57  4998.3  114.76  5001.1  114.26  5004.3  114.76
    5008  116.86  5015.6  117.16  5022.2  122.03  5029.8   122.8  5064.9  122.79
  5121.8  125.03  5192.1  124.11  5255.5  124.79  5369.4  126.23  5506.3  130.81
  5586.6  135.06  5645.4  140.93  5661.1  141.28  5674.2  142.76  5745.9  147.71
#Mann= 6 ,-1 , 0
  4575.6      .1       0  4858.4     .08       0  4879.9     .12       0
  4998.3     .07       0  5004.3     .12       0  5255.5      .1       0
Bank Sta=4958.7,5029.8
XS Rating Curve= 0 ,0
Exp/Cntr=0.3,0.1

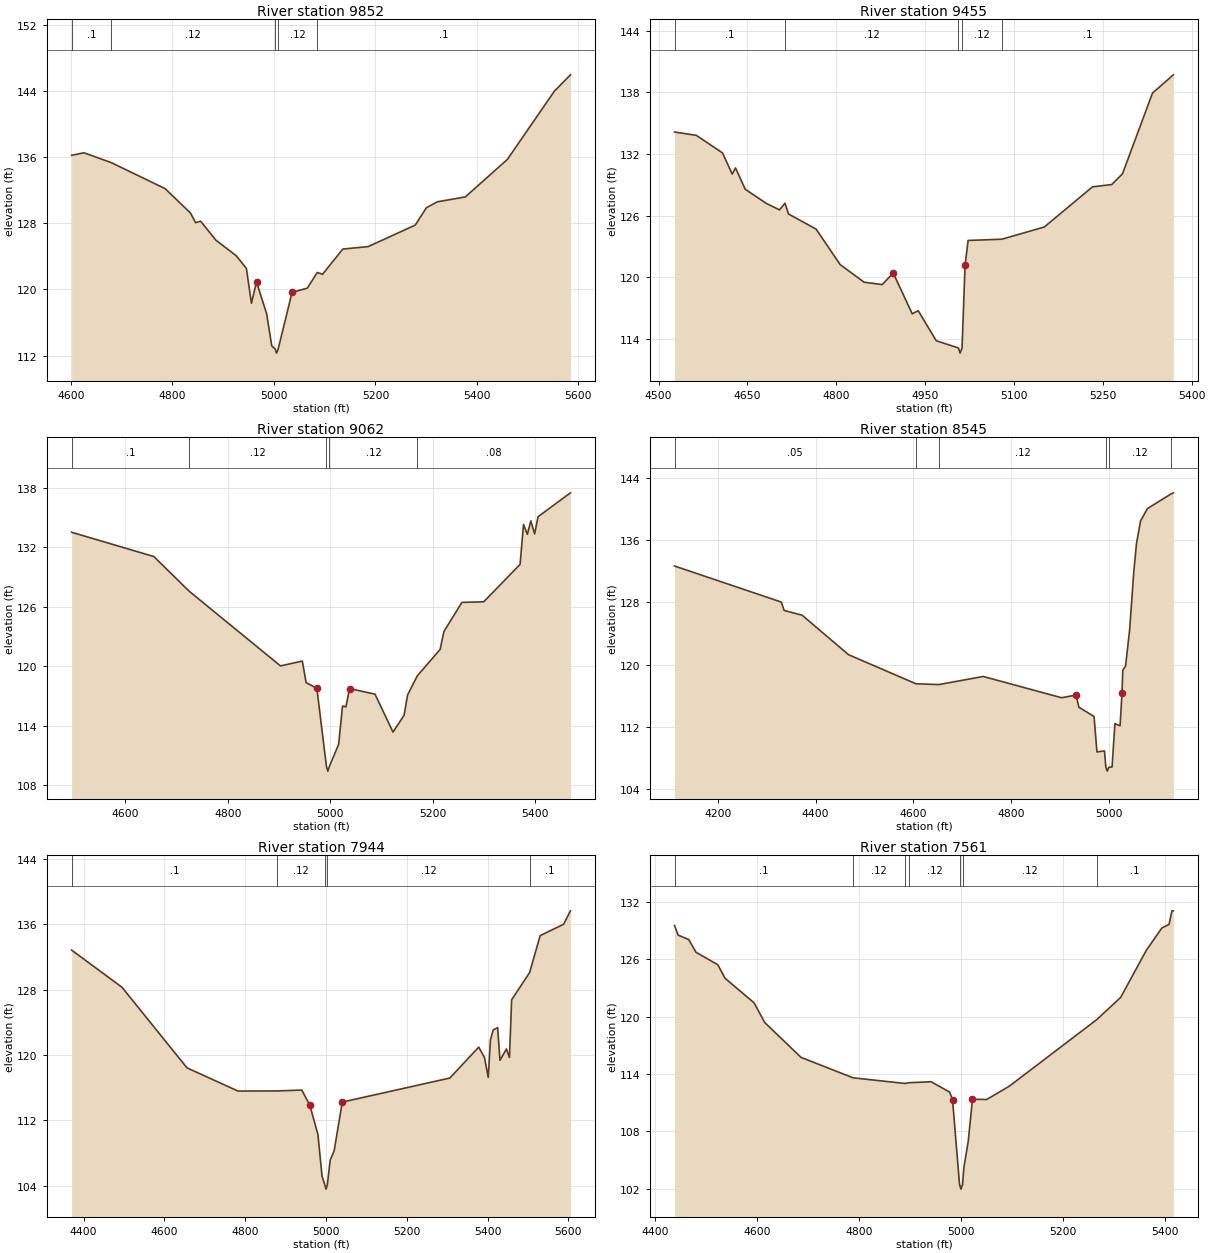
Type RM Length L Ch R = 1 ,9852    ,397,397,397
BEGIN DESCRIPTION:
HOBBS HOLLOW 19.0
END DESCRIPTION:
XS GIS Cut Line= 4
      2312944.11     13193341.11      2312948.45     13193119.73
      2312935.43     13192694.38      2313073.51     13192388.03
#Sta/Elev= 30
  4601.3  136.23  4625.6  136.54  4679.4  135.35  4785.6   132.2  4835.6  129.25
  4845.6  128.08  4855.6  128.26  4885.6  125.97  4925.6  124.09  4945.7  122.55
  4955.7  118.34  4965.7  120.92  4985.7  117.05  4995.7  113.18  5002.4   112.8
  5005.1   112.3  5008.4   112.8  5035.7  119.65  5065.7  120.16  5085.5  122.06
  5095.7  121.83  5135.7  124.89  5185.8  125.19  5278.5  127.79  5300.4  129.89
  5322.3  130.61  5377.2   131.2  5460.1  135.74  5552.6  143.99  5584.3  145.97
#Mann= 5 ,-1 , 0
  4601.3      .1       0  4679.4     .12       0  5002.4     .07       0
  5008.4     .12       0  5085.5      .1       0
Bank Sta=4965.7,5035.7
XS Rating Curve= 0 ,0
Exp/Cntr=0.3,0.1

Type RM Length L Ch R = 1 ,9455    ,393,393,393
BEGIN DESCRIPTION:
HOBBS HOLLOW 18.0
END DESCRIPTION:
XS GIS Cut Line= 3
      2313135.09     13193323.71      2313221.89     13193158.79
       2313330.4     13192512.09
#Sta/Elev= 30
    4527  134.14  4563.9  133.81    4608   132.1  4624.4  130.04    4630  130.64
  4646.4  128.56  4681.7  127.19  4704.3  126.55  4713.5   127.2  4719.4  126.15
    4766  124.68  4806.6  121.22  4847.1   119.5  4877.6  119.27  4896.2   120.4
  4928.3  116.42  4938.4  116.73  4968.8   113.8  5006.4  113.09  5009.1  112.59
  5012.4  113.09  5017.5  121.13  5022.6  123.57  5079.5  123.69  5151.3  124.88
  5232.5  128.79  5265.1  129.02  5283.2  130.06  5333.9  137.93  5369.1  139.71
#Mann= 5 ,-1 , 0
    4527      .1       0  4713.5     .12       0  5006.4     .07       0
  5012.4     .12       0  5079.5      .1       0
Bank Sta=4896.2,5017.5
XS Rating Curve= 0 ,0
Exp/Cntr=0.3,0.1

Type RM Length L Ch R = 1 ,9062    ,517,517,517
BEGIN DESCRIPTION:
HOBBS HOLLOW 17.0
END DESCRIPTION:
XS GIS Cut Line= 3
      2313208.87     13193414.87      2313412.86     13193219.56
      2313877.29     13192707.39
#Sta/Elev= 30
  4495.3  133.53  4655.8  131.08  4724.8  127.58  4903.1  120.04  4945.7  120.53
  4953.1  118.35  4974.1  117.78  4992.7  109.92  4995.5  109.42  4998.7  109.92
  5016.6  112.12  5024.1  115.98  5030.8  115.91  5037.9  117.75  5087.6  117.19
  5122.7  113.36  5144.4  115.06  5151.1   117.1  5170.3  119.05  5214.7   121.7
  5222.1  123.51  5257.2  126.45  5299.8  126.51  5370.8  130.29  5377.5  134.32
    5385  133.32  5391.7  134.68  5399.2  133.37  5405.9   135.1  5469.1  137.51
#Mann= 5 ,-1 , 0
  4495.3      .1       0  4724.8     .12       0  4992.7     .07       0
  4998.7     .12       0  5170.3     .08       0
Bank Sta=4974.1,5037.9
XS Rating Curve= 0 ,0
Exp/Cntr=0.3,0.1

Type RM Length L Ch R = 1 ,8545    ,601,601,601
BEGIN DESCRIPTION:
HOBBS HOLLOW 16.0
END DESCRIPTION:
XS GIS Cut Line= 3
      2313310.64     13193567.96      2314087.72     13193096.85
      2314137.71     13192996.88
#Sta/Elev= 30
  4111.2  132.67  4329.6  128.04  4335.5  126.96  4372.3  126.35  4467.3  121.28
  4605.2  117.55  4652.2  117.45  4742.7  118.49    4903  115.76  4932.7   116.1
  4938.5  114.54  4969.5  113.35  4975.4   108.8  4990.8  108.93  4993.7  106.84
  4996.4  106.34  4999.7  106.84  5006.3  106.87  5012.2  112.44  5022.7  112.16
 5026.67  116.31  5028.3  119.29  5033.9  119.82  5042.3  124.48  5050.7  131.86
  5056.3  135.56  5064.6  138.44  5078.6  140.03  5126.2  141.89  5131.7  142.06
#Mann= 6 ,-1 , 0
  4111.2     .05       0  4605.2      .1       0  4652.2     .12       0
  4993.7     .07       0  4999.7     .12       0  5126.2     .08       0
Bank Sta=4932.7,5026.67
XS Rating Curve= 0 ,0
Exp/Cntr=0.3,0.1

Type RM Length L Ch R = 1 ,7944    ,383,383,383
BEGIN DESCRIPTION:
HOBBS HOLLOW 15.0
END DESCRIPTION:
XS GIS Cut Line= 4
      2313514.86     13193751.68      2313985.38     13193536.41
      2314403.77     13193505.14      2314521.62     13193231.31
#Sta/Elev= 30
  4370.1  132.82  4494.8  128.28  4655.9  118.42    4782  115.59  4878.9   115.6
    4940  115.71  4960.1  113.85  4980.1  110.25  4990.1  105.19  4997.2   104.1
  4999.9   103.6  5003.2   104.1  5010.2  107.11  5020.2   108.3  5040.3  114.24
  5306.6  117.18  5378.1  120.96  5392.3   119.7  5401.7  117.26  5407.1  121.84
  5414.1  123.07    5425  123.34  5430.7  119.35  5446.7  120.73  5454.2  119.69
  5459.6  126.74  5504.2  130.08  5530.2  134.59  5588.3  135.98  5605.2  137.62
#Mann= 5 ,-1 , 0
  4370.1      .1       0  4878.9     .12       0  4997.2     .07       0
  5003.2     .12       0  5504.2      .1       0
Bank Sta=4960.1,5040.3
XS Rating Curve= 0 ,0
Exp/Cntr=0.3,0.1

Type RM Length L Ch R = 1 ,7561    ,368,368,368
BEGIN DESCRIPTION:
HOBBS HOLLOW 14.0
END DESCRIPTION:
XS GIS Cut Line= 3
      2314037.73     13194146.84      2314387.72     13193746.85
      2314587.72     13193346.86
#Sta/Elev= 30
  4437.5  129.55  4444.6  128.55  4465.5  128.08  4479.7  126.75  4522.4  125.45
  4536.7  124.03  4593.6  121.46  4614.5   119.4  4685.7  115.75  4787.9  113.61
  4889.7  113.02  4898.1   113.1    4941   113.2  4977.4  112.11    4983  111.31
  4996.7  102.46  4999.5  101.96  5002.7  102.46  5005.3  104.26  5013.7  106.93
  5022.1  111.37    5050  111.34  5094.8  112.75  5265.6  119.69  5312.8  122.02
  5363.1  126.95  5393.8   129.3  5407.8  129.67  5413.4  131.09  5416.2  131.09
#Mann= 7 ,-1 , 0
  4437.5      .1       0  4787.9     .12       0  4889.7      .1       0
  4898.1     .12       0  4996.7     .07       0  5002.7     .12       0
  5265.6      .1       0
Bank Sta=4983,5022.1
XS Rating Curve= 0 ,0
Exp/Cntr=0.3,0.1