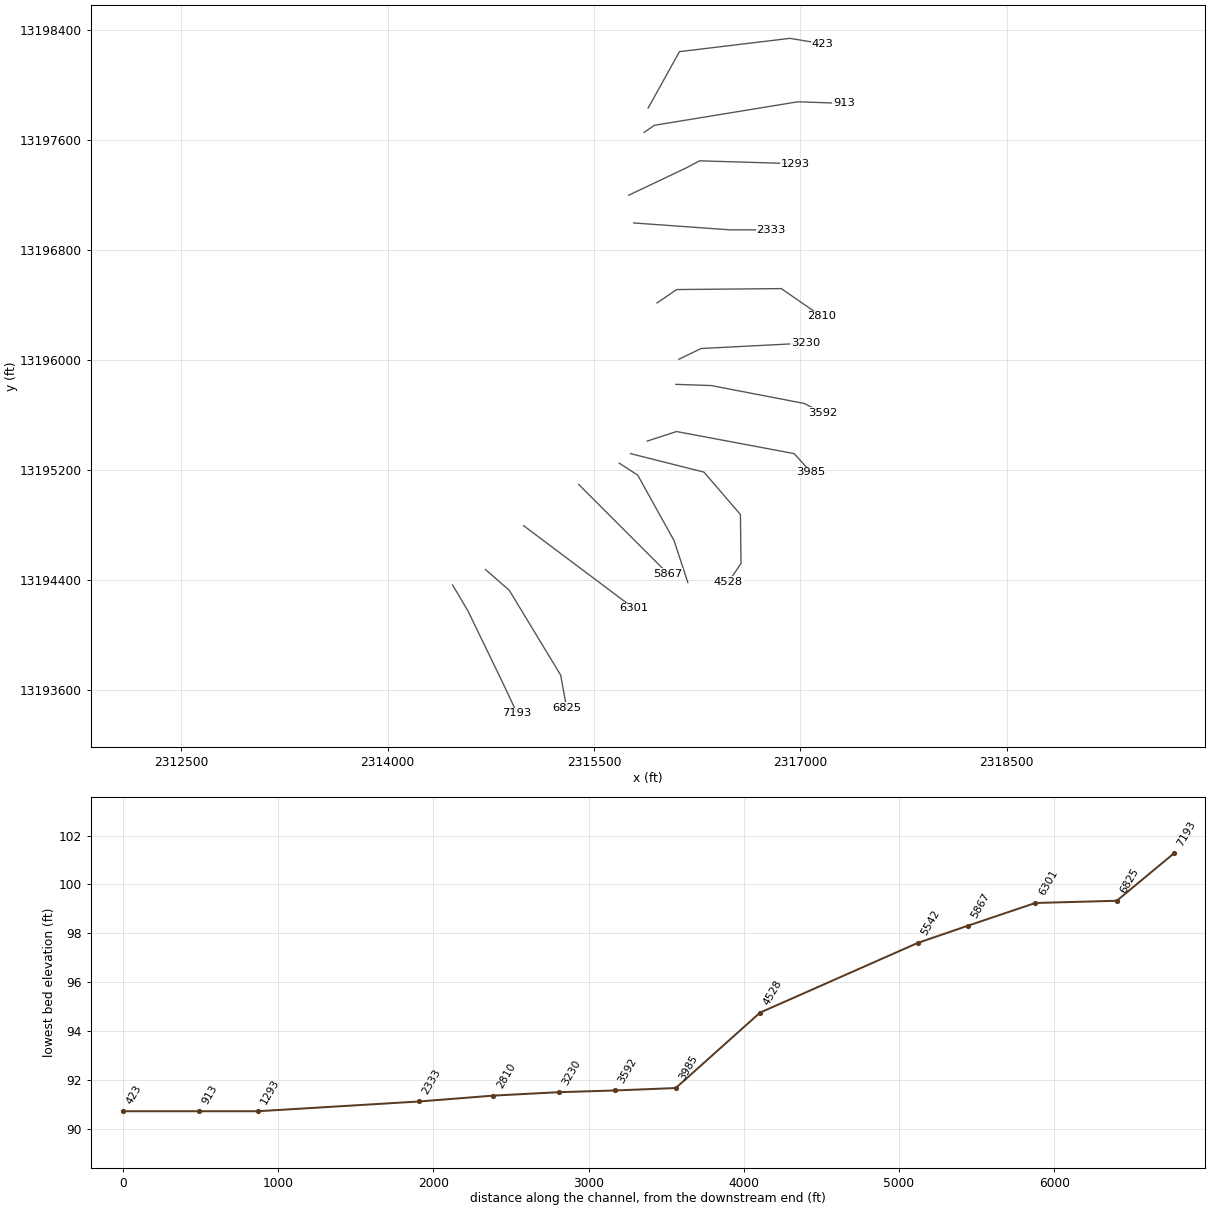
HEC-RAS study HOBBS HOLLOW.prj: HOBBS HOLLOW Base Level Engineering

--- HOBBS HOLLOW.g01 (geometry) --- (continued)

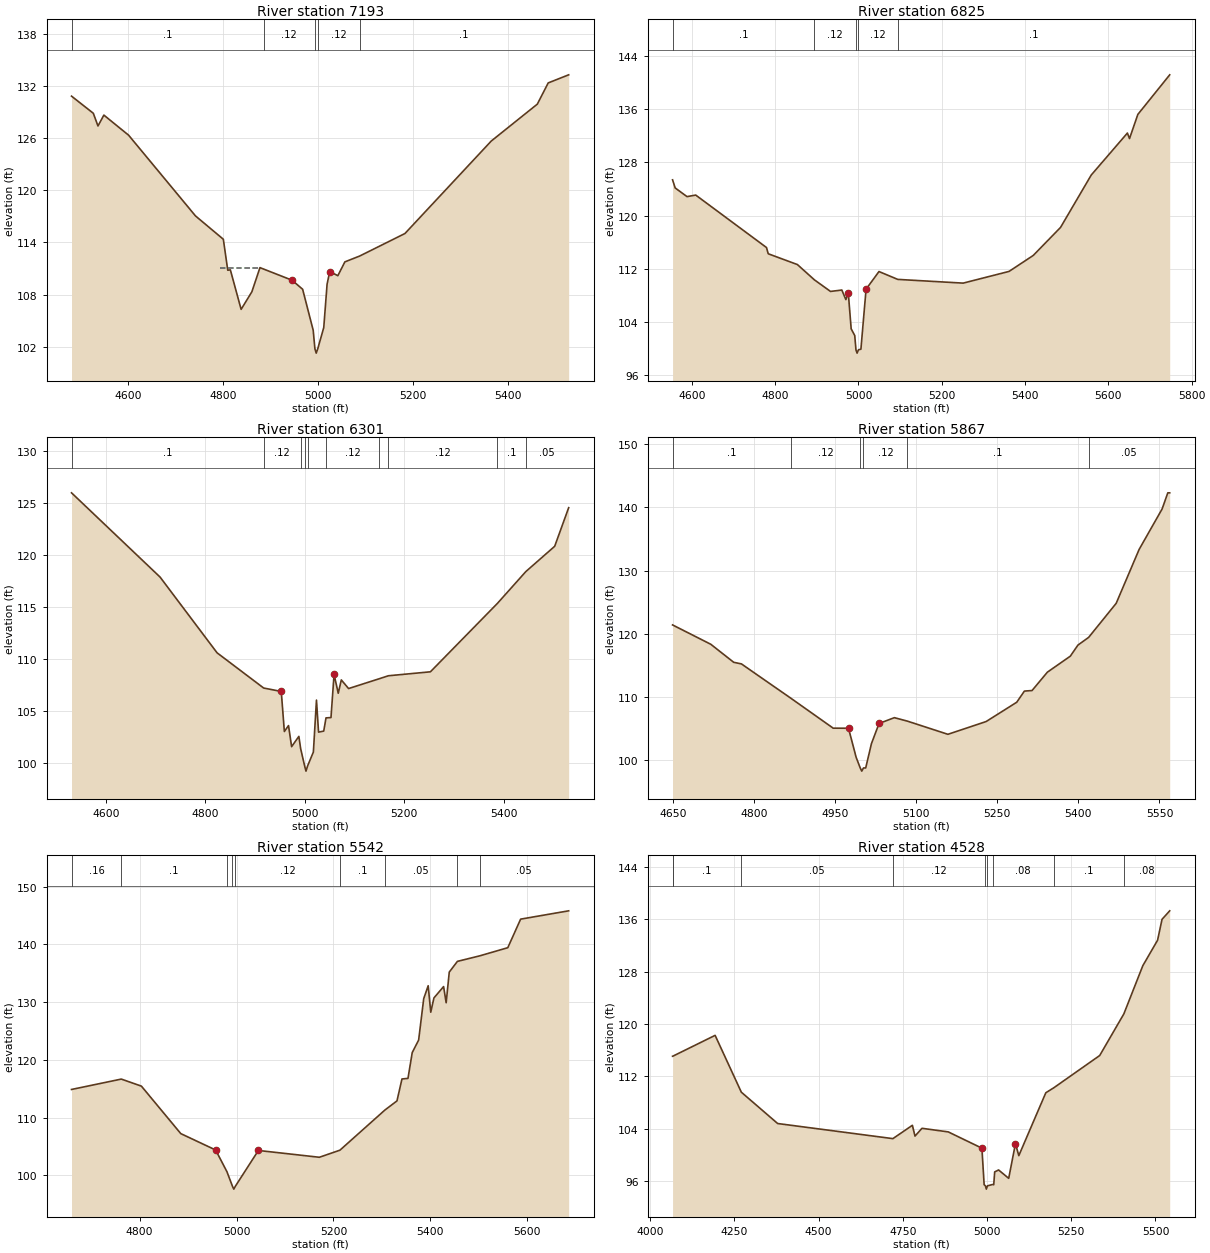
Type RM Length L Ch R = 1 ,7193    ,368,368,368
BEGIN DESCRIPTION:
HOBBS HOLLOW 13.0
END DESCRIPTION:
XS GIS Cut Line= 4
      2314471.87     13194365.42      2314584.74     13194174.42
      2314845.16     13193636.23      2314940.65     13193432.22
#Sta/Elev= 30
  4481.9  130.81  4527.7  128.84  4537.5  127.38  4549.9  128.63  4601.9  126.32
  4742.5  117.04    4801  114.36  4810.3   110.8  4815.8  110.84  4838.4   106.3
    4861  108.32    4878   111.1  4885.8  110.93  4945.5  109.65  4967.7  108.61
  4989.9   103.9  4993.5  101.77  4996.3  101.27  4999.5  101.77  5012.1  104.21
  5019.1   109.2  5024.7  110.65  5041.7  110.17  5056.5  111.76  5087.6  112.43
  5182.8  115.02  5364.2  125.65    5461  129.89  5483.9  132.33  5526.9  133.26
#Mann= 5 ,-1 , 0
  4481.9      .1       0  4885.8     .12       0  4993.5     .07       0
  4999.5     .12       0  5087.6      .1       0
#XS Ineff= 1 ,-1
 4794.17  4877.5  111.08
Permanent Ineff=
       T
Bank Sta=4945.5,5024.7
XS Rating Curve= 0 ,0
Exp/Cntr=0.3,0.1

Type RM Length L Ch R = 1 ,6825    ,524,524,524
BEGIN DESCRIPTION:
HOBBS HOLLOW 12.0
END DESCRIPTION:
XS GIS Cut Line= 4
       2314710.6     13194478.25      2314884.22     13194326.33
      2315257.48     13193710.01      2315300.84     13193471.56
#Sta/Elev= 30
  4553.7  125.37    4560  124.15  4588.4  122.85  4609.3  123.08  4779.2   115.2
  4783.4  114.26  4853.4  112.64  4894.1  110.35  4932.9   108.6  4960.1  108.81
  4969.8  107.37  4975.6  108.39  4982.5  102.99  4991.1  101.97    4994   99.83
  4996.7   99.33    5000   99.83  5005.9   99.92  5018.3  108.94  5049.3  111.59
  5094.3  110.41  5251.4  109.85  5361.6  111.61  5419.7  114.01  5485.2  118.22
    5559   126.1  5645.7   132.4  5650.8  131.57  5670.8   135.2  5747.3  141.15
#Mann= 5 ,-1 , 0
  4553.7      .1       0  4894.1     .12       0    4994     .07       0
    5000     .12       0  5094.3      .1       0
Bank Sta=4975.6,5018.3
XS Rating Curve= 0 ,0
Exp/Cntr=0.3,0.1

Type RM Length L Ch R = 1 ,6301    ,434,434,434
BEGIN DESCRIPTION:
HOBBS HOLLOW 11.0
END DESCRIPTION:
XS GIS Cut Line= 3
      2314987.72     13194796.85      2315387.72     13194496.85
      2315787.72     13194196.85
#Sta/Elev= 30
  4530.7     126  4708.8   117.9  4823.4  110.62  4917.2  107.23  4952.6   106.9
  4958.8  103.05  4967.2  103.62  4973.4  101.59    4988  102.58  4991.6   101.4
  4999.6   99.74  5002.3   99.24  5005.6   99.74  5017.2  101.08  5023.4  106.07
  5027.6  102.99    5038  103.09  5042.6  104.36  5052.6  104.39  5058.8  108.54
  5067.2  106.73  5073.4  108.01    5088  107.18  5150.1  108.13  5168.1  108.41
  5252.6  108.79  5387.4  115.37  5444.6  118.43  5502.6  120.86  5530.7  124.57
#Mann= 10 ,-1 , 0
  4530.7      .1       0  4917.2     .12       0  4991.6     .16       0
  4999.6     .07       0  5005.6     .16       0  5042.6     .12       0
  5150.1     .16       0  5168.1     .12       0  5387.4      .1       0
  5444.6     .05       0
Bank Sta=4952.6,5058.8
XS Rating Curve= 0 ,0
Exp/Cntr=0.3,0.1

Type RM Length L Ch R = 1 ,5867    ,325,325,325
BEGIN DESCRIPTION:
HOBBS HOLLOW 10.0
END DESCRIPTION:
XS GIS Cut Line= 3
      2315387.73     13195096.85      2315637.72     13194846.85
       2316037.7     13194446.87
#Sta/Elev= 30
  4649.7  121.42  4720.4  118.36  4762.8  115.51    4777  115.26  4867.8  109.87
  4946.7   105.1    4975  105.09  4989.1   100.5  4996.7   98.81  4999.5   98.31
  5002.7   98.81  5006.8   98.81  5017.4  102.65  5031.5  105.84  5059.8  106.76
    5084  106.21  5158.8  104.13  5229.5  106.15  5286.1   109.2  5300.2  110.96
  5314.4  111.05  5342.7  113.95  5385.1  116.48  5399.2  118.23    5419  119.45
  5469.9  124.83  5512.4  133.36  5554.8  139.74  5565.4   142.3  5568.9   142.3
#Mann= 6 ,-1 , 0
  4649.7      .1       0  4867.8     .12       0  4996.7     .07       0
  5002.7     .12       0    5084      .1       0    5419     .05       0
Bank Sta=4975,5031.5
XS Rating Curve= 0 ,0
Exp/Cntr=0.3,0.1

Type RM Length L Ch R = 1 ,5542    ,1014,1014,1014
BEGIN DESCRIPTION:
HOBBS HOLLOW 9.0
END DESCRIPTION:
XS GIS Cut Line= 4
      2315682.81     13195250.82      2315817.38       13195164.
      2316082.13     13194686.57      2316181.97     13194382.73
#Sta/Elev= 30
  4659.4  114.87  4762.1  116.67  4803.6  115.45  4884.9  107.22  4956.8  104.38
  4980.1  100.62  4991.5    98.1  4994.3    97.6  4997.5    98.1    5045   104.3
  5170.8  103.12  5213.3  104.35    5306   111.3    5331  112.89  5341.3  116.69
  5353.7  116.79  5362.5  121.27  5375.7  123.43  5386.2  130.62  5395.4  132.85
  5400.7  128.26  5407.3  130.74  5427.2   132.7  5432.5   129.9  5438.9  135.21
  5455.7  137.07  5501.9  138.03  5559.7  139.44  5586.2  144.39  5685.3  145.83
#Mann= 9 ,-1 , 0
  4659.4     .16       0  4762.1      .1       0  4980.1     .12       0
  4991.5     .07       0  4997.5     .12       0  5213.3      .1       0
    5306     .05       0  5455.7     .08       0  5501.9     .05       0
Bank Sta=4956.8,5045
XS Rating Curve= 0 ,0
Exp/Cntr=0.3,0.1

Type RM Length L Ch R = 1 ,4528    ,543,543,543
BEGIN DESCRIPTION:
Mapping XS 50203ca4
END DESCRIPTION:
XS GIS Cut Line= 5
      2315765.26     13195320.26      2316299.15      13195185.7
      2316563.91     13194877.54      2316568.25     13194521.64
       2316477.1     13194387.09
#Sta/Elev= 30
  4066.9  115.06  4067.1  115.06  4193.2  118.26    4271  109.57  4378.8  104.78
  4720.7  102.47  4778.6  104.51  4786.3  102.86  4807.1  104.05    4885   103.5
  4984.9  101.01  4991.5   95.44  4995.3   95.25    4998   94.75  5001.3   95.25
  5016.5   95.46    5020   95.42  5022.8   97.38  5034.4   97.68  5064.4    96.4
  5084.4   101.7  5094.4   99.87  5174.5  109.48  5198.9  110.27  5334.5  115.18
  5406.1  121.54  5462.4  128.91  5506.2  132.81  5519.4     136  5542.2   137.3
#Mann= 9 ,-1 , 0
  4066.9     .16       0  4067.1      .1       0    4271     .05       0
  4720.7     .12       0  4995.3     .07       0  5001.3     .12       0
  5016.5     .08       0  5198.9      .1       0  5406.1     .08       0
Bank Sta=4984.9,5084.4
XS Rating Curve= 0 ,0
Exp/Cntr=0.3,0.1

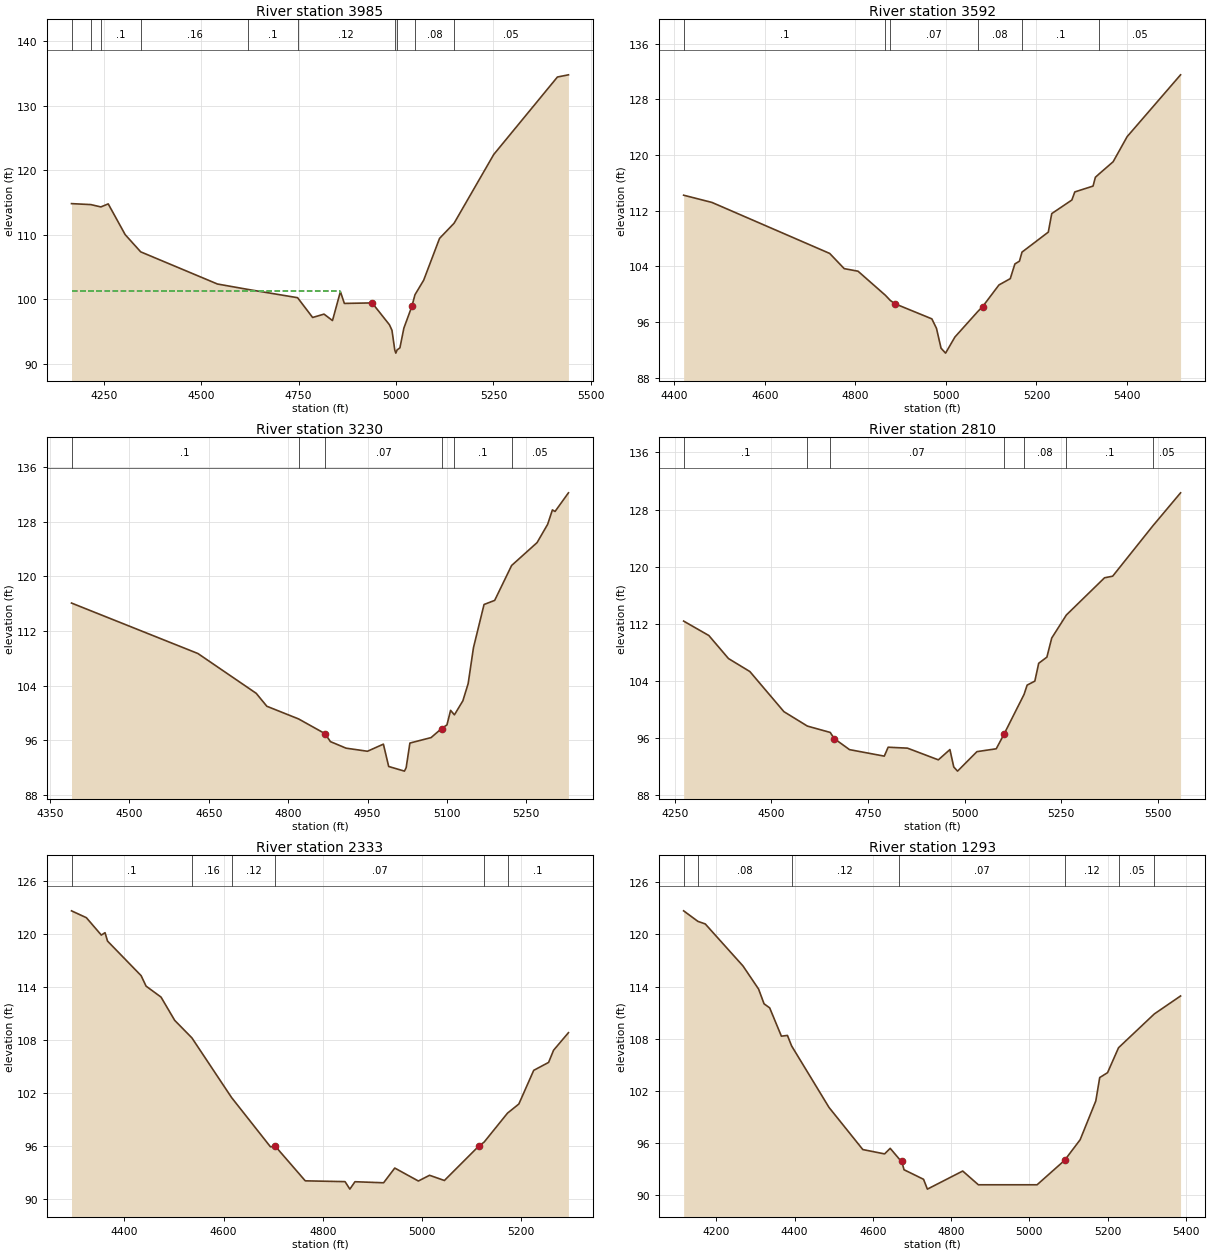
Type RM Length L Ch R = 1 ,3985    ,393,393,393
BEGIN DESCRIPTION:
HOBBS HOLLOW 8.0
END DESCRIPTION:
XS GIS Cut Line= 4
      2315886.84      13195411.4       2316099.5     13195480.84
      2316954.53     13195320.25      2317076.06     13195185.71
#Sta/Elev= 30
  4167.5  114.85  4217.1   114.7  4242.8  114.34  4261.7  114.81  4305.2  110.04
    4345  107.37    4542  102.38  4621.2  101.53  4747.5  100.26  4786.2   97.19
  4815.4   97.71  4837.1   96.71  4857.4   101.2  4867.6   99.37  4938.8   99.45
  4983.1   96.07  4989.7   95.21  4996.9   92.16  4999.6   91.66  5002.9   92.16
  5010.1   92.48  5020.2   95.53  5040.8   98.92  5048.7  100.71  5071.1  102.98
  5111.8  109.46  5149.1  111.81  5250.8  122.47  5414.2  134.49  5442.5  134.83
#Mann= 10 ,-1 , 0
  4167.5      .1       0  4217.1     .16       0  4242.8      .1       0
    4345     .16       0  4621.2      .1       0  4747.5     .12       0
  4996.9     .07       0  5002.9     .12       0  5048.7     .08       0
  5149.1     .05       0
#XS Ineff= 2 , 0
       0 4856.67  101.23               0
Permanent Ineff=
       T       F
Bank Sta=4938.8,5040.8
XS Rating Curve= 0 ,0
Exp/Cntr=0.3,0.1

Type RM Length L Ch R = 1 ,3592    ,362,362,362
BEGIN DESCRIPTION:
HOBBS HOLLOW 7.0
END DESCRIPTION:
XS GIS Cut Line= 4
      2316095.15     13195823.73      2316351.23     13195815.04
      2317028.32     13195684.84      2317162.83     13195615.41
#Sta/Elev= 30
    4421  114.23  4483.6  113.19  4743.5  105.87  4775.5  103.69    4806  103.32
  4866.5   99.86  4877.3   99.12  4887.5   98.65    4969   96.48  4979.2   95.12
  4989.3   92.27  4999.3   91.56  5019.9   93.87  5070.8   97.56    5081   98.23
  5117.2  101.35  5142.1  102.25  5152.3  104.36  5162.4  104.76    5168  106.06
  5226.1  108.93  5233.7  111.59  5278.1  113.54  5284.6   114.7  5324.9  115.54
    5330   116.8  5338.7  117.31  5369.2  119.03  5400.2  122.64  5518.1  131.51
#Mann= 6 ,-1 , 0
    4421      .1       0  4866.5     .12       0  4877.3     .07       0
  5070.8     .08       0    5168      .1       0  5338.7     .05       0
Bank Sta=4887.5,5081
XS Rating Curve= 0 ,0
Exp/Cntr=0.3,0.1

Type RM Length L Ch R = 1 ,3230    ,420,420,420
BEGIN DESCRIPTION:
HOBBS HOLLOW 6.0
END DESCRIPTION:
XS GIS Cut Line= 3
      2316116.87     13196006.02      2316277.45     13196084.14
      2317036.97      13196123.2
#Sta/Elev= 30
  4390.6   116.1  4629.5  108.71  4739.7  102.88  4759.7  100.99  4819.8   99.13
  4869.8   96.97  4879.9   95.81  4909.5   94.85  4949.9    94.4    4980   95.44
    4990   92.17  5019.8   91.49    5023   91.99  5030.1    95.6  5070.1    96.4
  5090.1   97.73  5100.1   98.26    5107  100.39  5114.2   99.73  5130.2  101.79
  5140.2  104.31  5150.2  109.56  5170.2  115.89  5190.3  116.49  5222.3   121.6
  5270.4  124.95  5290.4  127.63  5299.4  129.74  5304.4  129.51  5329.7  132.24
#Mann= 6 ,-1 , 0
  4390.6      .1       0  4819.8     .12       0  4869.8     .07       0
  5090.1     .08       0  5114.2      .1       0  5222.3     .05       0
Bank Sta=4869.8,5090.1
XS Rating Curve= 0 ,0
Exp/Cntr=0.3,0.1

Type RM Length L Ch R = 1 ,2810    ,477,477,477
BEGIN DESCRIPTION:
HOBBS HOLLOW 5.0
END DESCRIPTION:
XS GIS Cut Line= 4
      2315957.98     13196415.54      2316100.36     13196512.78
      2316860.78     13196519.72      2317152.44     13196318.34
#Sta/Elev= 30
  4272.4  112.37  4337.7  110.35  4388.6  107.12    4444   105.3  4532.2   99.68
    4593   97.66  4652.2   96.77  4662.2   95.92  4702.2   94.36  4792.2   93.45
  4802.2    94.7  4852.2   94.57  4932.2   92.93  4962.2   94.37  4972.2   91.93
    4982   91.35  5032.2   94.08  5082.2   94.48  5102.2   96.51  5154.3   102.1
  5162.2   103.4  5182.2  103.96  5192.2  106.46  5213.4  107.32  5225.9  109.99
  5263.8  113.22  5362.8  118.44  5383.8  118.66  5487.7   125.7  5559.7  130.34
#Mann= 7 ,-1 , 0
  4272.4      .1       0    4593     .16       0  4652.2     .07       0
  5102.2     .12       0  5154.3     .08       0  5263.8      .1       0
  5487.7     .05       0
Bank Sta=4662.2,5102.2
XS Rating Curve= 0 ,0
Exp/Cntr=0.3,0.1

Type RM Length L Ch R = 1 ,2333    ,1040,1040,1040
BEGIN DESCRIPTION:
HOBBS HOLLOW 4.0
END DESCRIPTION:
XS GIS Cut Line= 3
      2315787.76     13196996.85      2316487.72     13196946.85
      2316787.68     13196946.85
#Sta/Elev= 30
  4293.3  122.67  4323.3  121.89  4353.4  119.92  4360.9  120.19  4365.9  119.24
  4433.6  115.32  4443.6  114.13  4473.7  112.89  4501.3  110.25    4536  108.26
  4615.9   101.5  4694.3   95.91  4704.3   95.96  4764.5   92.05  4844.7   91.96
  4854.4   91.11  4864.7   91.95  4922.4   91.83  4944.9    93.5  4992.5   92.03
    5015   92.68    5045   92.09    5115   96.03    5125   96.44  5172.2   99.73
    5195  100.76    5225  104.58    5255  105.48    5265  106.86    5295  108.85
#Mann= 6 ,-1 , 0
  4293.3      .1       0    4536     .16       0  4615.9     .12       0
  4704.3     .07       0    5125     .12       0  5172.2      .1       0
Bank Sta=4704.3,5115
XS Rating Curve= 0 ,0
Exp/Cntr=0.3,0.1

Type RM Length L Ch R = 1 ,1293    ,380,380,380
BEGIN DESCRIPTION:
HOBBS HOLLOW 3.0
END DESCRIPTION:
XS GIS Cut Line= 4
       2315752.1     13197198.46      2316168.74     13197396.37
       2316267.7     13197448.45      2316964.21     13197427.66
#Sta/Elev= 30
  4116.4  122.71  4152.8   121.5  4171.7   121.2  4268.1  116.37    4308  113.71
  4321.9  112.02  4336.3  111.55  4366.2   108.3  4381.7  108.38  4392.3  107.18
    4488   100.1  4574.3   95.26  4629.9   94.76  4644.3    95.4  4666.9    94.2
  4673.9   93.89  4679.6   92.94  4729.5   91.84  4739.3   90.71  4829.6   92.79
  4869.6   91.21  5019.6   91.21  5089.7   94.01  5129.7   96.39  5169.7  100.85
  5179.7  103.54  5199.7   104.1  5227.8  106.97  5319.1  110.85  5386.3  112.92
#Mann= 7 ,-1 , 0
  4116.4      .1       0  4152.8     .08       0  4392.3     .12       0
  4666.9     .07       0  5089.7     .12       0  5227.8     .05       0
  5319.1      .1       0
Bank Sta=4673.9,5089.7
XS Rating Curve= 0 ,0
Exp/Cntr=0.3,0.1

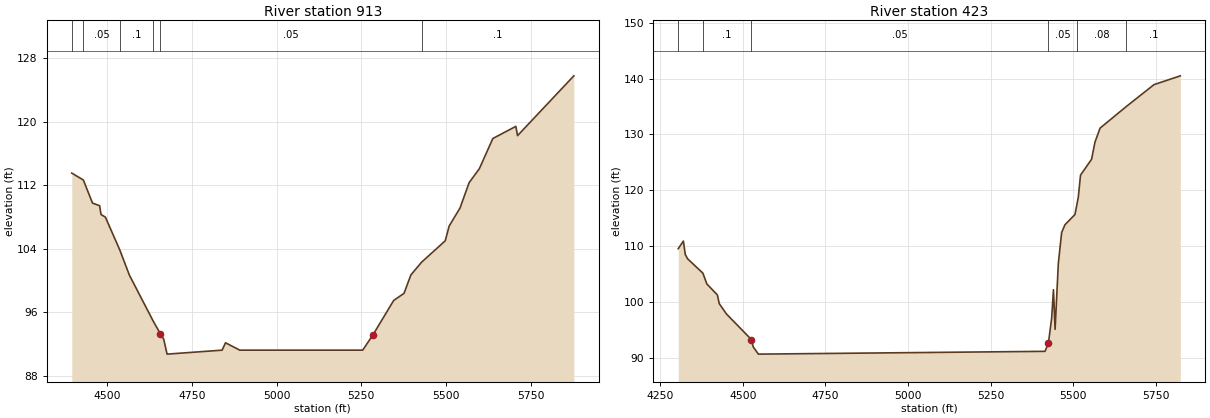
Type RM Length L Ch R = 1 ,913     ,490,490,490
BEGIN DESCRIPTION:
HOBBS HOLLOW 2.0
END DESCRIPTION:
XS GIS Cut Line= 4
      2315864.63     13197655.45      2315938.67     13197706.71
      2316980.76     13197877.54      2317316.71     13197866.16
#Sta/Elev= 30
  4395.1  113.53  4429.3  112.66  4456.3  109.75  4477.3  109.42  4481.5  108.31
  4494.3  107.98  4536.8  103.85  4565.3  100.66  4635.8   94.85  4656.5   93.29
  4666.6   92.59  4676.5   90.71  4838.9   91.21    4849   92.14  4891.2   91.21
    5254   91.21  5284.7   93.17  5345.5   97.48  5375.9   98.37  5396.2  100.69
  5427.6  102.29  5497.5  104.99  5509.4  106.87  5541.2  109.12  5568.1  112.32
  5598.2  114.07  5638.2  117.89  5706.1  119.42  5711.1  118.25  5877.3  125.79
#Mann= 6 ,-1 , 0
  4395.1      .1       0  4429.3     .05       0  4536.8      .1       0
  4635.8     .12       0  4656.5     .05       0  5427.6      .1       0
Bank Sta=4656.5,5284.7
XS Rating Curve= 0 ,0
Exp/Cntr=0.3,0.1

Type RM Length L Ch R = 1 ,423     ,0,0,0
BEGIN DESCRIPTION:
HOBBS HOLLOW 1.0
END DESCRIPTION:
XS GIS Cut Line= 4
      2315893.11     13197831.97       2316120.9     13198241.99
      2316923.81     13198338.79      2317162.84     13198298.96
#Sta/Elev= 30
  4304.5  109.56  4320.1  110.93  4325.8  108.53    4333  107.75  4379.2  105.19
    4391  103.27    4423   101.3  4428.7   99.74  4450.5   97.89    4526   93.32
  4531.7   91.98  4547.4   90.71    5415   91.21  5425.1   92.64  5435.1   97.11
  5440.5  102.23  5445.5   95.14  5455.3  106.93  5465.3  112.45  5475.4  113.85
  5505.6  115.67  5512.8  117.86  5515.7  118.74  5522.5  122.73    5556  125.56
  5566.1   128.6  5581.7  131.13  5661.1  134.99  5744.8   138.9  5824.6  140.48
#Mann= 6 ,-1 , 0
  4304.5     .05       0  4379.2      .1       0    4526     .05       0
  5425.1     .05       0  5512.8     .08       0  5661.1      .1       0
Bank Sta=4526,5425.1
XS Rating Curve= 0 ,0
Exp/Cntr=0.3,0.1

Chan Stop Cuts=-1
Use User Specified Reach Order=0
Composite Channel Slope=5

--- HOBBS HOLLOW.g02 (geometry) ---

Geom Title=Delete
Program Version=4.10

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
River Reach=HOBBS HOLLOW    ,Reach-1

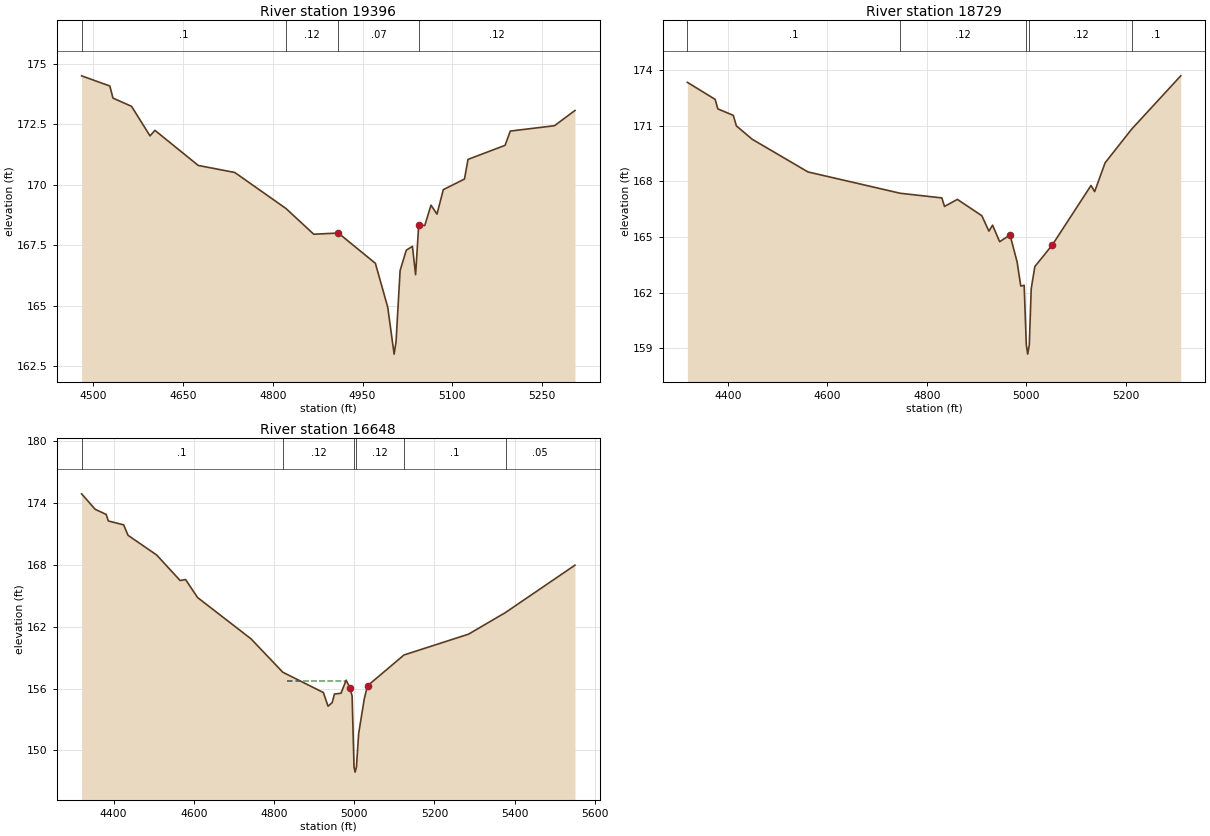
Type RM Length L Ch R = 1 ,19396   ,255,255,255
BEGIN DESCRIPTION:
HOBBS HOLLOW 39.0
END DESCRIPTION:
XS GIS Cut Line= 4
      2308332.24     13187214.71      2308479.82     13187266.79
      2308722.87     13187310.19      2309130.88     13187206.02
#Sta/Elev= 30
  4480.4   174.5  4527.6  174.08  4532.9  173.58  4563.9  173.24  4594.8  172.02
  4602.9  172.25  4675.4   170.8  4736.4  170.51  4822.1  169.02  4868.4  167.96
  4909.4  168.01  4971.4  166.76    4992  164.95  5002.7  163.01  5005.9  163.51
  5012.7  166.46    5023   167.3  5033.3  167.46  5038.6  166.29  5043.8  168.34
  5053.9  168.32  5064.3  169.16  5074.3  168.79  5084.9   169.8  5120.3  170.24
  5126.2  171.05  5188.1  171.63  5196.9  172.22  5270.7  172.44  5304.9  173.07
#Mann= 4 ,-1 , 0
  4480.4      .1       0  4822.1     .12       0  4909.4     .07       0
  5043.8     .12       0
Bank Sta=4909.4,5043.8
XS Rating Curve= 0 ,0
Exp/Cntr=0.3,0.1

Type RM Length L Ch R = 1 ,18729   ,670,670,670
BEGIN DESCRIPTION:
Mapping XS 2cdf5fff
END DESCRIPTION:
XS GIS Cut Line= 3
      2308444.59     13187981.87      2308975.82     13187796.98
      2309267.51     13187481.85
#Sta/Elev= 30
  4318.7  173.33  4374.6  172.41  4379.9   171.9    4411  171.55  4417.3  170.98
  4449.1  170.26  4561.2   168.5  4746.7  167.35  4830.3   167.1  4835.7  166.64
  4861.5  167.02  4910.7  166.14  4924.9  165.31  4932.3  165.63  4946.5  164.74
  4967.4   165.1  4981.6  163.65    4989  162.35  4995.8  162.39  5000.1  159.18
  5002.9  158.68  5006.1  159.18    5010  162.21  5017.3   163.4  5052.5  164.57
  5130.2  167.77  5137.5  167.44  5158.5  168.99  5211.7   170.8  5310.6  173.68
#Mann= 5 ,-1 , 0
  4318.7      .1       0  4746.7     .12       0  5000.1     .07       0
  5006.1     .12       0  5211.7      .1       0
Bank Sta=4967.4,5052.5
XS Rating Curve= 0 ,0
Exp/Cntr=0.3,0.1

Type RM Length L Ch R = 1 ,16648   ,426,426,426
BEGIN DESCRIPTION:
HOBBS HOLLOW 34.0
END DESCRIPTION:
XS GIS Cut Line= 3
      2308974.64      13189445.6      2309287.11     13189376.17
      2310092.56     13188951.79
#Sta/Elev= 30
  4320.1  174.88    4354  173.38  4381.5  172.88  4386.7  172.25  4425.1  171.87
  4435.9  170.86  4507.6  168.94  4565.9  166.47  4579.4  166.57  4609.5  164.82
  4742.6  160.82  4821.9  157.58  4923.1  155.61  4934.8  154.28  4945.1  154.63
  4950.7  155.46  4967.1  155.54    4980  156.81  4989.2  156.07  4994.8  155.27
  4999.6  148.39  5002.3  147.89  5005.6  148.39  5011.2  151.65  5025.2  155.01
  5033.2  156.26  5124.1  159.25  5285.2  161.27  5377.4  163.37  5550.6  167.96
#Mann= 6 ,-1 , 0
  4320.1      .1       0  4821.9     .12       0  4999.6     .07       0
  5005.6     .12       0  5124.1      .1       0  5377.4     .05       0
#XS Ineff= 1 ,-1
 4831.94 4978.75  156.73
Permanent Ineff=
       T
Bank Sta=4989.2,5033.2
XS Rating Curve= 0 ,0
Exp/Cntr=0.3,0.1