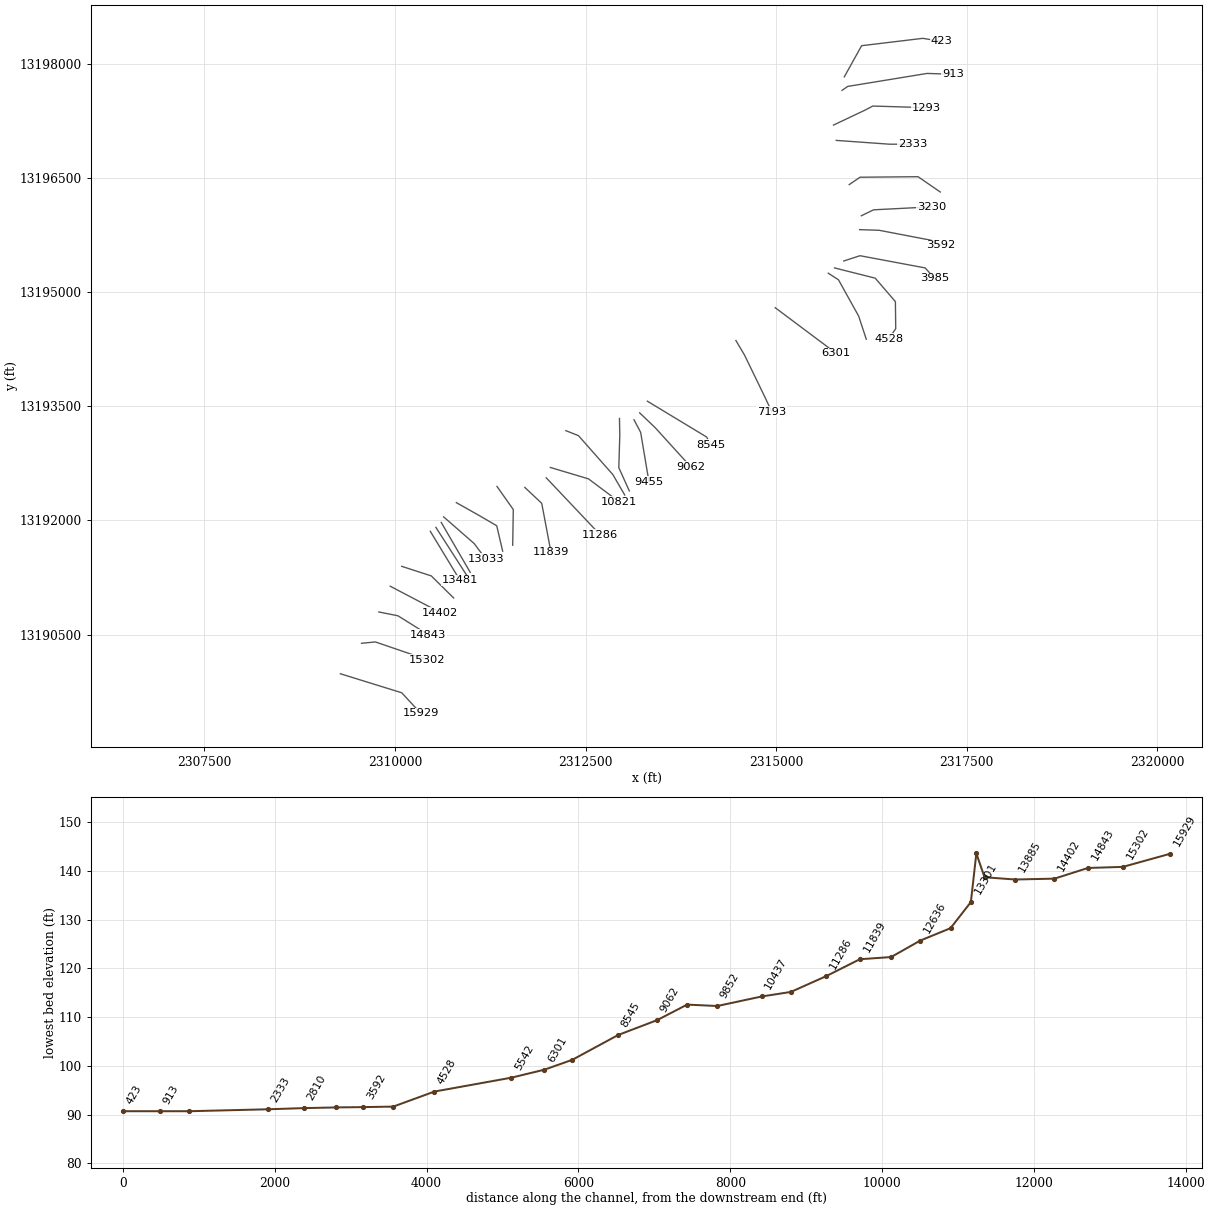
HEC-RAS study HOBBS HOLLOW.prj: HOBBS HOLLOW Base Level Engineering

--- HOBBS HOLLOW.g02 (geometry) --- (continued)

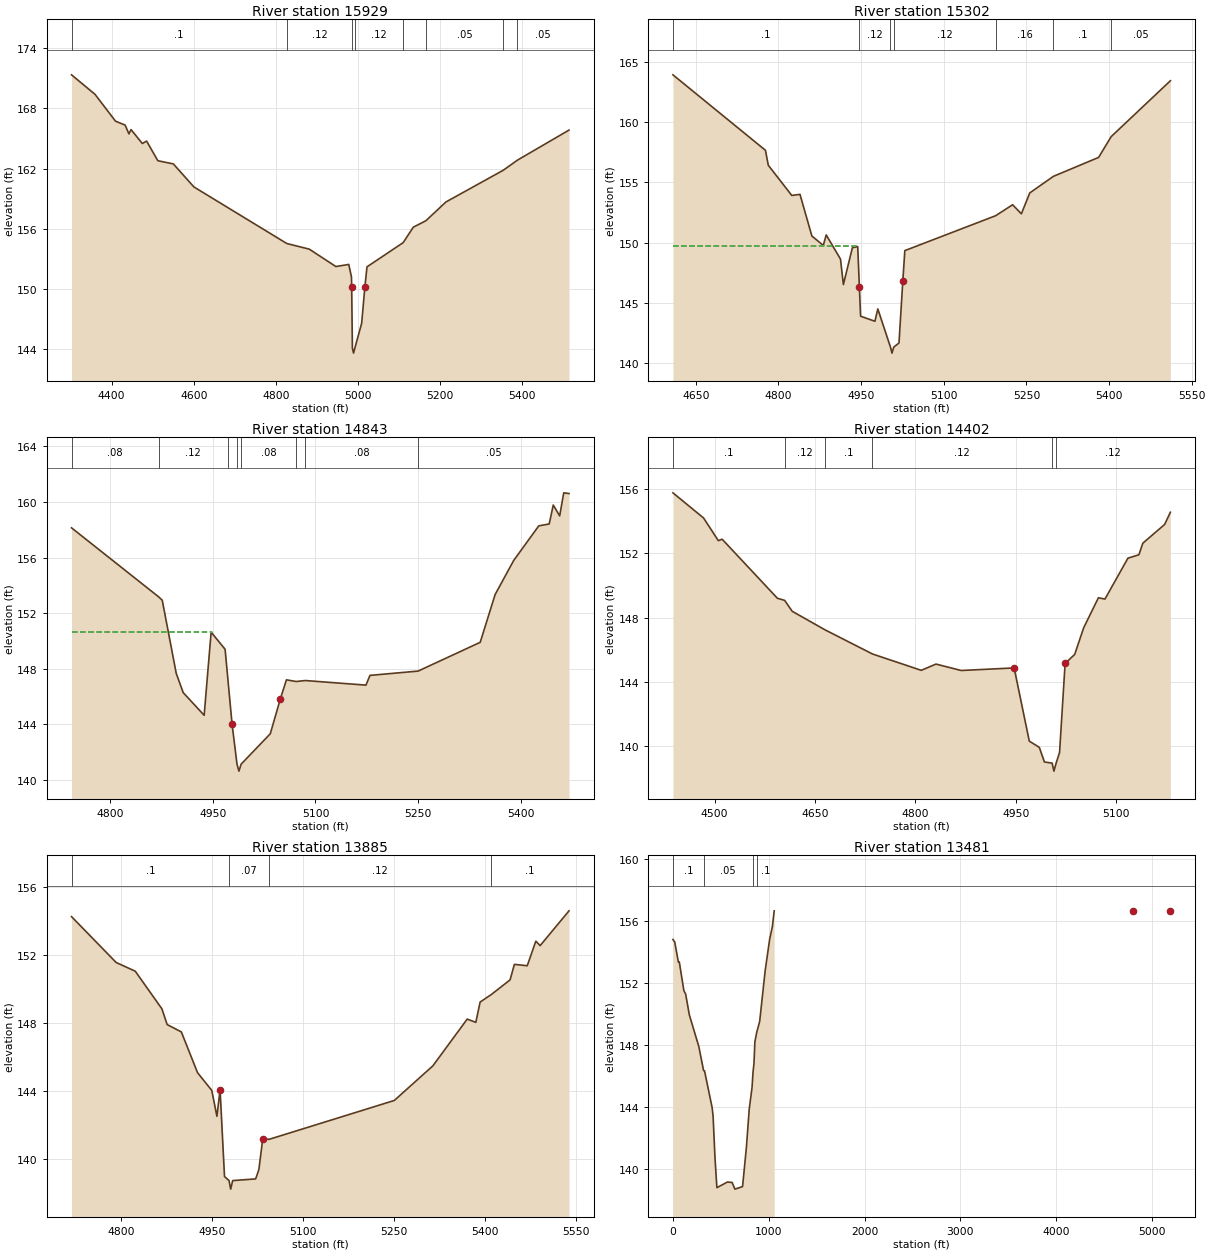
Type RM Length L Ch R = 1 ,15929   ,627,627,627
BEGIN DESCRIPTION:
HOBBS HOLLOW 32.0
END DESCRIPTION:
XS GIS Cut Line= 3
      2309283.11     13189984.48       2310087.8     13189734.48
      2310337.79     13189463.66
#Sta/Elev= 30
  4302.5  171.36  4359.7  169.41  4409.6  166.73    4433  166.34  4442.2  165.46
  4447.4  165.89  4474.8   164.5  4485.3  164.74  4512.6  162.78  4550.4  162.46
  4600.5  160.16  4826.6  154.51  4881.2  153.95  4946.1  152.21  4977.5  152.42
  4984.1  151.15 4984.58  150.18  4986.3  144.06  4989.1  143.56  4992.3  144.06
  5008.9  146.55  5016.7  150.17  5021.9  152.18    5110   154.6  5134.6  156.14
  5165.1  156.78  5214.1  158.66  5353.7  161.83  5388.3  162.84  5513.7  165.84
#Mann= 8 ,-1 , 0
  4302.5      .1       0  4826.6     .12       0  4986.3     .07       0
  4992.3     .12       0    5110      .1       0  5165.1     .05       0
  5353.7      .1       0  5388.3     .05       0
Bank Sta=4984.58,5016.7
XS Rating Curve= 0 ,0
Exp/Cntr=0.3,0.1

Type RM Length L Ch R = 1 ,15302   ,459,459,459
BEGIN DESCRIPTION:
HOBBS HOLLOW 31.0
END DESCRIPTION:
XS GIS Cut Line= 3
      2309560.57     13190385.43      2309742.85     13190402.79
      2310423.51     13190168.67
#Sta/Elev= 30
  4608.5   163.9  4776.4  157.65  4781.6  156.41  4824.2  153.91  4839.1     154
  4860.7  150.55  4881.4  149.77  4886.7  150.64  4912.6  148.64  4917.9  146.53
  4934.2  149.58  4943.9  149.67  4946.9  146.35  4949.1  143.91  4975.1  143.49
  4980.4  144.51  5003.3  141.35  5006.1  140.85  5009.3  141.35  5018.8  141.69
 5025.69  146.79  5029.4  149.34  5194.2  152.23    5225  153.14  5240.9  152.39
  5256.2  154.12    5299  155.49  5381.1  157.06  5403.9  158.78  5511.4  163.41
#Mann= 7 ,-1 , 0
  4608.5      .1       0  4946.9     .12       0  5003.3     .07       0
  5009.3     .12       0  5194.2     .16       0    5299      .1       0
  5403.9     .05       0
#XS Ineff= 2 , 0
       0 4943.75  149.73               0
Permanent Ineff=
       T       F
Bank Sta=4946.9,5025.69
XS Rating Curve= 0 ,0
Exp/Cntr=0.3,0.1

Type RM Length L Ch R = 1 ,14843   ,441,441,441
BEGIN DESCRIPTION:
HOBBS HOLLOW 30.0
END DESCRIPTION:
XS GIS Cut Line= 3
      2309787.77     13190796.85      2310037.72     13190746.85
      2310437.72     13190496.86
#Sta/Elev= 30
  4743.7  158.14    4871  153.17  4876.2  152.93  4896.6  147.67  4906.8  146.28
  4937.4  144.65  4947.6  150.63    4968   149.4  4971.7  147.44  4978.2     144
  4985.4  141.13  4988.2  140.63  4991.4  141.13    5034  143.32  5048.7  145.83
  5057.6   147.2  5071.8  147.08    5085  147.15  5173.7  146.82  5179.6  147.52
  5249.9  147.83  5340.6   149.9  5362.4  153.34  5389.5  155.79  5426.1  158.28
  5441.4  158.42  5447.3  159.78  5456.7     159  5462.6  160.66  5470.3  160.61
#Mann= 8 ,-1 , 0
  4743.7     .08       0    4871     .12       0  4971.7     .08       0
  4985.4     .07       0  4991.4     .08       0  5071.8     .12       0
    5085     .08       0  5249.9     .05       0
#XS Ineff= 2 , 0
       0 4948.33  150.62               0
Permanent Ineff=
       T       F
Bank Sta=4978.2,5048.7
XS Rating Curve= 0 ,0
Exp/Cntr=0.3,0.1

Type RM Length L Ch R = 1 ,14402   ,517,517,517
BEGIN DESCRIPTION:
HOBBS HOLLOW 29.0
END DESCRIPTION:
XS GIS Cut Line= 2
      2309936.72     13191135.54       2310594.2     13190789.91
#Sta/Elev= 30
  4437.9  155.78  4483.7  154.21  4505.7   152.8  4511.4  152.89  4593.9  149.21
  4604.7  149.08    4616   148.4  4664.7  147.25  4735.8  145.74  4808.7  144.72
  4830.7  145.11  4868.3  144.71  4947.4  144.87    4970  140.31    4985  139.92
  4992.6  139.01  5004.1  138.94  5006.8  138.44  5010.1  138.94  5015.2   139.6
  5023.5  145.15  5037.8  145.71  5051.2  147.37  5073.2  149.24    5083  149.16
  5117.3  151.71  5133.7  151.92  5139.5  152.64  5172.1  153.81  5180.7  154.57
#Mann= 6 ,-1 , 0
  4437.9      .1       0  4604.7     .12       0  4664.7      .1       0
  4735.8     .12       0  5004.1     .07       0  5010.1     .12       0
Bank Sta=4947.4,5023.5
XS Rating Curve= 0 ,0
Exp/Cntr=0.3,0.1

Type RM Length L Ch R = 1 ,13885   ,404,404,404
BEGIN DESCRIPTION:
HOBBS HOLLOW 28.0
END DESCRIPTION:
XS GIS Cut Line= 3
      2310087.75     13191396.85      2310475.82     13191270.94
       2310768.8     13190980.55
#Sta/Elev= 30
  4718.5  154.24  4792.1  151.55  4823.6  151.04  4867.6  148.83  4876.2  147.91
  4899.6  147.48  4926.3  145.09  4949.8  144.05  4958.3  142.53  4963.5  144.09
  4970.8     139  4978.3  138.76    4981  138.26  4984.3  138.76  5022.2  138.86
  5027.5  139.41  5033.9  141.22  5044.4  141.18  5250.9  143.46  5314.5  145.49
  5371.1  148.23  5385.3  148.04  5392.4  149.23  5410.8  149.67  5441.8  150.53
  5448.9  151.44  5470.1  151.36  5484.3   152.8  5491.4  152.54    5539  154.58
#Mann= 4 ,-1 , 0
  4718.5      .1       0  4978.3     .07       0  5044.4     .12       0
  5410.8      .1       0
Bank Sta=4963.5,5033.9
XS Rating Curve= 0 ,0
Exp/Cntr=0.3,0.1

Type RM Length L Ch R = 1 ,13481   ,108,108,108
BEGIN DESCRIPTION:
HOBBS HOLLOW 27.0
END DESCRIPTION:
XS GIS Cut Line= 2
      2310462.75     13191856.94      2310852.82     13191212.03
#Sta/Elev= 30
       0 154.82919.01493154.663257.04479 153.36866.55225153.3796114.0896151.5336
133.1045151.3022171.1344149.9706270.3303147.9203319.9282146.3736329.8478146.3529
409.2045143.9831419.1241143.4294438.9633140.7401458.8024138.8167567.9179139.1797
617.5159139.1543647.2746138.7234726.6313138.8858766.3097141.3904796.0684143.8754
825.8272145.2926835.7468146.2697845.6664 146.822 855.586148.2395875.4252148.8626
905.1839 149.537962.6729152.82291009.735154.85711037.973155.66381056.797  156.68
#Mann= 4 ,-1 , 0
       0      .1       0319.9282     .05       0835.7468     .12       0
875.4252      .1       0
Bank Sta=4799.6,5191.5
XS Rating Curve= 0 ,0
Exp/Cntr=0.3,0.1

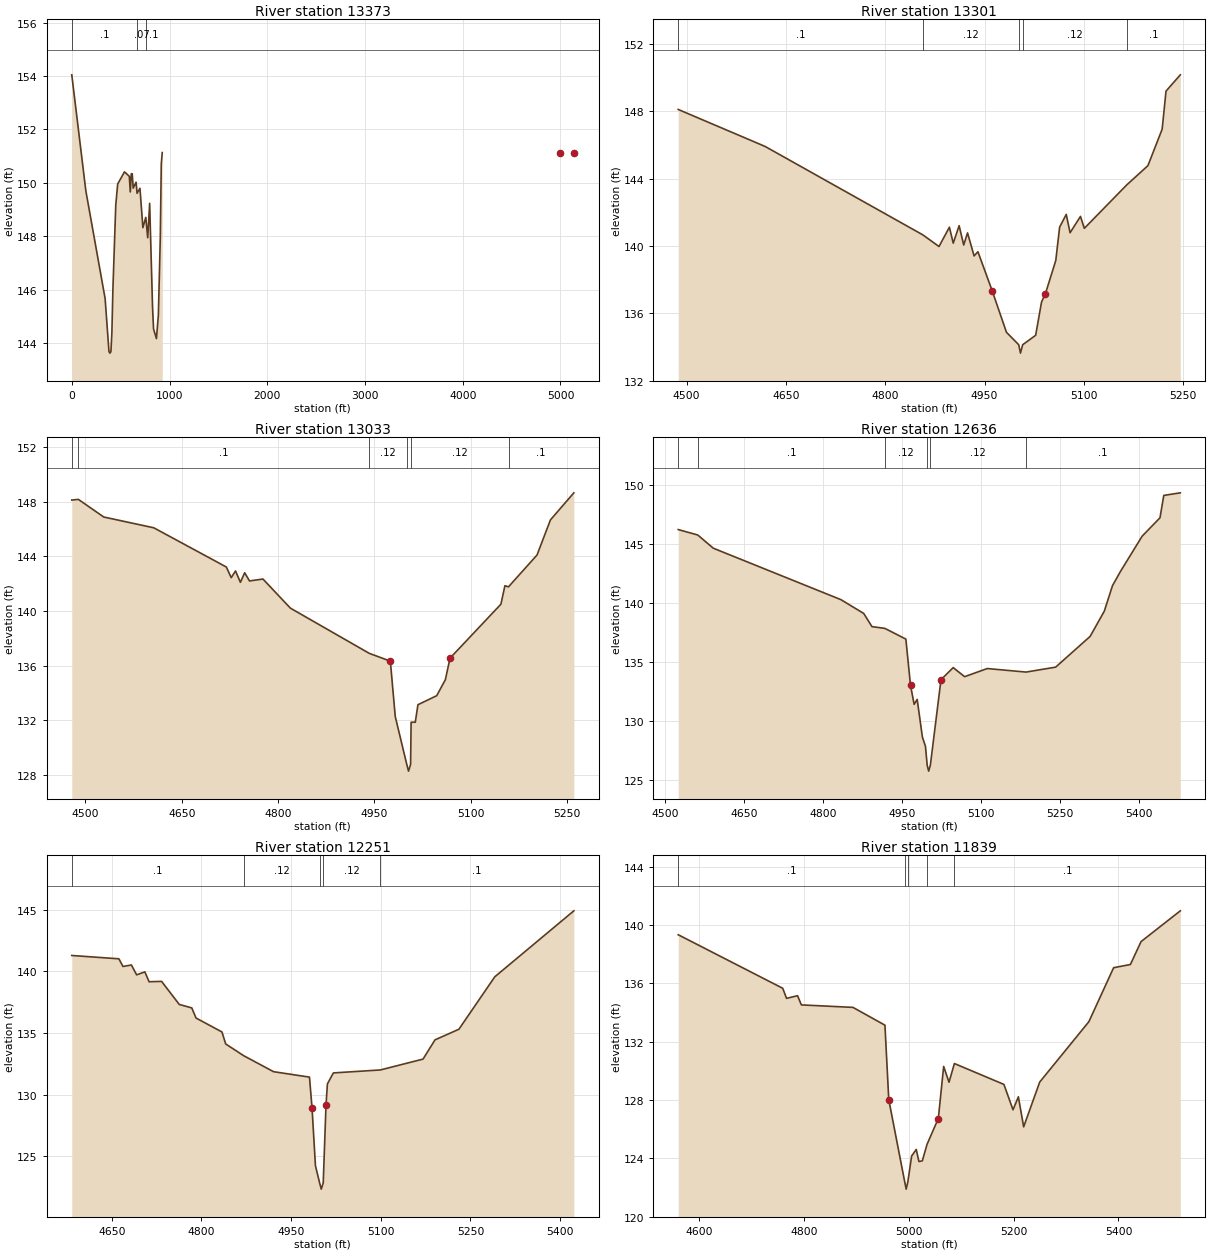
Type RM Length L Ch R = 1 ,13373   ,72,72,72
BEGIN DESCRIPTION:
Mapping XS f2c6afef
END DESCRIPTION:
XS GIS Cut Line= 2
      2310535.72     13191908.95      2310941.98     13191276.13
#Sta/Elev= 30
       0154.0461143.9141149.7017341.1206145.6639380.7497143.6706 390.657143.6164
400.5642143.6707410.4715144.3985420.3788145.9579450.1006149.1642469.9152149.9538
539.2661150.4101588.8024 150.242598.7097 149.658 608.617150.3364618.5243150.3404
628.4316   149.8658.1534150.0209668.0607149.6058697.7825149.7921727.5043148.3191
757.2261148.7046777.0406147.9413796.8552  149.23 826.577145.3276836.4843144.5283
866.2062144.1612886.0207 145.036905.8353147.9595915.7426150.7049925.6498151.1319
#Mann= 3 ,-1 , 0
       0      .1       0668.0607     .07       0757.2261      .1       0
Bank Sta=4991.5,5136.8
XS Rating Curve= 0 ,0
Exp/Cntr=0.3,0.1

Type RM Length L Ch R = 1 ,13301   ,268,268,268
BEGIN DESCRIPTION:
Mapping XS 2bba420b
END DESCRIPTION:
XS GIS Cut Line= 2
      2310606.05     13191974.03      2310986.24     13191317.81
#Sta/Elev= 30
  4487.3  148.12  4618.6  145.92  4856.9  140.66  4881.2  139.97  4896.9  141.12
  4902.7  140.17  4911.6  141.21  4918.5  140.06  4924.3  140.78  4934.2  139.41
    4940  139.66  4961.5  137.34  4983.1  134.87  5001.6  134.13  5004.3  133.63
  5007.6  134.13  5027.2  134.69  5036.1  136.67  5041.9  137.16  5057.6  139.14
  5063.4  141.12  5073.4  141.88  5079.2  140.79  5094.9  141.76  5100.7  141.05
  5164.7  143.63  5196.8  144.78  5218.3  146.95  5224.1  149.21  5245.7  150.18
#Mann= 5 ,-1 , 0
  4487.3      .1       0  4856.9     .12       0  5001.6     .07       0
  5007.6     .12       0  5164.7      .1       0
Bank Sta=4961.5,5041.9
XS Rating Curve= 0 ,0
Exp/Cntr=0.3,0.1

Type RM Length L Ch R = 1 ,13033   ,397,397,397
BEGIN DESCRIPTION:
HOBBS HOLLOW 26.0
END DESCRIPTION:
XS GIS Cut Line= 3
      2310637.71     13192046.87      2311037.72     13191696.85
       2311187.7     13191496.88
#Sta/Elev= 30
  4478.9  148.11  4489.2  148.16  4528.7  146.87  4606.6  146.08  4719.5  143.21
  4727.1  142.43  4733.8  142.92  4741.4  142.09    4748  142.79  4755.6  142.19
  4776.5  142.33  4819.2   140.2    4942  136.89  4974.8  136.32  4982.4  132.27
  5000.3  128.77  5003.1  128.27  5006.3  128.77  5007.1  131.85  5013.6  131.85
  5017.7  133.13  5046.9  133.79  5060.4  134.96  5067.7  136.54  5146.9  140.49
  5153.1  141.84  5158.7  141.76  5203.1  144.09    5224  146.66  5260.4  148.64
#Mann= 6 ,-1 , 0
  4478.9     .08       0  4489.2      .1       0    4942     .12       0
  5000.3     .07       0  5006.3     .12       0  5158.7      .1       0
Bank Sta=4974.8,5067.7
XS Rating Curve= 0 ,0
Exp/Cntr=0.3,0.1

Type RM Length L Ch R = 1 ,12636   ,385,385,385
BEGIN DESCRIPTION:
HOBBS HOLLOW 25.0
END DESCRIPTION:
XS GIS Cut Line= 4
      2310804.38      13192234.3      2311103.84     13192065.04
      2311333.87      13191930.5        2311412.     13191596.28
#Sta/Elev= 30
  4525.2  146.25  4562.3  145.79  4591.7  144.67  4834.2   140.3  4877.5  139.13
  4893.2  138.01  4917.7  137.86  4957.6  136.95  4966.4  133.03  4973.3  131.41
  4979.1  131.83    4989  128.63  4994.8  127.85  4998.1  126.24  5000.9  125.74
  5004.1  126.24  5024.3   133.5  5047.5  134.53  5069.2  133.76  5112.2  134.45
  5185.9  134.15  5242.1  134.57  5307.6  137.18  5334.5  139.32  5350.1  141.49
  5365.3   142.7  5406.4  145.69  5440.3  147.25  5447.5  149.15  5478.9  149.37
#Mann= 6 ,-1 , 0
  4525.2     .08       0  4562.3      .1       0  4917.7     .12       0
  4998.1     .07       0  5004.1     .12       0  5185.9      .1       0
Bank Sta=4966.4,5024.3
XS Rating Curve= 0 ,0
Exp/Cntr=0.3,0.1

Type RM Length L Ch R = 1 ,12251   ,412,412,412
BEGIN DESCRIPTION:
HOBBS HOLLOW 24.0
END DESCRIPTION:
XS GIS Cut Line= 3
       2311337.7     13192446.88      2311551.34     13192143.34
      2311543.53     13191674.59
#Sta/Elev= 30
    4583  141.29  4661.9  141.02  4668.6   140.4  4682.8  140.52  4691.5  139.72
  4705.3  139.96  4712.4  139.16  4733.3  139.19  4762.9  137.32  4783.8  137.04
  4790.9  136.22  4834.3  135.09  4840.5  134.12  4870.5  133.17  4920.6  131.87
  4980.7  131.43    4985  128.93  4990.7  124.24  4997.7  122.85  5000.4  122.35
  5003.7  122.85 5008.33  129.13  5010.7  130.88  5020.7  131.77  5099.2  132.01
  5170.7  132.89  5190.7  134.45  5230.7  135.31  5290.7  139.56    5423  144.91
#Mann= 5 ,-1 , 0
    4583      .1       0  4870.5     .12       0  4997.7     .07       0
  5003.7     .12       0  5099.2      .1       0
Bank Sta=4985,5008.33
XS Rating Curve= 0 ,0
Exp/Cntr=0.3,0.1

Type RM Length L Ch R = 1 ,11839   ,443,443,443
BEGIN DESCRIPTION:
HOBBS HOLLOW 23.0
END DESCRIPTION:
XS GIS Cut Line= 3
       2311702.8     13192433.96      2311924.15     13192225.63
      2312045.67     13191583.29
#Sta/Elev= 30
  4560.3  139.34  4759.6  135.67  4766.9  134.98  4787.9  135.16  4795.2  134.53
  4893.6  134.36  4954.6  133.14  4961.9  128.03  4992.3   122.4  4995.1   121.9
  4998.3   122.4  5005.5  124.17  5014.3  124.62  5019.4  123.79  5025.9  123.84
  5034.9  124.97  5056.4  126.74  5066.6  130.31  5076.8  129.23  5087.1  130.51
  5181.5  129.08  5198.9  127.34  5209.1  128.23  5219.2  126.17  5249.8  129.24
  5343.6  133.38  5390.8  137.08  5422.8   137.3  5443.1  138.87    5518  140.98
#Mann= 5 ,-1 , 0
  4560.3      .1       0  4992.3     .07       0  4998.3      .1       0
  5034.9     .12       0  5087.1      .1       0
#XS Ineff= 1 ,-1
  5087.5 5323.33  130.46
Permanent Ineff=
       T
Bank Sta=4961.9,5056.4
XS Rating Curve= 0 ,0
Exp/Cntr=0.3,0.1

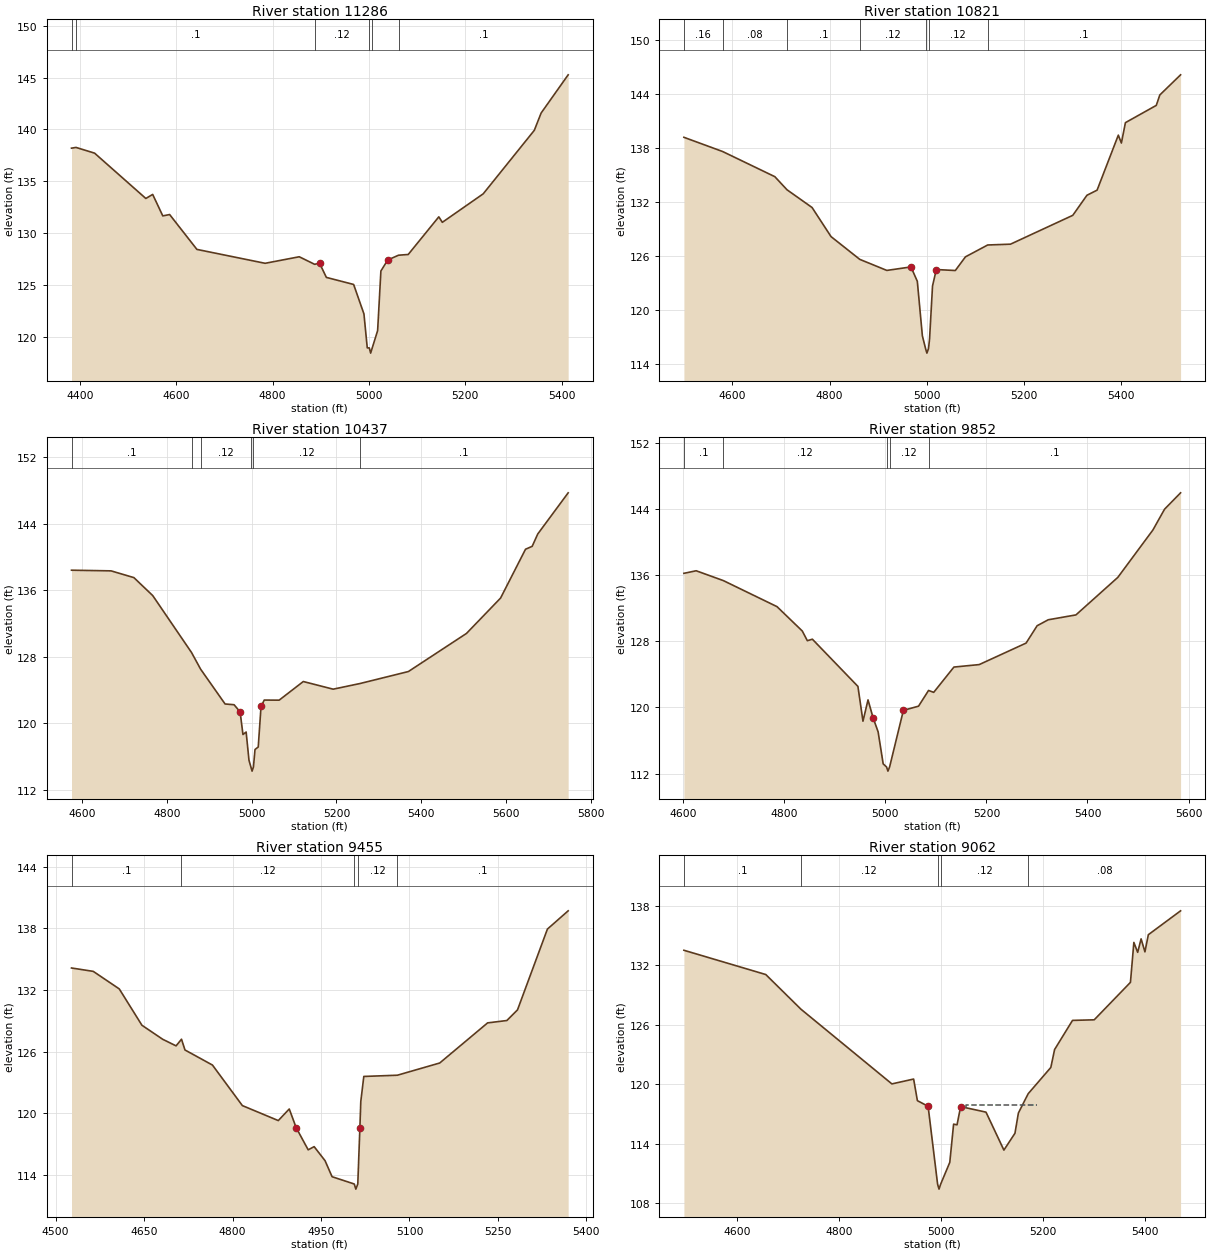
Type RM Length L Ch R = 1 ,11286   ,465,465,465
BEGIN DESCRIPTION:
HOBBS HOLLOW 22.0
END DESCRIPTION:
XS GIS Cut Line= 2
       2311983.6     13192560.73      2312691.44     13191811.25
#Sta/Elev= 30
  4382.6  138.19    4392  138.26  4430.5  137.71  4536.9  133.34  4551.1  133.73
  4572.1  131.66  4586.3  131.79  4642.9  128.43  4784.5  127.09  4855.3  127.72
  4887.4  126.99  4897.4  127.11  4911.6  125.73  4968.2  125.05  4989.6  122.21
  4996.5  118.94  5000.8  118.93  5003.5  118.43  5006.8  118.93    5018   120.6
  5024.8  126.35    5039  127.41  5061.4  127.87  5081.5  127.94    5145  131.57
  5152.3  131.04  5237.2  133.79  5343.2  139.91  5357.4  141.58  5413.5  145.26
#Mann= 6 ,-1 , 0
  4382.6     .08       0    4392      .1       0  4887.4     .12       0
  5000.8     .07       0  5006.8     .12       0  5061.4      .1       0
Bank Sta=4897.4,5039
XS Rating Curve= 0 ,0
Exp/Cntr=0.3,0.1

Type RM Length L Ch R = 1 ,10821   ,384,384,384
BEGIN DESCRIPTION:
HOBBS HOLLOW 21.0
END DESCRIPTION:
XS GIS Cut Line= 3
      2312037.69     13192696.86      2312537.72     13192546.85
      2312937.68     13192246.88
#Sta/Elev= 30
  4500.3   139.2  4579.9  137.62  4687.4  134.82  4712.5  133.36    4764  131.39
  4803.1  128.15  4862.2  125.62  4917.9  124.39  4967.5  124.78  4980.6  123.18
    4991  117.11  4997.6  115.69  5000.3  115.19  5003.6  115.69  5005.8  116.77
  5011.9  122.67  5019.7  124.49  5058.8  124.38  5079.6   125.9  5125.4  127.22
  5172.3  127.31  5300.5  130.52  5329.6  132.75  5350.5  133.32  5394.2  139.44
  5400.5  138.56  5408.8  140.83  5472.3  142.75  5479.6  143.91  5522.3  146.15
#Mann= 7 ,-1 , 0
  4500.3     .16       0  4579.9     .08       0  4712.5      .1       0
  4862.2     .12       0  4997.6     .07       0  5003.6     .12       0
  5125.4      .1       0
Bank Sta=4967.5,5019.7
XS Rating Curve= 0 ,0
Exp/Cntr=0.3,0.1

Type RM Length L Ch R = 1 ,10437   ,585,585,585
BEGIN DESCRIPTION:
HOBBS HOLLOW 20.0
END DESCRIPTION:
XS GIS Cut Line= 4
      2312241.02     13193180.48      2312405.92     13193115.39
      2312857.31     13192603.24      2313013.14     13192334.86
#Sta/Elev= 30
  4575.6  138.41  4668.8  138.33  4722.6  137.52    4767  135.36  4858.4  128.52
  4879.9  126.51  4937.5  122.33  4958.7  122.24  4972.9  121.38  4979.6  118.66
  4987.1  118.96  4993.8  115.57  4998.3  114.76  5001.1  114.26  5004.3  114.76
    5008  116.86  5015.6  117.16  5022.2  122.03  5029.8   122.8  5064.9  122.79
  5121.8  125.03  5192.1  124.11  5255.5  124.79  5369.4  126.23  5506.3  130.81
  5586.6  135.06  5645.4  140.93  5661.1  141.28  5674.2  142.76  5745.9  147.71
#Mann= 6 ,-1 , 0
  4575.6      .1       0  4858.4     .08       0  4879.9     .12       0
  4998.3     .07       0  5004.3     .12       0  5255.5      .1       0
Bank Sta=4972.9,5022.2
XS Rating Curve= 0 ,0
Exp/Cntr=0.3,0.1

Type RM Length L Ch R = 1 ,9852    ,397,397,397
BEGIN DESCRIPTION:
HOBBS HOLLOW 19.0
END DESCRIPTION:
XS GIS Cut Line= 4
      2312944.11     13193341.11      2312948.45     13193119.73
      2312935.43     13192694.38      2313073.51     13192388.03
#Sta/Elev= 30
  4601.3  136.23  4625.6  136.54  4679.4  135.35  4785.6   132.2  4835.6  129.25
  4845.6  128.08  4855.6  128.26  4945.7  122.55  4955.7  118.34  4965.7  120.92
  4975.7  118.76  4985.7  117.05  4995.7  113.18  5002.4   112.8  5005.1   112.3
  5008.4   112.8  5035.7  119.65  5065.7  120.16  5085.5  122.06  5095.7  121.83
  5135.7  124.89  5185.8  125.19  5278.5  127.79  5300.4  129.89  5322.3  130.61
  5377.2   131.2  5460.1  135.74  5529.5  141.47  5552.6  143.99  5584.3  145.97
#Mann= 5 ,-1 , 0
  4601.3      .1       0  4679.4     .12       0  5002.4     .07       0
  5008.4     .12       0  5085.5      .1       0
Bank Sta=4975.7,5035.7
XS Rating Curve= 0 ,0
Exp/Cntr=0.3,0.1

Type RM Length L Ch R = 1 ,9455    ,393,393,393
BEGIN DESCRIPTION:
HOBBS HOLLOW 18.0
END DESCRIPTION:
XS GIS Cut Line= 3
      2313135.09     13193323.71      2313221.89     13193158.79
       2313330.4     13192512.09
#Sta/Elev= 30
    4527  134.14  4563.9  133.81    4608   132.1  4646.4  128.56  4681.7  127.19
  4704.3  126.55  4713.5   127.2  4719.4  126.15    4766  124.68  4816.7  120.73
  4877.6  119.27  4896.2   120.4    4908  118.57  4928.3  116.42  4938.4  116.73
  4956.9  115.36  4968.8   113.8  5006.4  113.09  5009.1  112.59  5012.4  113.09
 5015.97  118.58  5017.5  121.13  5022.6  123.57  5079.5  123.69  5151.3  124.88
  5232.5  128.79  5265.1  129.02  5283.2  130.06  5333.9  137.93  5369.1  139.71
#Mann= 5 ,-1 , 0
    4527      .1       0  4713.5     .12       0  5006.4     .07       0
  5012.4     .12       0  5079.5      .1       0
Bank Sta=4908,5015.97
XS Rating Curve= 0 ,0
Exp/Cntr=0.3,0.1

Type RM Length L Ch R = 1 ,9062    ,517,517,517
BEGIN DESCRIPTION:
HOBBS HOLLOW 17.0
END DESCRIPTION:
XS GIS Cut Line= 3
      2313208.87     13193414.87      2313412.86     13193219.56
      2313877.29     13192707.39
#Sta/Elev= 30
  4495.3  133.53  4655.8  131.08  4724.8  127.58  4903.1  120.04  4945.7  120.53
  4953.1  118.35  4974.1  117.78  4992.7  109.92  4995.5  109.42  4998.7  109.92
  5016.6  112.12  5024.1  115.98  5030.8  115.91  5037.9  117.75  5087.6  117.19
  5122.7  113.36  5144.4  115.06  5151.1   117.1  5170.3  119.05  5214.7   121.7
  5222.1  123.51  5257.2  126.45  5299.8  126.51  5370.8  130.29  5377.5  134.32
    5385  133.32  5391.7  134.68  5399.2  133.37  5405.9   135.1  5469.1  137.51
#Mann= 5 ,-1 , 0
  4495.3      .1       0  4724.8     .12       0  4992.7     .07       0
  4998.7     .12       0  5170.3     .08       0
#XS Ineff= 1 ,-1
 5049.17 5188.33  117.95
Permanent Ineff=
       T
Bank Sta=4974.1,5037.9
XS Rating Curve= 0 ,0
Exp/Cntr=0.3,0.1

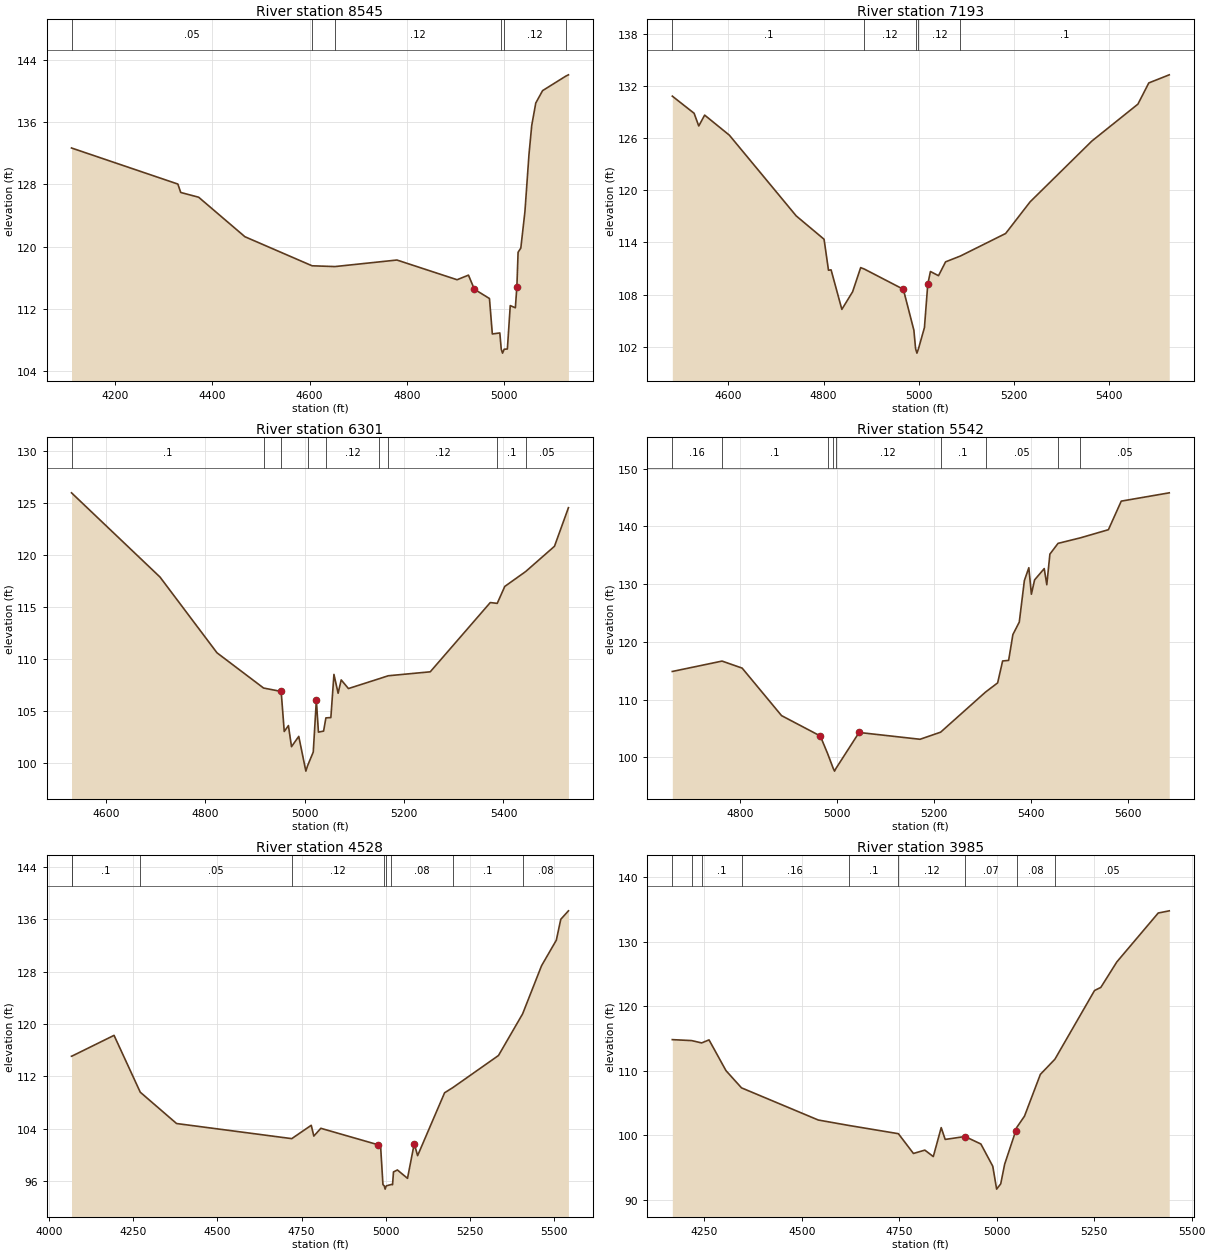
Type RM Length L Ch R = 1 ,8545    ,601,601,601
BEGIN DESCRIPTION:
HOBBS HOLLOW 16.0
END DESCRIPTION:
XS GIS Cut Line= 3
      2313310.64     13193567.96      2314087.72     13193096.85
      2314137.71     13192996.88
#Sta/Elev= 30
  4111.2  132.67  4329.6  128.04  4335.5  126.96  4372.3  126.35  4467.3  121.28
  4605.2  117.55  4652.2  117.45  4779.5  118.29    4903  115.76  4926.4  116.35
  4938.5  114.54  4969.5  113.35  4975.4   108.8  4990.8  108.93  4993.7  106.84
  4996.4  106.34  4999.7  106.84  5006.3  106.87  5012.2  112.44  5022.7  112.16
 5025.83  114.89  5028.3  119.29  5033.9  119.82  5042.3  124.48  5050.7  131.86
  5056.3  135.56  5064.6  138.44  5078.6  140.03  5126.2  141.89  5131.7  142.06
#Mann= 6 ,-1 , 0
  4111.2     .05       0  4605.2      .1       0  4652.2     .12       0
  4993.7     .07       0  4999.7     .12       0  5126.2     .08       0
Bank Sta=4938.5,5025.83
XS Rating Curve= 0 ,0
Exp/Cntr=0.3,0.1

Type RM Length L Ch R = 1 ,7193    ,368,368,368
BEGIN DESCRIPTION:
HOBBS HOLLOW 13.0
END DESCRIPTION:
XS GIS Cut Line= 4
      2314471.87     13194365.42      2314584.74     13194174.42
      2314845.16     13193636.23      2314940.65     13193432.22
#Sta/Elev= 30
  4481.9  130.81  4527.7  128.84  4537.5  127.38  4549.9  128.63  4601.9  126.32
  4742.5  117.04    4801  114.36  4810.3   110.8  4815.8  110.84  4838.4   106.3
    4861  108.32    4878   111.1  4885.8  110.93  4967.7  108.61  4989.9   103.9
  4993.5  101.77  4996.3  101.27  4999.5  101.77  5012.1  104.21  5019.1   109.2
  5024.7  110.65  5041.7  110.17  5056.5  111.76  5087.6  112.43  5182.8  115.02
  5234.3  118.66  5364.2  125.65    5461  129.89  5483.9  132.33  5526.9  133.26
#Mann= 5 ,-1 , 0
  4481.9      .1       0  4885.8     .12       0  4993.5     .07       0
  4999.5     .12       0  5087.6      .1       0
#XS Ineff= 1 ,-1
    4780 4878.33  111.03
Permanent Ineff=
       T
Bank Sta=4967.7,5019.1
XS Rating Curve= 0 ,0
Exp/Cntr=0.3,0.1

Type RM Length L Ch R = 1 ,6301    ,434,434,434
BEGIN DESCRIPTION:
HOBBS HOLLOW 11.0
END DESCRIPTION:
XS GIS Cut Line= 3
      2314987.72     13194796.85      2315387.72     13194496.85
      2315787.72     13194196.85
#Sta/Elev= 30
  4530.7     126  4708.8   117.9  4823.4  110.62  4917.2  107.23  4952.6   106.9
  4958.8  103.05  4967.2  103.62  4973.4  101.59    4988  102.58  5002.3   99.24
  5005.6   99.74  5017.2  101.08  5023.4  106.07  5027.6  102.99    5038  103.09
  5042.6  104.36  5052.6  104.39  5058.8  108.54  5067.2  106.73  5073.4  108.01
    5088  107.18  5150.1  108.13  5168.1  108.41  5252.6  108.79  5373.4  115.45
  5387.4  115.37  5402.6     117  5444.6  118.43  5502.6  120.86  5530.7  124.57
#Mann= 9 ,-1 , 0
  4530.7      .1       0  4917.2     .12       0  4952.6     .07       0
  5005.6     .16       0  5042.6     .12       0  5150.1     .16       0
  5168.1     .12       0  5387.4      .1       0  5444.6     .05       0
Bank Sta=4952.6,5023.4
XS Rating Curve= 0 ,0
Exp/Cntr=0.3,0.1

Type RM Length L Ch R = 1 ,5542    ,1014,1014,1014
BEGIN DESCRIPTION:
HOBBS HOLLOW 9.0
END DESCRIPTION:
XS GIS Cut Line= 4
      2315682.81     13195250.82      2315817.38       13195164.
      2316082.13     13194686.57      2316181.97     13194382.73
#Sta/Elev= 30
  4659.4  114.87  4762.1  116.67  4803.6  115.45  4884.9  107.22  4964.9  103.69
  4980.1  100.62  4991.5    98.1  4994.3    97.6  4997.5    98.1    5045   104.3
  5170.8  103.12  5213.3  104.35    5306   111.3    5331  112.89  5341.3  116.69
  5353.7  116.79  5362.5  121.27  5375.7  123.43  5386.2  130.62  5395.4  132.85
  5400.7  128.26  5407.3  130.74  5427.2   132.7  5432.5   129.9  5438.9  135.21
  5455.7  137.07  5501.9  138.03  5559.7  139.44  5586.2  144.39  5685.3  145.83
#Mann= 9 ,-1 , 0
  4659.4     .16       0  4762.1      .1       0  4980.1     .12       0
  4991.5     .07       0  4997.5     .12       0  5213.3      .1       0
    5306     .05       0  5455.7     .08       0  5501.9     .05       0
Bank Sta=4964.9,5045
XS Rating Curve= 0 ,0
Exp/Cntr=0.3,0.1

Type RM Length L Ch R = 1 ,4528    ,543,543,543
BEGIN DESCRIPTION:
Mapping XS 50203ca4
END DESCRIPTION:
XS GIS Cut Line= 5
      2315765.26     13195320.26      2316299.15      13195185.7
      2316563.91     13194877.54      2316568.25     13194521.64
       2316477.1     13194387.09
#Sta/Elev= 30
  4066.9  115.06  4067.1  115.06  4193.2  118.26    4271  109.57  4378.8  104.78
  4720.7  102.47  4778.6  104.51  4786.3  102.86  4807.1  104.05  4977.2  101.53
  4984.9  101.01  4991.5   95.44  4995.3   95.25    4998   94.75  5001.3   95.25
  5016.5   95.46    5020   95.42  5022.8   97.38  5034.4   97.68  5064.4    96.4
  5084.4   101.7  5094.4   99.87  5174.5  109.48  5198.9  110.27  5334.5  115.18
  5406.1  121.54  5462.4  128.91  5506.2  132.81  5519.4     136  5542.2   137.3
#Mann= 9 ,-1 , 0
  4066.9     .16       0  4067.1      .1       0    4271     .05       0
  4720.7     .12       0  4995.3     .07       0  5001.3     .12       0
  5016.5     .08       0  5198.9      .1       0  5406.1     .08       0
Bank Sta=4977.2,5084.4
XS Rating Curve= 0 ,0
Exp/Cntr=0.3,0.1

Type RM Length L Ch R = 1 ,3985    ,393,393,393
BEGIN DESCRIPTION:
HOBBS HOLLOW 8.0
END DESCRIPTION:
XS GIS Cut Line= 4
      2315886.84      13195411.4       2316099.5     13195480.84
      2316954.53     13195320.25      2317076.06     13195185.71
#Sta/Elev= 30
  4167.5  114.85  4217.1   114.7  4242.8  114.34  4261.7  114.81  4305.2  110.04
    4345  107.37    4542  102.38  4621.2  101.53  4747.5  100.26  4786.2   97.19
  4815.4   97.71  4837.1   96.71  4857.4   101.2  4867.6   99.37  4918.5   99.82
  4959.2   98.66  4989.7   95.21  4999.6   91.66  5010.1   92.48  5020.2   95.53
  5048.7  100.71  5050.8  101.19  5071.1  102.98  5111.8  109.46  5149.1  111.81
  5250.8  122.47  5266.9  122.95  5308.1  126.91  5414.2  134.49  5442.5  134.83
#Mann= 9 ,-1 , 0
  4167.5      .1       0  4217.1     .16       0  4242.8      .1       0
    4345     .16       0  4621.2      .1       0  4747.5     .12       0
  4918.5     .07       0  5050.8     .08       0  5149.1     .05       0
Bank Sta=4918.5,5048.7
XS Rating Curve= 0 ,0
Exp/Cntr=0.3,0.1

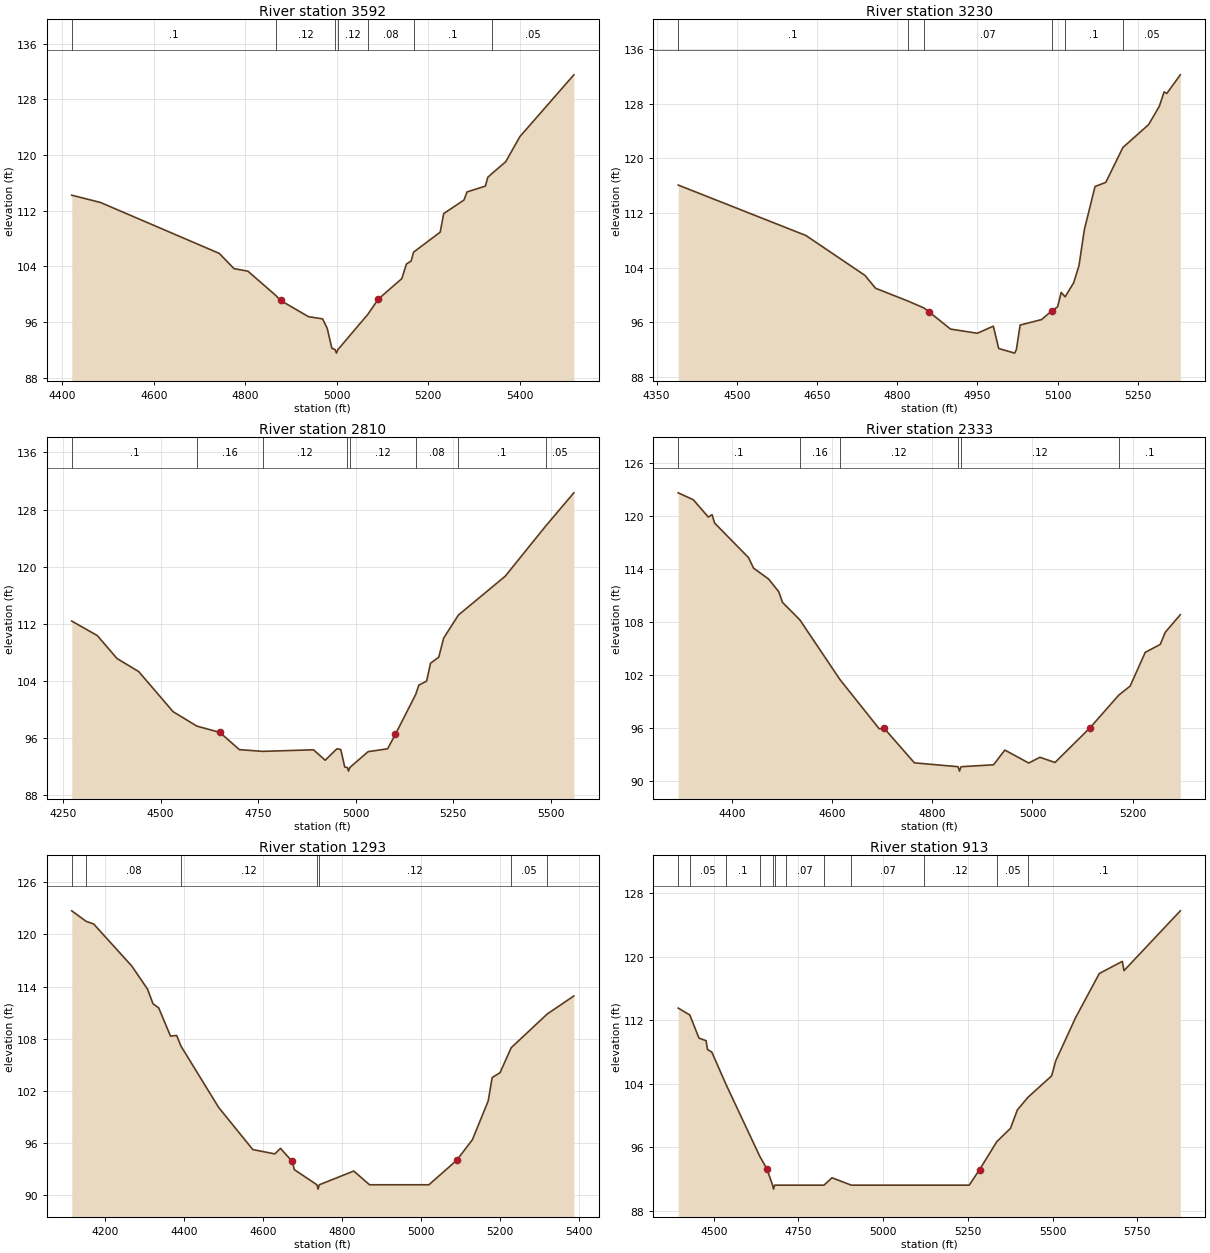
Type RM Length L Ch R = 1 ,3592    ,362,362,362
BEGIN DESCRIPTION:
HOBBS HOLLOW 7.0
END DESCRIPTION:
XS GIS Cut Line= 4
      2316095.15     13195823.73      2316351.23     13195815.04
      2317028.32     13195684.84      2317162.83     13195615.41
#Sta/Elev= 30
    4421  114.23  4483.6  113.19  4743.5  105.87  4775.5  103.69    4806  103.32
  4866.5   99.86  4877.3   99.12  4938.4   96.79    4969   96.48  4979.2   95.12
  4989.3   92.27  4996.5   92.06  4999.3   91.56  5002.5   92.06  5067.5   97.09
  5091.2   99.34  5142.1  102.25  5152.3  104.36  5162.4  104.76    5168  106.06
  5226.1  108.93  5233.7  111.59  5278.1  113.54  5284.6   114.7  5324.9  115.54
    5330   116.8  5338.7  117.31  5369.2  119.03  5400.2  122.64  5518.1  131.51
#Mann= 7 ,-1 , 0
    4421      .1       0  4866.5     .12       0  4996.5     .07       0
  5002.5     .12       0  5067.5     .08       0    5168      .1       0
  5338.7     .05       0
Bank Sta=4877.3,5091.2
XS Rating Curve= 0 ,0
Exp/Cntr=0.3,0.1

Type RM Length L Ch R = 1 ,3230    ,420,420,420
BEGIN DESCRIPTION:
HOBBS HOLLOW 6.0
END DESCRIPTION:
XS GIS Cut Line= 3
      2316116.87     13196006.02      2316277.45     13196084.14
      2317036.97      13196123.2
#Sta/Elev= 30
  4390.6   116.1  4629.5  108.71  4739.7  102.88  4759.7  100.99  4819.8   99.13
  4849.8   98.12  4859.8   97.53  4899.9   95.01  4949.9    94.4    4980   95.44
    4990   92.17  5019.8   91.49    5023   91.99  5030.1    95.6  5070.1    96.4
  5090.1   97.73  5100.1   98.26    5107  100.39  5114.2   99.73  5130.2  101.79
  5140.2  104.31  5150.2  109.56  5170.2  115.89  5190.3  116.49  5222.3   121.6
  5270.4  124.95  5290.4  127.63  5299.4  129.74  5304.4  129.51  5329.7  132.24
#Mann= 6 ,-1 , 0
  4390.6      .1       0  4819.8     .12       0  4849.8     .07       0
  5090.1     .08       0  5114.2      .1       0  5222.3     .05       0
Bank Sta=4859.8,5090.1
XS Rating Curve= 0 ,0
Exp/Cntr=0.3,0.1

Type RM Length L Ch R = 1 ,2810    ,477,477,477
BEGIN DESCRIPTION:
HOBBS HOLLOW 5.0
END DESCRIPTION:
XS GIS Cut Line= 4
      2315957.98     13196415.54      2316100.36     13196512.78
      2316860.78     13196519.72      2317152.44     13196318.34
#Sta/Elev= 30
  4272.4  112.37  4337.7  110.35  4388.6  107.12    4444   105.3  4532.2   99.68
    4593   97.66  4652.2   96.77  4702.2   94.36  4761.9   94.12  4892.2   94.34
  4922.2   92.88  4952.2   94.48  4962.2   94.37  4972.2   91.93  4979.2   91.85
    4982   91.35  4985.2   91.85  5032.2   94.08  5082.2   94.48  5102.2   96.51
  5154.3   102.1  5162.2   103.4  5182.2  103.96  5192.2  106.46  5213.4  107.32
  5225.9  109.99  5263.8  113.22  5383.8  118.66  5487.7   125.7  5559.7  130.34
#Mann= 8 ,-1 , 0
  4272.4      .1       0    4593     .16       0  4761.9     .12       0
  4979.2     .07       0  4985.2     .12       0  5154.3     .08       0
  5263.8      .1       0  5487.7     .05       0
Bank Sta=4652.2,5102.2
XS Rating Curve= 0 ,0
Exp/Cntr=0.3,0.1

Type RM Length L Ch R = 1 ,2333    ,1040,1040,1040
BEGIN DESCRIPTION:
HOBBS HOLLOW 4.0
END DESCRIPTION:
XS GIS Cut Line= 3
      2315787.76     13196996.85      2316487.72     13196946.85
      2316787.68     13196946.85
#Sta/Elev= 30
  4293.3  122.67  4323.3  121.89  4353.4  119.92  4360.9  120.19  4365.9  119.24
  4433.6  115.32  4443.6  114.13  4473.7  112.89  4493.8  111.46  4501.3  110.25
    4536  108.26  4615.9   101.5  4694.3   95.91  4704.3   95.96  4764.5   92.05
  4851.7   91.61  4854.4   91.11  4857.7   91.61  4922.4   91.83  4944.9    93.5
  4992.5   92.03    5015   92.68    5045   92.09    5115   96.03  5172.2   99.73
    5195  100.76    5225  104.58    5255  105.48    5265  106.86    5295  108.85
#Mann= 6 ,-1 , 0
  4293.3      .1       0    4536     .16       0  4615.9     .12       0
  4851.7     .07       0  4857.7     .12       0  5172.2      .1       0
Bank Sta=4704.3,5115
XS Rating Curve= 0 ,0
Exp/Cntr=0.3,0.1

Type RM Length L Ch R = 1 ,1293    ,380,380,380
BEGIN DESCRIPTION:
HOBBS HOLLOW 3.0
END DESCRIPTION:
XS GIS Cut Line= 4
       2315752.1     13197198.46      2316168.74     13197396.37
       2316267.7     13197448.45      2316964.21     13197427.66
#Sta/Elev= 30
  4116.4  122.71  4152.8   121.5  4171.7   121.2  4268.1  116.37    4308  113.71
  4321.9  112.02  4336.3  111.55  4366.2   108.3  4381.7  108.38  4392.3  107.18
    4488   100.1  4574.3   95.26  4629.9   94.76  4644.3    95.4  4673.9   93.89
  4679.6   92.94  4736.5   91.21  4739.3   90.71  4742.5   91.21  4829.6   92.79
  4869.6   91.21  5019.6   91.21  5089.7   94.01  5129.7   96.39  5169.7  100.85
  5179.7  103.54  5199.7   104.1  5227.8  106.97  5319.1  110.85  5386.3  112.92
#Mann= 7 ,-1 , 0
  4116.4      .1       0  4152.8     .08       0  4392.3     .12       0
  4736.5     .07       0  4742.5     .12       0  5227.8     .05       0
  5319.1      .1       0
Bank Sta=4673.9,5089.7
XS Rating Curve= 0 ,0
Exp/Cntr=0.3,0.1

Type RM Length L Ch R = 1 ,913     ,490,490,490
BEGIN DESCRIPTION:
HOBBS HOLLOW 2.0
END DESCRIPTION:
XS GIS Cut Line= 4
      2315864.63     13197655.45      2315938.67     13197706.71
      2316980.76     13197877.54      2317316.71     13197866.16
#Sta/Elev= 30
  4395.1  113.53  4429.3  112.66  4456.3  109.75  4477.3  109.42  4481.5  108.31
  4494.3  107.98  4536.8  103.85  4635.8   94.85  4656.5   93.29  4673.7   91.21
  4676.5   90.71  4679.7   91.21  4712.1   91.21  4825.5   91.21    4849   92.14
  4906.2   91.21  5119.2   91.21    5254   91.21  5284.7   93.17  5335.5   96.69
  5375.9   98.37  5396.2  100.69  5427.6  102.29  5497.5  104.99  5509.4  106.87
  5568.1  112.32  5638.2  117.89  5706.1  119.42  5711.1  118.25  5877.3  125.79
#Mann= 12 ,-1 , 0
  4395.1      .1       0  4429.3     .05       0  4536.8      .1       0
  4635.8     .12       0  4673.7     .07       0  4679.7     .12       0
  4712.1     .07       0  4825.5     .12       0  4906.2     .07       0
  5119.2     .12       0  5335.5     .05       0  5427.6      .1       0
Bank Sta=4656.5,5284.7
XS Rating Curve= 0 ,0
Exp/Cntr=0.3,0.1

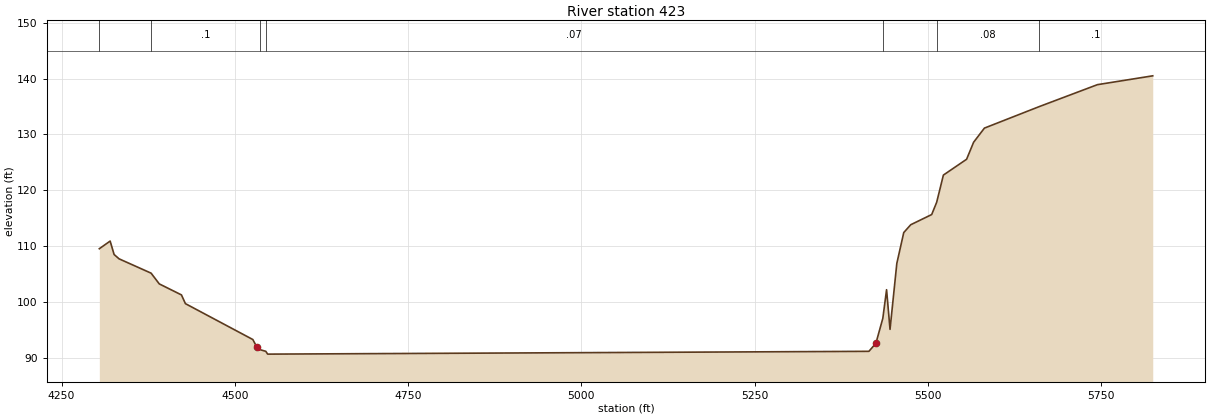
Type RM Length L Ch R = 1 ,423     ,0,0,0
BEGIN DESCRIPTION:
HOBBS HOLLOW 1.0
END DESCRIPTION:
XS GIS Cut Line= 4
      2315893.11     13197831.97       2316120.9     13198241.99
      2316923.81     13198338.79      2317162.84     13198298.96
#Sta/Elev= 30
  4304.5  109.56  4320.1  110.93  4325.8  108.53    4333  107.75  4379.2  105.19
    4391  103.27    4423   101.3  4428.7   99.74    4526   93.32  4531.7   91.98
  4536.6    91.5  4544.7   91.21  4547.4   90.71    5415   91.21  5425.1   92.64
  5435.1   97.11  5440.5  102.23  5445.5   95.14  5455.3  106.93  5465.3  112.45
  5475.4  113.85  5505.6  115.67  5512.8  117.86  5522.5  122.73    5556  125.56
  5566.1   128.6  5581.7  131.13  5661.1  134.99  5744.8   138.9  5824.6  140.48
#Mann= 7 ,-1 , 0
  4304.5     .05       0  4379.2      .1       0  4536.6     .12       0
  4544.7     .07       0  5435.1     .05       0  5512.8     .08       0
  5661.1      .1       0
Bank Sta=4531.7,5425.1
XS Rating Curve= 0 ,0
Exp/Cntr=0.3,0.1