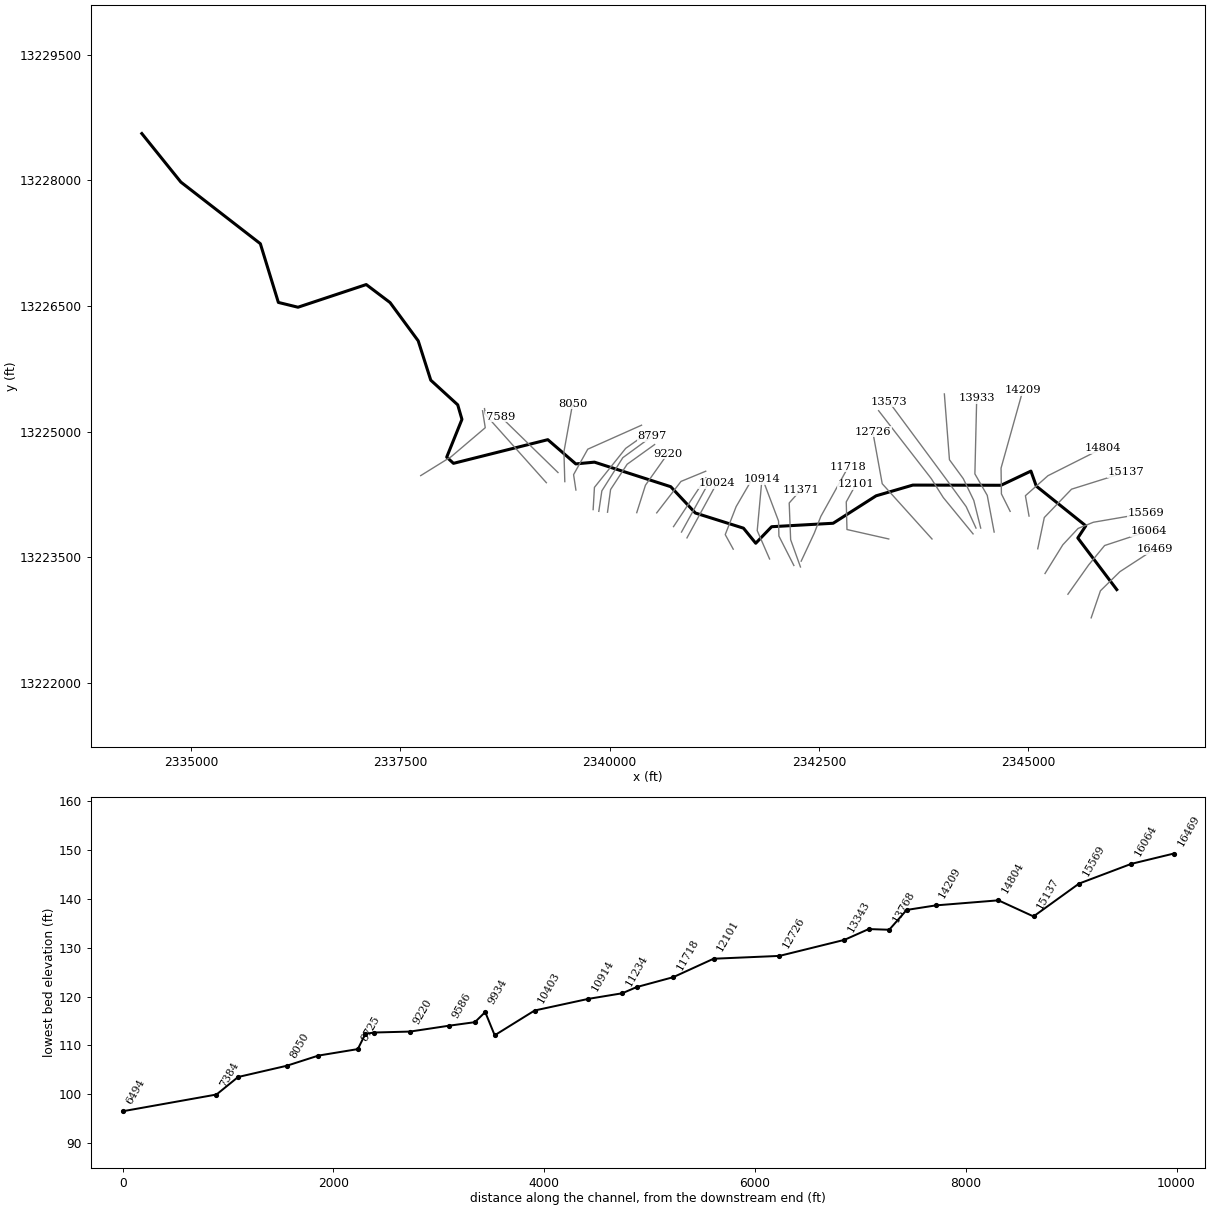
--- JACK GREEN HOLLOW.prj (project) ---

Proj Title=JACK GREEN HOLLOW Base Level Engineering
Current Plan=p01
Default Exp/Contr=0.3,0.1
English Units
Geom File=g01
Flow File=f01
Plan File=p01
Y Axis Title=Elevation
X Axis Title(PF)=Main Channel Distance
X Axis Title(XS)=Station
BEGIN DESCRIPTION:
JACK GREEN HOLLOW
END DESCRIPTION:
DSS Export Rating Curves= 0
DSS Export Rating Curve Sorted= 0
DSS Export Volume Flow Curves= 0
DXF OffsetX= 0
DXF OffsetY= 0
DXF ScaleX= 1
DXF ScaleY= 10

--- JACK GREEN HOLLOW.p01 (plan) ---

Plan Title=Multiple Run
Short Identifier=Multiple
Geom File=g01
Flow File=f01
Subcritical Flow
K Sum by GR= 0
Std Step Tol= 0.01
Critical Tol= 0.01
Num of Std Step Trials= 20
Max Error Tol= 0.3
Flow Tol Ratio= 0.001
Split Flow NTrial= 30
Split Flow Tol= 0.02
Split Flow Ratio= 0.02
Log Output Level= 0
Friction Slope Method= 1
Unsteady Friction Slope Method= 2
Unsteady Bridges Friction Slope Method= 1
Parabolic Critical Depth
Global Vel Dist=  1 , 1 , 1
Global Log Level= 0
CheckData=True
Encroach Param= -1, 0, 0, 0
BEGIN DESCRIPTION:
Multiple Run
END DESCRIPTION:

--- JACK GREEN HOLLOW.f01 (steady flow) ---

Flow Title=Multiple
Program Version=4.10
Number of Profiles= 7
Profile Names=10-year,25-year,50-year,1pct_min,100-year,1pct_plu,500-year
River Rch & RM=JACK GREEN HOLLO,Reach-1         ,16469
     431     585     708     626     847    1145    1215
River Rch & RM=JACK GREEN HOLLO,Reach-1         ,8881
     839    1180    1462    1320    1785    2414    2670
Boundary for River Rch & Prof#=JACK GREEN HOLLO,Reach-1         , 1
Up Type= 0
Dn Type= 3
Dn Slope=0.00008
Boundary for River Rch & Prof#=JACK GREEN HOLLO,Reach-1         , 2
Up Type= 0
Dn Type= 3
Dn Slope=0.00008
Boundary for River Rch & Prof#=JACK GREEN HOLLO,Reach-1         , 3
Up Type= 0
Dn Type= 3
Dn Slope=0.00008
Boundary for River Rch & Prof#=JACK GREEN HOLLO,Reach-1         , 4
Up Type= 0
Dn Type= 3
Dn Slope=0.00008
Boundary for River Rch & Prof#=JACK GREEN HOLLO,Reach-1         , 5
Up Type= 0
Dn Type= 3
Dn Slope=0.00008
Boundary for River Rch & Prof#=JACK GREEN HOLLO,Reach-1         , 6
Up Type= 0
Dn Type= 3
Dn Slope=0.00008
Boundary for River Rch & Prof#=JACK GREEN HOLLO,Reach-1         , 7
Up Type= 0
Dn Type= 3
Dn Slope=0.00008
DSS Import GetInterval= 0
DSS Import GetPeak= 0
DSS Import FillOption= 0

--- JACK GREEN HOLLOW.g01 (geometry) ---

Geom Title=Existing Conditions
Program Version=4.10

River Reach=JACK GREEN HOLLO,Reach-1
Reach XY= 30
      2346057.76     13223115.03      2345592.27     13223731.35
      2345687.75     13223876.75      2345096.39     13224350.92
      2345032.37     13224529.96      2344675.38     13224360.69
      2343621.78     13224362.86      2343183.41     13224234.82
      2342670.18     13223907.13      2341935.58     13223865.89
       2341745.7     13223668.41      2341599.21     13223848.53
        2341025.     13224029.35      2340730.36     13224343.67
      2339819.45     13224636.81      2339596.41     13224615.89
      2339262.24     13224905.12      2338135.53     13224622.58
      2338054.75     13224696.78      2338236.62     13225147.55
      2338186.15     13225321.21      2337864.19     13225615.65
      2337714.26     13226085.42      2337377.97     13226542.42
      2337093.48     13226757.35      2336278.42     13226486.62
      2336044.05     13226543.91      2335828.77      13227245.3
       2334879.4     13227980.93      2334413.06     13228560.44

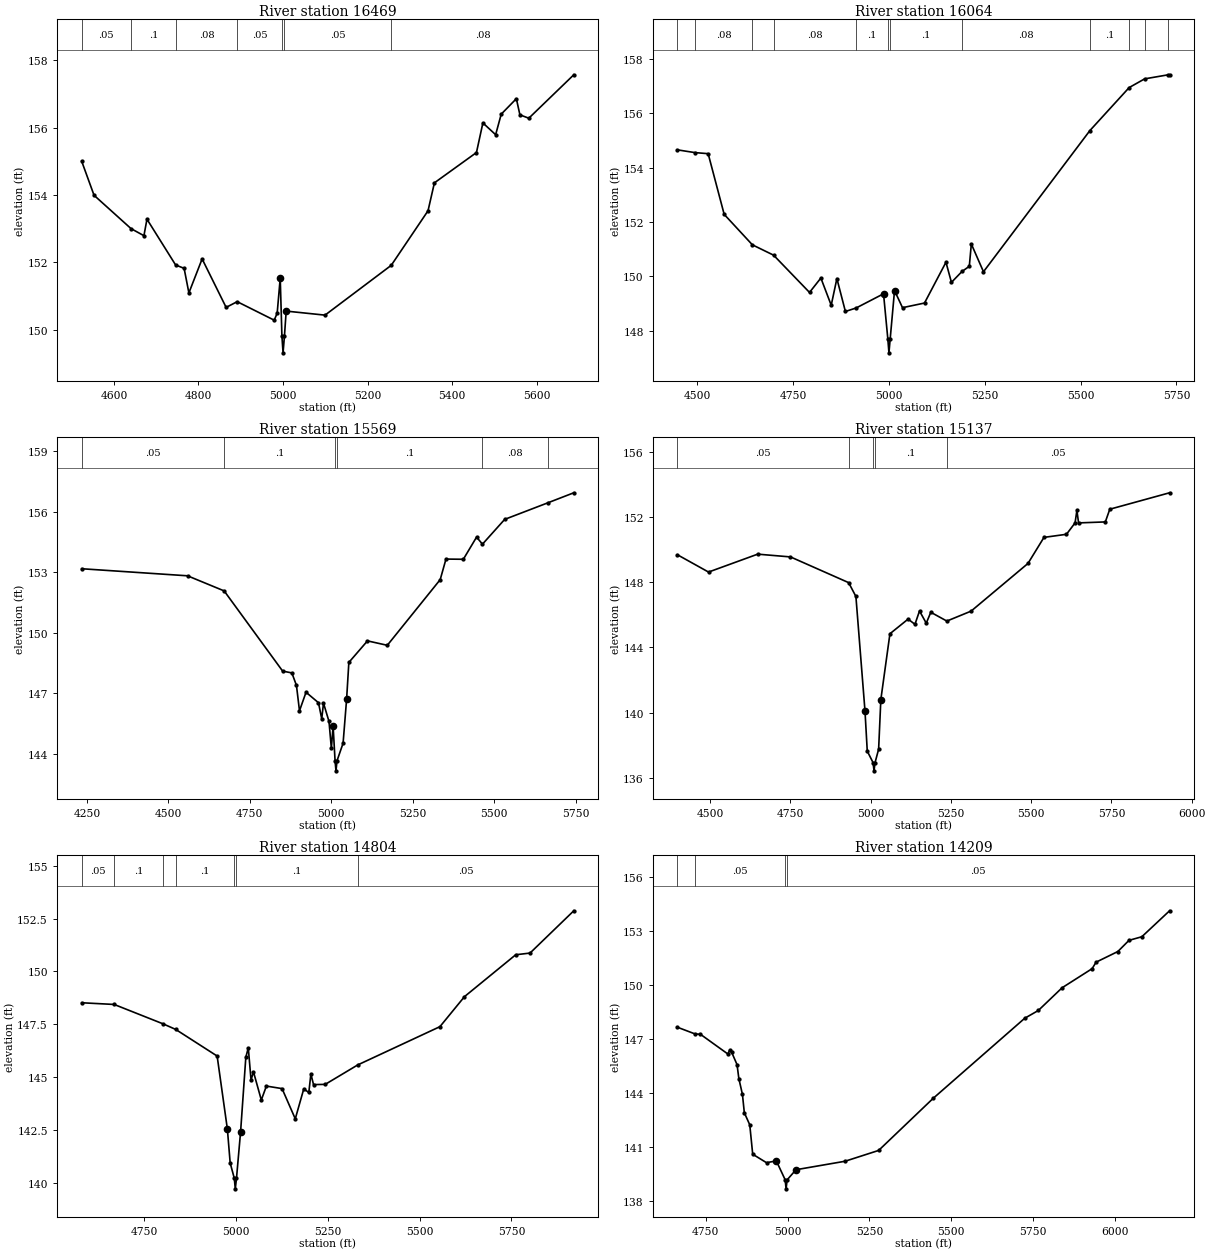
Type RM Length L Ch R = 1 ,16469   ,405,405,405
BEGIN DESCRIPTION:
JACK GREEN HOLLOW 15.0
END DESCRIPTION:
XS GIS Cut Line= 4
      2345752.08     13222777.63      2345862.76     13223100.97
      2346094.96     13223328.84      2346511.64     13223600.12
#Sta/Elev= 30
  4523.7     155  4552.9  153.99  4640.4     153  4670.9  152.79  4678.1  153.28
  4745.9  151.92    4766  151.82  4777.3  151.09  4808.6   152.1  4865.4  150.66
  4891.6  150.83  4979.2  150.28  4986.2  150.49  4993.4  151.53  4997.4  149.81
  5000.1  149.31  5003.4  149.81  5007.5  150.55  5099.4  150.43  5256.1  151.91
  5343.1  153.53  5358.2  154.36  5457.7  155.26  5472.9  156.14  5503.1  155.79
  5516.3   156.4  5552.1  156.86  5560.5  156.38  5581.6  156.28    5688  157.57
#Mann= 7 ,-1 , 0
  4523.7     .05       0  4640.4      .1       0  4745.9     .08       0
  4891.6     .05       0  4997.4     .04       0  5003.4     .05       0
  5256.1     .08       0
Bank Sta=4993.4,5007.5
XS Rating Curve= 0 ,0
Exp/Cntr=0.3,0.1

Type RM Length L Ch R = 1 ,16064   ,495,495,495
BEGIN DESCRIPTION:
Mapping XS dff2755f
END DESCRIPTION:
XS GIS Cut Line= 4
       2345474.3     13223059.73       2345721.7     13223409.13
      2345912.67     13223641.34      2346440.05     13223814.96
#Sta/Elev= 30
  4448.2  154.65  4493.5  154.55  4528.2  154.51    4570  152.28  4643.6  151.16
  4698.9  150.78  4792.7  149.41  4822.3  149.94  4849.3  148.94  4864.1  149.92
  4886.3  148.71  4914.5  148.84  4985.8  149.36  4997.1  147.69  4999.9  147.19
  5003.1  147.69  5014.5  149.48  5035.3  148.85  5092.7  149.02  5148.7  150.52
    5163  149.78  5190.5  150.18  5209.6  150.37  5214.9  151.19  5246.6  150.17
  5524.3  155.36  5626.7  156.94  5667.1  157.26    5729  157.41  5732.2  157.41
#Mann= 12 ,-1 , 0
  4448.2     .05       0  4493.5     .08       0  4643.6     .05       0
  4698.9     .08       0  4914.5      .1       0  4997.1     .07       0
  5003.1      .1       0  5190.5     .08       0  5524.3      .1       0
  5626.7     .08       0  5667.1      .1       0    5729     .05       0
Bank Sta=4985.8,5014.5
XS Rating Curve= 0 ,0
Exp/Cntr=0.3,0.1

Type RM Length L Ch R = 1 ,15569   ,432,432,432
BEGIN DESCRIPTION:
Mapping XS 303d3726
END DESCRIPTION:
XS GIS Cut Line= 5
      2345200.84      13223307.1      2345413.54     13223650.02
      2345595.83     13223845.33      2345778.12     13223919.12
      2346411.84     13224027.63
#Sta/Elev= 30
  4234.2  153.18  4558.9  152.83  4671.4  152.08  4850.9   148.1  4879.2  148.01
  4893.3  147.39  4902.6  146.13  4922.7  147.05  4960.9  146.53  4970.9  145.73
  4976.3  146.51  4993.2   145.6  5000.4  144.27  5005.8  145.37  5011.8  143.65
  5014.6  143.15  5017.8  143.65  5036.4  144.52  5047.2   146.7  5054.1  148.53
  5111.3   149.6  5172.1  149.38  5334.5  152.64  5352.2  153.66  5405.5  153.65
  5446.1  154.75  5464.2   154.4  5532.4  155.63  5664.6  156.45  5744.5  156.95
#Mann= 6 ,-1 , 0
  4234.2     .05       0  4671.4      .1       0  5011.8     .07       0
  5017.8      .1       0  5464.2     .08       0  5664.6      .1       0
Bank Sta=5005.8,5047.2
XS Rating Curve= 0 ,0
Exp/Cntr=0.3,0.1

Type RM Length L Ch R = 1 ,15137   ,333,333,333
BEGIN DESCRIPTION:
Mapping XS 450b9319
END DESCRIPTION:
XS GIS Cut Line= 4
      2345114.05     13223602.25      2345192.18     13223975.54
       2345517.7     13224314.08      2346168.76     13224518.08
#Sta/Elev= 30
  4397.9  149.69  4494.6  148.63  4647.8  149.73    4750  149.56  4931.2  147.98
  4953.8  147.13  4982.1   140.1  4989.2  137.63  5007.4  136.92  5010.2  136.42
  5013.4  136.92  5024.6  137.75  5031.5   140.8  5059.8  144.84  5116.4  145.74
  5137.8  145.42    5152  146.24    5173  145.49  5187.2  146.16  5237.2  145.62
  5312.7  146.23    5490  149.16  5539.8  150.76  5609.9  150.95  5636.7  151.65
  5642.4  152.42  5647.6  151.65    5731  151.71  5744.9  152.49  5931.2   153.5
#Mann= 5 ,-1 , 0
  4397.9     .05       0  4931.2      .1       0  5007.4     .07       0
  5013.4      .1       0  5237.2     .05       0
Bank Sta=4982.1,5031.5
XS Rating Curve= 0 ,0
Exp/Cntr=0.3,0.1

Type RM Length L Ch R = 1 ,14804   ,595,595,595
BEGIN DESCRIPTION:
Mapping XS 138c818a
END DESCRIPTION:
XS GIS Cut Line= 4
      2345009.89     13223992.91      2344966.49     13224235.96
      2345235.59     13224474.67      2345890.94     13224804.52
#Sta/Elev= 30
  4579.6  148.52    4668  148.44  4801.6  147.52  4835.5  147.26  4948.5     146
  4976.4  142.54    4984  140.94  4995.2  140.22  4997.9  139.72  5001.2  140.22
  5012.4  142.43  5026.6  145.94  5033.3  146.39  5040.8  144.87  5047.5  145.25
  5068.8  143.92  5082.6  144.58  5125.3  144.46  5161.3  143.03  5184.3  144.44
  5198.2  144.28  5203.8  145.15    5211  144.65  5242.8  144.66  5331.4  145.58
  5555.3  147.39  5622.2  148.81  5761.7  150.79  5800.7  150.87  5919.9  152.87
#Mann= 7 ,-1 , 0
  4579.6     .05       0    4668      .1       0  4801.6     .05       0
  4835.5      .1       0  4995.2     .07       0  5001.2      .1       0
  5331.4     .05       0
Bank Sta=4976.4,5012.4
XS Rating Curve= 0 ,0
Exp/Cntr=0.3,0.1

Type RM Length L Ch R = 1 ,14209   ,276,276,276
BEGIN DESCRIPTION:
Mapping XS 37f1ad13
END DESCRIPTION:
XS GIS Cut Line= 4
      2344784.21     13224049.31      2344680.03     13224257.66
      2344675.69     13224565.82      2344935.71     13225493.22
#Sta/Elev= 30
  4663.4  147.64  4717.1  147.27  4733.6  147.25  4817.2  146.16    4823  146.37
  4828.6  146.27  4845.4  145.57    4851  144.79  4861.9  143.92  4867.7   142.9
  4884.3  142.23  4893.3   140.6  4935.5  140.13  4965.5  140.23  4992.6  139.18
  4995.3  138.68  4998.6  139.18  5025.6  139.74  5175.6  140.21  5278.3  140.81
  5444.5  143.69  5724.9  148.14  5766.4  148.57  5839.1  149.83  5930.9  150.89
    5943  151.25  6009.5  151.84  6043.6  152.46  6082.9  152.66  6167.7   154.1
#Mann= 4 ,-1 , 0
  4663.4      .1       0  4717.1     .05       0  4992.6    .035       0
  4998.6     .05       0
Bank Sta=4965.5,5025.6
XS Rating Curve= 0 ,0
Exp/Cntr=0.3,0.1

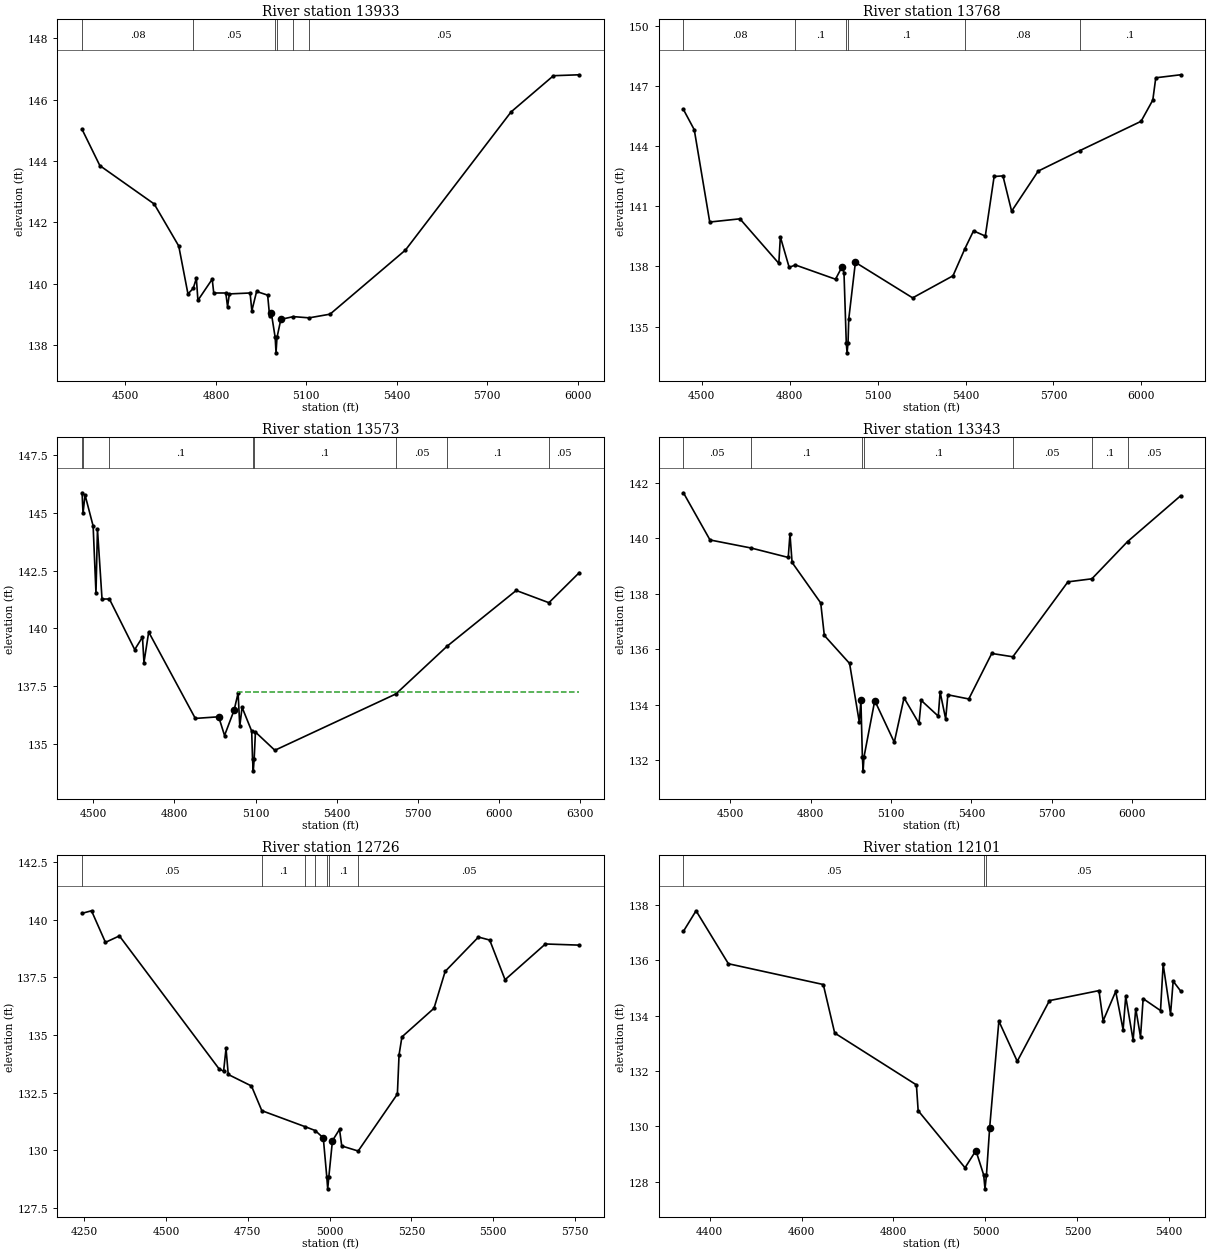
Type RM Length L Ch R = 1 ,13933   ,165,165,165
BEGIN DESCRIPTION:
Mapping XS a3898737
END DESCRIPTION:
XS GIS Cut Line= 4
      2344593.23     13223801.92      2344510.76      13224240.3
      2344363.19     13224496.37      2344384.87      13225402.7
#Sta/Elev= 30
  4356.4  145.03  4415.3  143.85  4595.5   142.6  4676.9  141.23  4707.4  139.67
  4724.8  139.85  4735.3  140.18  4740.4  139.46  4787.8  140.15  4792.9   139.7
    4833   139.7  4838.7  139.25  4844.7  139.67  4913.4   139.7  4919.2  139.12
    4935  139.75  4971.6  139.63  4978.1  138.95  4983.9  139.04  4996.6  138.25
  4999.4  137.75  5002.6  138.25  5015.4  138.84  5056.9  138.93  5109.2  138.89
  5178.5  139.01  5428.6   141.1  5778.7   145.6  5919.2  146.78  6004.6  146.81
#Mann= 6 ,-1 , 0
  4356.4     .08       0  4724.8     .05       0  4996.6    .035       0
  5002.6     .05       0  5056.9     .08       0  5109.2     .05       0
Bank Sta=4983.9,5015.4
XS Rating Curve= 0 ,0
Exp/Cntr=0.3,0.1

Type RM Length L Ch R = 1 ,13768   ,195,195,195
BEGIN DESCRIPTION:
Mapping XS 9d86c979
END DESCRIPTION:
XS GIS Cut Line= 5
      2344432.63     13223849.69      2344350.17     13224179.53
       2344224.3     13224439.95      2344059.37     13224665.64
      2343998.61     13225451.23
#Sta/Elev= 30
  4437.2  145.82  4474.2  144.81    4527  140.21  4630.1  140.37  4762.8  138.15
    4768  139.47  4798.1  137.95  4819.3  138.07  4956.3  137.36  4978.9  137.99
  4985.2  137.68    4993  134.19  4995.7  133.69    4999  134.19  5001.5  135.38
  5024.1   138.2  5219.5  136.43  5357.2  137.53  5397.8  138.88  5427.3  139.77
  5467.5  139.51  5497.6  142.48  5527.7  142.51  5557.3  140.75  5648.1  142.75
  5790.3  143.77  5999.1  145.23  6039.2  146.29  6049.3   147.4  6133.9  147.55
#Mann= 6 ,-1 , 0
  4437.2     .08       0  4819.3      .1       0    4993     .07       0
    4999      .1       0  5397.8     .08       0  5790.3      .1       0
Bank Sta=4978.9,5024.1
XS Rating Curve= 0 ,0
Exp/Cntr=0.3,0.1

Type RM Length L Ch R = 1 ,13573   ,230,230,230
BEGIN DESCRIPTION:
Mapping XS 0d44c1f0
END DESCRIPTION:
XS GIS Cut Line= 4
      2344376.19     13223849.71      2344259.02     13224105.75
      2344015.97     13224439.95      2343334.55     13225360.08
#Sta/Elev= 30
  4458.2  145.87  4461.7  144.98  4469.1  145.78  4499.1  144.43  4509.6  141.52
  4515.1   144.3    4532  141.27  4559.3  141.27    4653  139.08  4681.7  139.62
  4687.2  138.52  4704.7  139.84  4877.2   136.1  4963.7  136.17  4985.4  135.36
  5020.9  136.46  5035.6   137.2  5041.8  135.76  5050.3  136.58  5085.9  135.55
    5089  134.33  5091.8  133.83    5095  134.33  5099.7  135.51  5171.6  134.72
  5619.6  137.16  5808.4  139.22  6064.8  141.64  6185.8  141.11    6298  142.41
#Mann= 8 ,-1 , 0
  4458.2     .08       0  4461.7     .05       0  4559.3      .1       0
    5089     .07       0    5095      .1       0  5619.6     .05       0
  5808.4      .1       0  6185.8     .05       0
#XS Ineff= 2 , 0
       0                 5035.61       0  137.23
Permanent Ineff=
       F       T
Bank Sta=4963.7,5020.9
XS Rating Curve= 0 ,0
Exp/Cntr=0.3,0.1

Type RM Length L Ch R = 1 ,13343   ,617,617,617
BEGIN DESCRIPTION:
Mapping XS 974c0c3c
END DESCRIPTION:
XS GIS Cut Line= 4
      2344341.52     13223780.19      2343985.59     13224214.25
      2343842.36     13224439.95      2343213.01     13225251.59
#Sta/Elev= 30
  4324.8  141.64    4424  139.94  4577.2  139.65    4716  139.31  4722.5  140.15
  4730.4  139.13  4837.3  137.67  4850.7   136.5    4945  135.49  4981.4  133.37
  4987.3  134.16  4992.8  132.12  4995.6  131.62  4998.8  132.12    5039  134.15
  5111.9  132.65  5148.3  134.25  5204.1  133.33  5212.3  134.16  5276.1  133.59
  5282.9  134.46  5303.7  133.49  5311.9  134.36    5390  134.21  5475.7  135.85
  5554.4  135.73    5760  138.43  5849.5  138.54  5982.5  139.88  6180.5  141.53
#Mann= 7 ,-1 , 0
  4324.8     .05       0  4577.2      .1       0  4992.8     .07       0
  4998.8      .1       0  5554.4     .05       0  5849.5      .1       0
  5982.5     .05       0
Bank Sta=4987.3,5039
XS Rating Curve= 0 ,0
Exp/Cntr=0.3,0.1

Type RM Length L Ch R = 1 ,12726   ,625,625,625
BEGIN DESCRIPTION:
Mapping XS 5489a6ff
END DESCRIPTION:
XS GIS Cut Line= 3
      2343851.07     13223719.43      2343256.42     13224379.19
      2343143.58     13224999.82
#Sta/Elev= 30
  4243.8  140.28  4272.6  140.39  4315.2  139.02  4357.8   139.3    4662  133.54
  4676.2  133.43  4683.6  134.42  4690.4  133.29  4761.4  132.79    4793  131.72
  4924.4  131.03  4955.9  130.86  4980.8  130.54  4991.6  128.83  4994.3  128.33
  4997.6  128.83  5008.8  130.42  5030.4  130.91  5037.2  130.19  5087.4  129.97
  5207.2  132.44  5212.3  134.14  5221.1  134.92    5319  136.16  5353.2  137.76
  5454.9  139.25  5489.3  139.12  5536.2   137.4  5659.5  138.95  5762.8   138.9
#Mann= 7 ,-1 , 0
  4243.8     .05       0    4793      .1       0  4924.4     .05       0
  4955.9      .1       0  4991.6     .07       0  4997.6      .1       0
  5087.4     .05       0
Bank Sta=4980.8,5008.8
XS Rating Curve= 0 ,0
Exp/Cntr=0.3,0.1

Type RM Length L Ch R = 1 ,12101   ,383,383,383
BEGIN DESCRIPTION:
Mapping XS b9d42e94
END DESCRIPTION:
XS GIS Cut Line= 4
      2343334.53     13223719.47      2342835.41     13223832.31
      2342826.73     13224162.17      2342942.51     13224372.29
#Sta/Elev= 30
    4343  137.04  4370.5  137.78  4440.8  135.87  4647.3  135.12  4672.1  133.37
  4849.9   131.5  4853.7  130.57  4955.7  128.51  4979.3  129.13  4996.3  128.25
  4999.1  127.75  5002.3  128.25  5009.3  129.96  5029.3   133.8  5069.3  132.35
  5139.4  134.54  5247.1   134.9  5256.1  133.81  5283.5  134.87  5299.6  133.49
  5305.3  134.69  5321.4  133.11  5327.1  134.25  5337.5  133.23  5343.2  134.61
    5381  134.18  5386.7  135.85  5402.8  134.05  5408.5  135.24  5424.6  134.89
#Mann= 3 ,-1 , 0
    4343     .05       0  4996.3     .03       0  5002.3     .05       0
Bank Sta=4979.3,5009.3
XS Rating Curve= 0 ,0
Exp/Cntr=0.3,0.1

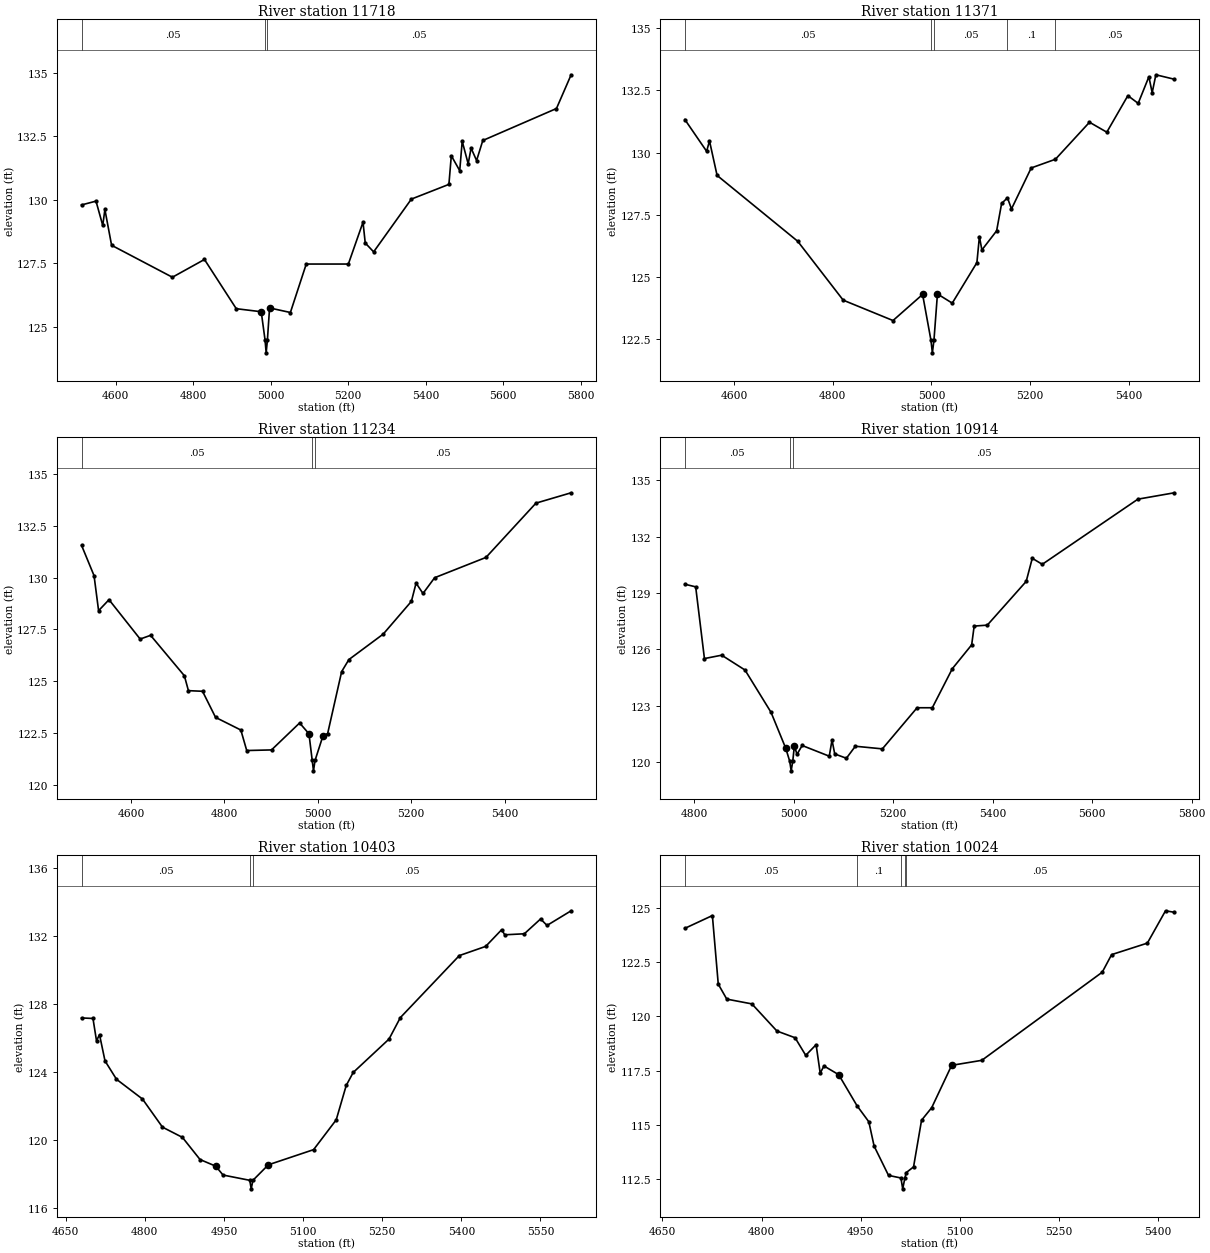
Type RM Length L Ch R = 1 ,11718   ,347,347,347
BEGIN DESCRIPTION:
Mapping XS f1546a49
END DESCRIPTION:
XS GIS Cut Line= 4
      2342288.54     13223454.72      2342444.79     13223788.91
      2342522.91     13223988.56      2342852.39     13224582.49
#Sta/Elev= 30
  4512.3   129.8  4549.5  129.95  4566.9  128.99  4572.4  129.62  4589.7  128.21
  4746.5  126.95  4829.2  127.65  4911.2  125.71  4975.6  125.59  4985.5  124.47
  4988.3  123.97  4991.5  124.47  4997.1  125.74  5050.8  125.56  5091.7  127.47
  5200.3  127.47  5238.1  129.12  5243.8   128.3  5265.5  127.95  5362.8  130.03
  5459.6  130.61  5465.8  131.74  5487.5  131.15  5493.9  132.31  5509.3  131.42
  5516.8  132.04    5531  131.55    5547  132.34    5737   133.6  5774.8  134.93
#Mann= 3 ,-1 , 0
  4512.3     .05       0  4985.5     .03       0  4991.5     .05       0
Bank Sta=4975.6,4997.1
XS Rating Curve= 0 ,0
Exp/Cntr=0.3,0.1

Type RM Length L Ch R = 1 ,11371   ,137,137,137
BEGIN DESCRIPTION:
Mapping XS 69dba6ba
END DESCRIPTION:
XS GIS Cut Line= 4
      2342279.85     13223385.28      2342162.67     13223710.78
      2342145.31     13224149.15      2342283.45     13224304.56
#Sta/Elev= 30
  4499.9  131.33  4544.1  130.05  4549.9  130.47  4565.3  129.08  4728.8  126.43
    4821  124.06    4922  123.24    4982  124.29    4999  122.44  5001.8  121.94
    5005  122.44  5012.1  124.31  5042.1  123.94  5092.1  125.57  5097.2  126.62
  5102.2  126.08  5132.1  126.85  5142.2  127.95  5154.1  128.18  5162.2  127.73
  5202.2  129.38  5251.3  129.73  5320.4  131.22  5355.5  130.82  5398.2  132.29
  5419.1  131.98  5440.8  133.05  5447.5  132.41    5455  133.13  5492.5  132.95
#Mann= 5 ,-1 , 0
  4499.9     .05       0    4999    .035       0    5005     .05       0
  5154.1      .1       0  5251.3     .05       0
Bank Sta=4982,5012.1
XS Rating Curve= 0 ,0
Exp/Cntr=0.3,0.1

Type RM Length L Ch R = 1 ,11234   ,320,320,320
BEGIN DESCRIPTION:
Mapping XS 3f48a608
END DESCRIPTION:
XS GIS Cut Line= 4
      2342201.13     13223403.06      2342022.47     13223754.16
      2342018.31      13223932.8      2341850.07      13224377.3
#Sta/Elev= 30
  4494.3  131.55    4521  130.09  4530.7   128.4    4553  128.93  4619.7  127.03
    4642  127.21  4714.3  125.26    4723  124.54  4753.2  124.51  4781.1  123.25
  4835.2  122.64  4847.8  121.65  4900.9  121.68    4961  122.98    4981  122.46
    4988  121.17  4990.7  120.67    4994  121.17    5011  122.36    5021  122.47
    5051  125.46  5066.5  126.04    5140  127.27  5200.3  128.85  5210.3  129.73
  5225.1  129.23    5250  129.99  5359.9  130.97  5466.9  133.59  5542.2  134.09
#Mann= 3 ,-1 , 0
  4494.3     .05       0    4988    .035       0    4994     .05       0
Bank Sta=4981,5011
XS Rating Curve= 0 ,0
Exp/Cntr=0.3,0.1

Type RM Length L Ch R = 1 ,10914   ,511,511,511
BEGIN DESCRIPTION:
Mapping XS 91da2b40
END DESCRIPTION:
XS GIS Cut Line= 3
      2341910.94     13223480.73      2341763.36     13223819.29
      2341819.79     13224431.27
#Sta/Elev= 30
  4781.4  129.47  4803.2  129.33  4820.8  125.51  4855.5  125.69  4902.3   124.9
  4954.6  122.65  4984.4  120.72  4992.3  120.03  4995.1  119.53  4998.3  120.03
  5001.5  120.85  5006.9  120.41  5017.2  120.88  5071.7  120.31  5077.2  121.17
  5082.7  120.43  5106.1   120.2  5124.1  120.84  5178.4   120.7  5248.2  122.89
  5278.8  122.89    5319  124.97  5357.9  126.24  5362.9  127.24  5389.3  127.29
  5467.5  129.62  5479.7  130.85  5499.8  130.53    5692     134  5765.3  134.34
#Mann= 3 ,-1 , 0
  4781.4     .05       0  4992.3    .035       0  4998.3     .05       0
Bank Sta=4984.4,5001.5
XS Rating Curve= 0 ,0
Exp/Cntr=0.3,0.1

Type RM Length L Ch R = 1 ,10403   ,379,379,379
BEGIN DESCRIPTION:
Mapping XS 2074fb0c
END DESCRIPTION:
XS GIS Cut Line= 4
      2341476.89     13223597.96      2341381.42     13223771.55
      2341511.63     13224105.75      2341698.24     13224426.89
#Sta/Elev= 30
    4680  127.17  4701.6  127.14  4708.3  125.83    4714  126.19  4724.4  124.65
  4746.2  123.57  4795.5  122.41  4833.4  120.76  4871.2  120.16  4904.6  118.86
  4934.4  118.47  4948.2  117.95  4998.9  117.64  5001.6  117.14  5004.9  117.64
  5034.1  118.55  5119.9  119.44  5162.8  121.19  5181.8  123.21    5195  123.97
  5262.9  125.93  5284.4  127.19  5396.2  130.83  5446.2  131.37  5476.5  132.35
  5482.3  132.05  5519.5  132.11  5550.3  132.98  5562.5   132.6  5608.2  133.46
#Mann= 3 ,-1 , 0
    4680     .05       0  4998.9    .035       0  5004.9     .05       0
Bank Sta=4934.4,5034.1
XS Rating Curve= 0 ,0
Exp/Cntr=0.3,0.1

Type RM Length L Ch R = 1 ,10024   ,90,90,90
BEGIN DESCRIPTION:
Mapping XS 7987b10f
END DESCRIPTION:
XS GIS Cut Line= 2
      2340924.25     13223732.47      2341279.68     13224382.66
#Sta/Elev= 30
  4683.9  124.06  4725.6  124.65  4734.5  121.49  4747.4   120.8  4785.4  120.58
  4823.3  119.33  4850.8  119.02  4866.9  118.21  4882.6   118.7  4888.8  117.39
  4894.5  117.72  4916.8  117.32  4944.5  115.89  4962.4  115.15  4970.4  114.03
  4992.2  112.68    5011  112.56  5013.7  112.06    5017  112.56  5019.1  112.81
  5030.1  113.07  5042.2  115.22  5057.6   115.8  5087.8  117.75  5133.4  117.98
  5315.7  122.04  5329.9  122.85    5384  123.38  5411.5  124.87  5424.9   124.8
#Mann= 5 ,-1 , 0
  4683.9     .05       0  4944.5      .1       0    5011     .07       0
    5017      .1       0  5019.1     .05       0
Bank Sta=4916.8,5087.8
XS Rating Curve= 0 ,0
Exp/Cntr=0.3,0.1

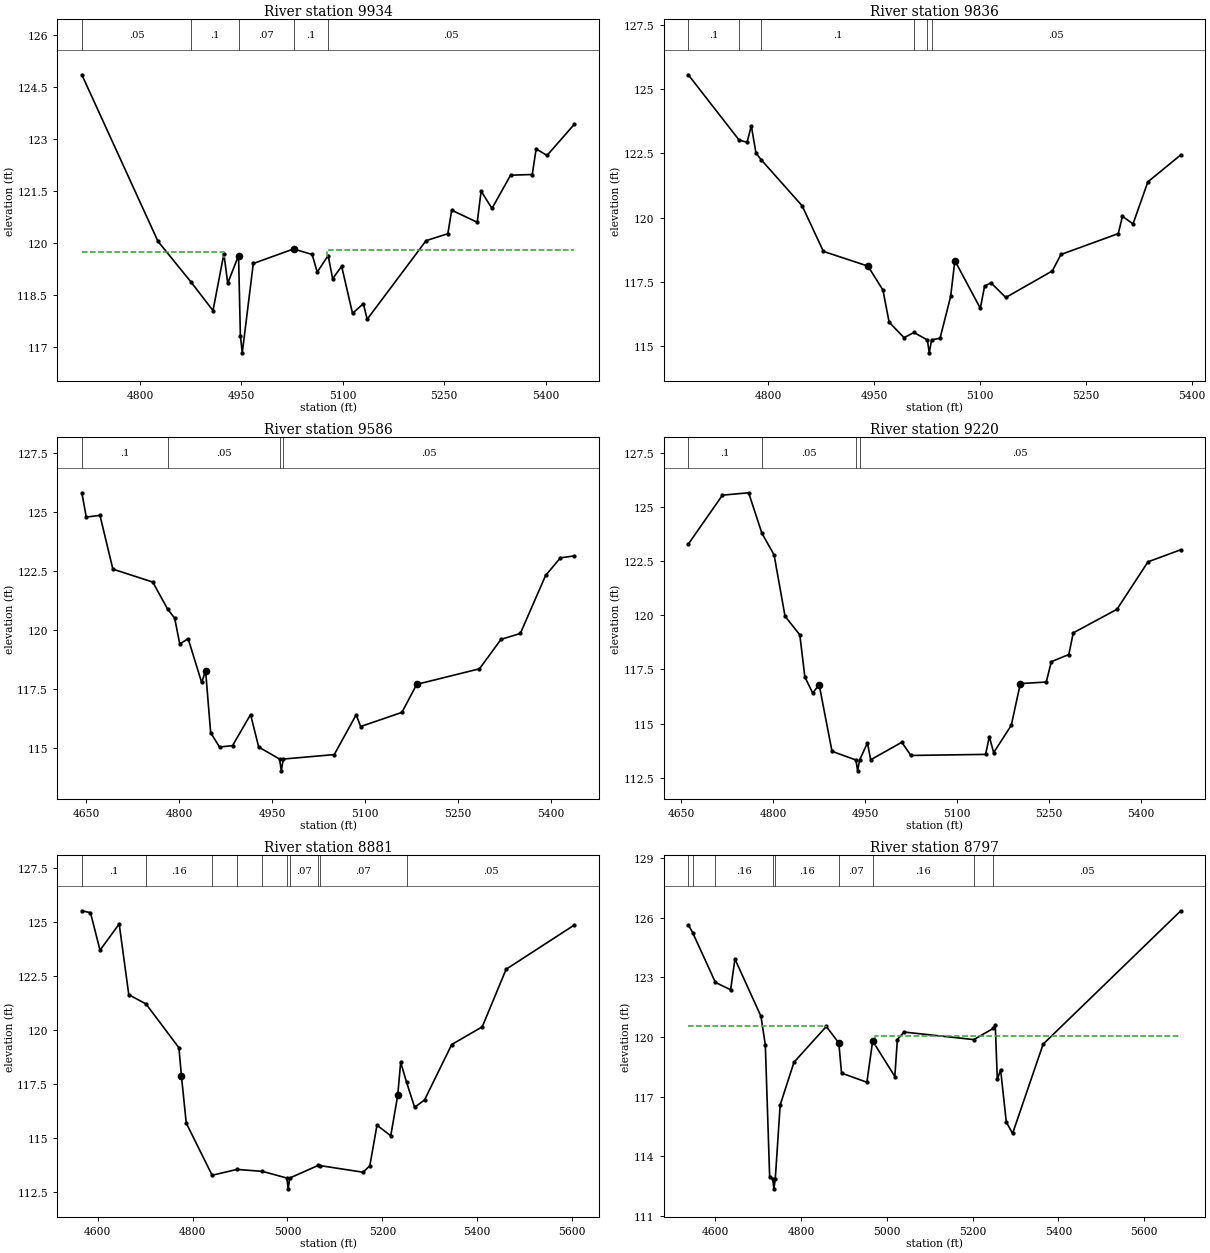
Type RM Length L Ch R = 1 ,9934    ,98,98,98
BEGIN DESCRIPTION:
Mapping XS 9ba76924
END DESCRIPTION:
XS GIS Cut Line= 2
      2340859.13     13223801.89      2341210.71     13224439.94
#Sta/Elev= 30
  4714.1  124.85  4826.7  120.04  4875.8  118.86  4908.1  118.04  4924.2  119.68
  4929.9  118.83  4945.9  119.63  4948.6  117.32  4951.4  116.82  4967.7   119.4
  5027.3  119.82  5054.8  119.66  5062.3  119.15  5078.4  119.63  5085.1  118.96
  5098.4  119.32  5114.5  117.96  5130.5  118.24  5136.2  117.79  5223.3  120.06
  5255.5  120.26  5261.2  120.94    5299  120.59  5304.7  121.49  5320.8  120.99
  5348.3  121.95  5380.4  121.97  5386.1  122.71  5402.2  122.52  5442.6  123.42
#Mann= 5 ,-1 , 0
  4714.1     .05       0  4875.8      .1       0  4945.9     .07       0
  5027.3      .1       0  5078.4     .05       0
#XS Ineff= 2 , 0
       0    4925  119.72 5077.22       0  119.78
Permanent Ineff=
       T       T
Bank Sta=4945.9,5027.3
XS Rating Curve= 0 ,0
Exp/Cntr=0.3,0.1

Type RM Length L Ch R = 1 ,9836    ,250,250,250
BEGIN DESCRIPTION:
Mapping XS d891ee54
END DESCRIPTION:
XS GIS Cut Line= 2
      2340763.65       13223867.      2341149.94      13224448.6
#Sta/Elev= 30
  4686.5  125.55  4758.6  123.01  4769.8  122.93  4775.8  123.57  4782.4  122.51
  4789.8  122.25  4847.9  120.46    4878  118.69  4941.1  118.12  4962.4  117.19
  4971.2  115.94  4992.3  115.34  5006.4  115.54  5025.4  115.25  5028.1  114.75
  5031.4  115.25  5043.4  115.32  5058.4  116.94  5064.4  118.33  5100.5  116.48
  5106.5  117.34  5115.6  117.47  5136.6   116.9  5202.5  117.93  5214.8  118.57
    5296  119.38    5302  120.05    5317  119.76    5338  121.39  5384.7  122.44
#Mann= 6 ,-1 , 0
  4686.5      .1       0  4758.6     .05       0  4789.8      .1       0
  5006.4     .05       0  5025.4     .07       0  5031.4     .05       0
Bank Sta=4941.1,5064.4
XS Rating Curve= 0 ,0
Exp/Cntr=0.3,0.1

Type RM Length L Ch R = 1 ,9586    ,366,366,366
BEGIN DESCRIPTION:
JACK GREEN HOLLOW 14.0
END DESCRIPTION:
XS GIS Cut Line= 3
      2340562.98     13224031.27      2340852.98     13224406.71
      2341148.17     13224528.42
#Sta/Elev= 30
  4643.5  125.81  4650.6  124.78  4672.7  124.85  4693.5  122.57  4757.8  122.02
  4781.8  120.87  4793.1  120.49  4801.3  119.39  4814.8  119.62  4836.6  117.76
  4842.9  118.26  4851.1  115.63  4865.4  115.02  4886.4  115.08  4915.4   116.4
  4928.5  115.02  4962.2  114.51  4964.9  114.01  4968.2  114.51  5050.3   114.7
  5085.6  116.39  5092.8  115.89  5159.3  116.49  5183.2  117.68  5284.3  118.34
  5319.1  119.59  5350.2  119.84  5390.9   122.3  5414.8  123.05  5437.2  123.13
#Mann= 4 ,-1 , 0
  4643.5      .1       0  4781.8     .05       0  4962.2    .033       0
  4968.2     .05       0
Bank Sta=4842.9,5183.2
XS Rating Curve= 0 ,0
Exp/Cntr=0.3,0.1

Type RM Length L Ch R = 1 ,9220    ,339,339,339
BEGIN DESCRIPTION:
Mapping XS 0cad781c
END DESCRIPTION:
XS GIS Cut Line= 3
       2340324.4     13224033.63      2340428.59      13224361.8
      2340693.48     13224735.78
#Sta/Elev= 30
  4661.8  123.29  4717.4  125.55  4760.1  125.66  4781.6   123.8  4801.6  122.79
  4819.4  119.96  4843.5   119.1  4851.7  117.16  4864.5  116.41    4875   116.8
    4896  113.72    4935  113.32  4937.7  112.82    4941  113.32  4953.7  114.11
    4959  113.33  5009.7  114.14  5024.5  113.53  5146.3  113.58  5152.4   114.4
  5159.4  113.66  5188.1  114.92  5202.9  116.85  5245.1  116.92  5253.4  117.86
  5281.9  118.19  5289.1  119.19  5360.4  120.28  5410.9  122.47  5464.4  123.03
#Mann= 4 ,-1 , 0
  4661.8      .1       0  4781.6     .05       0    4935    .033       0
    4941     .05       0
Bank Sta=4875,5202.9
XS Rating Curve= 0 ,0
Exp/Cntr=0.3,0.1

Type RM Length L Ch R = 1 ,8881    ,84,84,84
BEGIN DESCRIPTION:
JACK GREEN HOLLOW 13.0
END DESCRIPTION:
XS GIS Cut Line= 4
      2339975.46     13224038.87      2340011.92     13224309.72
      2340209.84      13224611.8      2340537.74     13224846.87
#Sta/Elev= 30
  4566.7  125.52  4584.9  125.43    4605  123.69  4645.4  124.91  4665.6  121.63
  4701.9   121.2  4771.3  119.17  4776.6  117.85  4786.7  115.68  4841.3  113.26
  4893.8  113.53  4947.3  113.44  4998.8  113.13  5001.6  112.63  5004.8  113.13
  5065.2  113.72  5067.8  113.71  5159.4   113.4  5173.6   113.7  5188.7  115.58
  5217.7  115.09  5232.4  116.96  5238.6   118.5  5251.2  117.56    5268  116.41
  5288.9  116.75  5346.2  119.32  5410.5  120.14  5460.9  122.81  5604.6  124.86
#Mann= 10 ,-1 , 0
  4566.7      .1       0  4701.9     .16       0  4841.3     .07       0
  4893.8     .05       0  4947.3     .07       0  4998.8     .07       0
  5004.8     .07       0  5065.2     .05       0  5067.8     .07       0
  5251.2     .05       0
Bank Sta=4776.6,5232.4
XS Rating Curve= 0 ,0
Exp/Cntr=0.3,0.1

Type RM Length L Ch R = 1 ,8797    ,72,72,72
BEGIN DESCRIPTION:
Mapping XS 1b20d322
END DESCRIPTION:
XS GIS Cut Line= 4
       2339871.3     13224049.33      2339907.75     13224294.09
      2340157.75     13224689.93      2340506.74     13224945.16
#Sta/Elev= 30
  4537.3  125.65  4547.4  125.26  4600.5  122.75  4635.9  122.38    4646  123.93
  4706.7  121.04  4716.8   119.6  4726.9  112.96    4734  112.85  4736.8  112.35
    4740  112.85  4751.4  116.57  4783.6  118.73    4859  120.53  4888.1   119.7
  4894.5  118.18  4953.6  117.72    4967   119.8  5018.7  118.01  5024.6  119.87
  5039.9  120.25  5202.8  119.87  5247.9  120.43  5252.9  120.58  5257.6  117.86
  5265.3  118.35  5278.5  115.72  5293.2  115.14  5364.4  119.64  5685.3  126.36
#Mann= 9 ,-1 , 0
  4537.3     .05       0  4547.4      .1       0  4600.5     .16       0
    4734     .07       0    4740     .16       0  4888.1     .07       0
    4967     .16       0  5202.8     .07       0  5247.9     .05       0
#XS Ineff= 2 , 0
       0 4858.89  120.56 4973.61       0  120.04
Permanent Ineff=
       T       T
Bank Sta=4888.1,4967
XS Rating Curve= 0 ,0
Exp/Cntr=0.3,0.1

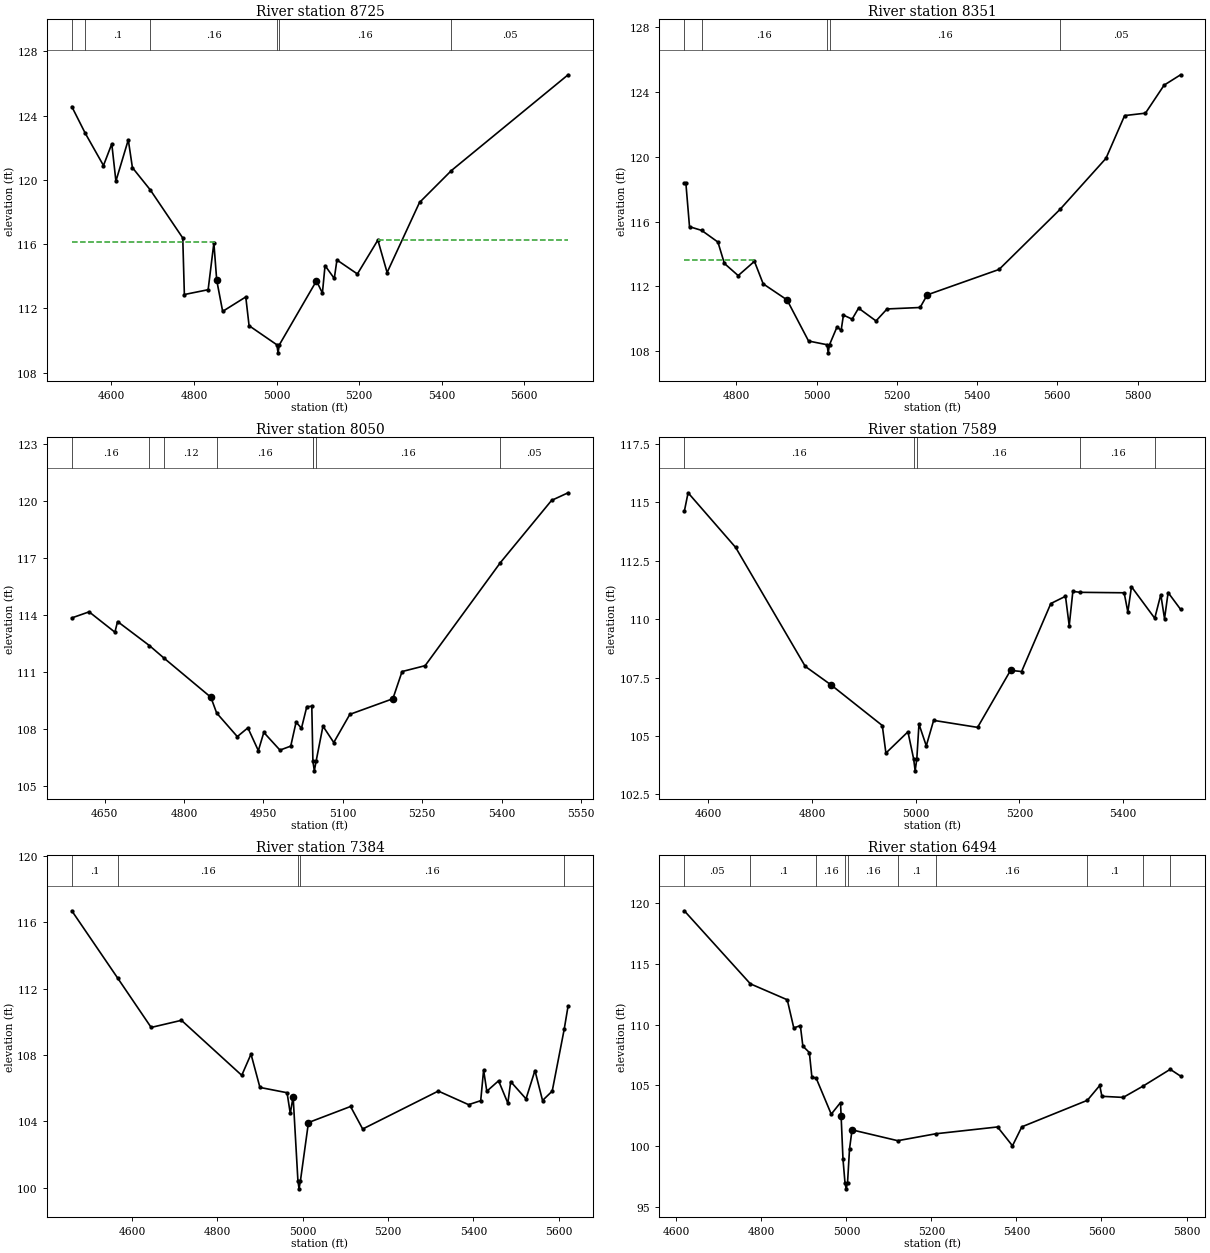
Type RM Length L Ch R = 1 ,8725    ,374,374,374
BEGIN DESCRIPTION:
JACK GREEN HOLLOW 12.0
END DESCRIPTION:
XS GIS Cut Line= 4
      2339803.59     13224070.16      2339819.21     13224335.76
      2340192.19     13224801.32      2340470.22      13224997.2
#Sta/Elev= 30
  4503.9  124.56  4536.5   122.9  4580.7  120.89  4600.8  122.24  4610.8  119.92
  4640.8  122.49  4650.8  120.76  4694.2  119.37  4772.8  116.38  4776.7  112.86
  4834.3  113.16  4848.2  116.07  4855.1  113.75  4869.5  111.81  4925.5  112.71
  4933.5  110.92  5000.9  109.73  5003.7  109.23  5006.9  109.73  5096.8  113.71
  5111.2  112.95  5117.6  114.66    5140  113.86  5146.4  115.01    5196  114.14
  5245.6  116.25    5268  114.23  5346.5  118.59  5423.9  120.58  5706.6  126.54
#Mann= 6 ,-1 , 0
  4503.9     .05       0  4536.5      .1       0  4694.2     .16       0
  5000.9     .07       0  5006.9     .16       0  5423.9     .05       0
#XS Ineff= 2 , 0
         4848.19  116.11 5245.83          116.24
Permanent Ineff=
       F       F
Bank Sta=4855.1,5096.8
XS Rating Curve= 0 ,0
Exp/Cntr=0.3,0.1

Type RM Length L Ch R = 1 ,8351    ,301,301,301
BEGIN DESCRIPTION:
JACK GREEN HOLLOW 11.0
END DESCRIPTION:
XS GIS Cut Line= 4
      2339597.71       13224304.      2339570.08     13224487.67
      2339739.35     13224791.49      2340381.74     13225077.96
#Sta/Elev= 30
  4670.4  118.36  4674.4  118.36  4683.4  115.69  4713.7  115.46  4754.2  114.74
  4770.3  113.42  4804.7  112.67  4845.2  113.55    4867  112.16  4926.4  111.17
  4980.1  108.63  5026.3   108.4    5029   107.9  5032.3   108.4    5051   109.5
  5061.3  109.29    5067  110.23  5088.7  109.98  5104.7  110.66  5148.2  109.87
  5175.7  110.61  5258.1   110.7  5275.9  111.48  5454.9  113.05  5607.3  116.77
  5721.3  119.91  5767.8  122.55  5819.7   122.7  5866.2  124.43  5907.3  125.07
#Mann= 5 ,-1 , 0
  4670.4     .16       0  4713.7     .16       0  5026.3     .07       0
  5032.3     .16       0  5607.3     .05       0
#XS Ineff= 2 , 0
       0 4846.12  113.64               0
Permanent Ineff=
       T       F
Bank Sta=4926.4,5275.9
XS Rating Curve= 0 ,0
Exp/Cntr=0.3,0.1

Type RM Length L Ch R = 1 ,8050    ,461,461,461
BEGIN DESCRIPTION:
Mapping XS 720964b6
END DESCRIPTION:
XS GIS Cut Line= 3
      2339465.19     13224404.15      2339454.83     13224761.43
      2339558.23     13225332.72
#Sta/Elev= 30
  4587.7  113.85  4620.4  114.17  4669.2   113.1  4674.2  113.66  4734.2   112.4
  4762.7  111.72  4850.5  109.68  4861.5  108.85  4900.5  107.61  4920.5  108.07
  4940.3  106.87  4950.6  107.83  4981.1   106.9  5001.5  107.11  5011.6  108.37
  5021.8  108.05  5031.9  109.19  5041.3   109.2  5043.4  106.31  5046.1  105.81
  5049.4  106.31  5062.4  108.16  5082.8   107.3  5113.2  108.78  5194.5   109.6
  5211.9  111.03  5255.5  111.34  5397.8  116.76  5494.5  120.03  5525.7  120.43
#Mann= 8 ,-1 , 0
  4587.7     .16       0  4734.2      .1       0  4762.7     .12       0
  4861.5     .16       0  5043.4      .1       0  5043.4     .07       0
  5049.4     .16       0  5397.8     .05       0
Bank Sta=4850.5,5194.5
XS Rating Curve= 0 ,0
Exp/Cntr=0.3,0.1

Type RM Length L Ch R = 1 ,7589    ,205,205,205
BEGIN DESCRIPTION:
JACK GREEN HOLLOW 10.0
END DESCRIPTION:
XS GIS Cut Line= 2
      2339383.89     13224512.83      2338698.14     13225181.22
#Sta/Elev= 30
  4553.5  114.61  4560.8  115.41  4652.6  113.07  4786.9  107.98  4836.5  107.19
  4935.5  105.45  4942.5  104.27    4985  105.18  4996.1  104.01  4998.9  103.51
  5002.1  104.01  5006.3  105.51  5020.4  104.58  5034.6  105.67  5119.4  105.37
    5183  107.81  5204.3  107.76  5260.7  110.67    5289  110.98  5296.2  109.72
  5303.2  111.19  5317.3  111.15  5402.2  111.13  5409.3  110.31  5416.3  111.39
  5461.2  110.04  5472.9  111.05  5480.1  110.02    5487  111.14  5511.1  110.42
#Mann= 5 ,-1 , 0
  4553.5     .16       0  4996.1     .07       0  5002.1     .16       0
  5317.3     .16       0  5461.2      .1       0
Bank Sta=4836.5,5183
XS Rating Curve= 0 ,0
Exp/Cntr=0.3,0.1

Type RM Length L Ch R = 1 ,7384    ,890,890,890
BEGIN DESCRIPTION:
JACK GREEN HOLLOW 9.0
END DESCRIPTION:
XS GIS Cut Line= 3
      2339244.97     13224391.34       2338518.3     13225204.16
      2338506.01     13225275.92
#Sta/Elev= 30
  4458.6   116.7  4566.6  112.62  4644.6  109.66  4715.6  110.09  4856.9  106.77
  4878.6  108.05  4899.5  106.04  4963.1  105.72  4970.6  104.47  4977.3  105.48
  4988.5  100.42  4991.2   99.92  4994.5  100.42  5013.2  103.92  5111.9  104.89
  5140.3  103.53  5317.5  105.82  5388.5     105  5416.9  105.24  5423.7  107.09
  5431.2  105.81  5458.8  106.44  5480.5  105.09  5487.2  106.39  5523.1  105.35
    5544  107.06  5561.8  105.25  5584.5  105.82  5612.5  109.54  5621.7  110.96
#Mann= 5 ,-1 , 0
  4458.6      .1       0  4566.6     .16       0  4988.5     .07       0
  4994.5     .16       0  5612.5      .1       0
Bank Sta=4977.3,5013.2
XS Rating Curve= 0 ,0
Exp/Cntr=0.3,0.1

Type RM Length L Ch R = 1 ,6494    ,570,570,570
BEGIN DESCRIPTION:
JACK GREEN HOLLOW 8.0
END DESCRIPTION:
XS GIS Cut Line= 4
      2337743.99     13224475.91       2338107.6     13224701.59
      2338515.11     13225047.98      2338482.61      13225250.1
#Sta/Elev= 30
  4618.6  119.36  4774.1  113.35  4860.8  112.04  4876.2  109.72  4891.6  109.92
  4897.5  108.23  4912.8   107.7  4918.7   105.7    4929  105.58  4964.3  102.63
  4986.1  103.59  4987.5  102.47  4991.9   98.94  4996.6   96.99  4999.4   96.49
  5002.6   96.99  5007.3   99.78  5013.2  101.34  5120.7  100.45  5210.3  101.02
  5355.5  101.58  5390.6  100.03  5412.6  101.59  5566.7  103.77  5595.9  104.99
    5601   104.1  5651.1  104.01  5697.8  104.94  5761.7  106.32  5786.1  105.76
#Mann= 10 ,-1 , 0
  4618.6     .05       0  4774.1      .1       0    4929     .16       0
  4996.6     .07       0  5002.6     .16       0  5120.7      .1       0
  5210.3     .16       0  5566.7      .1       0  5697.8     .16       0
  5761.7      .1       0
Bank Sta=4987.5,5013.2
XS Rating Curve= 0 ,0
Exp/Cntr=0.3,0.1