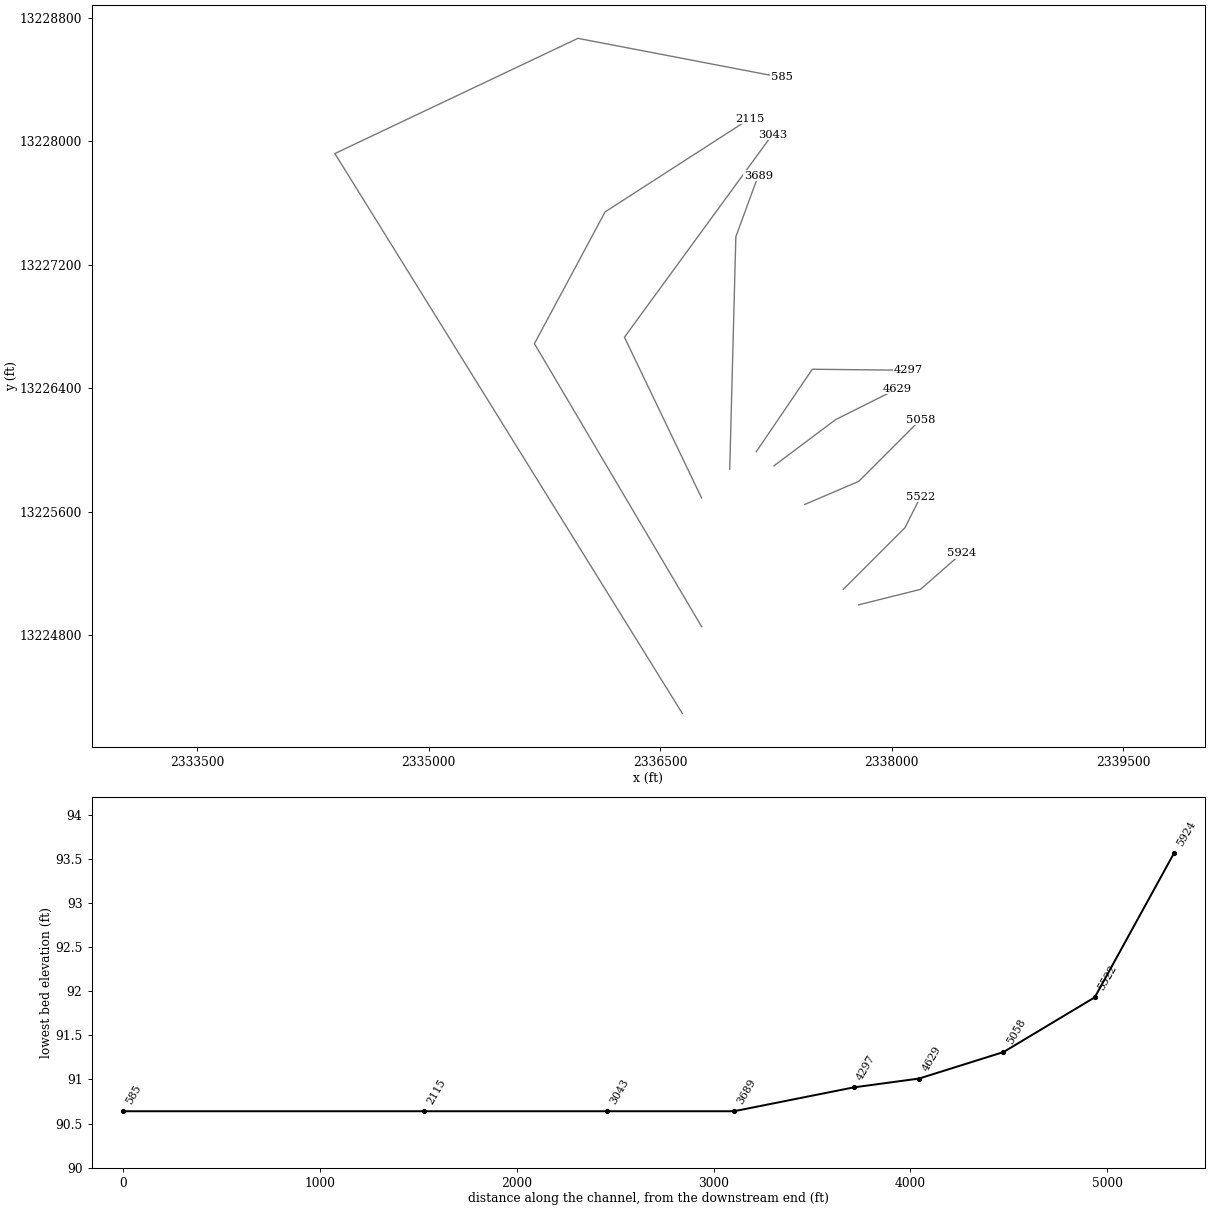
HEC-RAS study JACK GREEN HOLLOW.prj: JACK GREEN HOLLOW Base Level Engineering

--- JACK GREEN HOLLOW.g01 (geometry) --- (continued)

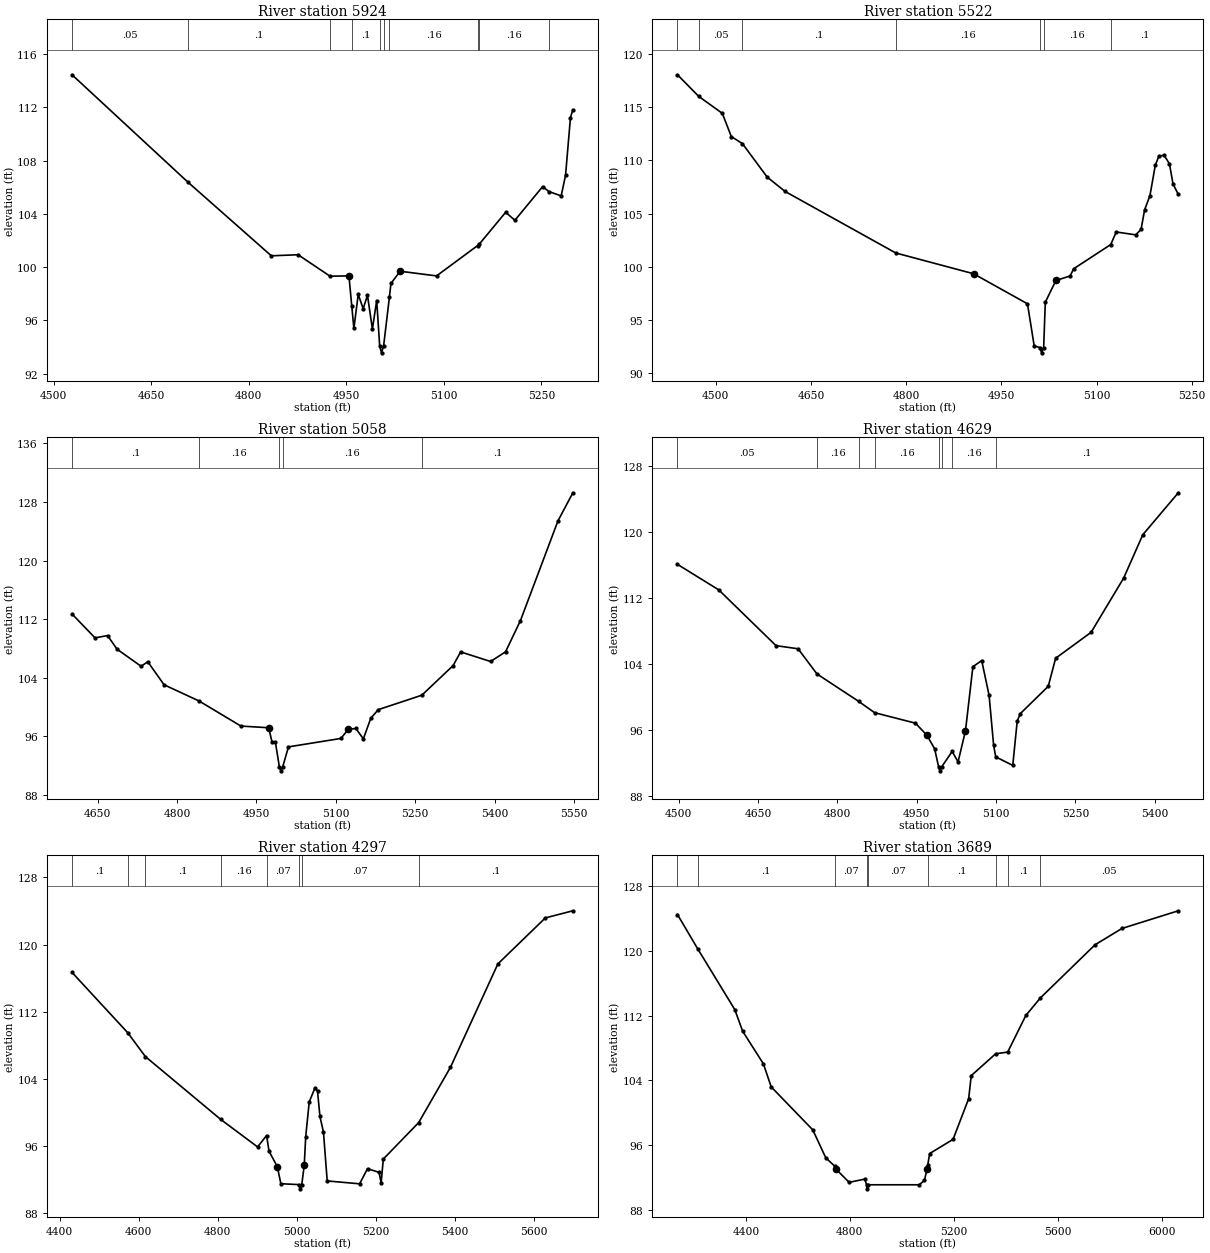
Type RM Length L Ch R = 1 ,5924    ,402,402,402
BEGIN DESCRIPTION:
JACK GREEN HOLLOW 7.0
END DESCRIPTION:
XS GIS Cut Line= 3
      2337787.77     13224996.87      2338187.72     13225096.85
      2338457.32     13225332.76
#Sta/Elev= 30
    4528  114.45  4705.7  106.41  4834.6  100.85  4875.8  100.93  4924.8   99.32
    4954   99.34  4958.3   97.11  4961.6   95.39  4968.3   97.95  4975.9   96.88
  4982.5   97.88  4990.1   95.35  4996.7   97.49  5001.3   94.06  5004.1   93.56
  5007.3   94.06  5016.3   97.76  5018.6   98.77  5032.8   99.69  5088.8   99.34
    5152  101.62  5154.6  101.73  5195.1  104.12  5209.3  103.52    5252  106.05
  5261.5  105.68  5280.5  105.35  5287.2  106.89  5294.8  111.24  5298.5  111.82
#Mann= 10 ,-1 , 0
    4528     .05       0  4705.7      .1       0  4924.8     .16       0
  4958.3      .1       0  5001.3     .07       0  5007.3      .1       0
  5016.3     .16       0    5152      .1       0  5154.6     .16       0
  5261.5      .1       0
Bank Sta=4954,5032.8
XS Rating Curve= 0 ,0
Exp/Cntr=0.3,0.1

Type RM Length L Ch R = 1 ,5522    ,464,464,464
BEGIN DESCRIPTION:
JACK GREEN HOLLOW 6.0
END DESCRIPTION:
XS GIS Cut Line= 3
      2337687.71     13225096.85      2338087.72     13225496.85
      2338187.72     13225696.85
#Sta/Elev= 30
  4439.6  118.02    4473     116  4510.3   114.4  4524.5  112.22    4542  111.56
    4581  108.42  4609.3  107.07  4783.6   101.3  4906.3   99.35  4991.2   96.53
  5001.8   92.58  5010.7   92.43  5013.4   91.93  5016.7   92.43  5019.3   96.68
    5036   98.72  5058.4   99.14    5064   99.82  5122.4  102.09  5131.1  103.27
  5161.8     103  5170.2  103.51  5175.8  105.35  5184.2  106.68  5192.6  109.52
  5198.2  110.38  5206.5  110.47  5214.9  109.67  5220.5  107.79  5228.9  106.79
#Mann= 7 ,-1 , 0
  4439.6      .1       0    4473     .05       0    4542      .1       0
  4783.6     .16       0  5010.7     .07       0  5016.7     .16       0
  5122.4      .1       0
Bank Sta=4906.3,5036
XS Rating Curve= 0 ,0
Exp/Cntr=0.3,0.1

Type RM Length L Ch R = 1 ,5058    ,429,429,429
BEGIN DESCRIPTION:
JACK GREEN HOLLOW 5.0
END DESCRIPTION:
XS GIS Cut Line= 3
      2337437.75     13225646.87      2337787.72     13225796.85
      2338187.69     13226196.83
#Sta/Elev= 30
  4601.5  112.71    4645  109.45  4668.6  109.77  4686.7   107.9    4732  105.58
  4744.7  106.19  4775.5  103.05  4841.6  100.84  4920.6   97.42  4973.2   97.19
  4979.5   95.21  4985.8   95.21  4993.4   91.81  4996.1   91.31  4999.4   91.81
  5010.5   94.58  5109.5   95.73  5123.7   96.98  5137.8   97.09    5152   95.68
  5166.1   98.49  5180.2   99.66  5262.5  101.63  5321.7  105.68  5335.8  107.54
  5392.4  106.23  5420.7  107.55  5448.9  111.82  5519.7  125.41  5547.9  129.25
#Mann= 5 ,-1 , 0
  4601.5      .1       0  4841.6     .16       0  4993.4     .07       0
  4999.4     .16       0  5262.5      .1       0
Bank Sta=4973.2,5123.7
XS Rating Curve= 0 ,0
Exp/Cntr=0.3,0.1

Type RM Length L Ch R = 1 ,4629    ,332,332,332
BEGIN DESCRIPTION:
JACK GREEN HOLLOW 4.0
END DESCRIPTION:
XS GIS Cut Line= 3
      2337237.75     13225896.88      2337637.72     13226196.85
      2338037.75     13226396.87
#Sta/Elev= 30
  4497.5  116.08  4575.6  112.98  4683.9  106.21  4725.6  105.83  4761.4  102.77
  4840.3   99.44  4870.3   98.07  4947.5    96.8  4969.3   95.33  4983.9   93.68
  4991.3   91.51  4994.1   91.01  4997.3   91.51    5017   93.36  5028.2    92.1
  5042.2   95.87  5056.2  103.65  5072.9   104.4  5086.9  100.16  5095.3    94.2
  5099.3   92.71  5131.6   91.67    5140   97.02  5145.6   97.94  5198.7  101.27
  5212.7  104.68  5279.8  107.83  5341.3  114.41  5377.6  119.68  5444.7  124.77
#Mann= 8 ,-1 , 0
  4497.5     .05       0  4761.4     .16       0  4840.3      .1       0
  4870.3     .16       0  4991.3     .07       0  4997.3     .16       0
    5017     .16       0  5099.3      .1       0
Bank Sta=4969.3,5042.2
XS Rating Curve= 0 ,0
Exp/Cntr=0.3,0.1

Type RM Length L Ch R = 1 ,4297    ,608,608,608
BEGIN DESCRIPTION:
JACK GREEN HOLLOW 3.0
END DESCRIPTION:
XS GIS Cut Line= 3
      2337123.34     13225988.33      2337486.59     13226523.29
      2338107.42     13226516.69
#Sta/Elev= 30
  4431.6  116.68  4572.2  109.52  4617.2  106.66  4807.5   99.19  4901.2    95.9
    4924   97.26  4930.2   95.39  4951.2   93.54  4960.1   91.52    5007   91.41
  5009.8   90.91    5013   91.41 5019.31   93.73    5023   97.14  5031.9  101.26
  5046.3  102.91  5052.9  102.54    5059   99.53  5067.9   97.66  5077.4   91.85
  5159.4   91.51  5179.4   93.31  5208.8   92.87  5213.8    91.6  5219.4   94.46
  5308.9    98.8  5389.4  105.39  5509.4   117.7  5629.4  123.17  5699.1  124.02
#Mann= 8 ,-1 , 0
  4431.6      .1       0  4572.2     .05       0  4617.2      .1       0
  4807.5     .16       0    4924     .07       0    5007     .07       0
    5013     .07       0  5308.9      .1       0
#XS Ineff= 2 , 0
                          5047.5          102.84
Permanent Ineff=
       F       F
Bank Sta=4951.2,5019.31
XS Rating Curve= 0 ,0
Exp/Cntr=0.3,0.1

Type RM Length L Ch R = 1 ,3689    ,646,646,646
BEGIN DESCRIPTION:
JACK GREEN HOLLOW 2.0
END DESCRIPTION:
XS GIS Cut Line= 3
      2336951.64     13225876.04      2336991.27     13227381.84
      2337136.57     13227778.12
#Sta/Elev= 30
  4136.2  124.46  4213.8  120.25  4357.1  112.73  4387.1  110.08  4467.1  106.05
  4497.1  103.21  4657.2   97.91  4707.2   94.47  4742.1   93.42  4747.2   93.05
  4797.2   91.44  4857.3   91.84  4864.3   91.14    4867   90.64  4870.3   91.14
  5067.3   91.14  5087.3   91.69  5097.3   93.11  5099.8   93.58  5107.3   94.99
  5197.4   96.74  5257.4  101.76  5267.4   104.6  5361.3  107.29  5407.7   107.5
  5477.5  112.01  5533.4  114.17  5743.7  120.72  5847.5  122.74  6064.6  124.92
#Mann= 9 ,-1 , 0
  4136.2     .05       0  4213.8      .1       0  4742.1     .07       0
  4864.3     .07       0  4870.3     .07       0  5099.8      .1       0
  5361.3     .05       0  5407.7      .1       0  5533.4     .05       0
Bank Sta=4747.2,5097.3
XS Rating Curve= 0 ,0
Exp/Cntr=0.3,0.1

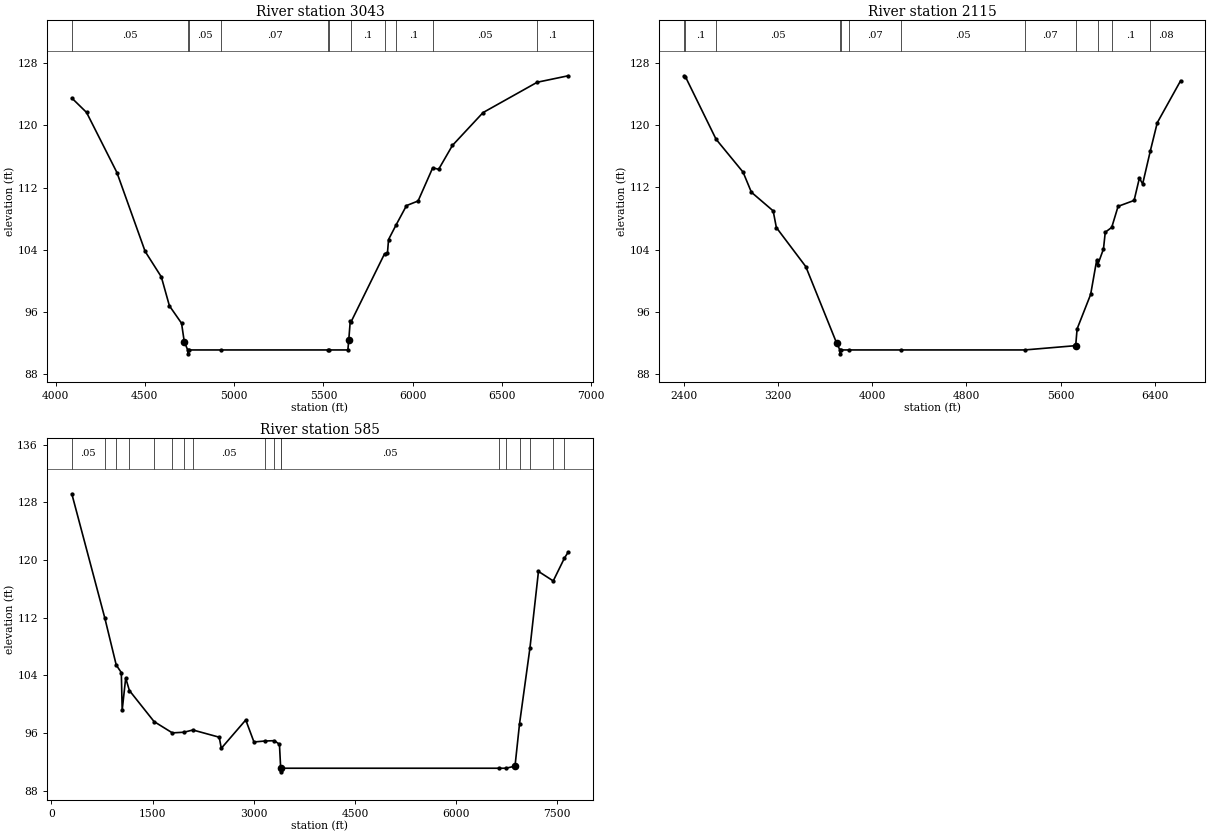
Type RM Length L Ch R = 1 ,3043    ,928,928,928
BEGIN DESCRIPTION:
Mapping XS 2e6ddd56
END DESCRIPTION:
XS GIS Cut Line= 3
      2336769.28     13225689.09       2336269.3     13226730.73
      2337227.13     13228042.54
#Sta/Elev= 30
  4091.1  123.51  4173.7  121.66  4343.7  113.94  4501.8   103.8  4592.4  100.53
  4637.7   96.81  4705.7   94.57  4720.9    92.2  4740.1   91.14  4742.8   90.64
  4746.1   91.14  4929.3   91.14  5524.4   91.14  5530.5   91.14  5637.1   91.14
 5641.96    92.4  5650.3   94.81  5655.6   94.78  5842.5   103.5  5858.7  103.59
  5864.9  105.33  5905.6  107.14  5965.3  109.69  6030.2  110.28  6112.3  114.55
  6145.3  114.35  6222.5  117.42    6394  121.64  6697.4  125.54  6870.8  126.37
#Mann= 11 ,-1 , 0
  4091.1     .05       0  4740.1     .07       0  4746.1     .05       0
  4929.3     .07       0  5524.4     .05       0  5530.5     .07       0
  5655.6      .1       0  5842.5     .08       0  5905.6      .1       0
  6112.3     .05       0  6697.4      .1       0
Bank Sta=4720.9,5641.96
XS Rating Curve= 0 ,0
Exp/Cntr=0.3,0.1

Type RM Length L Ch R = 1 ,2115    ,1530,1530,1530
BEGIN DESCRIPTION:
Mapping XS bdd59819
END DESCRIPTION:
XS GIS Cut Line= 4
      2336769.29     13224855.73      2335685.96     13226689.06
       2336144.3     13227543.23      2337081.83     13228147.41
#Sta/Elev= 30
  2403.6  126.31  2414.5  126.17  2674.1  118.17  2903.3  113.95  2974.1  111.37
  3158.8  108.98    3186  106.84  3435.8  101.83  3697.1   92.04  3725.4   91.14
  3728.1   90.64  3731.4   91.14  3802.1   91.14  4247.9   91.14  5294.9   91.14
  5727.2   91.69  5739.2   93.84  5854.1   98.26  5905.6  102.67  5913.5  102.03
    5963  104.09  5978.2  106.24  6033.1  106.86  6087.1  109.56  6223.1  110.32
  6267.9  113.18  6295.7  112.44  6361.3   116.7  6419.8  120.29  6617.8  125.67
#Mann= 12 ,-1 , 0
  2403.6     .05       0  2414.5      .1       0  2674.1     .05       0
  3725.4    .033       0  3731.4     .05       0  3802.1     .07       0
  4247.9     .05       0  5294.9     .07       0  5727.2      .1       0
  5913.5     .08       0  6033.1      .1       0  6361.3     .08       0
Bank Sta=3697.1,5727.2
XS Rating Curve= 0 ,0
Exp/Cntr=0.3,0.1

Type RM Length L Ch R = 1 ,585     ,0,0,0
BEGIN DESCRIPTION:
JACK GREEN HOLLOW 1.0
END DESCRIPTION:
XS GIS Cut Line= 4
      2336644.31      13224293.2       2334392.9     13227921.04
      2335967.96     13228667.68       2337290.5     13228413.92
#Sta/Elev= 30
     302  129.18   791.7  111.95   960.6  105.45    1036   104.4  1049.1   99.21
  1101.1  103.64  1155.9  101.91  1521.5   97.61  1792.8   96.04  1964.5   96.13
  2097.7   96.44  2487.7   95.44  2518.4    93.9    2881   97.83  3002.6   94.78
  3163.1   94.91  3304.6   94.96  3380.6   94.46  3398.8   91.14  3401.6   90.64
  3404.8   91.14  6638.1   91.14  6738.7   91.14  6872.9   91.43  6939.7   97.28
  7094.6  107.82  7220.7  118.42  7439.7   117.1    7605  120.25  7661.4   121.1
#Mann= 18 ,-1 , 0
     302     .05       0   791.7      .1       0   960.6      .1       0
  1155.9     .05       0  1521.5     .08       0  1792.8     .05       0
  1964.5     .08       0  2097.7     .05       0  3163.1     .08       0
  3304.6     .07       0  3398.8    .033       0  3404.8     .05       0
  6638.1     .07       0  6738.7     .05       0  6939.7     .08       0
  7094.6      .1       0  7439.7     .08       0    7605      .1       0
Bank Sta=3398.8,6872.9
XS Rating Curve= 0 ,0
Exp/Cntr=0.3,0.1

Chan Stop Cuts=-1
Use User Specified Reach Order=0
Composite Channel Slope=5