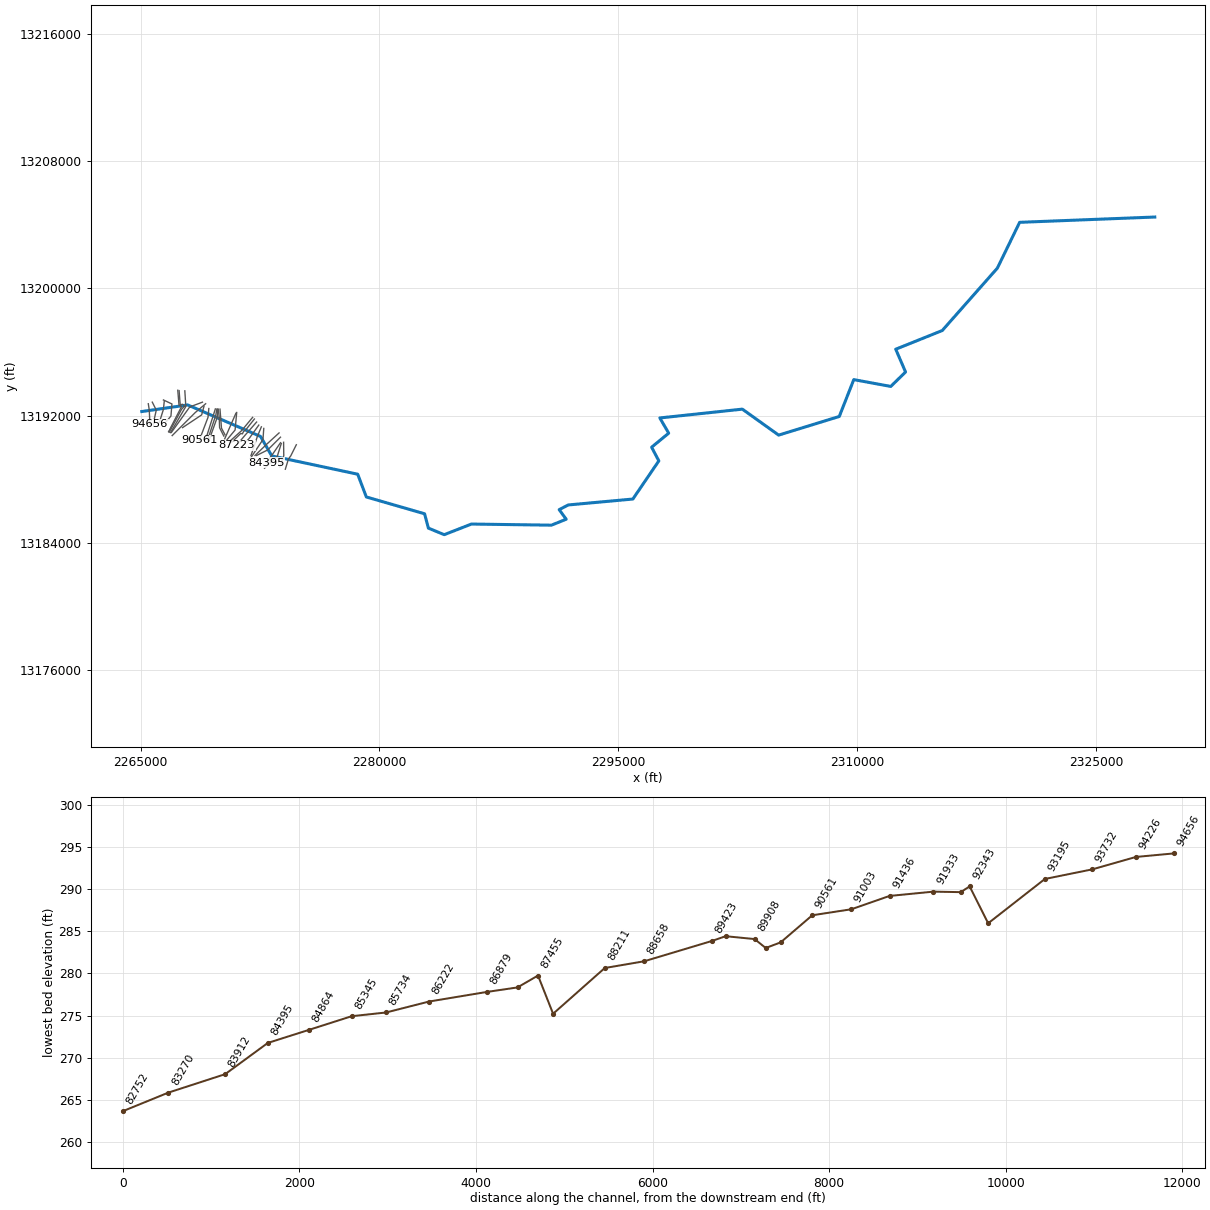
--- PENITAS CREEK.prj (project) ---

Proj Title=PENITAS CREEK Base Level Engineering
Current Plan=p01
Default Exp/Contr=0.3,0.1
English Units
Geom File=g01
Flow File=f01
Plan File=p01
Y Axis Title=Elevation
X Axis Title(PF)=Main Channel Distance
X Axis Title(XS)=Station
BEGIN DESCRIPTION:
PENITAS CREEK
END DESCRIPTION:
DSS Export Rating Curves= 0
DSS Export Rating Curve Sorted= 0
DSS Export Volume Flow Curves= 0
DXF OffsetX= 0
DXF OffsetY= 0
DXF ScaleX= 1
DXF ScaleY= 10

--- PENITAS CREEK.p01 (plan) ---

Plan Title=Multiple Run
Short Identifier=Multiple
Geom File=g01
Flow File=f01
Subcritical Flow
K Sum by GR= 0
Std Step Tol= 0.01
Critical Tol= 0.01
Num of Std Step Trials= 20
Max Error Tol= 0.3
Flow Tol Ratio= 0.001
Split Flow NTrial= 30
Split Flow Tol= 0.02
Split Flow Ratio= 0.02
Log Output Level= 0
Friction Slope Method= 1
Unsteady Friction Slope Method= 2
Unsteady Bridges Friction Slope Method= 1
Parabolic Critical Depth
Global Vel Dist=  1 , 1 , 1
Global Log Level= 0
CheckData=True
Encroach Param= -1, 0, 0, 0
BEGIN DESCRIPTION:
Multiple Run
END DESCRIPTION:

--- PENITAS CREEK.f01 (steady flow) ---

Flow Title=Multiple
Program Version=4.10
Number of Profiles= 7
Profile Names=10-year,25-year,50-year,1pct_min,100-year,1pct_plu,500-year
River Rch & RM=PENITAS CREEK,Reach-1         ,94656
     132     173     204     178     241     325     338
River Rch & RM=PENITAS CREEK,Reach-1         ,93195
     205     274     330     291     394     533     570
River Rch & RM=PENITAS CREEK,Reach-1         ,89423
     226     304     367     325     439     594     639
River Rch & RM=PENITAS CREEK,Reach-1         ,85734
     258     350     424     377     510     690     750
River Rch & RM=PENITAS CREEK,Reach-1         ,84395
     280     381     463     413     558     755     824
River Rch & RM=PENITAS CREEK,Reach-1         ,82752
     295     403     490     438     592     801     878
River Rch & RM=PENITAS CREEK,Reach-1         ,81490
     341     470     576     518     700     947    1051
River Rch & RM=PENITAS CREEK,Reach-1         ,77030
     413     574     708     640     865    1170    1313
River Rch & RM=PENITAS CREEK,Reach-1         ,76687
     514     721     894     812    1098    1485    1683
River Rch & RM=PENITAS CREEK,Reach-1         ,65891
     571     805    1001     913    1234    1669    1905
River Rch & RM=PENITAS CREEK,Reach-1         ,60498
     575     811    1008     919    1243    1681    1917
River Rch & RM=PENITAS CREEK,Reach-1         ,58874
     593     838    1043     952    1287    1741    1990
River Rch & RM=PENITAS CREEK,Reach-1         ,56863
     649     919    1148    1050    1420    1920    2206
River Rch & RM=PENITAS CREEK,Reach-1         ,55879
     693     984    1231    1128    1525    2063    2376
River Rch & RM=PENITAS CREEK,Reach-1         ,54444
     865    1240    1559    1435    1940    2624    3047
River Rch & RM=PENITAS CREEK,Reach-1         ,49724
     906    1300    1636    1506    2036    2754    3197
River Rch & RM=PENITAS CREEK,Reach-1         ,44979
    1039    1499    1893    1747    2363    3195    3730
River Rch & RM=PENITAS CREEK,Reach-1         ,42445
    1586    2320    2958    2752    3722    5034    5969
River Rch & RM=PENITAS CREEK,Reach-1         ,35338
    1967    2893    3702    3455    4672    6318    7525
River Rch & RM=PENITAS CREEK,Reach-1         ,26136
    2081    3059    3913    3647    4932    6670    7923
River Rch & RM=PENITAS CREEK,Reach-1         ,15426
    2635    3892    4993    4663    6307    8529   10158
River Rch & RM=PENITAS CREEK,Reach-1         ,9977
    3600    5356    6905    6472    8753   11838   14186
Boundary for River Rch & Prof#=PENITAS CREEK,Reach-1         , 1
Up Type= 0
Dn Type= 3
Dn Slope=0.00005
Boundary for River Rch & Prof#=PENITAS CREEK,Reach-1         , 2
Up Type= 0
Dn Type= 3
Dn Slope=0.00005
Boundary for River Rch & Prof#=PENITAS CREEK,Reach-1         , 3
Up Type= 0
Dn Type= 3
Dn Slope=0.00005
Boundary for River Rch & Prof#=PENITAS CREEK,Reach-1         , 4
Up Type= 0
Dn Type= 3
Dn Slope=0.00005
Boundary for River Rch & Prof#=PENITAS CREEK,Reach-1         , 5
Up Type= 0
Dn Type= 3
Dn Slope=0.00005
Boundary for River Rch & Prof#=PENITAS CREEK,Reach-1         , 6
Up Type= 0
Dn Type= 3
Dn Slope=0.00005
Boundary for River Rch & Prof#=PENITAS CREEK,Reach-1         , 7
Up Type= 0
Dn Type= 3
Dn Slope=0.00005
DSS Import GetInterval= 0
DSS Import GetPeak= 0
DSS Import FillOption= 0

--- PENITAS CREEK.g01 (geometry) ---

Geom Title=Existing Conditions
Program Version=4.10

River Reach=PENITAS CREEK   ,Reach-1
Reach XY= 30
      2265079.83     13192257.88      2267959.86     13192672.85
      2272537.22     13190690.84      2273238.99     13189470.13
      2278636.34     13188319.47      2279178.67     13186889.34
      2282835.38     13185833.22       2283075.5     13184932.42
      2284068.77     13184519.79      2285778.91      13185187.5
      2290802.53     13185117.32      2291730.83     13185491.39
      2291287.84     13186091.82      2291855.81     13186387.04
      2295916.38     13186759.33      2297546.47     13189156.96
      2297093.75     13190014.93      2298165.16     13190898.26
      2297609.48     13191854.67      2302791.77     13192408.05
      2305072.42     13190777.16      2308877.84     13191947.21
      2309788.92     13194263.95      2312110.89     13193834.63
      2313039.41     13194741.17      2312423.23     13196173.38
       2315343.2     13197347.61      2318805.61     13201269.94
      2320204.06     13204147.62      2328689.38     13204480.23

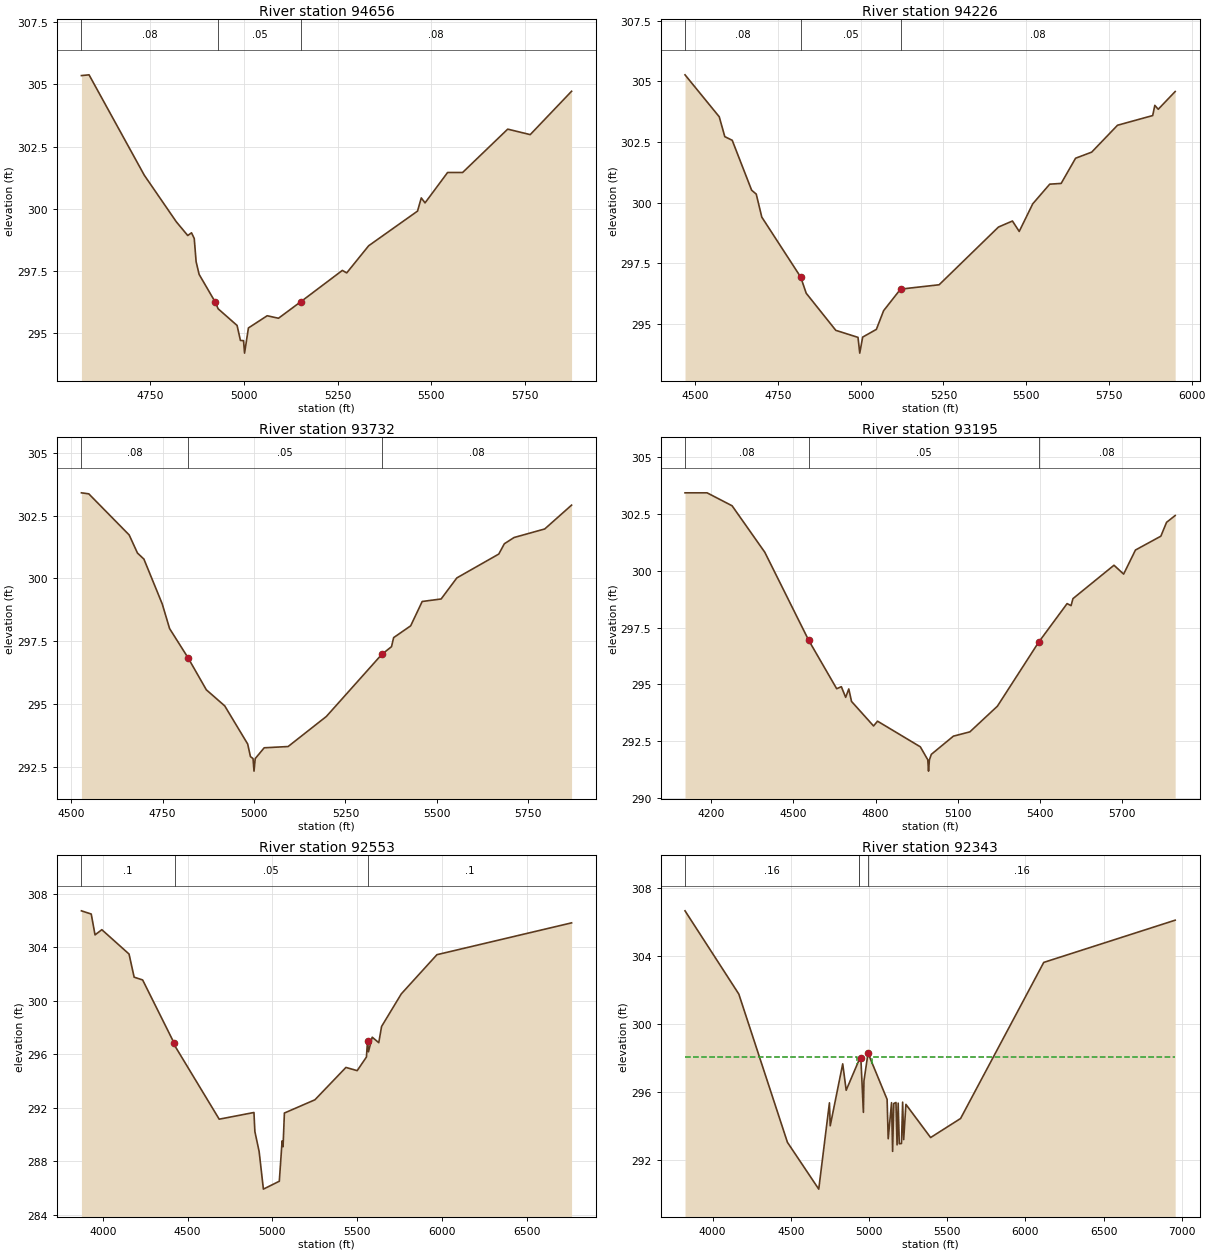
Type RM Length L Ch R = 1 ,94656   ,430,430,430
BEGIN DESCRIPTION:
PENITAS CREEK 168.0
END DESCRIPTION:
XS GIS Cut Line= 3
      2265487.72     13192746.88      2265551.27      13192324.3
      2265587.72     13191446.89
#Sta/Elev= 30
  4567.8  305.35  4588.1  305.38  4735.3  301.35  4820.6  299.48    4851  298.93
  4861.1  299.04  4868.3  298.81  4873.3  297.88  4881.3  297.37  4924.2  296.26
  4931.9  295.99  4982.4  295.32  4991.3  294.72  4999.6  294.71  5002.3  294.21
  5012.6  295.22  5062.6  295.71  5092.7  295.61  5152.7  296.28  5262.8  297.53
  5274.4  297.43  5332.9  298.52    5463  299.91    5473  300.44    5483  300.24
  5543.1  301.46  5583.1  301.46  5703.2   303.2  5763.2  302.98  5873.3  304.72
#Mann= 3 ,-1 , 0
  4567.8     .08       0  4931.9     .05       0  5152.7     .08       0
Bank Sta=4924.2,5152.7
XS Rating Curve= 0 ,0
Exp/Cntr=0.3,0.1

Type RM Length L Ch R = 1 ,94226   ,494,494,494
BEGIN DESCRIPTION:
PENITAS CREEK 167.0
END DESCRIPTION:
XS GIS Cut Line= 3
      2265737.71     13192846.87      2265987.72     13192346.85
      2265787.72     13191446.84
#Sta/Elev= 30
  4469.2  305.27  4572.6  303.54  4589.4  302.72  4611.8  302.57  4670.5  300.51
  4684.4  300.35  4701.2   299.4  4818.6  296.93  4835.4  296.26  4924.8  294.73
  4991.9  294.44  4997.2  293.79  5005.9  294.45  5047.4  294.77  5069.2  295.54
  5120.4  296.43    5237  296.61  5416.2  298.99  5458.5  299.24    5479  298.81
  5519.9  299.95  5571.2  300.76  5605.7  300.79  5649.3  301.83  5697.9  302.08
    5776  303.19  5882.3  303.59  5888.7  304.01    5899  303.85  5950.2  304.58
#Mann= 3 , 0 , 0
  4469.2     .08       0  4818.6     .05       0  5120.4     .08       0
Bank Sta=4818.6,5120.4
XS Rating Curve= 0 ,0
Exp/Cntr=0.3,0.1

Type RM Length L Ch R = 1 ,93732   ,537,537,537
BEGIN DESCRIPTION:
PENITAS CREEK 166.0
END DESCRIPTION:
XS GIS Cut Line= 3
      2266487.72     13192896.86      2266437.72     13192396.85
      2266187.71     13191596.81
#Sta/Elev= 30
  4527.9  303.41    4548  303.37  4658.6  301.73  4681.2  301.01  4698.8  300.77
    4749  298.98  4769.1     298  4819.4  296.84  4869.6  295.56  4919.9  294.92
  4982.7   293.4  4990.2   292.9  4997.3  292.82    5000  292.32  5003.3  292.82
  5027.9  293.25  5093.3   293.3    5198   294.5  5349.4  296.97  5376.1  297.28
  5381.9  297.64  5428.5  298.11    5460  299.08  5511.8  299.18  5554.8  300.02
  5669.5  300.97  5684.7  301.38  5711.4  301.63  5795.2  301.97  5868.6  302.92
#Mann= 3 , 0 , 0
  4527.9     .08       0  4819.4     .05       0  5349.4     .08       0
Bank Sta=4819.4,5349.4
XS Rating Curve= 0 ,0
Exp/Cntr=0.3,0.1

Type RM Length L Ch R = 1 ,93195   ,642,642,642
BEGIN DESCRIPTION:
PENITAS CREEK 165.0
END DESCRIPTION:
XS GIS Cut Line= 4
      2266437.39     13192984.89      2266971.81     13192733.22
      2266909.63     13191977.93      2266632.31     13191638.22
#Sta/Elev= 30
  4105.5  303.44  4185.9  303.44  4277.1  302.87  4396.5  300.82  4556.1  296.95
  4658.5  294.81  4675.5   294.9  4691.2  294.43  4702.6   294.8  4712.6  294.25
  4792.9  293.17  4807.5  293.38  4963.5  292.25  4990.6  291.68  4993.3  291.18
  4996.6  291.68  5003.6  291.92  5083.9  292.72  5144.1  292.91  5244.4  294.04
  5394.9  296.86  5498.6  298.56    5513  298.47    5520  298.78  5669.5  300.25
  5704.7  299.86  5747.8  300.92  5840.4  301.53  5861.2  302.14  5892.6  302.44
#Mann= 3 , 0 , 0
  4105.5     .08       0  4556.1     .05       0  5394.9     .08       0
Bank Sta=4556.1,5394.9
XS Rating Curve= 0 ,0
Exp/Cntr=0.3,0.1

Type RM Length L Ch R = 1 ,92553   ,210,210,210
BEGIN DESCRIPTION:
PENITAS CREEK 164.0
END DESCRIPTION:
XS GIS Cut Line= 5
      2267337.72     13193596.85      2267416.58     13192642.86
      2267531.16      13192601.2      2267562.41     13192543.91
      2266760.33     13190991.83
#Sta/Elev= 30
  3873.2  306.74  3931.1   306.5  3953.5  304.94  3993.6  305.33  4154.1  303.51
  4184.2  301.78  4234.4  301.57  4419.7  296.86  4425.1  296.63    4686  291.16
    4891  291.66  4896.4  290.24  4921.6  288.74  4946.7  285.93  5040.6  286.52
  5057.1  289.54  5062.7   289.1  5070.6  291.62  5250.7  292.61  5433.6  295.03
  5500.1  294.79  5554.6  295.81  5560.9     297  5566.5   296.2  5588.6  297.29
  5627.3  296.88  5643.8  298.09  5760.2  300.53  5970.4  303.46  6764.7  305.84
#Mann= 3 ,-1 , 0
  3873.2      .1       0  4425.1     .05       0  5560.9      .1       0
Bank Sta=4419.7,5560.9
XS Rating Curve= 0 ,0
Exp/Cntr=0.3,0.1

Type RM Length L Ch R = 1 ,92343   ,101,101,101
BEGIN DESCRIPTION:
PENITAS CREEK 163.0
END DESCRIPTION:
XS GIS Cut Line= 6
      2267421.79     13193569.94       2267489.5     13192684.53
      2267645.75     13192715.78      2267749.91     13192585.57
      2267578.04     13192403.28      2266802.36     13190956.05
#Sta/Elev= 30
  3823.4  306.65  4167.5  301.76  4478.4  293.05  4678.7   290.3    4747  295.37
  4752.1  294.02    4832  297.66  4854.1  296.11  4934.3  297.84    4948     298
  4964.2  294.81  4967.8  296.66  4993.9  298.29  5115.9  295.57  5122.8  293.26
  5144.3  295.38  5151.1  292.52  5158.4  295.33  5172.6  295.39  5179.5   292.9
  5186.7  295.35  5193.6  292.97  5207.8  292.98  5215.1  295.41  5221.9  293.21
  5236.1  295.28  5394.1  293.33  5585.8  294.45  6117.7  303.62  6958.2   306.1
#Mann= 4 ,-1 , 0
  3823.4     .16       0  4934.3     .05       0  4934.3     .07       0
  4993.9     .16       0
#XS Ineff= 2 , 0
       0 4925.39  298.08 5021.64       0  298.08
Permanent Ineff=
       T       T
Bank Sta=4948,4993.9
XS Rating Curve= 0 ,0
Exp/Cntr=0.3,0.1

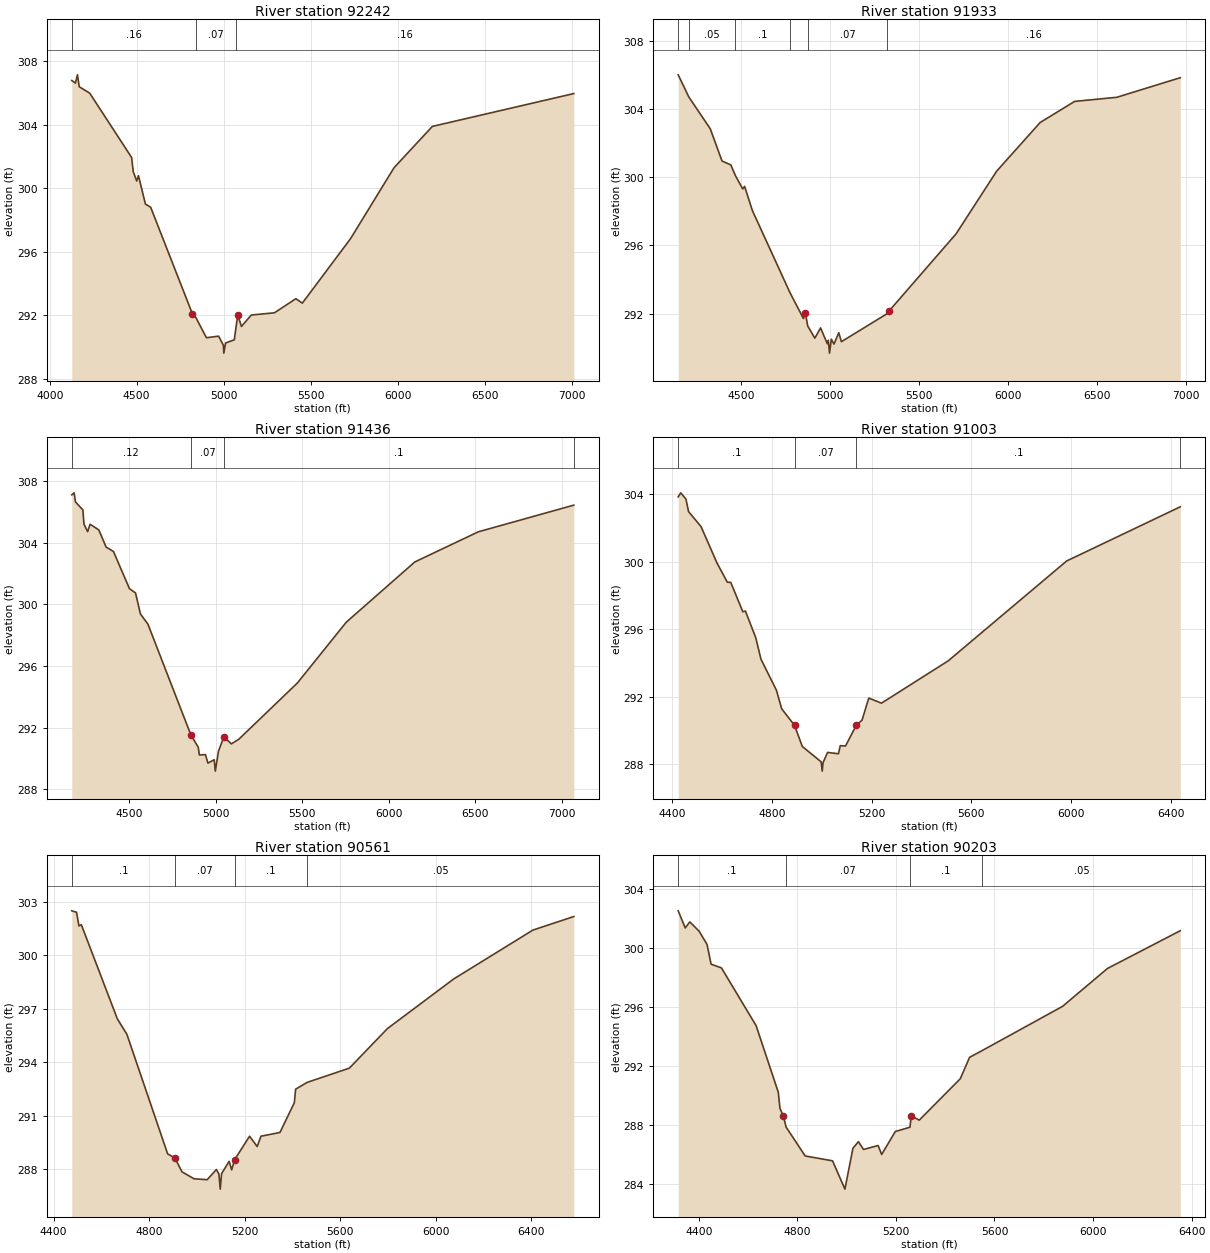
Type RM Length L Ch R = 1 ,92242   ,309,309,309
BEGIN DESCRIPTION:
Mapping XS 2a0e939c
END DESCRIPTION:
XS GIS Cut Line= 3
      2267781.16     13193559.54      2267843.66     13192575.16
      2266885.32     13190934.51
#Sta/Elev= 30
  4126.8  306.79  4147.9  306.63  4159.5  307.15  4169.6   306.4  4229.7     306
  4471.1  301.94  4480.2  301.05  4500.2  300.46  4510.3   300.8  4550.3  299.01
  4580.4  298.81  4820.9  292.08  4840.9  291.85    4901  290.59  4971.2  290.69
  4998.2  290.12    5001  289.62  5011.3  290.26  5061.4  290.46  5071.4  291.27
  5081.4  292.01  5102.4   291.3    5159  292.02  5292.1  292.16  5415.3  293.05
  5452.5  292.77  5730.2  296.84  5979.8   301.3  6199.7   303.9  7013.2  305.97
#Mann= 3 ,-1 , 0
  4126.8     .16       0  4840.9     .07       0  5071.4     .16       0
Bank Sta=4820.9,5081.4
XS Rating Curve= 0 ,0
Exp/Cntr=0.3,0.1

Type RM Length L Ch R = 1 ,91933   ,497,497,497
BEGIN DESCRIPTION:
PENITAS CREEK 162.0
END DESCRIPTION:
XS GIS Cut Line= 3
      2268887.69     13192846.84      2268087.72     13192546.85
       2266937.7     13190946.83
#Sta/Elev= 30
  4145.2  306.02    4205  304.72  4325.8  302.85  4391.7  300.96  4441.5  300.73
  4467.3   300.1  4508.3  299.32    4519  299.47  4562.6  298.05  4774.6  293.22
    4850  291.71  4860.7  292.04  4874.1  291.27  4914.1  290.56  4946.2  291.16
  4984.4  290.23  4989.8  290.43  4996.6  289.68  5006.9   290.5  5021.7  290.21
  5048.8  290.88  5063.4  290.35  5321.2     292  5329.8  292.13  5709.2  296.69
  5937.5  300.37  6181.8  303.22  6375.8  304.46  6612.7   304.7    6970  305.85
#Mann= 6 ,-1 , 0
  4145.2      .1       0    4205     .05       0  4467.3      .1       0
  4774.6     .16       0  4874.1     .07       0  5321.2     .16       0
Bank Sta=4860.7,5329.8
XS Rating Curve= 0 ,0
Exp/Cntr=0.3,0.1

Type RM Length L Ch R = 1 ,91436   ,433,433,433
BEGIN DESCRIPTION:
PENITAS CREEK 161.0
END DESCRIPTION:
XS GIS Cut Line= 3
       2269087.7     13192746.84      2268437.72     13192196.85
      2266987.69     13190746.83
#Sta/Elev= 30
  4166.8  307.11  4180.5  307.24  4188.2  306.65  4231.1  306.13  4237.6   305.2
  4258.5  304.72  4272.8   305.2  4323.4  304.83  4365.1  303.72  4407.9  303.43
  4500.2  301.02  4535.4  300.74  4563.9  299.37  4606.8  298.72  4855.1  291.53
    4898  290.72  4904.5  290.22  4939.7  290.24  4953.9  289.69  4990.3  289.91
  4996.6  289.17    5015  290.47  5046.5  291.41    5089  290.94  5131.4  291.23
  5470.8  294.89  5753.6  298.84  6149.6  302.75  6517.3  304.71  7068.9  306.44
#Mann= 4 ,-1 , 0
  4166.8     .12       0  4855.1     .07       0  5046.5      .1       0
  7068.9     .05       0
Bank Sta=4855.1,5046.5
XS Rating Curve= 0 ,0
Exp/Cntr=0.3,0.1

Type RM Length L Ch R = 1 ,91003   ,442,442,442
BEGIN DESCRIPTION:
PENITAS CREEK 160.0
END DESCRIPTION:
XS GIS Cut Line= 3
      2268987.71     13192596.83      2268837.72     13192046.85
      2267637.71     13191246.85
#Sta/Elev= 30
  4425.1  303.85  4435.4  304.09  4456.2  303.72  4466.5  302.98  4516.6  302.09
  4580.6  299.93    4622  298.79  4635.8  298.78  4684.2  297.04  4694.6  297.08
    4736   295.5  4756.8  294.23    4819  292.38  4839.7  291.29  4891.5   290.3
  4922.6  289.05  4998.2  288.14  5002.4  287.59  5005.7  288.09  5023.7   288.7
  5067.3  288.62  5074.8   289.1  5095.8  289.08  5139.4  290.32  5161.9  290.61
    5189  291.92    5240  291.62  5507.5  294.13  5982.2  300.05  6437.4  303.26
#Mann= 4 ,-1 , 0
  4425.1      .1       0  4891.5     .07       0  5139.4      .1       0
  6437.4     .05       0
Bank Sta=4891.5,5139.4
XS Rating Curve= 0 ,0
Exp/Cntr=0.3,0.1

Type RM Length L Ch R = 1 ,90561   ,358,358,358
BEGIN DESCRIPTION:
PENITAS CREEK 159.0
END DESCRIPTION:
XS GIS Cut Line= 3
      2269287.72     13192446.84      2269237.72     13191896.85
      2268687.71     13190446.81
#Sta/Elev= 30
  4475.8   302.5  4495.9  302.42  4505.9  301.65  4515.9  301.72  4666.6  296.44
  4706.7  295.57  4877.4  288.86  4907.6  288.63  4937.7  287.85  4987.9  287.46
  5043.1  287.41  5081.5  287.98  5092.2  287.73  5097.8  286.88  5103.4  287.75
    5135  288.44  5145.7  287.96  5158.3  288.54  5220.6  289.85  5252.6  289.27
  5268.2  289.85  5347.9  290.06  5408.2  291.73  5413.6  292.49  5461.6  292.87
  5638.6  293.67  5798.1  295.89  6076.2  298.68  6407.7  301.42  6578.9  302.18
#Mann= 4 ,-1 , 0
  4475.8      .1       0  4907.6     .07       0  5158.3      .1       0
  5461.6     .05       0
Bank Sta=4907.6,5158.3
XS Rating Curve= 0 ,0
Exp/Cntr=0.3,0.1

Type RM Length L Ch R = 1 ,90203   ,169,169,169
BEGIN DESCRIPTION:
Mapping XS a2381ceb
END DESCRIPTION:
XS GIS Cut Line= 2
      2269697.83     13192424.12      2269083.31     13190481.61
#Sta/Elev= 30
  4316.4  302.55    4345  301.39  4363.6   301.8  4401.2  301.17  4433.5  300.27
  4449.9  298.93  4491.8  298.68  4632.6  294.76  4722.6  290.24  4729.5  289.14
  4743.6  288.62    4754  287.89  4831.7  285.92  4942.8  285.59    4993  283.67
  5025.5  286.44  5047.7  286.89  5068.7  286.36  5127.7  286.63  5142.1  286.02
  5197.6  287.58    5257  287.87  5262.2  288.64  5294.5  288.35  5461.3  291.16
  5498.9  292.61  5551.1  293.08  5876.3  296.07  6058.6  298.64  6353.8   301.2
#Mann= 4 ,-1 , 0
  4316.4      .1       0    4754     .07       0    5257      .1       0
  5551.1     .05       0
Bank Sta=4743.6,5262.2
XS Rating Curve= 0 ,0
Exp/Cntr=0.3,0.1

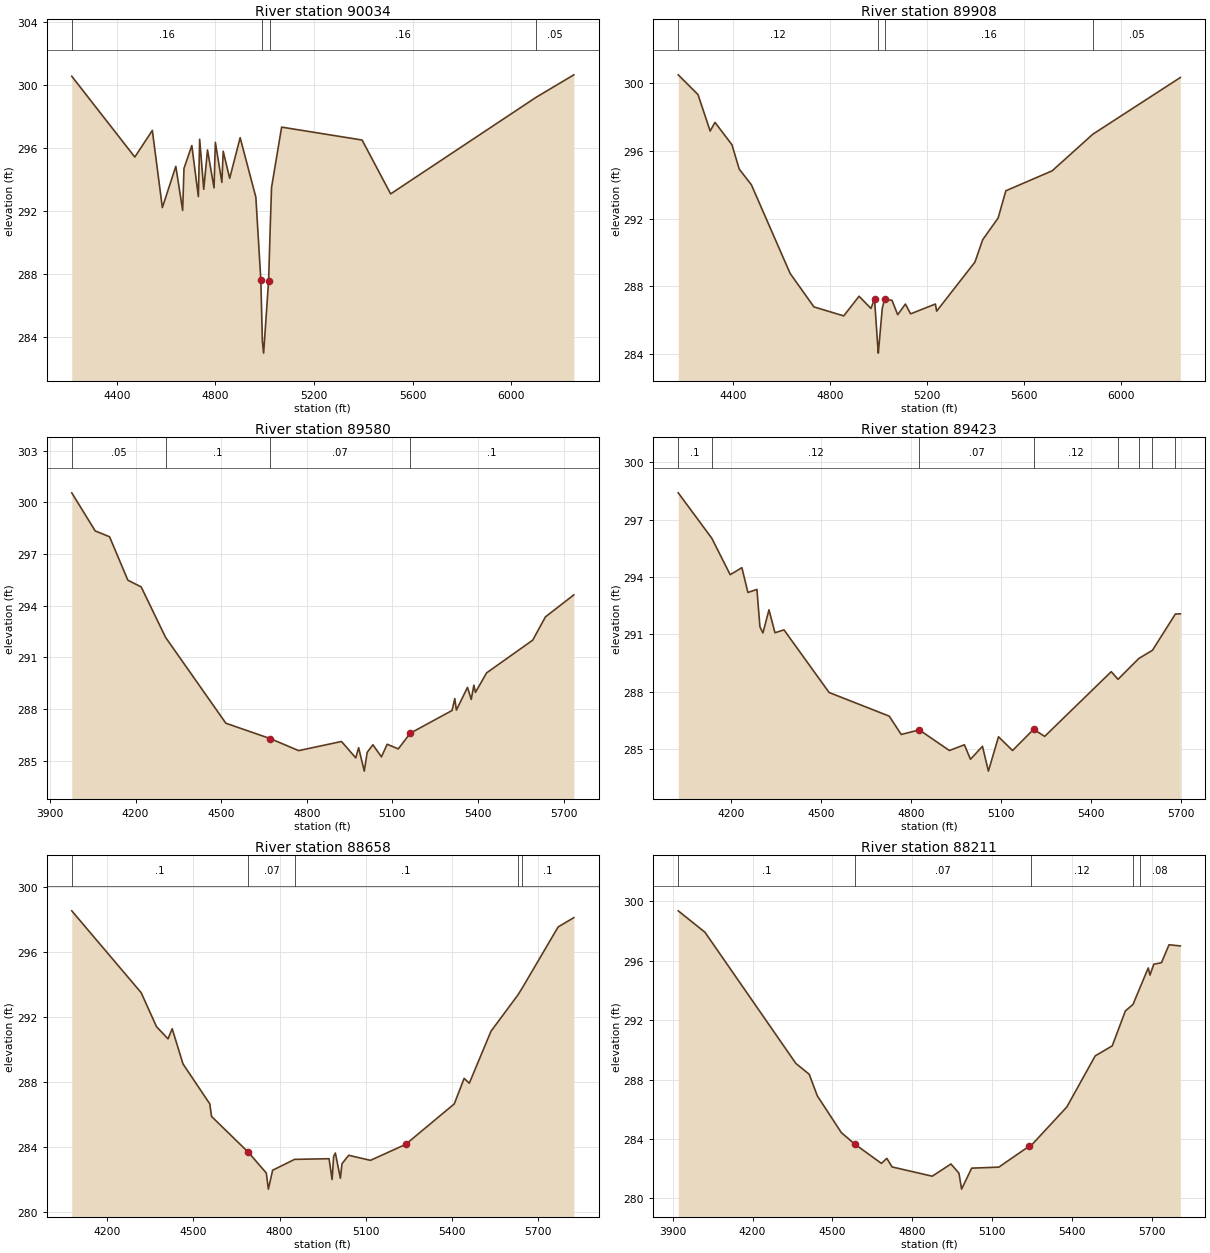
Type RM Length L Ch R = 1 ,90034   ,126,126,126
BEGIN DESCRIPTION:
PENITAS CREEK 158.0
END DESCRIPTION:
XS GIS Cut Line= 3
      2269791.58     13192408.49      2269723.87     13192028.28
      2269208.47     13190461.25
#Sta/Elev= 30
  4217.3  300.58  4472.9  295.45    4544  297.14  4584.6  292.24  4639.2  294.86
    4667  292.06  4672.3  294.73  4704.1  296.18  4730.6  292.94  4735.9  296.58
  4752.4   293.4  4767.7   295.9  4794.2  293.49  4799.5  296.38    4826  293.84
  4831.3  295.82  4857.6   294.1  4900.1  296.68  4963.7   292.9    4984  287.63
  4990.2  283.75  4995.2     283  5015.5  287.61    5022  290.98  5027.3  293.51
  5068.2  297.35  5394.5  296.53  5510.3  293.11  6099.8  299.24  6253.1  300.67
#Mann= 4 ,-1 , 0
  4217.3     .16       0  4990.2     .07       0    5022     .16       0
  6099.8     .05       0
Bank Sta=4984,5015.5
XS Rating Curve= 0 ,0
Exp/Cntr=0.3,0.1

Type RM Length L Ch R = 1 ,89908   ,328,328,328
BEGIN DESCRIPTION:
PENITAS CREEK 157.0
END DESCRIPTION:
XS GIS Cut Line= 3
      2269833.25      13192408.5      2269822.83     13191908.49
      2269291.58     13190429.32
#Sta/Elev= 30
    4173   300.5  4254.7  299.33  4304.7  297.18  4324.7  297.69  4394.7  296.37
  4424.7  294.93  4474.7  294.01  4634.7  288.77    4733  286.79  4855.9  286.26
  4919.2  287.42  4968.2   286.7    4983  287.25  4995.9  284.56  4998.6  284.06
  5014.9   286.7  5024.3  287.23  5055.1  287.18  5078.6  286.33  5110.5  286.96
  5131.8  286.38  5234.1  286.96  5239.4  286.54  5397.4  289.44  5429.3  290.76
    5493  292.04  5524.9  293.65  5716.1  294.83  5883.6  296.99  6244.8  300.34
#Mann= 4 ,-1 , 0
    4173     .12       0  4995.9     .07       0  5024.3     .16       0
  5883.6     .05       0
Bank Sta=4983,5024.3
XS Rating Curve= 0 ,0
Exp/Cntr=0.3,0.1

Type RM Length L Ch R = 1 ,89580   ,157,157,157
BEGIN DESCRIPTION:
Mapping XS a8d00905
END DESCRIPTION:
XS GIS Cut Line= 4
      2269880.12     13192408.47      2269942.62     13191872.03
      2269963.45     13191241.82      2270229.07      13190715.8
#Sta/Elev= 30
  3976.3  300.55  4058.5  298.34  4108.8     298  4172.9  295.48  4219.6  295.09
  4305.2  292.16  4516.4  287.18  4671.6  286.29  4771.7  285.59  4921.8  286.12
  4971.8  285.17  4981.8  285.76  5001.6   284.4  5011.8  285.49  5031.8  285.93
  5061.8  285.23  5081.9  285.96  5120.8  285.69  5162.8   286.6  5309.3  287.92
  5318.9  288.61  5324.5  287.94  5363.4  289.26  5376.5  288.56  5385.7  289.39
  5391.3  288.97  5430.3   290.1    5592     292  5636.6  293.35  5736.2  294.63
#Mann= 4 ,-1 , 0
  3976.3     .05       0  4305.2      .1       0  4671.6     .07       0
  5162.8      .1       0
Bank Sta=4671.6,5162.8
XS Rating Curve= 0 ,0
Exp/Cntr=0.3,0.1

Type RM Length L Ch R = 1 ,89423   ,765,765,765
BEGIN DESCRIPTION:
PENITAS CREEK 156.0
END DESCRIPTION:
XS GIS Cut Line= 3
      2269989.49     13192408.54      2270083.25     13191210.57
      2270307.22     13190793.88
#Sta/Elev= 30
  4022.9  298.41  4134.9  296.03  4196.3  294.12  4235.2  294.49  4255.3  293.19
  4285.4  293.35  4295.4  291.39  4305.4  291.07  4325.6  292.28  4345.6  291.08
  4375.7  291.23  4526.1  287.95  4726.7  286.71  4766.8  285.75    4827  285.99
  4927.3  284.91  4977.5  285.21  4997.6  284.45  5037.7  285.13  5057.5  283.83
  5091.2  285.63    5138  284.91  5208.2  286.02  5245.2  285.65  5467.2  289.04
  5489.9  288.64    5559  289.73  5604.7  290.16  5681.1  292.06  5697.6  292.07
#Mann= 8 ,-1 , 0
  4022.9      .1       0  4134.9     .12       0    4827     .07       0
  5208.2     .12       0  5489.9     .05       0    5559      .1       0
  5604.7     .05       0  5681.1     .08       0
Bank Sta=4827,5208.2
XS Rating Curve= 0 ,0
Exp/Cntr=0.3,0.1

Type RM Length L Ch R = 1 ,88658   ,447,447,447
BEGIN DESCRIPTION:
PENITAS CREEK 155.0
END DESCRIPTION:
XS GIS Cut Line= 3
      2270987.71     13192146.84      2270637.72     13191346.85
      2270287.72     13190546.86
#Sta/Elev= 30
  4077.1  298.54  4318.4  293.51  4371.8  291.42  4411.9  290.67  4426.4  291.29
  4464.2  289.12  4557.3  286.67  4563.2   285.9 4691.65  283.69  4753.8  282.42
    4761  281.43  4775.7  282.59  4852.1  283.26  4972.1   283.3  4982.6  282.02
  4988.1  283.45    4994  283.65  5011.5   282.1    5017  282.99  5040.3  283.51
    5116   283.2  5238.4  284.18  5407.6  286.67  5441.9  288.24  5459.8  287.94
  5535.4  291.14  5628.6  293.36  5643.9  293.79  5768.9  297.55  5823.5  298.12
#Mann= 5 ,-1 , 0
  4077.1      .1       0 4691.65     .07       0  4852.1      .1       0
  5628.6     .08       0  5643.9      .1       0
Bank Sta=4691.65,5238.4
XS Rating Curve= 0 ,0
Exp/Cntr=0.3,0.1

Type RM Length L Ch R = 1 ,88211   ,585,585,585
BEGIN DESCRIPTION:
PENITAS CREEK 154.0
END DESCRIPTION:
XS GIS Cut Line= 3
      2271037.72     13192196.84      2270937.72     13191096.85
      2270437.75     13190496.89
#Sta/Elev= 30
    3921  299.34  4021.4   297.9  4362.8  289.08    4413  288.35  4443.1  286.91
  4533.5  284.43  4583.7  283.66  4684.1  282.36  4704.2   282.7  4724.3  282.12
  4874.9   281.5  4945.2  282.32  4975.3   281.7  4985.1  280.63    5023  282.04
  5125.1  282.11  5238.3  283.51  5246.2  283.56  5380.2  286.15    5487  289.59
  5550.8  290.26  5600.2  292.61  5628.9  293.05  5654.5  294.15  5686.1   295.5
  5692.6  295.02    5707  295.75  5735.6  295.85  5764.2  297.06  5806.5  296.98
#Mann= 5 ,-1 , 0
    3921      .1       0  4583.7     .07       0  5246.2     .12       0
  5628.9      .1       0  5654.5     .08       0
Bank Sta=4583.7,5238.3
XS Rating Curve= 0 ,0
Exp/Cntr=0.3,0.1

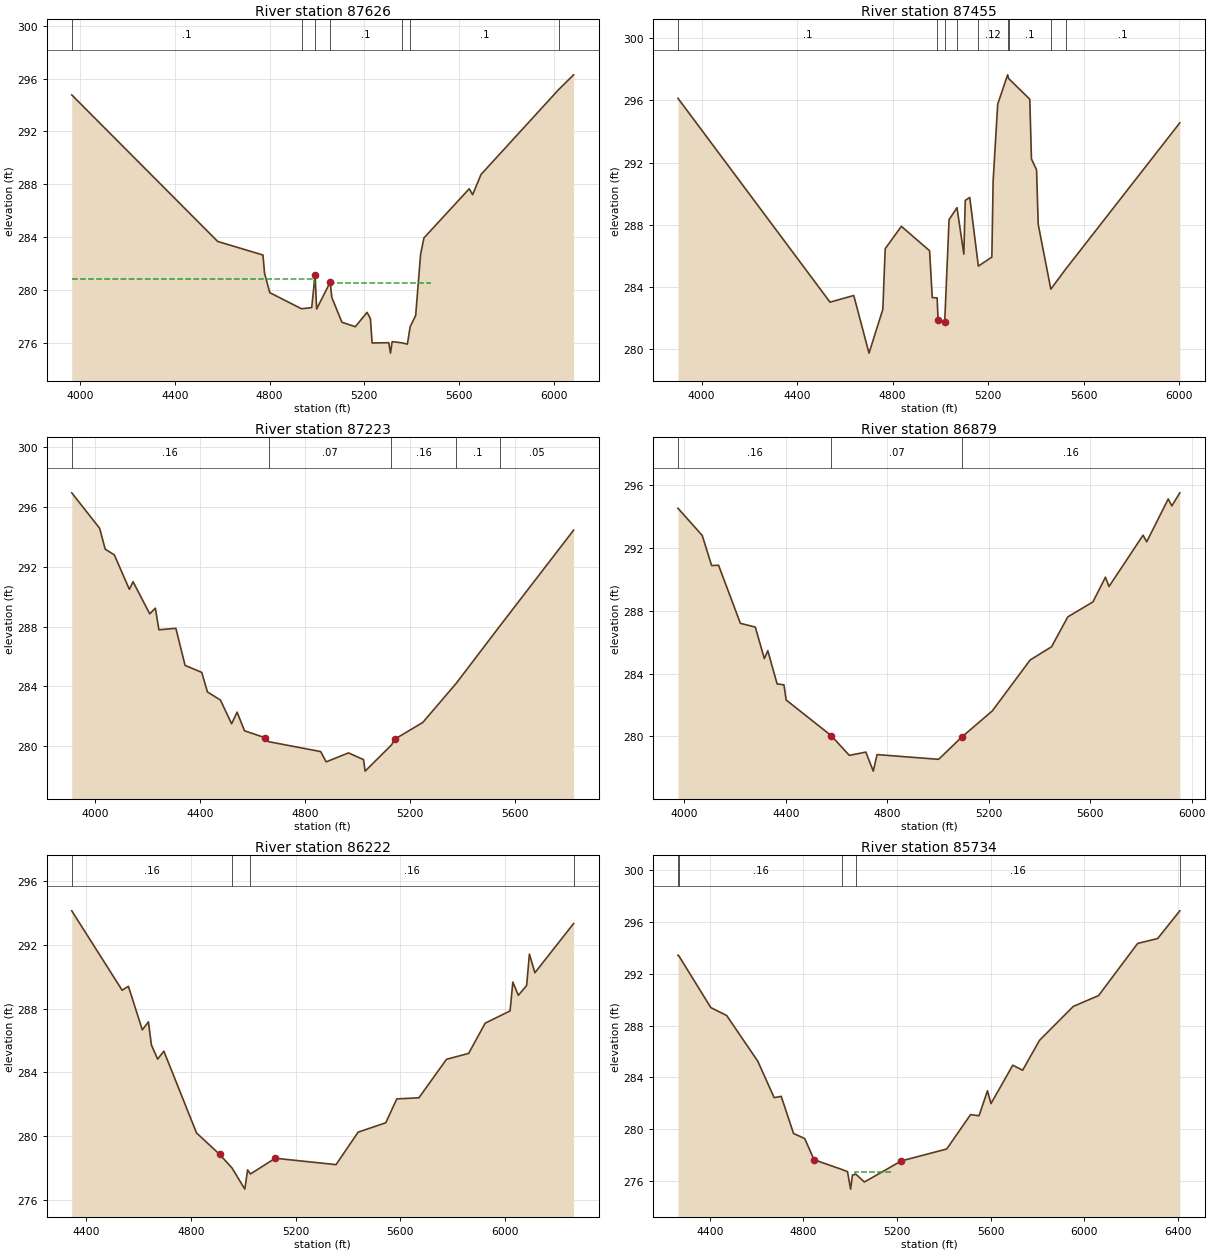
Type RM Length L Ch R = 1 ,87626   ,171,171,171
BEGIN DESCRIPTION:
Mapping XS b4a06297
END DESCRIPTION:
XS GIS Cut Line= 3
      2272038.99     13191892.88      2271354.95     13191066.47
      2270577.17     13190365.09
#Sta/Elev= 30
  3964.5  294.77    4581  283.67  4772.4  282.64  4778.9  281.27  4801.1  279.79
  4935.1  278.57  4978.2  278.66  4992.5  281.14    4999  278.55  5056.4  280.59
  5063.2  279.43  5105.8  277.55  5162.6  277.21  5211.9   278.3  5226.1  277.83
  5233.5  275.98  5303.8     276    5311  275.21    5318  276.08  5359.2  275.99
  5382.3  275.89  5394.2  277.21  5417.4  278.06  5438.3  282.71  5452.5  283.94
  5643.8  287.66    5658  287.21  5693.4  288.74  6020.8  295.16  6084.6  296.29
#Mann= 7 ,-1 , 0
  3964.5      .1       0  4935.1     .12       0  4992.5     .07       0
  5056.4      .1       0  5359.2     .12       0  5394.2      .1       0
  6020.8     .08       0
#XS Ineff= 2 ,-1
  3964.5 4988.07  280.85 5057.64 5481.57  280.51
Permanent Ineff=
       F       F
Bank Sta=4992.5,5056.4
XS Rating Curve= 0 ,0
Exp/Cntr=0.3,0.1

Type RM Length L Ch R = 1 ,87455   ,232,232,232
BEGIN DESCRIPTION:
PENITAS CREEK 153.0
END DESCRIPTION:
XS GIS Cut Line= 6
      2272150.11     13191788.73      2271608.42     13191108.14
       2271467.9     13191006.22      2271396.61     13190854.67
      2271292.45     13190878.97      2270731.37     13190335.21
#Sta/Elev= 30
  3901.2  296.14  4537.8  283.02  4637.1  283.45  4700.9  279.74  4758.8  282.56
  4768.7  286.46  4836.3   287.9  4954.5  286.33  4965.7  283.31  4986.1   283.3
 4989.88  281.88  5017.7  281.73    5036  288.33  5069.3   289.1  5097.8  286.11
  5103.8  289.57  5122.7  289.76  5158.6  285.34  5215.1  285.92  5220.4  290.79
  5239.6  295.76  5281.2  297.65  5285.5  297.41  5373.9  296.08  5380.9  292.23
  5402.2  291.54  5409.2  288.03    5462  283.86  5523.4  285.13  6001.9  294.56
#Mann= 9 ,-1 , 0
  3901.2      .1       0  4986.1     .07       0  5017.7     .12       0
  5069.3      .1       0  5158.6     .12       0  5281.2     .05       0
  5285.5      .1       0    5462     .05       0  5523.4      .1       0
#XS Ineff= 2 , 0
         4953.96  286.33
Permanent Ineff=
       F       F
Bank Sta=4989.88,5017.7
XS Rating Curve= 0 ,0
Exp/Cntr=0.3,0.1

Type RM Length L Ch R = 1 ,87223   ,344,344,344
BEGIN DESCRIPTION:
PENITAS CREEK 152.0
END DESCRIPTION:
XS GIS Cut Line= 3
       2272287.7     13191596.84      2271587.72     13190796.85
      2271037.69     13190146.82
#Sta/Elev= 30
    3910  296.96  4016.3  294.59  4037.6  293.19  4072.7   292.8  4129.7   290.5
  4143.9  291.01  4207.5  288.86  4228.9  289.24  4242.6  287.79  4307.2  287.89
  4342.3  285.41  4405.9  284.94  4427.7  283.63  4477.1  283.09  4519.8   281.5
  4540.7  282.28  4569.1  281.03    4647  280.57  4661.2   280.3  4859.6  279.64
  4880.5  278.95  4965.9  279.55    5023   279.1  5029.3  278.33  5129.6  280.08
  5143.3  280.48  5249.3  281.59  5376.4   284.2  5542.1  288.02  5824.5  294.46
#Mann= 5 ,-1 , 0
    3910     .16       0  4661.2     .07       0  5129.6     .16       0
  5376.4      .1       0  5542.1     .05       0
Bank Sta=4647,5143.3
XS Rating Curve= 0 ,0
Exp/Cntr=0.3,0.1

Type RM Length L Ch R = 1 ,86879   ,657,657,657
BEGIN DESCRIPTION:
PENITAS CREEK 151.0
END DESCRIPTION:
XS GIS Cut Line= 3
      2272424.19     13191404.65      2271826.03     13190571.67
       2271172.6      13189877.4
#Sta/Elev= 30
  3974.5   294.5  4070.3  292.77  4107.2  290.86  4134.6  290.88  4220.6  287.19
  4279.5  286.95  4315.1  284.95  4328.8  285.45  4365.5  283.34  4392.5  283.28
  4401.1  282.32  4579.1  280.05  4650.3   278.8  4715.4  279.01  4744.6   277.8
  4759.6  278.85  5002.4  278.55  5094.1  279.97  5214.3  281.63  5363.2  284.86
  5447.7   285.7  5511.7   287.6  5610.8  288.55  5660.2  290.12  5674.3  289.53
  5808.6  292.79  5822.8  292.37  5907.8  295.09  5921.9  294.65  5953.4  295.48
#Mann= 3 , 0 , 0
  3974.5     .16       0  4579.1     .07       0  5094.1     .16       0
Bank Sta=4579.1,5094.1
XS Rating Curve= 0 ,0
Exp/Cntr=0.3,0.1

Type RM Length L Ch R = 1 ,86222   ,488,488,488
BEGIN DESCRIPTION:
PENITAS CREEK 150.0
END DESCRIPTION:
XS GIS Cut Line= 3
      2272587.72     13191296.86      2272337.72     13190696.85
      2271937.73     13189496.87
#Sta/Elev= 30
  4345.9  294.15  4538.2  289.16    4562  289.41  4615.1  286.67  4638.4  287.17
  4649.8  285.72  4673.6  284.83  4697.4  285.33    4822  280.19  4909.8  278.85
  4957.4  277.99  5006.2  276.66    5017  277.87  5027.5  277.61  5122.4   278.6
  5354.3   278.2  5438.6  280.24    5544  280.83  5586.2  282.33  5670.5   282.4
  5775.9  284.82  5860.3  285.19  5923.5  287.09  6018.4  287.86  6028.9  289.67
    6050  288.84  6081.6  289.46  6092.2  291.43  6113.2  290.26  6260.8  293.35
#Mann= 4 ,-1 , 0
  4345.9     .16       0  4957.4     .07       0  5027.5     .16       0
  6260.8      .1       0
Bank Sta=4909.8,5122.4
XS Rating Curve= 0 ,0
Exp/Cntr=0.3,0.1

Type RM Length L Ch R = 1 ,85734   ,389,389,389
BEGIN DESCRIPTION:
PENITAS CREEK 149.0
END DESCRIPTION:
XS GIS Cut Line= 3
      2272737.72     13191196.88      2272687.72     13190496.85
      2271887.74     13189296.88
#Sta/Elev= 30
  4263.9  293.43  4266.4  293.43  4404.3  289.39    4472  288.78  4604.8  285.25
    4675  282.43    4705  282.53  4757.7  279.66  4805.3  279.27  4845.4  277.63
  4965.7  276.87  4988.2  276.71  5001.5  275.36  5009.3  276.45  5024.3  276.51
  5060.4  275.91  5218.1  277.54  5411.9  278.46  5514.1  281.12  5550.1  281.03
  5586.2  282.96  5601.2  281.97  5694.3  284.94  5736.4  284.55  5808.5  286.86
  5952.7  289.48  6060.9  290.32  6227.7  294.35  6313.3  294.73  6407.9  296.87
#Mann= 5 ,-1 , 0
  4263.9     .05       0  4266.4     .16       0  4965.7     .07       0
  5024.3     .16       0  6407.9     .08       0
#XS Ineff= 1 ,-1
 5022.01 5184.49   276.7
Permanent Ineff=
       F
Bank Sta=4845.4,5218.1
XS Rating Curve= 0 ,0
Exp/Cntr=0.3,0.1

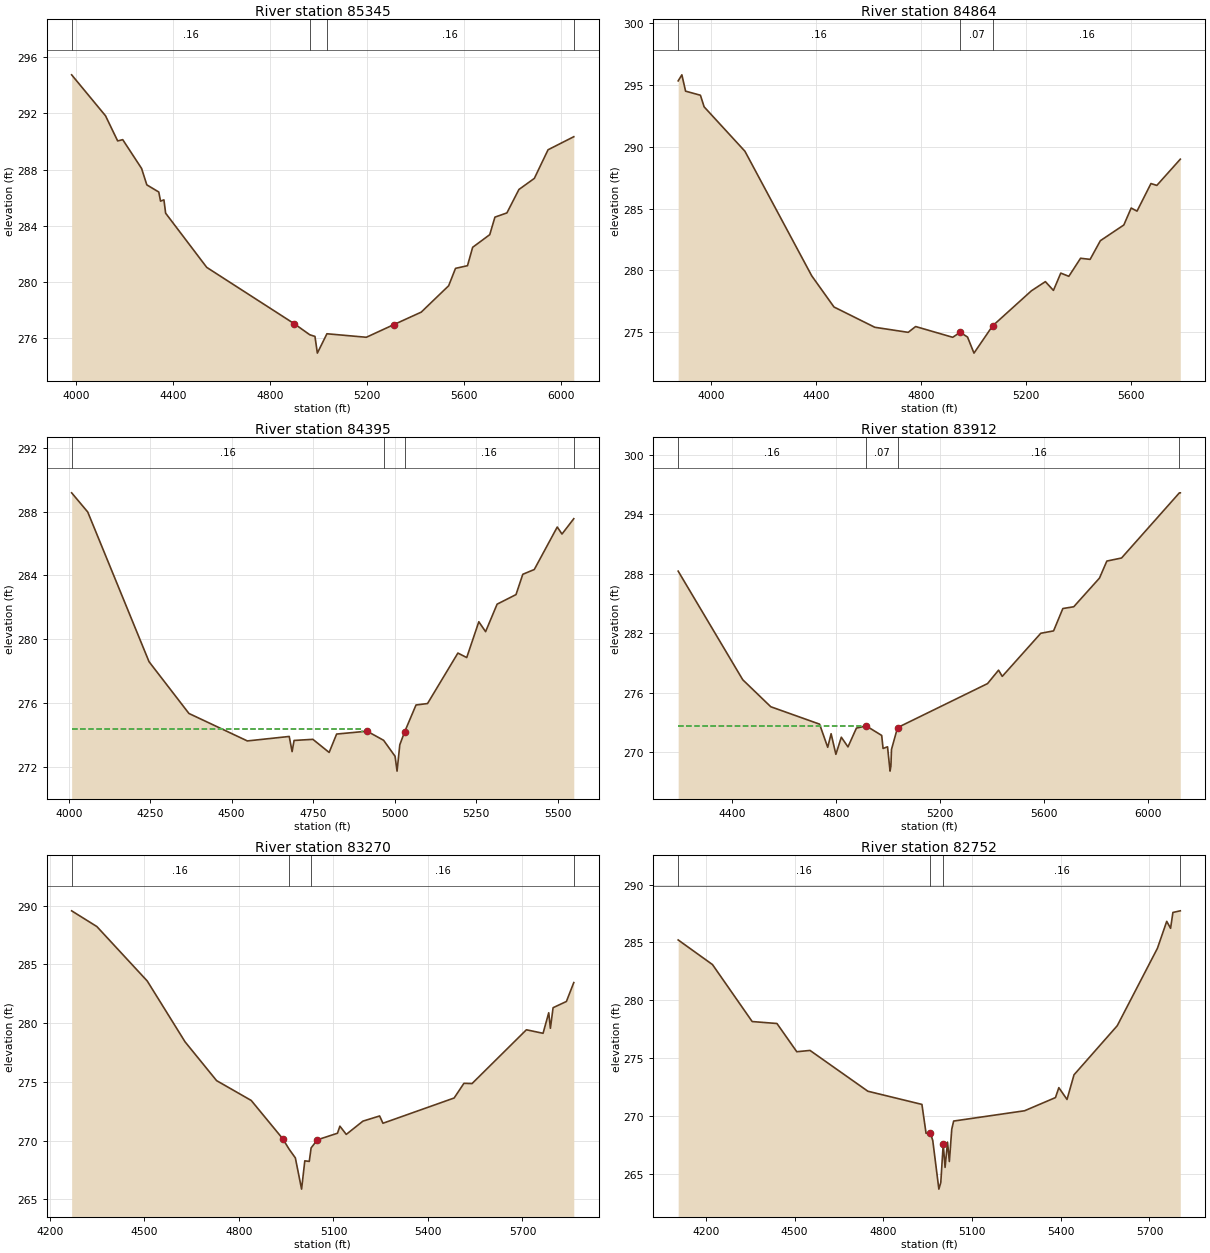
Type RM Length L Ch R = 1 ,85345   ,481,481,481
BEGIN DESCRIPTION:
PENITAS CREEK 148.0
END DESCRIPTION:
XS GIS Cut Line= 3
      2273698.69     13190913.69      2272947.93     13190227.36
      2272187.72     13189496.86
#Sta/Elev= 30
  3982.8  294.75  4122.6  291.83  4172.6  290.04  4193.6  290.13  4271.3  288.08
  4292.9  286.91  4342.2   286.4  4349.6  285.75  4363.5  285.84  4370.6  284.89
  4540.1  281.03  4901.5  277.01  4965.1  276.23  4986.6  276.11  4996.5  274.92
  5035.9   276.3  5198.5  276.05  5311.7  276.95  5424.9  277.84  5538.1  279.72
  5566.4  280.96  5615.8  281.15  5637.1  282.46  5707.6  283.36    5729  284.61
  5778.4  284.91    5828  286.58  5891.6  287.37  5948.2  289.41  6054.3  290.34
#Mann= 4 ,-1 , 0
  3982.8     .16       0  4965.1     .07       0  5035.9     .16       0
  6054.3     .05       0
Bank Sta=4901.5,5311.7
XS Rating Curve= 0 ,0
Exp/Cntr=0.3,0.1

Type RM Length L Ch R = 1 ,84864   ,469,469,469
BEGIN DESCRIPTION:
PENITAS CREEK 147.0
END DESCRIPTION:
XS GIS Cut Line= 3
      2273787.69     13190646.82      2272987.72     13189846.85
      2272287.68     13189496.83
#Sta/Elev= 30
  3874.4  295.32  3888.5  295.81  3902.6  294.49  3959.2  294.16  3973.4  293.22
  4128.9  289.63  4383.5  279.56  4468.3  277.04  4623.9   275.4  4751.2  274.99
  4779.5  275.46  4920.9  274.59  4949.2  274.99  4977.4  274.61  5001.9  273.31
  5072.8  275.51  5220.9  278.35  5274.1  279.09  5304.8  278.38  5332.8  279.78
  5363.5  279.52  5408.2  280.98  5444.6  280.89  5483.7   282.4  5573.1  283.67
  5601.1  285.04  5623.4  284.79  5676.5  287.02  5698.9  286.87  5788.4  288.99
#Mann= 3 , 0 , 0
  3874.4     .16       0  4949.2     .07       0  5072.8     .16       0
Bank Sta=4949.2,5072.8
XS Rating Curve= 0 ,0
Exp/Cntr=0.3,0.1

Type RM Length L Ch R = 1 ,84395   ,483,483,483
BEGIN DESCRIPTION:
PENITAS CREEK 146.0
END DESCRIPTION:
XS GIS Cut Line= 3
      2273787.72     13190296.86      2273237.72     13189496.85
      2272887.73     13189046.87
#Sta/Elev= 30
    4009  289.17  4058.4  287.97  4246.5   278.6  4368.9  275.36  4548.2  273.64
  4676.7  273.92  4685.5  272.97  4691.6  273.67  4749.3  273.74  4799.2  272.92
  4822.1  274.07  4915.6  274.25  4966.3  273.68  5001.5  272.68  5007.6  271.75
    5016   273.4  5030.5  274.19  5065.8  275.89  5101.1  275.98  5194.3  279.14
  5221.4  278.86  5258.5   281.1  5279.3  280.48  5314.6   282.2  5372.6   282.8
  5393.4  284.07  5428.7  284.37  5499.2  287.03  5513.7  286.59  5549.9  287.55
#Mann= 4 ,-1 , 0
    4009     .16       0  4966.3     .07       0  5030.5     .16       0
  5549.9     .05       0
#XS Ineff= 2 , 0
       0 4900.31  274.36               0
Permanent Ineff=
       T       F
Bank Sta=4915.6,5030.5
XS Rating Curve= 0 ,0
Exp/Cntr=0.3,0.1

Type RM Length L Ch R = 1 ,83912   ,642,642,642
BEGIN DESCRIPTION:
PENITAS CREEK 145.0
END DESCRIPTION:
XS GIS Cut Line= 3
      2273837.73     13190246.87      2273587.72     13189446.85
      2272787.69     13188696.82
#Sta/Elev= 30
  4191.5  288.27  4440.3  277.29  4548.3  274.56  4736.3   272.8  4767.7  270.46
  4780.8  271.83  4799.2  269.75  4820.1  271.48  4845.8   270.5  4878.3   272.4
    4916  272.62  4975.7  271.66    4981  270.34  4998.2  270.51  5007.9  268.05
  5011.2  268.55  5013.4  270.24  5036.8  272.45  5383.5   276.9    5426  278.26
  5440.2  277.63  5588.7  281.99    5638  282.23  5673.7  284.49  5715.7  284.67
  5814.9  287.57  5843.2  289.29  5899.9   289.6  6122.8  296.19  6126.3  296.19
#Mann= 4 ,-1 , 0
  4191.5     .16       0    4916     .07       0  5036.8     .16       0
  6122.8     .05       0
#XS Ineff= 2 , 0
       0 4896.37  272.63               0
Permanent Ineff=
       T       F
Bank Sta=4916,5036.8
XS Rating Curve= 0 ,0
Exp/Cntr=0.3,0.1

Type RM Length L Ch R = 1 ,83270   ,518,518,518
BEGIN DESCRIPTION:
PENITAS CREEK 144.0
END DESCRIPTION:
XS GIS Cut Line= 3
      2273983.42     13190326.92      2273993.84     13189483.14
      2273747.29     13188774.77
#Sta/Elev= 30
  4268.9  289.57    4349  288.23    4509  283.59    4629  278.41    4729  275.11
    4839  273.42    4939  270.16    4959  269.28    4979  268.53  4998.8  265.87
    5009  268.28  5023.2  268.23    5029  269.38    5049  270.07  5112.7  270.63
  5120.4  271.23  5140.6  270.53  5193.5  271.66  5246.5   272.1  5257.1  271.48
    5483  273.63  5514.1  274.88  5539.9  274.86  5712.4  279.44  5765.3  279.14
  5783.3  280.89  5788.6  279.57  5797.1  281.32  5839.4  281.85  5862.8  283.46
#Mann= 4 ,-1 , 0
  4268.9     .16       0    4959     .07       0    5029     .16       0
  5862.8     .05       0
Bank Sta=4939,5049
XS Rating Curve= 0 ,0
Exp/Cntr=0.3,0.1

Type RM Length L Ch R = 1 ,82752   ,624,624,624
BEGIN DESCRIPTION:
PENITAS CREEK 143.0
END DESCRIPTION:
XS GIS Cut Line= 4
      2274782.03     13190170.64      2274427.86     13189462.31
      2274288.98     13189281.75      2274092.41     13188632.91
#Sta/Elev= 30
  4106.5  285.22  4222.5  283.09  4356.7  278.16  4440.5  277.99  4507.5  275.55
  4552.3  275.66  4747.9  272.13  4930.6  270.99  4944.6  268.49  4959.1  268.54
  4967.3  267.86  4987.9  263.66  4994.4  264.23  5002.6  267.56  5008.9  265.54
  5017.1  267.73  5023.4  266.05  5031.5  268.85  5037.9  269.55  5277.6  270.44
  5382.1  271.58  5393.5  272.44  5421.2  271.42  5444.8  273.55    5591   277.8
  5726.9   284.5  5758.3  286.83  5771.3  286.23  5779.2   287.6  5804.2  287.74
#Mann= 4 ,-1 , 0
  4106.5     .16       0  4959.1     .07       0  5002.6     .16       0
  5804.2      .1       0
Bank Sta=4959.1,5002.6
XS Rating Curve= 0 ,0
Exp/Cntr=0.3,0.1