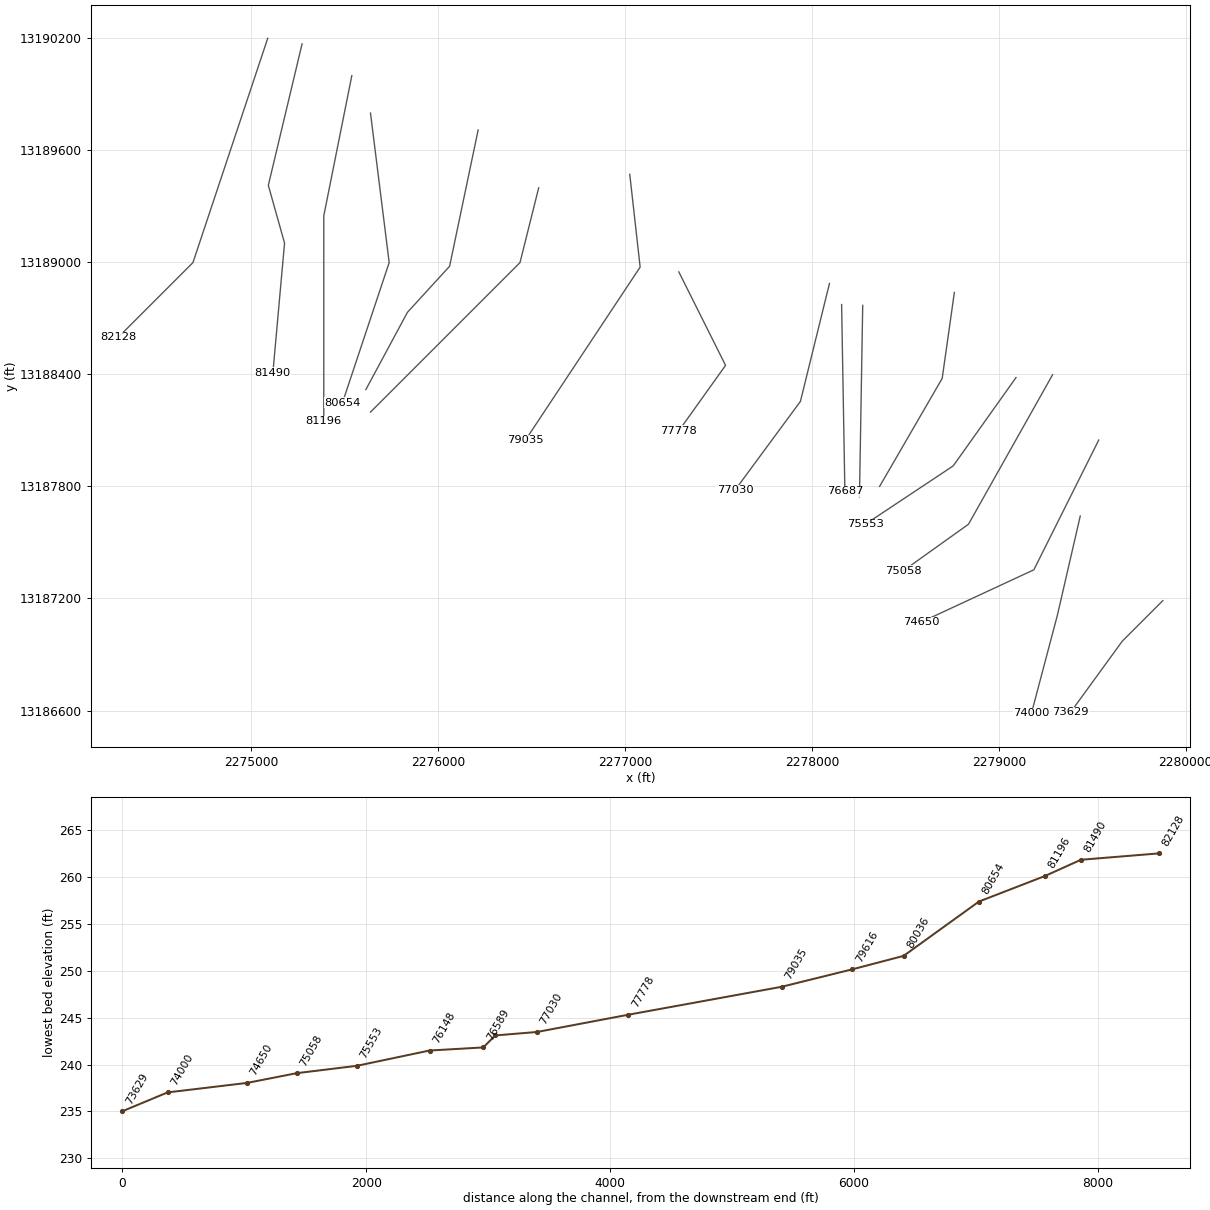
HEC-RAS study PENITAS CREEK.prj: PENITAS CREEK Base Level Engineering

--- PENITAS CREEK.g01 (geometry) --- (continued)

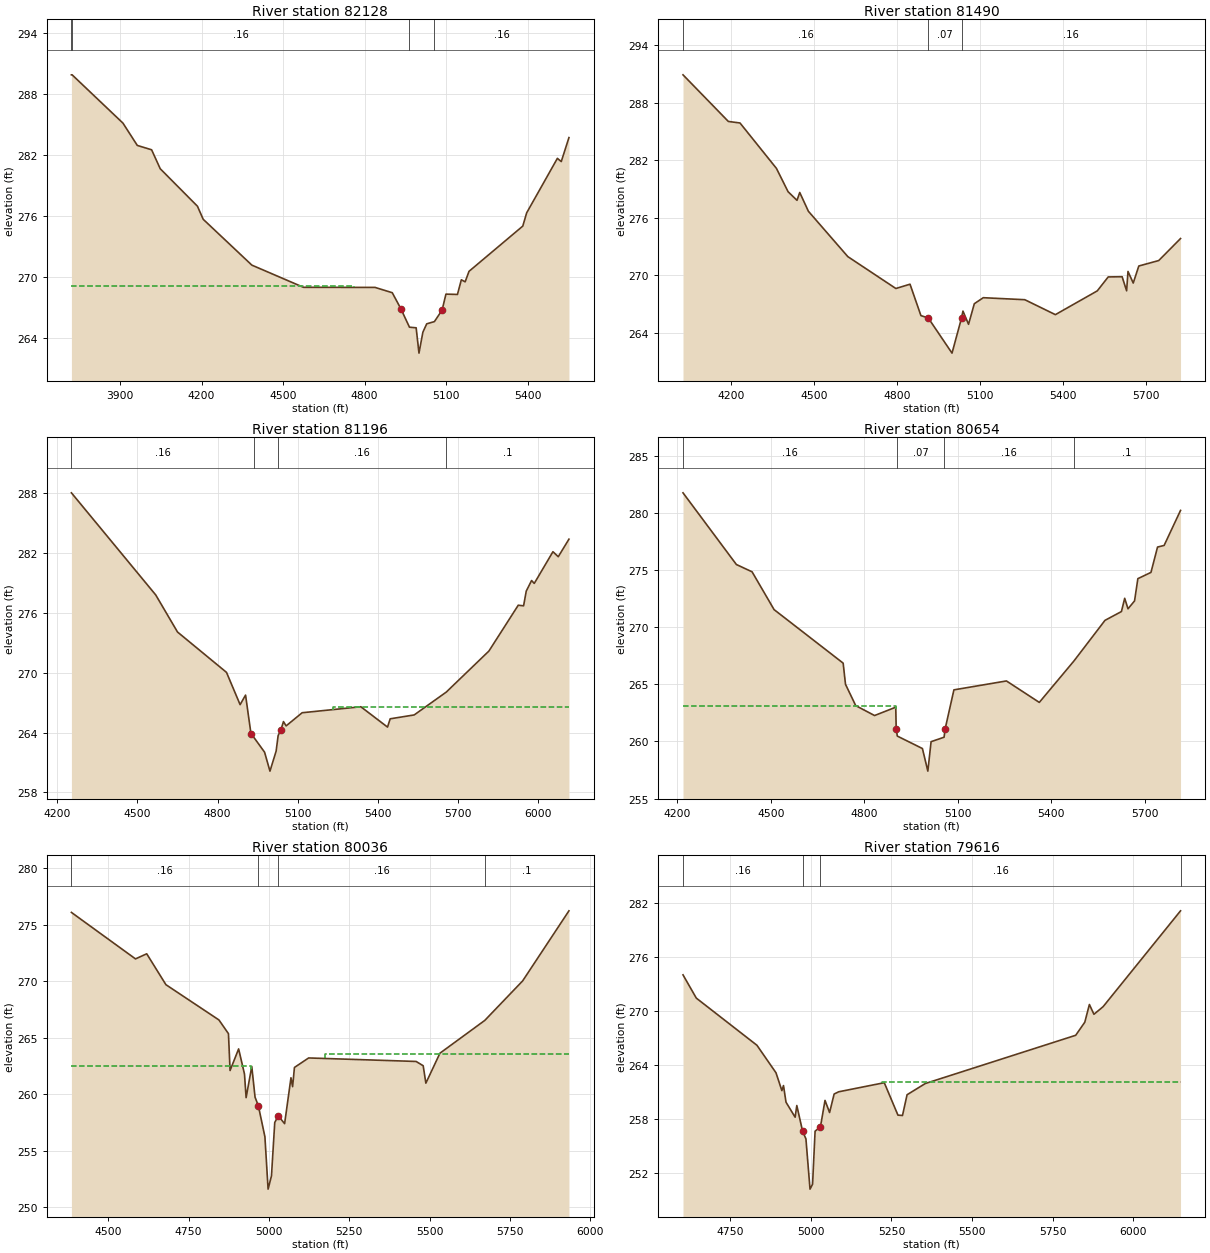
Type RM Length L Ch R = 1 ,82128   ,638,638,638
BEGIN DESCRIPTION:
PENITAS CREEK 142.0
END DESCRIPTION:
XS GIS Cut Line= 3
      2275087.71     13190196.82      2274687.72     13188996.85
      2274287.69     13188596.82
#Sta/Elev= 30
  3721.1   289.9  3723.7   289.9  3910.8  285.15  3963.5  282.96  4016.2  282.53
  4047.8  280.67  4184.9  276.98  4205.9   275.7  4385.1  271.19  4574.9  269.01
  4838.4     269  4901.6  268.48  4933.3   266.9  4964.9  265.09  4989.5  265.03
  4999.9  262.54  5014.3   264.6  5028.4  265.42  5056.7  265.64    5085  266.77
  5099.1  268.34  5141.5  268.31  5155.7  269.75  5169.8  269.55    5184  270.58
  5381.9  275.03  5396.1  276.33  5509.2  281.69  5523.4  281.37  5551.7  283.73
#Mann= 4 ,-1 , 0
  3721.1     .05       0  3723.7     .16       0  4964.9     .07       0
  5056.7     .16       0
#XS Ineff= 2 , 0
       0 4761.66  269.15               0
Permanent Ineff=
       T       F
Bank Sta=4933.3,5085
XS Rating Curve= 0 ,0
Exp/Cntr=0.3,0.1

Type RM Length L Ch R = 1 ,81490   ,294,294,294
BEGIN DESCRIPTION:
PENITAS CREEK 141.0
END DESCRIPTION:
XS GIS Cut Line= 4
      2275271.62     13190167.19      2275091.06     13189410.22
      2275177.86      13189101.2      2275115.37     13188406.79
#Sta/Elev= 30
  4027.5  290.93  4191.2  286.06  4233.3   285.9  4364.8  281.16  4406.9  278.72
  4439.1  277.82    4449  278.64  4480.2  276.68  4622.6  271.94  4796.1  268.61
  4847.2  269.06  4886.5  265.78  4913.1  265.53  4998.8  261.86  5033.1  265.52
  5038.3  266.25  5058.5  264.87  5079.3  267.02  5111.6  267.65  5261.6  267.44
    5372  265.88  5523.2  268.36  5562.8  269.82    5613  269.84  5629.2  268.37
  5634.2  270.39  5653.1  269.18  5673.2  270.96  5745.2  271.53  5823.9  273.83
#Mann= 3 , 0 , 0
  4027.5     .16       0  4913.1     .07       0  5033.1     .16       0
#XS Ineff= 2 , 0
       0                  5177.2       0  267.45
Permanent Ineff=
       F       T
Bank Sta=4913.1,5033.1
XS Rating Curve= 0 ,0
Exp/Cntr=0.3,0.1

Type RM Length L Ch R = 1 ,81196   ,542,542,542
BEGIN DESCRIPTION:
PENITAS CREEK 140.0
END DESCRIPTION:
XS GIS Cut Line= 3
      2275537.72     13189996.83      2275387.72     13189246.85
      2275387.72     13188146.89
#Sta/Elev= 30
  4252.4  288.06  4568.5  277.81  4650.1  274.09  4833.7  270.04  4884.7   266.8
  4905.1  267.76  4925.4  263.89  4935.6  263.54  4976.4  262.03  4996.6  260.13
  5019.7  262.14  5027.2   263.7  5037.2  264.24  5047.2   265.1  5057.2  264.67
  5117.2  265.99  5337.2  266.59  5437.2  264.55  5447.2  265.38  5537.2  265.77
  5657.3  268.06  5817.2  272.18  5927.2  276.78  5947.2  276.72  5957.2   278.2
  5977.2  279.26  5987.2  278.97  6057.2  282.15  6077.2  281.65  6117.2  283.41
#Mann= 4 ,-1 , 0
  4252.4     .16       0  4935.6     .07       0  5027.2     .16       0
  5657.3      .1       0
#XS Ineff= 2 , 0
       0                 5233.16       0  266.54
Permanent Ineff=
       F       T
Bank Sta=4925.4,5037.2
XS Rating Curve= 0 ,0
Exp/Cntr=0.3,0.1

Type RM Length L Ch R = 1 ,80654   ,618,618,618
BEGIN DESCRIPTION:
PENITAS CREEK 139.0
END DESCRIPTION:
XS GIS Cut Line= 3
      2275637.72     13189796.87      2275737.72     13188996.85
      2275487.72     13188246.86
#Sta/Elev= 30
  4218.4  281.78  4389.7   275.5  4440.1  274.86  4510.7  271.55  4732.4  266.86
  4739.9  265.01  4772.7  263.14  4833.2  262.27  4901.2     263 4902.62  261.11
  4906.2  260.47  4986.8  259.38  5004.2   257.4  5014.6  259.98  5056.3  260.37
  5059.8  261.11  5087.9  264.52  5256.5   265.3  5361.9  263.42  5472.8  267.04
  5572.8  270.61  5625.5  271.38    5636  272.54  5646.6  271.62  5667.6  272.31
  5678.2  274.26  5720.3  274.81  5741.4  277.03  5762.5  277.17  5815.2  280.24
#Mann= 4 ,-1 , 0
  4218.4     .16       0  4906.2     .07       0  5056.3     .16       0
  5472.8      .1       0
#XS Ineff= 2 , 0
       0 4901.35  263.08               0
Permanent Ineff=
       T       F
Bank Sta=4902.62,5059.8
XS Rating Curve= 0 ,0
Exp/Cntr=0.3,0.1

Type RM Length L Ch R = 1 ,80036   ,420,420,420
BEGIN DESCRIPTION:
Mapping XS ddb476c6
END DESCRIPTION:
XS GIS Cut Line= 4
      2276213.76     13189706.23      2276060.98     13188977.06
      2275835.29     13188730.54      2275613.07     13188317.34
#Sta/Elev= 30
  4385.1  276.07  4584.5  271.96  4619.5  272.41  4679.2  269.68  4844.2  266.56
  4873.8  265.35  4878.9  262.09  4905.5     264  4923.7  261.78  4928.8  259.69
  4946.4  262.45  4956.6  259.73  4966.8  258.98  4987.3  256.23  4997.2   251.6
  5007.7  252.77  5017.9  257.49  5028.7  258.08  5048.6  257.39  5068.4  261.45
  5073.5  260.66  5079.2  262.36  5123.4   263.2  5457.9  262.89  5479.9  262.51
  5488.2  260.97    5532  263.62  5671.6  266.52  5789.3  270.01  5933.5  276.21
#Mann= 4 ,-1 , 0
  4385.1     .16       0  4966.8     .07       0  5028.7     .16       0
  5671.6      .1       0
#XS Ineff= 2 , 0
       0 4944.25  262.46 5175.54       0  263.54
Permanent Ineff=
       T       T
Bank Sta=4966.8,5028.7
XS Rating Curve= 0 ,0
Exp/Cntr=0.3,0.1

Type RM Length L Ch R = 1 ,79616   ,581,581,581
BEGIN DESCRIPTION:
PENITAS CREEK 137.0
END DESCRIPTION:
XS GIS Cut Line= 3
      2276537.73     13189396.89      2276437.72     13188996.85
      2275637.73     13188196.86
#Sta/Elev= 30
  4603.4  274.03  4644.7  271.44  4832.8  266.19    4892  263.12  4910.1  261.14
  4915.2   261.7    4923  259.85  4951.3  258.18  4956.5  259.48  4974.5  256.61
  4984.8  255.77  4997.5  250.17  5005.4  250.72  5013.2  256.62  5029.9  257.12
    5044  260.05  5058.2   258.7  5072.3  260.76  5086.5  261.01  5227.9  262.02
  5270.3  258.41  5284.4  258.37  5298.6  260.68  5355.2  261.93  5821.8   267.3
  5850.1  268.76  5864.3  270.73  5878.4  269.64  5906.7  270.48  6147.1  281.16
#Mann= 4 ,-1 , 0
  4603.4     .16       0  4974.5     .07       0  5029.9     .16       0
  6147.1      .1       0
#XS Ineff= 2 , 0
                         5220.54          262.08
Permanent Ineff=
       F       F
Bank Sta=4974.5,5029.9
XS Rating Curve= 0 ,0
Exp/Cntr=0.3,0.1

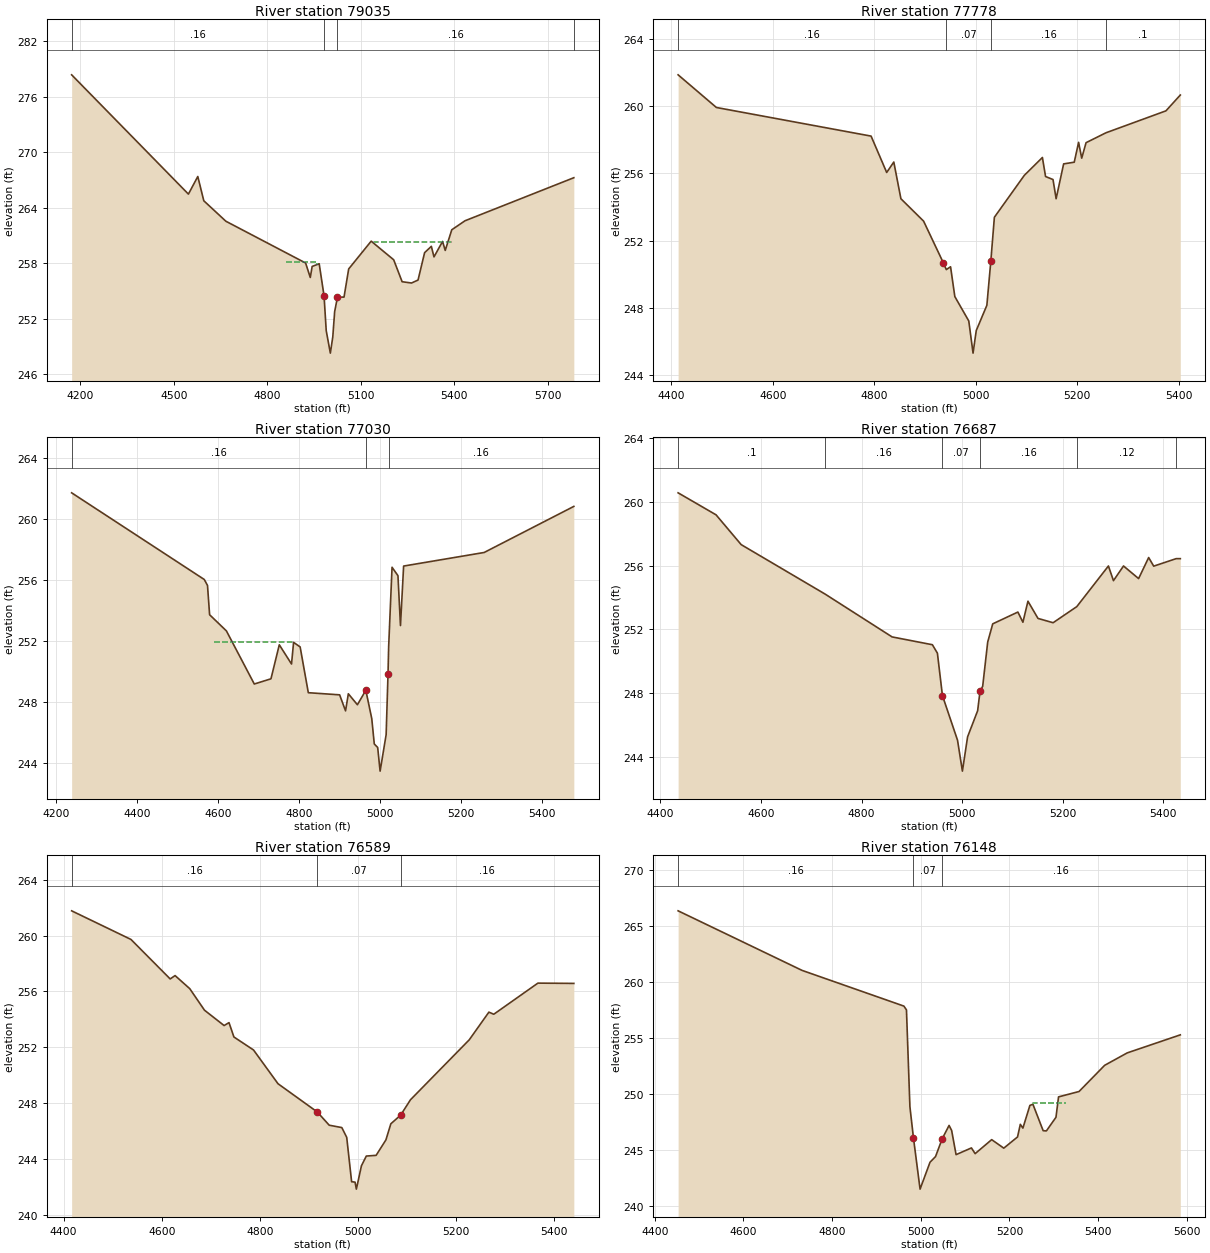
Type RM Length L Ch R = 1 ,79035   ,1257,1257,1257
BEGIN DESCRIPTION:
PENITAS CREEK 136.0
END DESCRIPTION:
XS GIS Cut Line= 3
      2277025.08     13189469.28      2277080.64     13188972.72
      2276466.03      13188045.6
#Sta/Elev= 30
  4171.7  278.35  4546.5  265.47  4576.6  267.37  4595.9  264.75  4666.8  262.54
  4922.7  258.03  4937.7  256.47  4943.7  257.66  4966.3  257.95 4981.87  254.49
  4988.9  250.72  5002.1   248.3  5009.9  250.04  5015.9  252.77    5025  254.35
    5046  254.35    5061  257.39  5133.2  260.39  5205.4  258.38  5232.5  256.01
  5262.6  255.87  5283.6  256.19  5304.7  259.15  5326.3  259.83  5334.8  258.69
  5362.3  260.36  5370.9  259.39  5391.9  261.62  5434.3  262.59  5783.7  267.24
#Mann= 4 ,-1 , 0
  4171.7     .16       0 4981.87     .07       0    5025     .16       0
  5783.7      .1       0
#XS Ineff= 2 ,-1
  4859.9 4958.76  258.19 5141.55 5393.37  260.35
Permanent Ineff=
       T       T
Bank Sta=4981.87,5025
XS Rating Curve= 0 ,0
Exp/Cntr=0.3,0.1

Type RM Length L Ch R = 1 ,77778   ,748,748,748
BEGIN DESCRIPTION:
PENITAS CREEK 135.0
END DESCRIPTION:
XS GIS Cut Line= 3
      2277287.74     13188946.82      2277537.72     13188446.85
      2277287.72     13188096.85
#Sta/Elev= 30
  4413.7  261.85  4489.1  259.91  4793.8  258.21  4824.5  256.05  4838.5  256.67
  4852.5  254.49  4897.2  253.16  4936.3  250.67  4941.9  250.28  4950.3  250.45
  4958.7  248.68  4986.2  247.23  4994.6  245.32  5000.9  246.66  5021.8  248.16
  5029.6  250.78  5036.6  253.39  5095.6  255.88  5131.2  256.94  5137.4  255.81
  5152.1  255.63  5158.2  254.49    5173  256.56  5193.9  256.66  5202.5  257.84
  5208.6   256.9  5217.2  257.82  5256.6  258.41  5374.5  259.71  5402.8  260.65
#Mann= 4 ,-1 , 0
  4413.7     .16       0  4941.9     .07       0  5029.6     .16       0
  5256.6      .1       0
Bank Sta=4936.3,5029.6
XS Rating Curve= 0 ,0
Exp/Cntr=0.3,0.1

Type RM Length L Ch R = 1 ,77030   ,343,343,343
BEGIN DESCRIPTION:
PENITAS CREEK 134.0
END DESCRIPTION:
XS GIS Cut Line= 3
      2278093.67     13188885.08      2277938.28     13188253.97
      2277587.62     13187778.32
#Sta/Elev= 30
  4237.6  261.72  4565.3  256.04  4573.3  255.65  4578.5  253.73    4620  252.67
  4688.9  249.19  4730.1  249.53  4750.7  251.76  4780.9   250.5    4786  251.92
  4802.2  251.62  4822.4  248.62  4899.8  248.48  4914.4  247.43  4921.3  248.55
  4943.7  247.83  4964.5  248.78  4979.2  246.92  4985.4  245.26  4993.8  245.03
  4999.8  243.48  5014.7  245.87 5019.32  249.82  5020.9  251.62  5029.3  256.84
  5043.9  256.29  5050.1  253.02  5057.9  256.92  5256.9  257.81  5478.5  260.83
#Mann= 3 ,-1 , 0
  4237.6     .16       0  4964.5     .07       0  5020.9     .16       0
#XS Ineff= 1 ,-1
 4590.26 4787.56  251.92
Permanent Ineff=
       T
Bank Sta=4964.5,5019.32
XS Rating Curve= 0 ,0
Exp/Cntr=0.3,0.1

Type RM Length L Ch R = 1 ,76687   ,98,98,98
BEGIN DESCRIPTION:
Mapping XS a940621d
END DESCRIPTION:
XS GIS Cut Line= 2
      2278158.77     13188772.24      2278176.13     13187773.99
#Sta/Elev= 30
  4435.2  260.57  4510.6  259.19  4560.6  257.32  4727.3  254.22  4860.6  251.53
  4940.7  251.04  4950.7  250.51  4960.7  247.85  4990.7  245.05  5000.4  243.11
  5010.7  245.26  5030.7   246.9 5035.45  248.13  5040.7  248.43  5050.7  251.21
  5060.7  252.35  5110.7  253.09  5120.7  252.45  5130.7  253.77  5150.7  252.69
  5180.7  252.42  5227.8  253.43  5290.7  255.98  5300.7  255.06  5320.7  255.98
  5350.7  255.19  5370.7  256.51  5380.7  255.97  5425.3  256.44  5433.6  256.44
#Mann= 6 ,-1 , 0
  4435.2      .1       0  4727.3     .16       0  4960.7     .07       0
 5035.45     .16       0  5227.8     .12       0  5425.3      .1       0
Bank Sta=4960.7,5035.45
XS Rating Curve= 0 ,0
Exp/Cntr=0.3,0.1

Type RM Length L Ch R = 1 ,76589   ,441,441,441
BEGIN DESCRIPTION:
Mapping XS 23b61bda
END DESCRIPTION:
XS GIS Cut Line= 2
      2278271.61     13188767.83      2278254.25     13187743.57
#Sta/Elev= 30
  4416.3  261.77  4537.3  259.72  4617.3  256.89  4627.3  257.13  4657.3  256.19
  4687.3  254.65  4727.3  253.55  4737.3  253.76  4747.3  252.73  4787.3   251.8
  4837.3  249.38  4917.3  247.36  4941.7  246.41  4967.4  246.24  4977.4  245.54
  4987.4  242.36  4994.4  242.33  4997.1  241.83  5007.4   243.5  5017.4   244.2
  5037.4  244.25  5057.4  245.36  5067.4  246.51  5087.4  247.13  5107.4  248.23
  5227.4  252.53  5267.4  254.51  5277.4  254.36  5367.4  256.59  5440.7  256.57
#Mann= 3 , 0 , 0
  4416.3     .16       0  4917.3     .07       0  5087.4     .16       0
Bank Sta=4917.3,5087.4
XS Rating Curve= 0 ,0
Exp/Cntr=0.3,0.1

Type RM Length L Ch R = 1 ,76148   ,595,595,595
BEGIN DESCRIPTION:
PENITAS CREEK 133.0
END DESCRIPTION:
XS GIS Cut Line= 3
      2278762.06     13188837.27      2278696.96     13188377.24
      2278362.14     13187799.23
#Sta/Elev= 30
  4452.7  266.36  4732.2  261.04  4961.9  257.85  4967.7  257.51  4975.5  248.85
  4983.5  246.07  4998.4   241.5  5020.8   243.9  5033.3  244.41  5048.1  245.98
  5063.8  247.19  5069.6  246.74  5079.6  244.58  5114.2  245.18  5122.6  244.67
  5159.9  245.92  5187.2  245.16  5218.2  246.16  5224.5  247.29  5230.3  246.95
  5246.1  248.98  5252.9  249.08    5276  246.72  5283.3   246.7  5304.9  247.92
  5310.7  249.74  5356.9  250.22  5414.7  252.56  5465.6  253.67  5585.3  255.28
#Mann= 3 , 0 , 0
  4452.7     .16       0  4983.5     .07       0  5048.1     .16       0
#XS Ineff= 2 ,-1
 5064.04 5235.65  247.15 5253.06 5326.42  249.23
Permanent Ineff=
       T       T
Bank Sta=4983.5,5048.1
XS Rating Curve= 0 ,0
Exp/Cntr=0.3,0.1

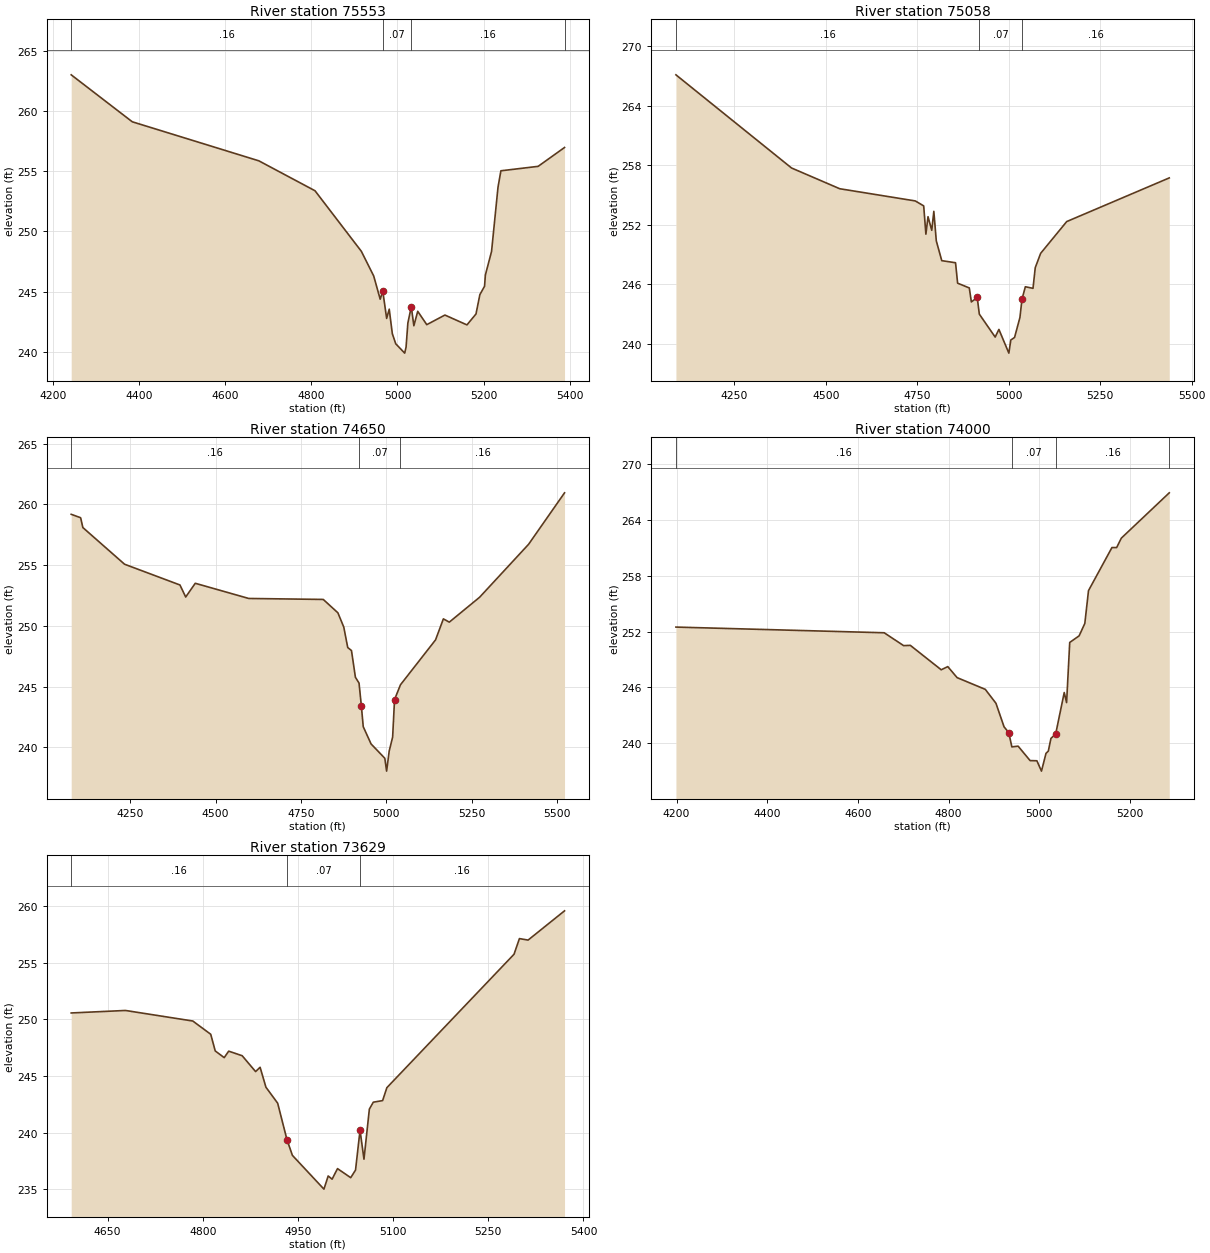
Type RM Length L Ch R = 1 ,75553   ,495,495,495
BEGIN DESCRIPTION:
PENITAS CREEK 132.0
END DESCRIPTION:
XS GIS Cut Line= 3
      2279091.92     13188381.56      2278755.94       13187909.
      2278284.64     13187595.99
#Sta/Elev= 30
  4242.4  263.04  4384.2  259.13  4678.1  255.88  4808.5  253.39  4916.1  248.35
  4944.9  246.29  4959.9  244.36  4965.9  245.04  4974.9  242.76  4980.9  243.53
  4988.1  241.49    4996  240.65  5016.8  239.87    5020  240.37  5024.2  242.38
  5032.1  243.73  5038.1  242.15  5047.1  243.35  5068.1  242.24  5110.2  243.04
  5161.4  242.22  5182.4  243.13  5191.4  244.74 5202.27  245.44  5204.2  246.38
  5218.5  248.33  5233.5  253.68  5240.2  255.05  5326.7  255.42    5388  256.99
#Mann= 4 ,-1 , 0
  4242.4     .16       0  4965.9     .07       0  5032.1     .16       0
    5388     .08       0
Bank Sta=4965.9,5032.1
XS Rating Curve= 0 ,0
Exp/Cntr=0.3,0.1

Type RM Length L Ch R = 1 ,75058   ,408,408,408
BEGIN DESCRIPTION:
PENITAS CREEK 131.0
END DESCRIPTION:
XS GIS Cut Line= 3
      2279287.73     13188396.88      2278837.72     13187596.85
      2278487.74     13187346.87
#Sta/Elev= 30
  4090.8  267.13  4406.7  257.74  4538.3  255.65  4744.8  254.42  4767.8  253.92
  4773.8  251.07  4779.6  252.83  4789.8  251.46  4795.5  253.37  4802.2   250.4
  4817.2   248.4  4854.8  248.19  4860.5  246.13  4892.4  245.65  4898.1  244.24
  4914.1  244.69  4919.8  243.01  4963.1   240.7  4973.3  241.47  5000.5  239.08
  5005.8   240.4  5016.1  240.66  5030.8  242.68 5036.36  244.51  5045.6  245.77
  5066.5  245.61  5072.6  247.69  5087.4  249.14  5158.6  252.34  5438.8  256.74
#Mann= 3 ,-1 , 0
  4090.8     .16       0  4919.8     .07       0 5036.36     .16       0
Bank Sta=4914.1,5036.36
XS Rating Curve= 0 ,0
Exp/Cntr=0.3,0.1

Type RM Length L Ch R = 1 ,74650   ,650,650,650
BEGIN DESCRIPTION:
PENITAS CREEK 130.0
END DESCRIPTION:
XS GIS Cut Line= 3
      2279534.62     13188047.35      2279187.41     13187352.93
      2278582.33       13187072.
#Sta/Elev= 30
  4077.8  259.19  4105.4  258.91  4111.9   258.1  4233.9  255.08    4396  253.37
  4412.8  252.38  4440.8  253.51  4597.3  252.26  4815.3  252.18  4858.1  251.08
  4875.4   249.9  4886.9  248.22  4897.9  247.97  4909.4  245.77    4920  245.29
  4926.7  243.44  4932.3   241.7  4955.2  240.28  4995.4   239.1  5000.7  238.04
  5008.2  239.69  5018.3  240.84  5023.9  243.93  5041.2  245.15  5143.9  248.85
  5166.8  250.58  5184.1  250.31  5272.8  252.36  5416.1  256.72  5521.3  260.96
#Mann= 3 ,-1 , 0
  4077.8     .16       0    4920     .07       0  5041.2     .16       0
Bank Sta=4926.7,5023.9
XS Rating Curve= 0 ,0
Exp/Cntr=0.3,0.1

Type RM Length L Ch R = 1 ,74000   ,371,371,371
BEGIN DESCRIPTION:
PENITAS CREEK 129.0
END DESCRIPTION:
XS GIS Cut Line= 3
      2279435.63     13187640.59      2279313.28     13187109.88
      2279174.38     13186584.67
#Sta/Elev= 30
  4198.7  252.48    4658  251.87  4700.8  250.49  4715.6  250.52  4783.7   247.9
  4798.2  248.24  4818.7  247.06  4880.9   245.8  4904.4  244.31  4922.3  241.78
  4932.6  241.17  4939.5  239.63  4953.3  239.71  4979.7  238.16  4994.7  238.14
  5004.8  237.03  5014.8  238.94  5019.9  239.18  5025.7  240.54  5036.1  241.01
    5055  245.46  5060.2  244.38  5067.1  250.83  5087.8  251.54  5100.4  252.87
  5108.5  256.39  5160.2  261.01  5170.6  261.01  5180.9  262.02  5286.6  266.88
#Mann= 4 ,-1 , 0
  4198.7     .16       0  4939.5     .07       0  5036.1     .16       0
  5286.6     .05       0
Bank Sta=4932.6,5036.1
XS Rating Curve= 0 ,0
Exp/Cntr=0.3,0.1

Type RM Length L Ch R = 1 ,73629   ,404,404,404
BEGIN DESCRIPTION:
PENITAS CREEK 128.0
END DESCRIPTION:
XS GIS Cut Line= 3
      2279877.53     13187188.02       2279660.5     13186970.99
      2279383.73     13186590.42
#Sta/Elev= 30
  4592.7  250.56  4678.2  250.78  4784.3  249.85  4812.6  248.68  4819.7  247.21
  4833.8  246.62  4840.9  247.19  4862.1  246.79  4883.3  245.39  4890.4  245.77
  4899.6  244.01  4918.1   242.6  4932.8  239.37  4941.3     238    4991  235.02
  4997.7  236.18  5003.9   235.9  5012.4  236.83  5033.2  236.03  5040.8   236.7
  5047.9  240.22  5054.1  237.66  5062.6  242.08  5068.8  242.69  5083.5  242.83
  5090.2  243.97  5290.6  255.74  5299.1  257.12  5312.8  256.99  5370.2  259.57
#Mann= 3 , 0 , 0
  4592.7     .16       0  4932.8     .07       0  5047.9     .16       0
Bank Sta=4932.8,5047.9
XS Rating Curve= 0 ,0
Exp/Cntr=0.3,0.1