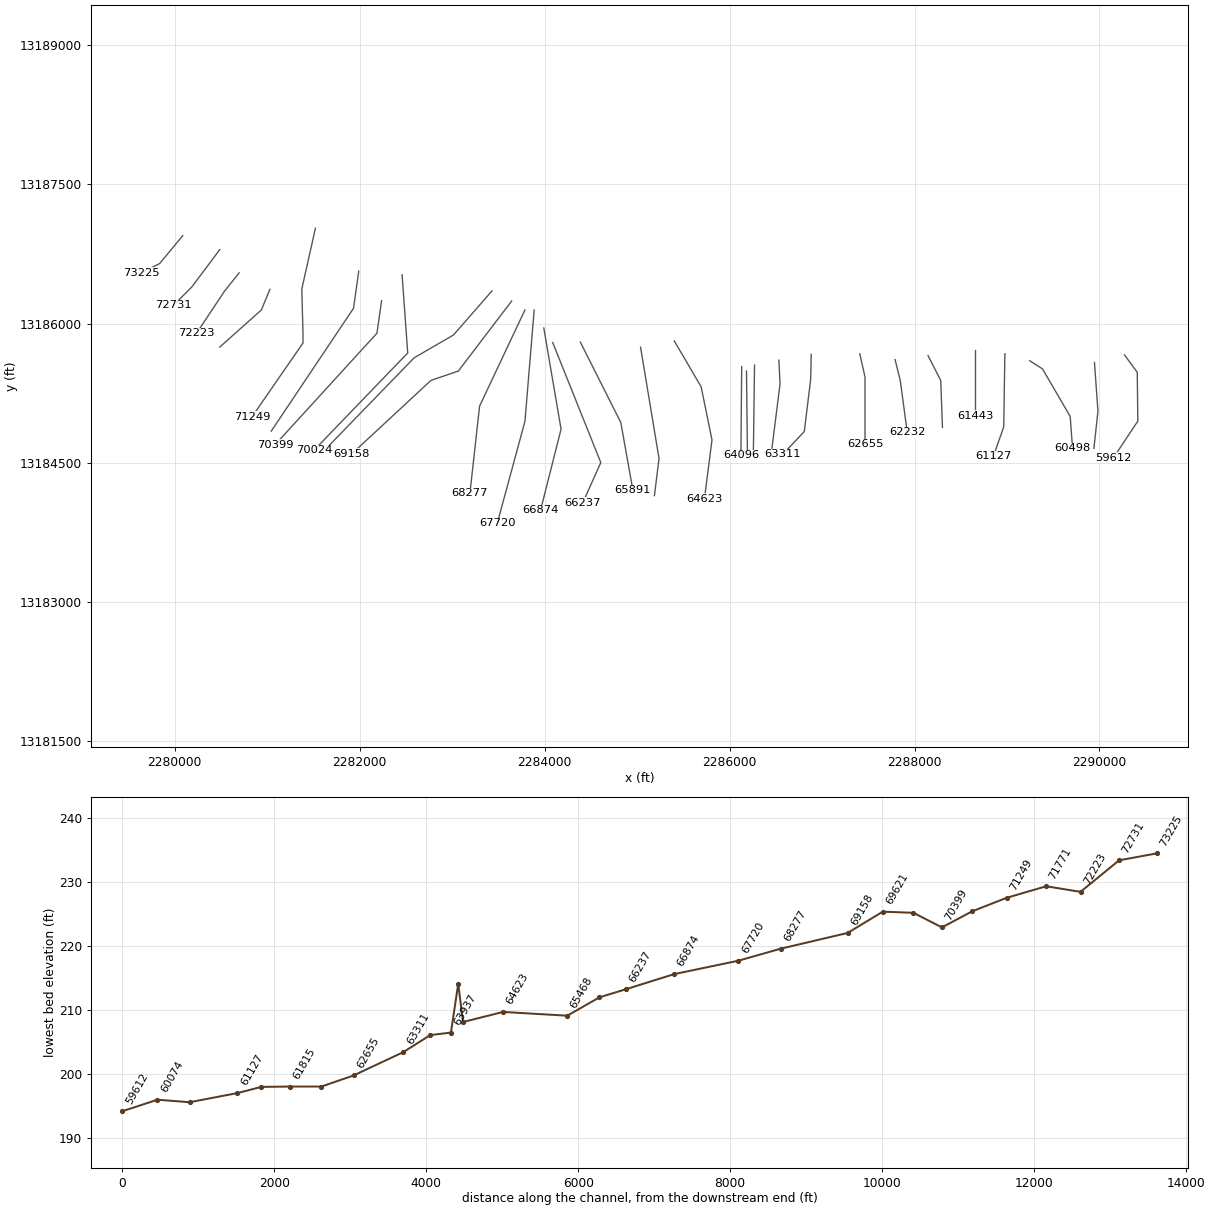
HEC-RAS study PENITAS CREEK.prj: PENITAS CREEK Base Level Engineering

--- PENITAS CREEK.g01 (geometry) --- (continued)

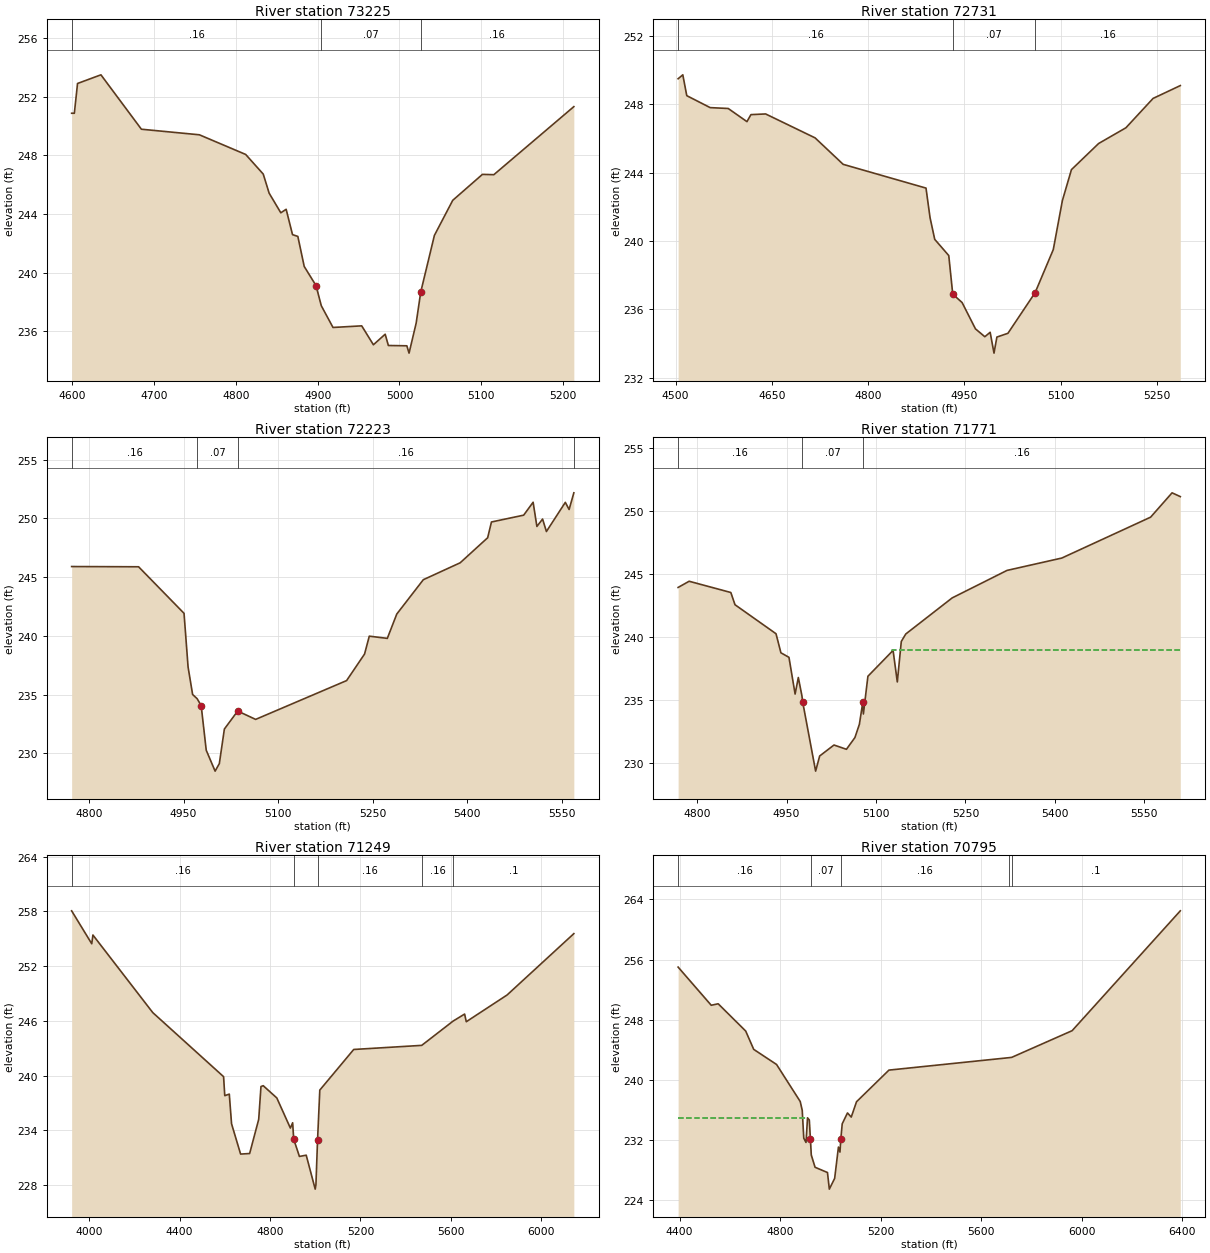
Type RM Length L Ch R = 1 ,73225   ,494,494,494
BEGIN DESCRIPTION:
PENITAS CREEK 127.0
END DESCRIPTION:
XS GIS Cut Line= 3
      2280087.73     13186946.86      2279837.72     13186646.85
      2279637.75     13186546.87
#Sta/Elev= 30
  4599.1  250.87  4602.4  250.87  4606.3   252.9  4634.9  253.49  4684.4  249.78
  4755.3   249.4  4811.9  248.06  4833.4  246.72  4840.6  245.42  4854.9  244.08
  4861.4  244.32  4869.2  242.59  4875.7  242.47  4883.5  240.42  4897.9  239.12
  4904.4  237.74  4918.7  236.26  4953.8  236.37  4968.1  235.08  4982.5   235.8
  4986.4  235.03    5009  235.01  5011.7  234.51  5020.4  236.56    5026  238.68
  5042.7  242.54  5065.1  244.93  5101.4   246.7  5115.4  246.68  5213.2  251.32
#Mann= 3 ,-1 , 0
  4599.1     .16       0  4904.4     .07       0    5026     .16       0
Bank Sta=4897.9,5026
XS Rating Curve= 0 ,0
Exp/Cntr=0.3,0.1

Type RM Length L Ch R = 1 ,72731   ,508,508,508
BEGIN DESCRIPTION:
PENITAS CREEK 126.0
END DESCRIPTION:
XS GIS Cut Line= 3
      2280487.71     13186796.84      2280187.72     13186396.85
      2279987.74     13186196.87
#Sta/Elev= 30
  4503.9  249.49  4511.2  249.72  4517.4   248.5  4553.9   247.8    4582  247.75
  4611.2  246.98  4617.4  247.39  4640.3  247.43  4717.4  246.03  4761.2  244.48
  4890.3  243.09  4896.6  241.36  4903.9  240.09  4925.8  239.14    4932  236.88
  4946.6  236.39  4967.4  234.85    4982  234.39  4990.3  234.65  4996.3  233.43
  5000.8  234.37    5018  234.59  5060.4  236.97  5088.7  239.49  5102.9  242.36
    5117  244.17  5159.4   245.7  5201.9  246.62  5244.3  248.34  5286.7  249.09
#Mann= 3 , 0 , 0
  4503.9     .16       0    4932     .07       0  5060.4     .16       0
Bank Sta=4932,5060.4
XS Rating Curve= 0 ,0
Exp/Cntr=0.3,0.1

Type RM Length L Ch R = 1 ,72223   ,452,452,452
BEGIN DESCRIPTION:
PENITAS CREEK 125.0
END DESCRIPTION:
XS GIS Cut Line= 3
      2280697.57     13186546.67      2280537.72     13186346.85
      2280237.73     13185896.87
#Sta/Elev= 30
  4772.4   245.9  4878.6  245.88  4950.7  241.92  4957.1  237.36  4964.3  235.02
  4971.5  234.66  4977.9  234.07  4985.9  230.28    5000   228.5  5006.7  229.14
  5014.7  232.08  5035.8  233.61  5064.3   232.9  5208.6   236.2  5237.1  238.46
  5244.6  239.98  5273.2  239.79  5288.2  241.86  5330.3  244.78  5388.8  246.22
  5432.4  248.35  5438.4  249.69  5489.5  250.27  5504.5  251.37  5510.5  249.31
  5519.5  249.94  5525.6  248.88  5555.6  251.36  5561.6  250.75  5569.1  252.17
#Mann= 4 ,-1 , 0
  4772.4     .16       0  4971.5     .07       0  5035.8     .16       0
  5569.1      .1       0
Bank Sta=4977.9,5035.8
XS Rating Curve= 0 ,0
Exp/Cntr=0.3,0.1

Type RM Length L Ch R = 1 ,71771   ,522,522,522
BEGIN DESCRIPTION:
PENITAS CREEK 124.0
END DESCRIPTION:
XS GIS Cut Line= 3
      2281030.06     13186368.46      2280937.72     13186146.85
      2280487.68     13185746.82
#Sta/Elev= 30
  4768.1  243.93  4786.6  244.42  4856.5  243.53  4863.5  242.56  4932.3  240.26
  4940.5  238.75    4954  238.39  4964.3  235.48  4969.7  236.79  4975.7  235.35
 4977.05  234.84  4998.7  229.37  5005.5  230.57  5029.5  231.44  5050.4   231.1
  5064.6  232.03  5072.1  233.08 5077.95  234.87  5078.8   233.9  5086.4  236.89
  5128.6  238.94  5135.7  236.44  5142.4  239.65  5149.9  240.24  5227.7   243.1
  5319.7  245.28  5411.6  246.26  5560.5   249.5  5596.5  251.43  5610.3  251.13
#Mann= 3 ,-1 , 0
  4768.1     .16       0  4975.7     .07       0 5077.95     .16       0
#XS Ineff= 2 , 0
       0                 5127.25       0     239
Permanent Ineff=
       F       T
Bank Sta=4977.05,5077.95
XS Rating Curve= 0 ,0
Exp/Cntr=0.3,0.1

Type RM Length L Ch R = 1 ,71249   ,454,454,454
BEGIN DESCRIPTION:
PENITAS CREEK 123.0
END DESCRIPTION:
XS GIS Cut Line= 5
      2281522.49     13187027.44      2281374.91     13186372.03
      2281387.93     13185898.94      2281387.93     13185790.43
      2280836.72     13184996.16
#Sta/Elev= 30
  3923.1  258.05    4012  254.44  4017.1   255.4  4281.8   246.9  4594.9  239.88
  4600.1   237.8  4620.1  237.97  4630.1  234.72  4670.1   231.4  4710.1  231.46
  4750.2  235.21  4760.2   238.8  4770.2  238.89  4830.2  237.55  4890.2  234.25
  4900.2  234.83 4904.96  233.03  4930.2  231.14  4960.2  231.28    5000  227.56
  5003.2  228.06  5010.3   232.9  5020.3  238.41  5170.3  242.86    5471  243.31
  5609.7  245.97  5660.6  246.74  5667.9   245.9  5848.4  248.83  6143.5  255.55
#Mann= 5 ,-1 , 0
  3923.1     .16       0 4904.96     .07       0  5010.3     .16       0
    5471     .16       0  5609.7      .1       0
#XS Ineff= 2 , 0
       0 4761.38  238.74               0
Permanent Ineff=
       T       F
Bank Sta=4904.96,5010.3
XS Rating Curve= 0 ,0
Exp/Cntr=0.3,0.1

Type RM Length L Ch R = 1 ,70795   ,396,396,396
BEGIN DESCRIPTION:
PENITAS CREEK 122.0
END DESCRIPTION:
XS GIS Cut Line= 3
      2281990.82     13186564.73       2281934.4     13186165.39
      2281044.71     13184841.71
#Sta/Elev= 30
    4394  254.99  4525.8  249.91  4553.4  250.11  4662.9  246.48  4694.8  244.04
  4785.7  242.03  4879.9   237.1  4887.9  235.92    4894  232.22  4902.9  231.65
  4908.9  234.93    4916  234.65 4920.45  232.06  4923.9  229.98  4938.9  228.35
  4988.3  227.65  4995.7  225.44  5016.9  226.87  5031.9  231.04    5038  230.37
 5041.32  232.06  5046.9  234.13  5067.9  235.58  5082.9  235.03  5103.9  237.07
  5232.9  241.28  5712.3  242.94  5721.6  242.98  5961.9  246.53  6392.2  262.48
#Mann= 5 ,-1 , 0
    4394     .16       0  4923.9     .07       0 5041.32     .16       0
  5712.3     .16       0  5721.6      .1       0
#XS Ineff= 2 , 0
       0 4909.33  234.95               0
Permanent Ineff=
       T       F
Bank Sta=4920.45,5041.32
XS Rating Curve= 0 ,0
Exp/Cntr=0.3,0.1

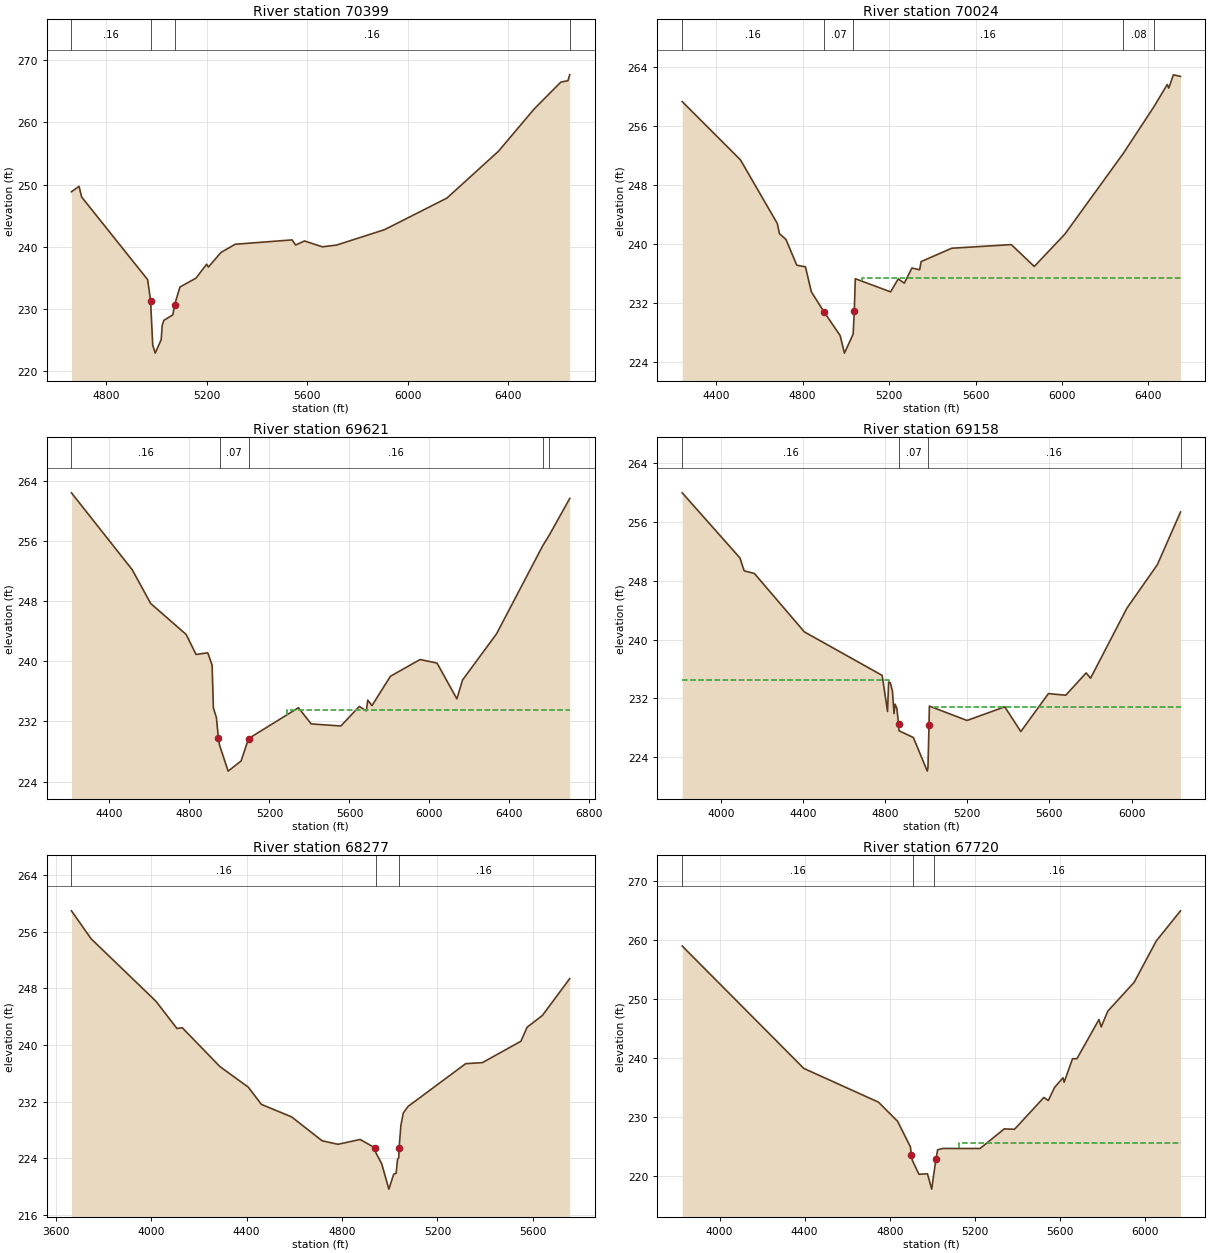
Type RM Length L Ch R = 1 ,70399   ,375,375,375
BEGIN DESCRIPTION:
PENITAS CREEK 121.0
END DESCRIPTION:
XS GIS Cut Line= 3
      2282237.72     13186246.82      2282187.72     13185896.85
      2281087.72     13184696.85
#Sta/Elev= 30
  4662.7  248.84    4693   249.7  4703.1     248  4965.7  234.73 4977.29  231.37
  4985.9  224.22  4995.8  222.94  5019.6  225.11  5023.3  227.35  5030.1   228.2
  5065.9  229.09  5072.6  230.67  5094.2  233.55  5157.7  234.97  5200.3  237.21
  5207.1  236.74    5257  239.09  5313.7  240.41    5540  241.11  5554.2  240.29
  5589.4  240.94  5660.3     240    5717  240.28  5908.2  242.76  6155.7  247.82
  6360.8  255.34  6502.6  262.12  6608.6  266.43    6637  266.66  6644.1   267.6
#Mann= 4 ,-1 , 0
  4662.7     .16       0 4977.29     .07       0  5072.6     .16       0
  6644.1     .05       0
Bank Sta=4977.29,5072.6
XS Rating Curve= 0 ,0
Exp/Cntr=0.3,0.1

Type RM Length L Ch R = 1 ,70024   ,403,403,403
BEGIN DESCRIPTION:
PENITAS CREEK 120.0
END DESCRIPTION:
XS GIS Cut Line= 3
      2282459.57     13186525.63      2282520.33     13185683.62
      2281504.68     13184633.25
#Sta/Elev= 30
  4242.9  259.29  4512.4   251.4  4682.8  242.78  4692.8   241.4  4722.9  240.62
    4773  237.13  4813.1  236.91  4840.3  233.52 4898.27  230.84  4973.6   227.6
  4993.4  225.22  5033.7  227.79    5039  230.91  5043.7   235.3    5207  233.52
  5242.2  235.27  5270.5   234.7  5305.8  236.75  5341.3  236.51  5348.2  237.62
  5489.7  239.43  5765.5  239.92  5871.7  236.96  6013.2  241.34  6283.9  252.29
  6425.5  258.61    6487  261.61    6494  261.12  6515.3  262.92  6548.2  262.71
#Mann= 5 ,-1 , 0
  4242.9     .16       0 4898.27     .07       0  5033.7     .16       0
  6283.9     .08       0  6425.5      .1       0
#XS Ineff= 2 , 0
       0                 5072.54       0  235.38
Permanent Ineff=
       F       T
Bank Sta=4898.27,5039
XS Rating Curve= 0 ,0
Exp/Cntr=0.3,0.1

Type RM Length L Ch R = 1 ,69621   ,463,463,463
BEGIN DESCRIPTION:
PENITAS CREEK 119.0
END DESCRIPTION:
XS GIS Cut Line= 4
      2283431.81     13186352.04      2283014.98     13185877.13
      2282589.78     13185631.54       2281635.5     13184651.23
#Sta/Elev= 30
  4210.3   262.4  4514.3  252.17  4606.4  247.69  4783.8  243.57  4833.2  240.91
  4891.9  241.13  4913.4  239.49  4919.9  233.79  4934.9  232.52 4944.73  229.84
  4950.7  228.85  4993.6   225.4  5058.4  226.75  5095.8  229.73    5345  233.83
  5408.8  231.68  5557.2   231.4  5649.1     234  5684.5  233.41  5691.5  234.84
  5712.8  234.11  5804.7  238.01  5953.3  240.24    6038  239.76    6137  235.01
  6165.3  237.51  6335.1  243.64  6566.4  255.37  6598.4  256.75  6701.3  261.65
#Mann= 5 ,-1 , 0
  4210.3     .16       0  4950.7     .07       0  5095.8     .16       0
  6566.4     .08       0  6598.4      .1       0
#XS Ineff= 2 , 0
       0                 5290.16       0  233.51
Permanent Ineff=
       F       T
Bank Sta=4944.73,5095.8
XS Rating Curve= 0 ,0
Exp/Cntr=0.3,0.1

Type RM Length L Ch R = 1 ,69158   ,881,881,881
BEGIN DESCRIPTION:
PENITAS CREEK 118.0
END DESCRIPTION:
XS GIS Cut Line= 4
      2283644.47     13186243.52      2283067.21     13185488.31
      2282772.07     13185388.48      2281917.04     13184598.55
#Sta/Elev= 30
  3812.3  259.98  4093.2  251.12    4114  249.35  4163.9  248.99    4407  241.04
  4785.9  235.11    4812   230.2  4817.3  234.21  4825.7   234.1  4836.2  232.91
  4843.5  229.91  4848.7  231.19  4857.3  230.64 4865.76  228.46  4867.9  227.57
  4937.8  226.65  5005.7  222.07  5008.9  222.57 5013.95  228.36  5015.7  230.93
  5199.1  228.97  5382.8  230.83    5461  227.46  5595.4  232.63  5679.9  232.41
  5779.1  235.45  5800.7  234.73  5977.6  244.27  6126.2  250.21  6238.5  257.37
#Mann= 4 ,-1 , 0
  3812.3     .16       0  4867.9     .07       0  5008.9     .16       0
  6238.5      .1       0
#XS Ineff= 2 , 0
       0 4818.13  234.46 5038.86       0  230.77
Permanent Ineff=
       T       T
Bank Sta=4865.76,5013.95
XS Rating Curve= 0 ,0
Exp/Cntr=0.3,0.1

Type RM Length L Ch R = 1 ,68277   ,557,557,557
BEGIN DESCRIPTION:
PENITAS CREEK 117.0
END DESCRIPTION:
XS GIS Cut Line= 3
      2283787.71     13186146.84      2283297.24      13185110.7
      2283193.08     13184173.23
#Sta/Elev= 30
  3665.4  258.96  3747.8  255.01  4019.4  246.19  4107.9  242.32  4130.1  242.43
  4287.6  236.95  4406.9  234.03    4462  231.59  4588.9  229.82  4716.4  226.45
  4782.8  225.95    4876  226.63  4936.4  225.48  4942.3  224.74  4966.6  223.19
  4996.5  219.61  5016.9  221.73  5026.9  221.85  5032.9  223.83  5037.9  224.03
 5039.31  225.42    5047  228.64  5057.1  230.38  5077.2  231.31  5318.7  237.35
  5389.1   237.5  5550.1  240.52  5576.2   242.5  5640.7  244.18    5755  249.38
#Mann= 3 ,-1 , 0
  3665.4     .16       0  4942.3     .07       0  5037.9     .16       0
Bank Sta=4936.4,5039.31
XS Rating Curve= 0 ,0
Exp/Cntr=0.3,0.1

Type RM Length L Ch R = 1 ,67720   ,846,846,846
BEGIN DESCRIPTION:
PENITAS CREEK 116.0
END DESCRIPTION:
XS GIS Cut Line= 3
      2283887.72     13186146.81      2283787.72     13184946.85
      2283487.72     13183846.84
#Sta/Elev= 30
  3823.9  258.97  4395.8  238.21    4747  232.49  4837.4  229.23  4897.6   224.9
 4901.97  223.44  4907.6  222.52  4937.7  220.25  4977.8  220.33  4997.7  217.73
  5007.9  220.38    5018  222.86  5025.5   224.4  5050.5  224.63    5225  224.62
    5339  227.95  5387.3  227.88  5525.5  233.28  5546.3  232.76  5575.6  234.98
  5615.4  236.62  5620.6  235.86  5660.3  239.85    5681  239.86  5784.7   246.5
    5795  245.24  5826.1  247.92  5950.5  252.83  6054.2  259.83  6168.2  264.94
#Mann= 3 ,-1 , 0
  3823.9     .16       0  4907.6     .07       0  5007.9     .16       0
#XS Ineff= 2 , 0
       0                 5125.91       0  225.54
Permanent Ineff=
       F       T
Bank Sta=4901.97,5018
XS Rating Curve= 0 ,0
Exp/Cntr=0.3,0.1

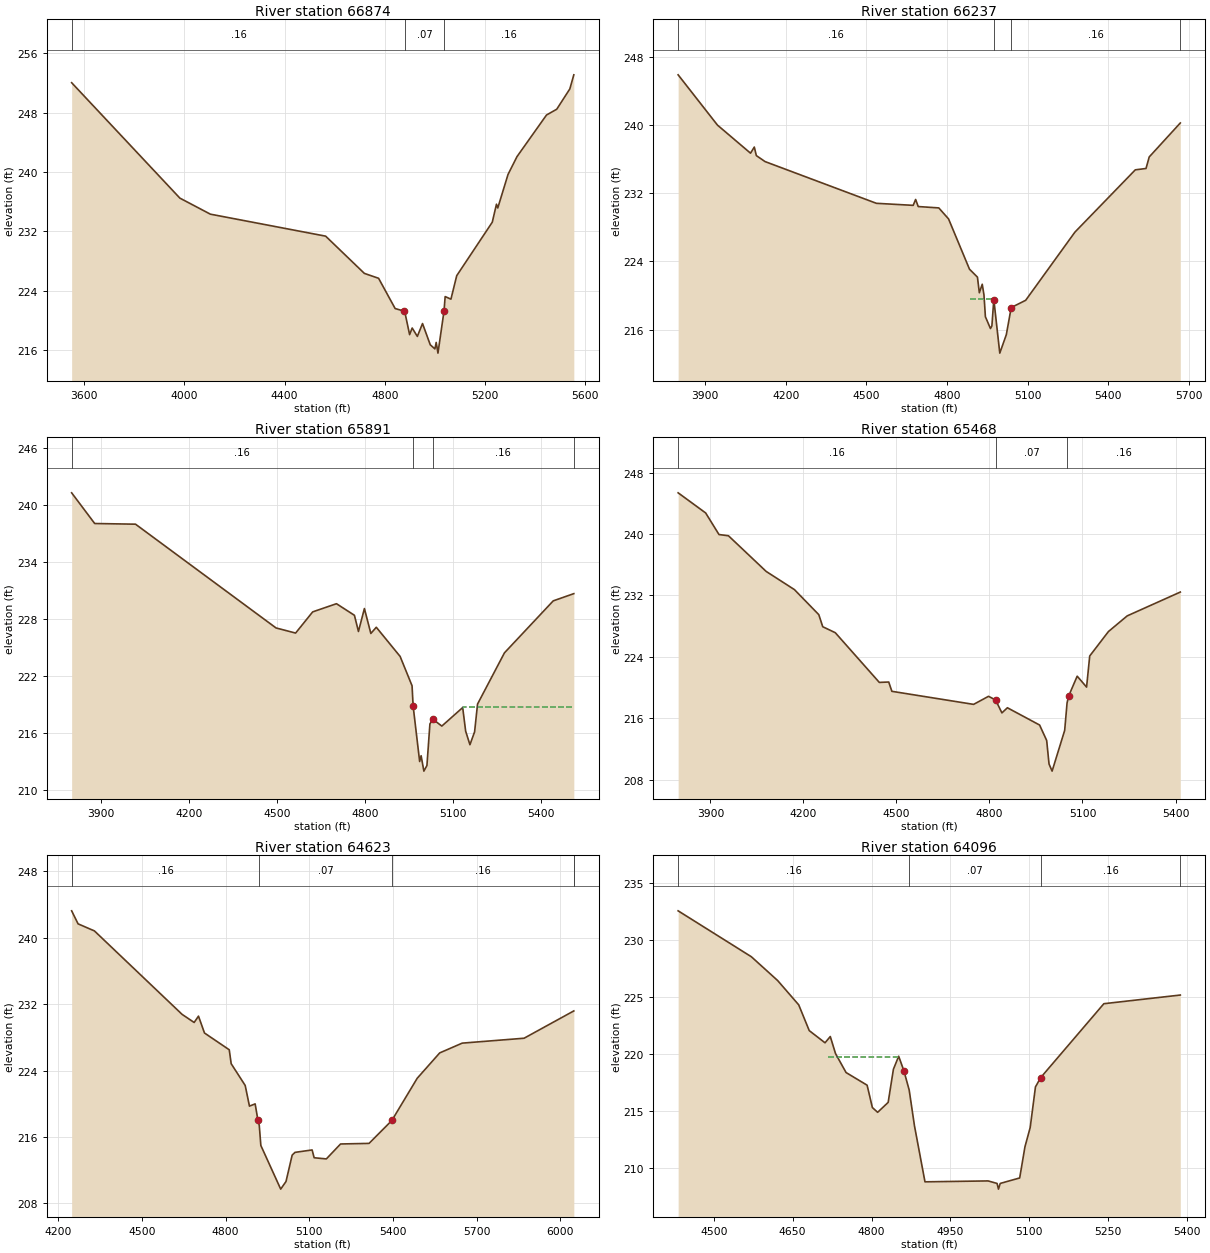
Type RM Length L Ch R = 1 ,66874   ,637,637,637
BEGIN DESCRIPTION:
Mapping XS 4d77f0eb
END DESCRIPTION:
XS GIS Cut Line= 3
       2283991.7     13185952.67      2284178.32     13184863.31
      2283957.08     13183991.37
#Sta/Elev= 30
  3549.9  252.02  3981.9  236.49  4103.7  234.33    4564  231.37  4718.5  226.36
  4775.3   225.7  4841.4  221.63  4877.2  221.28  4882.4  220.78  4899.1  218.12
  4909.4  219.01    4930  217.88  4950.7  219.61  4981.6  216.75  5000.1   216.2
  5005.3  217.07  5012.3  215.63 5036.36  221.25  5041.1  223.24  5064.1  222.89
  5087.2  226.05  5229.2  233.25  5245.9  235.67  5251.1  235.16    5292  239.67
  5327.8  242.07  5445.6  247.67  5486.5  248.45  5538.7  251.18  5554.7  253.08
#Mann= 3 ,-1 , 0
  3549.9     .16       0  4882.4     .07       0 5036.36     .16       0
Bank Sta=4877.2,5036.36
XS Rating Curve= 0 ,0
Exp/Cntr=0.3,0.1

Type RM Length L Ch R = 1 ,66237   ,346,346,346
BEGIN DESCRIPTION:
PENITAS CREEK 115.0
END DESCRIPTION:
XS GIS Cut Line= 3
      2284087.73     13185796.82      2284608.01     13184503.06
      2284413.35      13184070.5
#Sta/Elev= 30
  3799.4  245.86  3945.8  239.97  4068.8  236.68  4082.9   237.4  4090.4   236.4
  4122.7   235.7  4537.1  230.81  4674.1  230.57  4683.2  231.26  4692.9  230.43
  4769.4  230.27  4805.8  228.98  4883.7  223.09  4913.3  222.16  4920.3  220.33
  4931.1  221.33  4937.5  220.09  4942.9  217.52  4961.7  216.14    4967  216.44
  4974.2  219.54  4996.4  213.26  5020.8  215.43  5038.9   218.6  5092.8  219.45
  5275.9  227.43  5500.7  234.73  5540.6  234.89  5552.5  236.24  5668.2  240.22
#Mann= 4 ,-1 , 0
  3799.4     .16       0  4974.2     .07       0  5038.9     .16       0
  5668.2     .05       0
#XS Ineff= 1 ,-1
 4886.01 4974.09  219.64
Permanent Ineff=
       T
Bank Sta=4974.2,5038.9
XS Rating Curve= 0 ,0
Exp/Cntr=0.3,0.1

Type RM Length L Ch R = 1 ,65891   ,423,423,423
BEGIN DESCRIPTION:
PENITAS CREEK 114.0
END DESCRIPTION:
XS GIS Cut Line= 3
      2284386.66     13185800.79      2284824.61     13184933.97
      2284955.22     13184203.63
#Sta/Elev= 30
    3799  241.29  3877.6  238.06  4016.9  237.99  4496.2  227.07    4563  226.53
  4621.3  228.76  4702.4  229.62  4763.7   228.4  4777.4   226.7  4797.7  229.11
  4819.7  226.49  4838.3  227.14  4919.6  224.07  4960.3  220.98 4963.81  218.88
  4986.2  213.01  4991.2  213.62  5000.6     212    5011  212.59  5021.2  216.97
  5031.4  217.46  5061.8  216.74    5133  218.69  5143.1  216.21  5157.7  214.78
  5173.6  216.13  5183.7  219.06  5275.5  224.45  5441.9  229.92  5512.1  230.68
#Mann= 4 ,-1 , 0
    3799     .16       0 4963.81     .07       0  5031.4     .16       0
  5512.1      .1       0
#XS Ineff= 2 , 0
       0                 5133.68       0  218.71
Permanent Ineff=
       F       T
Bank Sta=4963.81,5031.4
XS Rating Curve= 0 ,0
Exp/Cntr=0.3,0.1

Type RM Length L Ch R = 1 ,65468   ,845,845,845
BEGIN DESCRIPTION:
PENITAS CREEK 113.0
END DESCRIPTION:
XS GIS Cut Line= 3
      2285037.71      13185746.9      2285237.72     13184546.85
      2285187.72     13184146.86
#Sta/Elev= 30
  3795.8  245.36  3884.6  242.74  3927.6  239.93  3958.1  239.77  4079.7  235.13
  4170.9  232.76  4249.5   229.5  4262.2  227.93  4302.7  227.15  4444.7  220.68
  4475.1  220.73  4485.2  219.52  4748.8  217.82    4797  218.87  4819.8  218.39
  4840.1  216.71  4857.8  217.38  4961.7  215.13  4984.5  213.12  4992.1  210.06
    5002  209.13  5042.6  214.44  5050.2  217.99  5055.2  218.89  5082.9  221.49
  5113.2  220.07  5123.3  224.12  5183.7   227.3  5244.2  229.34  5415.5  232.44
#Mann= 3 ,-1 , 0
  3795.8     .16       0  4819.8     .07       0  5050.2     .16       0
Bank Sta=4819.8,5055.2
XS Rating Curve= 0 ,0
Exp/Cntr=0.3,0.1

Type RM Length L Ch R = 1 ,64623   ,527,527,527
BEGIN DESCRIPTION:
PENITAS CREEK 112.0
END DESCRIPTION:
XS GIS Cut Line= 4
      2285402.27     13185813.84      2285693.08     13185319.04
      2285810.26     13184746.12      2285728.05     13184110.02
#Sta/Elev= 30
  4248.3  243.25  4271.4  241.68    4330  240.83  4644.4  230.77  4687.4   229.8
    4703  230.56  4724.5  228.53  4813.2  226.51  4820.2  224.83  4870.4  222.21
  4885.7  219.72  4906.1  219.99  4915.7  218.09  4920.8  217.41  4926.5  214.98
  4997.7  209.72  5016.7  210.64  5038.8  213.82    5049  214.15  5110.3  214.44
  5117.6   213.5  5161.3  213.36  5212.3  215.16  5314.4  215.23  5396.1  217.99
  5486.9  223.07  5567.6  226.13  5648.3  227.31  5870.1   227.9  6048.4  231.19
#Mann= 5 ,-1 , 0
  4248.3     .16       0  4920.8     .07       0  5396.1     .16       0
  6048.4      .1       0  6048.4      .1       0
Bank Sta=4915.7,5396.1
XS Rating Curve= 0 ,0
Exp/Cntr=0.3,0.1

Type RM Length L Ch R = 1 ,64096   ,63,63,63
BEGIN DESCRIPTION:
Mapping XS 2e64df63
END DESCRIPTION:
XS GIS Cut Line= 2
      2286131.44     13185536.02      2286122.77     13184581.56
#Sta/Elev= 30
  4432.4  232.56  4571.6  228.53  4621.6  226.44  4661.6  224.31  4681.6  222.05
  4711.6  220.98  4721.6  221.53  4731.6  220.03  4751.6  218.37  4791.6  217.26
  4801.6   215.3  4811.6  214.88  4831.6  215.75  4841.6  218.66  4851.6   219.8
  4861.6  218.51  4871.6  216.83  4881.6   213.7  4901.6  208.78  5021.6  208.86
  5038.6  208.64  5041.3  208.14  5044.6  208.64  5081.6  209.12  5091.6  211.85
  5101.6  213.55  5111.6  217.11  5121.6  217.93  5241.6  224.41  5386.9  225.17
#Mann= 4 ,-1 , 0
  4432.4     .16       0  4871.6     .07       0  5121.6     .16       0
  5386.9     .05       0
#XS Ineff= 1 ,-1
  4717.1 4849.74  219.69
Permanent Ineff=
       T
Bank Sta=4861.6,5121.6
XS Rating Curve= 0 ,0
Exp/Cntr=0.3,0.1

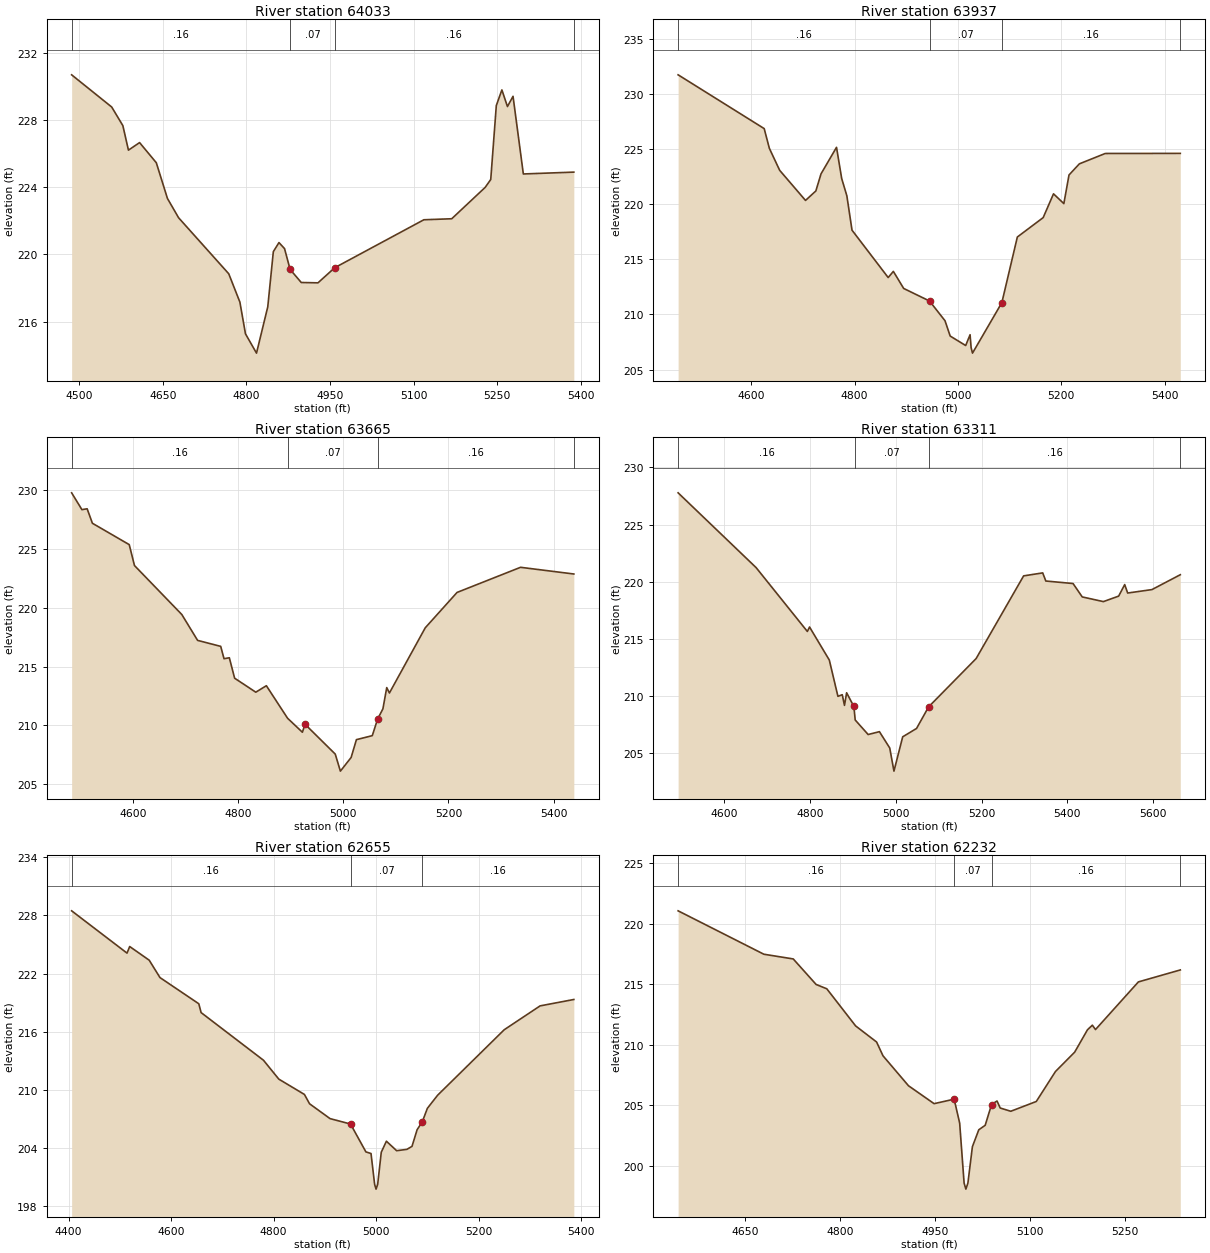
Type RM Length L Ch R = 1 ,64033   ,96,96,96
BEGIN DESCRIPTION:
PENITAS CREEK 111.0
END DESCRIPTION:
XS GIS Cut Line= 2
      2286183.31     13185488.78      2286193.73     13184587.74
#Sta/Elev= 30
  4486.4  230.71  4558.3  228.79  4578.3  227.68  4588.3  226.22  4608.3  226.67
  4638.3  225.47  4658.3  223.34  4678.3  222.19  4768.3  218.85  4788.3  217.16
  4798.3  215.27  4818.1  214.12  4838.3  216.88  4848.3  220.17  4858.4  220.71
  4868.4  220.35  4878.4  219.11  4898.4  218.33  4928.4  218.31  4958.4  219.21
  5118.4  222.07  5168.4  222.13  5228.4     224  5238.4  224.47  5248.4  228.88
  5258.4  229.81  5268.4  228.82  5278.4  229.43  5296.9   224.8  5387.5  224.91
#Mann= 4 ,-1 , 0
  4486.4     .16       0  4878.4     .07       0  4958.4     .16       0
  5387.5     .05       0
#XS Ineff= 2 , 0
       0 4858.03  220.69               0
Permanent Ineff=
       T       F
Bank Sta=4878.4,4958.4
XS Rating Curve= 0 ,0
Exp/Cntr=0.3,0.1

Type RM Length L Ch R = 1 ,63937   ,272,272,272
BEGIN DESCRIPTION:
Mapping XS d662aeef
END DESCRIPTION:
XS GIS Cut Line= 2
      2286270.33      13185553.4      2286257.32     13184581.48
#Sta/Elev= 30
  4458.4  231.75    4625  226.87    4635  225.08    4655  223.08    4705  220.35
    4725  221.21    4735  222.76    4765  225.17    4775  222.34    4785  220.77
    4795  217.65    4865  213.35    4875  213.91    4895  212.36    4945  211.22
    4975  209.43    4985  208.04    5015  207.18  5023.5  208.16  5025.5  206.99
  5028.2  206.49    5085  211.07    5115  217.03    5165  218.79    5185  220.95
    5205  220.06    5215  222.66    5235  223.67    5285  224.61  5430.4  224.62
#Mann= 4 ,-1 , 0
  4458.4     .16       0    4945     .07       0    5085     .16       0
  5430.4     .05       0
Bank Sta=4945,5085
XS Rating Curve= 0 ,0
Exp/Cntr=0.3,0.1

Type RM Length L Ch R = 1 ,63665   ,354,354,354
BEGIN DESCRIPTION:
PENITAS CREEK 110.0
END DESCRIPTION:
XS GIS Cut Line= 3
      2286533.46     13185606.29      2286545.96     13185350.05
      2286458.46     13184656.29
#Sta/Elev= 30
  4482.8  229.79  4502.3  228.36  4512.3  228.43  4522.3   227.2  4592.4  225.38
  4602.4   223.6  4692.5  219.43  4722.5  217.23  4766.5  216.72  4772.8  215.67
  4782.9  215.75    4793  214.01  4833.3  212.82  4853.4  213.37  4893.8   210.6
    4922  209.41    4927  210.09  4984.5  207.55  4994.3   206.1  5014.7  207.26
  5024.8  208.78    5055  209.12  5065.1  210.53  5075.2   211.4  5082.5  213.21
  5087.6  212.75  5155.8   218.3  5216.3  221.31  5337.2  223.45  5438.6  222.88
#Mann= 4 ,-1 , 0
  4482.8     .16       0  4893.8     .07       0  5065.1     .16       0
  5438.6      .1       0
Bank Sta=4927,5065.1
XS Rating Curve= 0 ,0
Exp/Cntr=0.3,0.1

Type RM Length L Ch R = 1 ,63311   ,656,656,656
BEGIN DESCRIPTION:
PENITAS CREEK 109.0
END DESCRIPTION:
XS GIS Cut Line= 4
      2286883.46     13185668.83      2286877.21     13185400.05
      2286808.46     13184837.55      2286577.22     13184593.82
#Sta/Elev= 30
  4491.9  227.77  4673.9  221.23  4793.4  215.65  4798.5  216.04  4844.6  213.15
  4864.7  209.98  4874.8  210.12    4880  209.19    4885  210.29 4901.93  209.09
    4905  207.91  4935.2  206.64  4961.5  206.89  4985.6  205.46  4995.4  203.44
  5015.8  206.44  5048.1  207.17  5076.3  209.06  5187.1  213.28  5297.9  220.51
  5342.4  220.77  5349.7  220.06  5413.2  219.84  5434.6  218.67    5484  218.26
  5519.6  218.74  5533.7  219.75  5540.6  219.01  5597.2  219.31  5663.4  220.61
#Mann= 4 ,-1 , 0
  4491.9     .16       0    4905     .07       0  5076.3     .16       0
  5663.4      .1       0
Bank Sta=4901.93,5076.3
XS Rating Curve= 0 ,0
Exp/Cntr=0.3,0.1

Type RM Length L Ch R = 1 ,62655   ,423,423,423
BEGIN DESCRIPTION:
PENITAS CREEK 108.0
END DESCRIPTION:
XS GIS Cut Line= 3
      2287408.46     13185675.04      2287464.71     13185425.05
      2287464.71     13184700.99
#Sta/Elev= 30
  4405.8  228.47  4513.9  224.11  4519.1  224.79  4557.2  223.38  4578.2  221.59
    4654  218.89  4658.5  217.98  4780.2  213.07  4810.2  211.12  4860.2  209.54
  4870.2  208.58  4910.2  207.05  4950.2  206.49  4980.2  203.62  4990.2  203.45
  4997.2  200.28    5000  199.78  5003.2  200.28  5010.2  203.58  5020.2  204.72
  5040.2  203.74  5060.2  203.88  5070.2  204.19  5080.2  205.91  5090.2  206.71
  5100.2  208.11  5120.2  209.46  5250.2  216.21  5320.2  218.67  5386.1  219.33
#Mann= 3 , 0 , 0
  4405.8     .16       0  4950.2     .07       0  5090.2     .16       0
Bank Sta=4950.2,5090.2
XS Rating Curve= 0 ,0
Exp/Cntr=0.3,0.1

Type RM Length L Ch R = 1 ,62232   ,417,417,417
BEGIN DESCRIPTION:
PENITAS CREEK 107.0
END DESCRIPTION:
XS GIS Cut Line= 3
       2287789.7     13185612.58      2287845.96     13185387.55
      2287920.93     13184831.54
#Sta/Elev= 30
  4544.3  221.07  4679.7  217.48  4726.1  217.09  4762.2  214.98  4779.1  214.62
  4824.6  211.55  4857.7  210.22  4867.8  209.08  4908.1   206.6  4948.5  205.12
  4980.2  205.49  4988.9  203.51  4995.9  198.55  4998.7  198.05  5001.9  198.55
    5009  201.56  5019.1  202.96  5029.2  203.33  5039.3  205.05  5047.9  205.34
  5052.9  204.76  5069.6  204.49  5109.9   205.3  5140.2  207.78  5170.5  209.38
  5190.7  211.23  5198.4  211.61  5203.4  211.25  5271.1  215.19  5337.3  216.18
#Mann= 4 ,-1 , 0
  4544.3     .16       0  4980.2     .07       0  5039.3     .16       0
  5337.3     .16       0
Bank Sta=4980.2,5039.3
XS Rating Curve= 0 ,0
Exp/Cntr=0.3,0.1

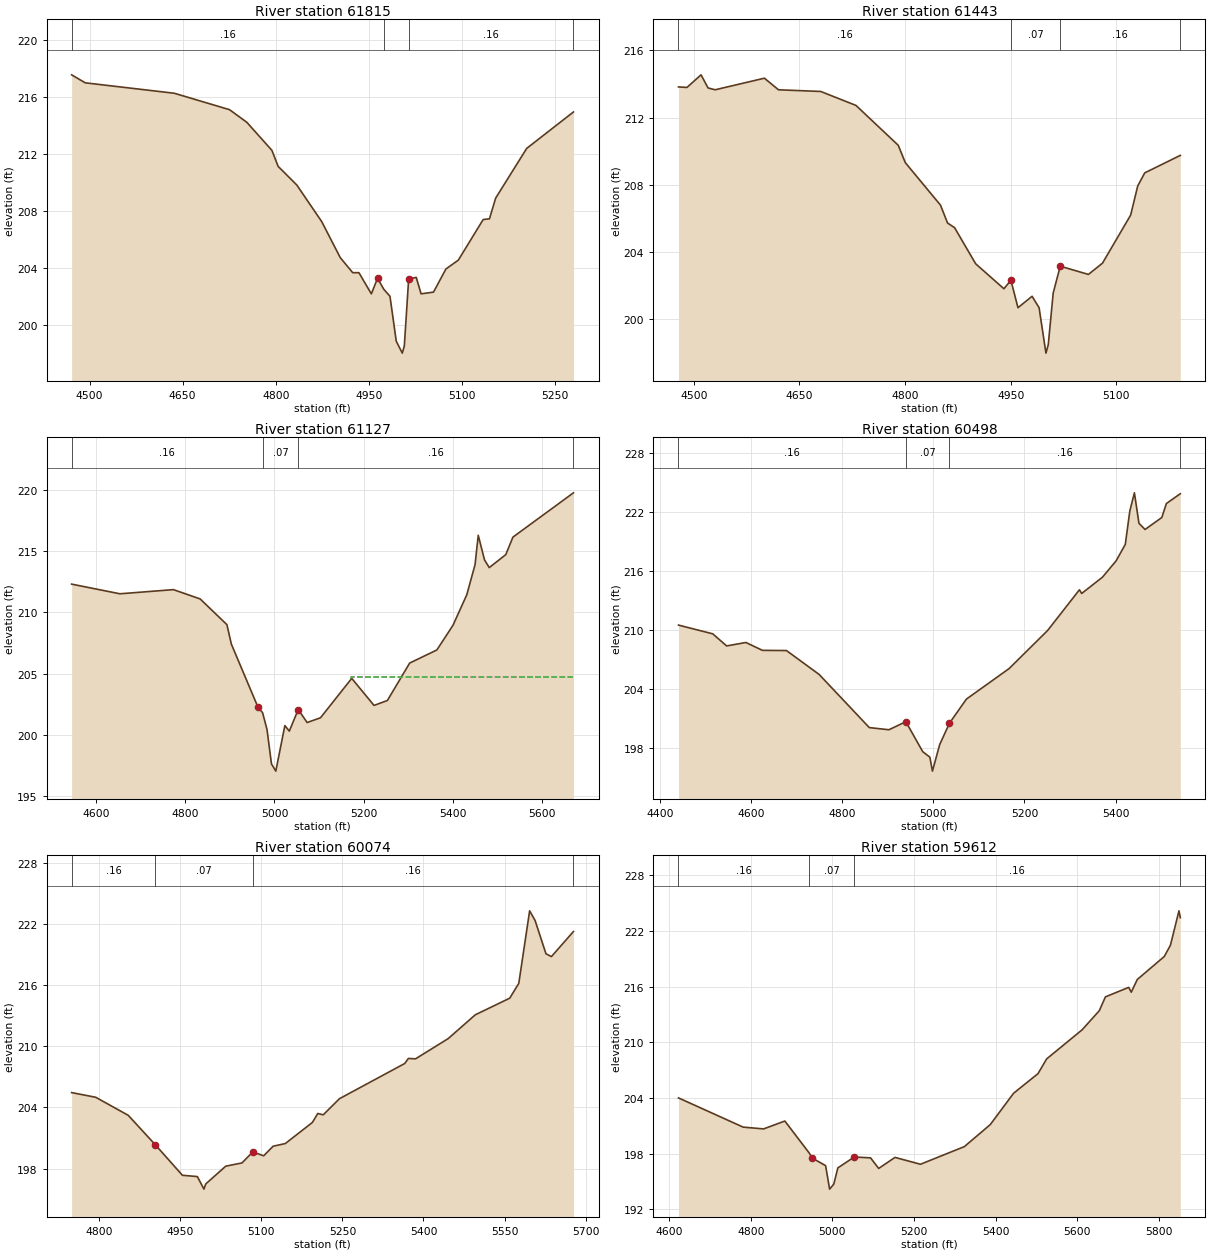
Type RM Length L Ch R = 1 ,61815   ,372,372,372
BEGIN DESCRIPTION:
PENITAS CREEK 106.0
END DESCRIPTION:
XS GIS Cut Line= 3
      2288145.95     13185656.32      2288283.46     13185387.55
       2288302.2      13184881.6
#Sta/Elev= 30
  4471.2  217.53  4493.1  216.97  4636.6  216.24  4725.5  215.09  4753.3  214.21
  4793.8  212.24  4803.8  211.12  4833.8  209.82  4873.9  207.26  4903.9  204.73
  4923.9  203.68  4933.9  203.68  4953.9   202.2  4963.9  203.29  4973.9  202.52
  4983.9  202.03    4994  198.89  5003.7  198.05    5007  198.55    5014  203.24
  5026.2  203.35    5034   202.2    5054  202.32    5074  203.94    5094  204.56
    5134   207.4  5144.1  207.45  5154.1   208.9  5204.1  212.38  5279.4  214.93
#Mann= 4 ,-1 , 0
  4471.2     .16       0  4973.9     .07       0    5014     .16       0
  5279.4      .1       0
Bank Sta=4963.9,5014
XS Rating Curve= 0 ,0
Exp/Cntr=0.3,0.1

Type RM Length L Ch R = 1 ,61443   ,316,316,316
BEGIN DESCRIPTION:
PENITAS CREEK 105.0
END DESCRIPTION:
XS GIS Cut Line= 2
      2288658.46     13185718.84      2288658.46     13185006.34
#Sta/Elev= 30
  4478.4  213.83  4490.4   213.8  4510.4  214.55  4520.4  213.77  4530.4  213.66
  4600.4  214.35  4620.4  213.66  4680.4  213.56  4730.4  212.73  4790.4  210.36
  4800.4  209.33  4850.4   206.8  4860.4  205.74  4870.4  205.46  4900.4  203.31
  4940.4  201.83  4950.4  202.33  4960.4   200.7  4980.4  201.38  4990.4   200.7
  5000.1     198  5003.4   198.5  5010.4  201.57  5020.4  203.17  5060.4  202.68
  5080.4  203.35  5120.4  206.21  5130.4  207.94  5140.4  208.72  5190.9  209.76
#Mann= 4 ,-1 , 0
  4478.4     .16       0  4950.4     .07       0  5020.4     .16       0
  5190.9      .1       0
Bank Sta=4950.4,5020.4
XS Rating Curve= 0 ,0
Exp/Cntr=0.3,0.1

Type RM Length L Ch R = 1 ,61127   ,629,629,629
BEGIN DESCRIPTION:
PENITAS CREEK 104.0
END DESCRIPTION:
XS GIS Cut Line= 3
      2288977.21     13185675.09      2288964.71     13184887.55
      2288852.19     13184568.77
#Sta/Elev= 30
    4545  212.31  4653.3  211.52  4773.3  211.86  4833.3   211.1  4893.3     209
  4903.3  207.41  4963.3  202.23  4973.3  201.81  4983.3  200.43  4993.3  197.62
    5003  197.03  5023.3  200.75  5033.3   200.3  5053.3  202.06  5073.3     201
  5103.3  201.39  5173.3  204.61  5223.3   202.4  5253.3   202.8  5303.3  205.86
  5364.3  206.93  5400.5  208.95  5431.4  211.44    5450  213.91  5457.1   216.3
  5471.2  214.29  5481.8  213.66  5518.9  214.72  5534.9  216.15  5670.7  219.77
#Mann= 4 ,-1 , 0
    4545     .16       0  4973.3     .07       0  5053.3     .16       0
  5670.7     .05       0
#XS Ineff= 2 , 0
       0                 5171.81       0  204.74
Permanent Ineff=
       F       T
Bank Sta=4963.3,5053.3
XS Rating Curve= 0 ,0
Exp/Cntr=0.3,0.1

Type RM Length L Ch R = 1 ,60498   ,424,424,424
BEGIN DESCRIPTION:
PENITAS CREEK 103.0
END DESCRIPTION:
XS GIS Cut Line= 4
      2289245.93     13185600.07      2289383.46     13185512.55
      2289683.46     13185000.05      2289708.46     13184656.33
#Sta/Elev= 30
  4440.6  210.46  4515.8  209.57  4546.3  208.34  4588.6  208.69  4624.8  207.89
  4677.6  207.87  4749.3  205.44  4859.4  200.03  4902.5  199.81  4939.6  200.63
  4976.7  197.58  4992.4  197.02    4998   195.6  5013.9   198.3  5035.4  200.48
  5072.6  202.93  5166.4  206.04  5250.8  209.91  5320.6  214.05  5325.6  213.68
  5371.1  215.33  5401.2     217  5421.3  218.67  5431.3  222.08  5441.3  223.92
  5451.3  220.82  5464.7  220.19  5501.5  221.41  5511.5  222.83  5542.1  223.83
#Mann= 4 ,-1 , 0
  4440.6     .16       0  4939.6     .07       0  5035.4     .16       0
  5542.1     .05       0
Bank Sta=4939.6,5035.4
XS Rating Curve= 0 ,0
Exp/Cntr=0.3,0.1

Type RM Length L Ch R = 1 ,60074   ,462,462,462
BEGIN DESCRIPTION:
PENITAS CREEK 102.0
END DESCRIPTION:
XS GIS Cut Line= 3
      2289945.96     13185581.34      2289983.46      13185056.3
       2289939.7     13184656.27
#Sta/Elev= 30
  4748.8  205.46  4793.4     205  4853.6  203.23  4903.7  200.34  4953.8  197.35
  4981.5  197.22  4993.7  195.99  4996.9  196.49    5034  198.24  5064.1  198.56
  5084.1  199.64  5104.2  199.26  5121.8   200.2  5144.3  200.46  5194.4  202.53
  5204.4  203.41  5214.5  203.28  5244.5  204.86  5365.2  208.31  5372.1  208.81
  5385.3  208.77  5445.6  210.75  5495.9  213.09  5559.6  214.72  5576.4  216.17
  5596.5  223.29  5606.6  222.34  5626.7  219.08  5636.8   218.8  5677.6  221.26
#Mann= 4 ,-1 , 0
  4748.8     .16       0  4903.7     .07       0  5084.1     .16       0
  5677.6     .05       0
Bank Sta=4903.7,5084.1
XS Rating Curve= 0 ,0
Exp/Cntr=0.3,0.1

Type RM Length L Ch R = 1 ,59612   ,738,738,738
BEGIN DESCRIPTION:
PENITAS CREEK 101.0
END DESCRIPTION:
XS GIS Cut Line= 4
      2290270.94     13185662.57      2290408.46     13185475.05
      2290414.71     13184950.05      2290152.49     13184556.72
#Sta/Elev= 30
  4622.7  204.02  4781.3  200.87  4831.5  200.68  4883.4  201.53  4943.4  198.07
    4950  197.55  4983.4  196.72  4993.2  194.19  5003.4  194.73  5013.4  196.48
  5053.5  197.65  5093.5  197.56  5113.5  196.42  5153.5  197.61  5215.9  196.87
  5323.5  198.77    5387  201.14  5444.2  204.52  5504.2  206.64  5525.2  208.22
  5612.3  211.36  5654.4  213.42  5669.4  214.91  5726.5  215.93  5732.7  215.41
  5747.5  216.78  5813.7  219.26  5828.7  220.47  5849.7  224.18    5853  223.44
#Mann= 4 ,-1 , 0
  4622.7     .16       0  4943.4     .07       0  5053.5     .16       0
    5853     .05       0
Bank Sta=4950,5053.5
XS Rating Curve= 0 ,0
Exp/Cntr=0.3,0.1