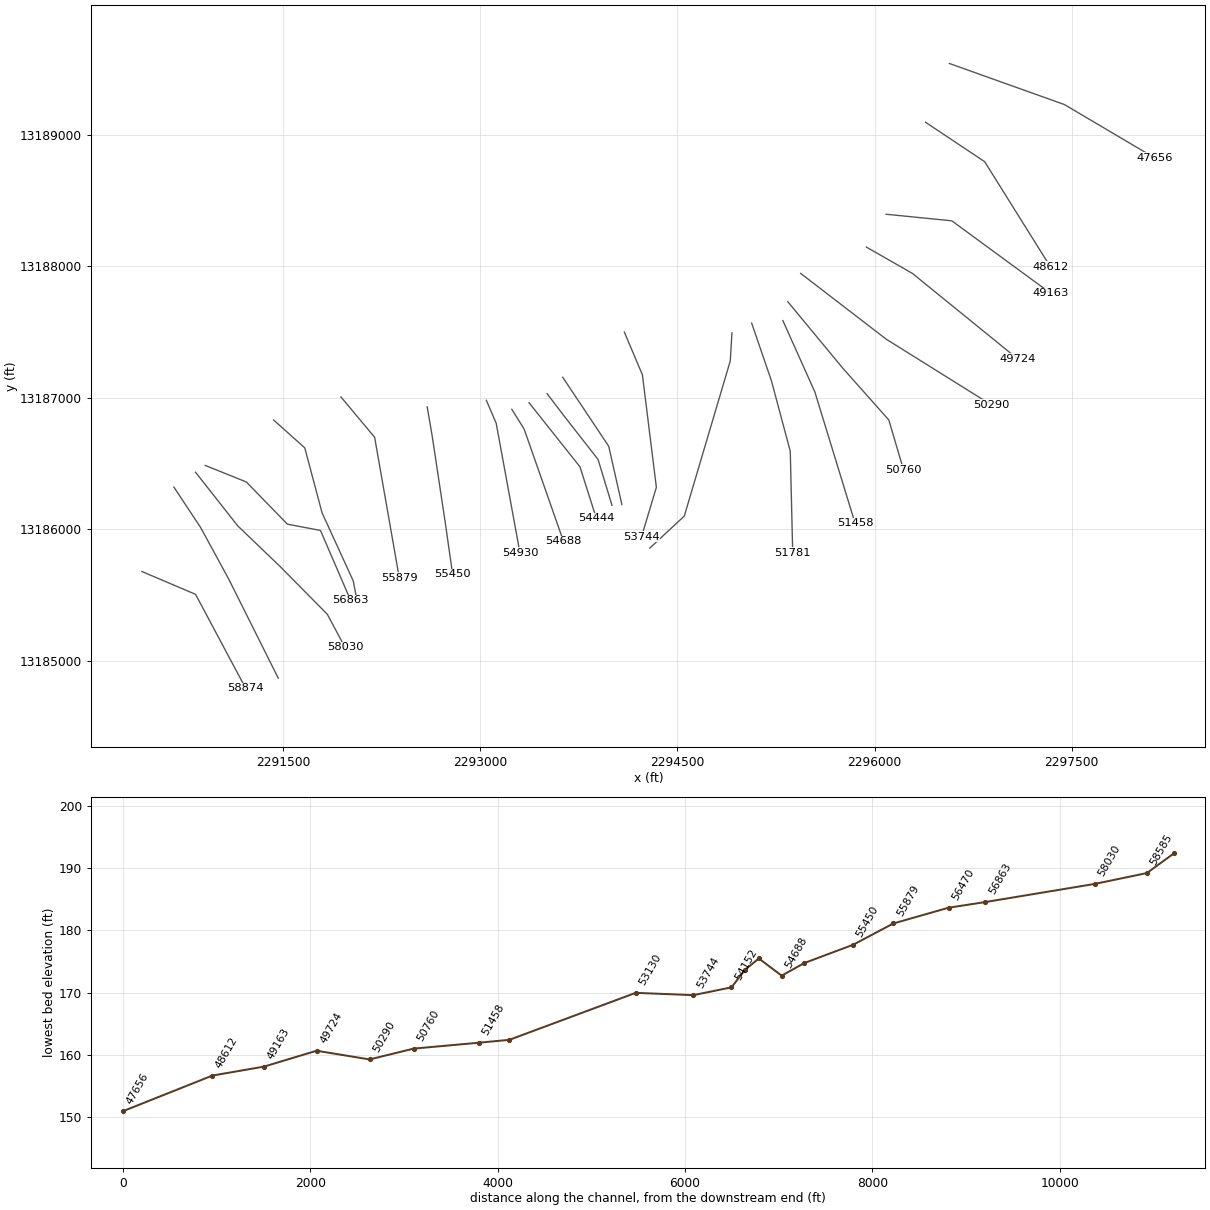
HEC-RAS study PENITAS CREEK.prj: PENITAS CREEK Base Level Engineering

--- PENITAS CREEK.g01 (geometry) --- (continued)

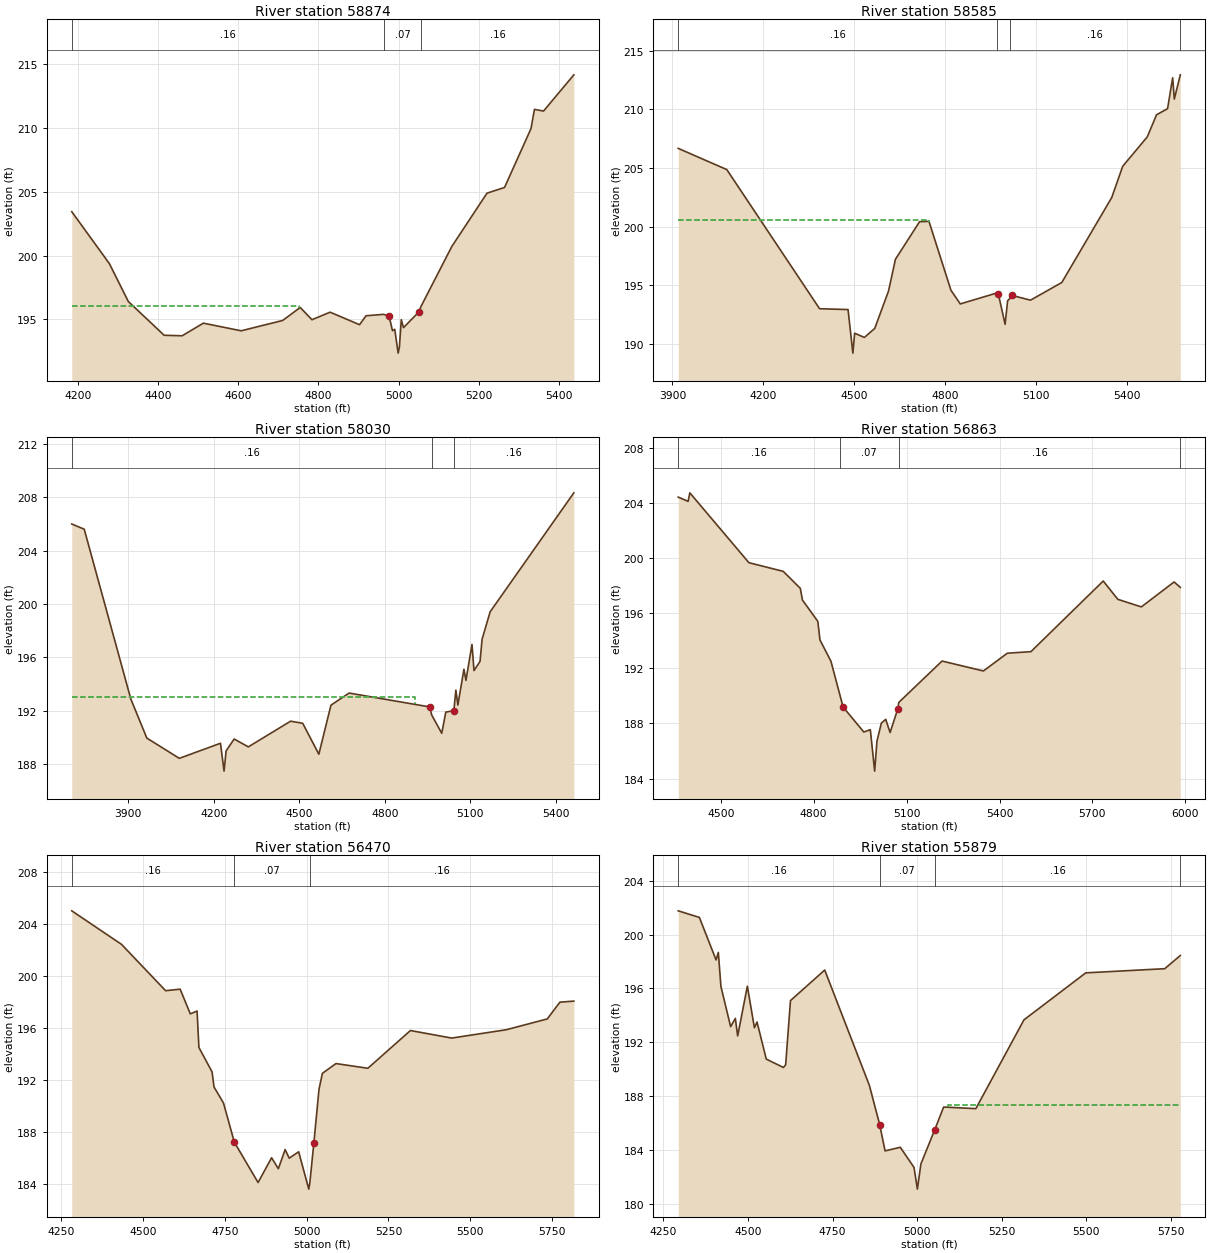
Type RM Length L Ch R = 1 ,58874   ,289,289,289
BEGIN DESCRIPTION:
Mapping XS dd524fad
END DESCRIPTION:
XS GIS Cut Line= 3
       2290425.5     13185678.19      2290833.49     13185504.58
      2291214.53     13184790.13
#Sta/Elev= 30
  4184.4  203.44  4278.2  199.37  4325.5   196.4    4415  193.75    4460  193.71
  4512.8   194.7  4607.2   194.1  4710.7  194.91  4754.6  195.93  4783.9  194.97
  4829.2  195.56  4902.6  194.58  4918.9  195.28  4962.9  195.39  4976.5  195.25
  4984.8  194.11  4990.5  194.22    4999  192.35  5002.2  192.85  5006.8  194.97
  5012.4  194.35  5050.7  195.58  5056.2  196.02  5132.9  200.71  5220.7  204.89
  5264.6  205.34  5330.5  209.95  5339.2  211.46  5361.9  211.33  5437.5  214.17
#Mann= 3 ,-1 , 0
  4184.4     .16       0  4962.9     .07       0  5056.2     .16       0
#XS Ineff= 2 , 0
       0 4752.75  196.03               0
Permanent Ineff=
       T       F
Bank Sta=4976.5,5050.7
XS Rating Curve= 0 ,0
Exp/Cntr=0.3,0.1

Type RM Length L Ch R = 1 ,58585   ,555,555,555
BEGIN DESCRIPTION:
PENITAS CREEK 100.0
END DESCRIPTION:
XS GIS Cut Line= 4
      2290668.55     13186320.57      2290872.55     13186012.39
      2291085.23     13185621.77      2291462.79     13184866.65
#Sta/Elev= 30
    3919  206.67  4079.4  204.86    4386  192.98    4480  192.91  4495.9  189.19
  4501.8  190.89    4534  190.53  4568.2   191.3  4613.7  194.49  4636.5   197.2
  4716.2  200.41  4747.3  200.44  4819.9  194.56  4850.7  193.39  4970.9  194.32
  4976.5  194.24  4998.8  191.65  5007.2  193.67  5015.6  193.87  5021.2  194.12
  5082.7  193.71  5186.1  195.22    5351  202.47  5387.3  205.14  5468.4  207.65
  5499.1  209.54  5535.5  210.06  5552.3   212.7  5557.8  210.88  5577.6  212.95
#Mann= 4 ,-1 , 0
    3919     .16       0  4970.9     .07       0  5015.6     .16       0
  5577.6      .1       0
#XS Ineff= 2 , 0
       0 4747.56  200.54               0
Permanent Ineff=
       T       F
Bank Sta=4976.5,5021.2
XS Rating Curve= 0 ,0
Exp/Cntr=0.3,0.1

Type RM Length L Ch R = 1 ,58030   ,1167,1167,1167
BEGIN DESCRIPTION:
PENITAS CREEK 99.0
END DESCRIPTION:
XS GIS Cut Line= 5
      2290833.47     13186433.42      2291154.67     13186025.42
      2291475.85     13185717.26      2291836.09     13185352.67
      2291970.38     13185101.42
#Sta/Elev= 30
  3701.9     206  3745.6  205.61  3909.2  192.86  3965.3  189.93  4079.3  188.41
  4223.7  189.54  4236.3  187.45  4243.5  188.97  4271.8  189.86  4321.4  189.27
  4469.9   191.2  4512.3  191.04  4568.9  188.72  4611.4   192.4    4675  193.31
  4957.8  192.27  4964.8  191.67  5000.2  190.29  5014.4  191.88  5042.7  191.99
  5049.7  193.53  5056.8  192.41    5078   195.1  5085.1  194.26  5106.3  196.96
  5113.4     195  5134.6  195.69  5141.7  197.35    5170  199.41  5463.7  208.34
#Mann= 3 ,-1 , 0
  3701.9     .16       0  4964.8     .07       0  5042.7     .16       0
#XS Ineff= 2 , 0
       0 4905.18  193.01               0
Permanent Ineff=
       T       F
Bank Sta=4957.8,5042.7
XS Rating Curve= 0 ,0
Exp/Cntr=0.3,0.1

Type RM Length L Ch R = 1 ,56863   ,393,393,393
BEGIN DESCRIPTION:
Mapping XS ae27ebe0
END DESCRIPTION:
XS GIS Cut Line= 5
      2290907.25     13186485.49      2291219.77     13186359.62
      2291532.27     13186038.44      2291784.01     13185990.69
      2292013.38     13185458.37
#Sta/Elev= 30
  4362.8  204.43  4394.8  204.12  4400.2  204.74  4590.9  199.67  4701.8  199.04
  4756.9  197.81  4763.8  196.96  4813.4  195.41  4820.4  194.06  4855.9  192.51
  4884.2  190.11 4895.13  189.19  4961.9  187.38    4983  187.55  4996.9  184.54
  5004.3  186.71  5018.5  188.02  5032.6   188.3  5046.8  187.34 5071.92  189.08
    5075  189.53  5214.5  192.53    5348  191.81  5425.3   193.1  5501.3  193.21
  5734.9  198.34  5781.9  197.01  5857.9  196.46  5963.6  198.27  5983.7  197.88
#Mann= 4 ,-1 , 0
  4362.8     .16       0  4884.2     .07       0    5075     .16       0
  5983.7      .1       0
Bank Sta=4895.13,5071.92
XS Rating Curve= 0 ,0
Exp/Cntr=0.3,0.1

Type RM Length L Ch R = 1 ,56470   ,591,591,591
BEGIN DESCRIPTION:
PENITAS CREEK 98.0
END DESCRIPTION:
XS GIS Cut Line= 5
      2291427.19     13186831.32      2291664.71      13186618.8
      2291795.96     13186125.05      2292033.46      13185606.3
      2292058.47     13185475.01
#Sta/Elev= 30
  4282.6  205.02  4434.7  202.44  4569.3  198.88  4613.7     199  4644.7   197.1
  4665.4  197.32    4671  194.52  4711.2  192.64  4717.2  191.48  4746.1  190.25
  4779.2  187.24  4851.7  184.14  4893.1  186.04  4913.7   185.2  4934.4  186.67
  4946.9  186.01  4975.8   186.5  5006.6  183.63  5009.9  184.13  5022.1  187.16
  5037.9  191.31  5048.3  192.53  5089.7  193.28  5187.2  192.92  5317.2  195.82
  5443.2  195.24  5609.8  195.88  5735.2  196.71  5773.8     198  5816.4  198.08
#Mann= 3 ,-1 , 0
  4282.6     .16       0  4779.2     .07       0  5009.9     .16       0
Bank Sta=4779.2,5022.1
XS Rating Curve= 0 ,0
Exp/Cntr=0.3,0.1

Type RM Length L Ch R = 1 ,55879   ,429,429,429
BEGIN DESCRIPTION:
PENITAS CREEK 97.0
END DESCRIPTION:
XS GIS Cut Line= 3
      2291939.71      13187006.3      2292195.96     13186700.05
      2292383.41     13185631.58
#Sta/Elev= 30
  4293.8  201.77  4356.3  201.28  4405.7  198.12  4412.3  198.68    4420  196.15
  4448.7  193.16  4462.6  193.78  4469.5  192.47  4498.1  196.17    4519  193.08
  4526.7  193.51  4554.1  190.75  4604.8  190.13  4611.3  190.33  4625.6   195.1
  4726.8  197.37  4858.8   188.8  4889.3  185.88  4905.2  183.93  4950.2   184.2
  4990.8   182.7  5000.7  181.09  5011.1  182.96  5051.7  185.48  5078.3  187.19
  5173.5  187.07  5315.8  193.67  5498.4  197.16  5731.9  197.47  5777.9  198.45
#Mann= 4 ,-1 , 0
  4293.8     .16       0  4889.3     .07       0  5051.7     .16       0
  5777.9      .1       0
#XS Ineff= 2 , 0
       0                 5092.02       0  187.37
Permanent Ineff=
       F       T
Bank Sta=4889.3,5051.7
XS Rating Curve= 0 ,0
Exp/Cntr=0.3,0.1

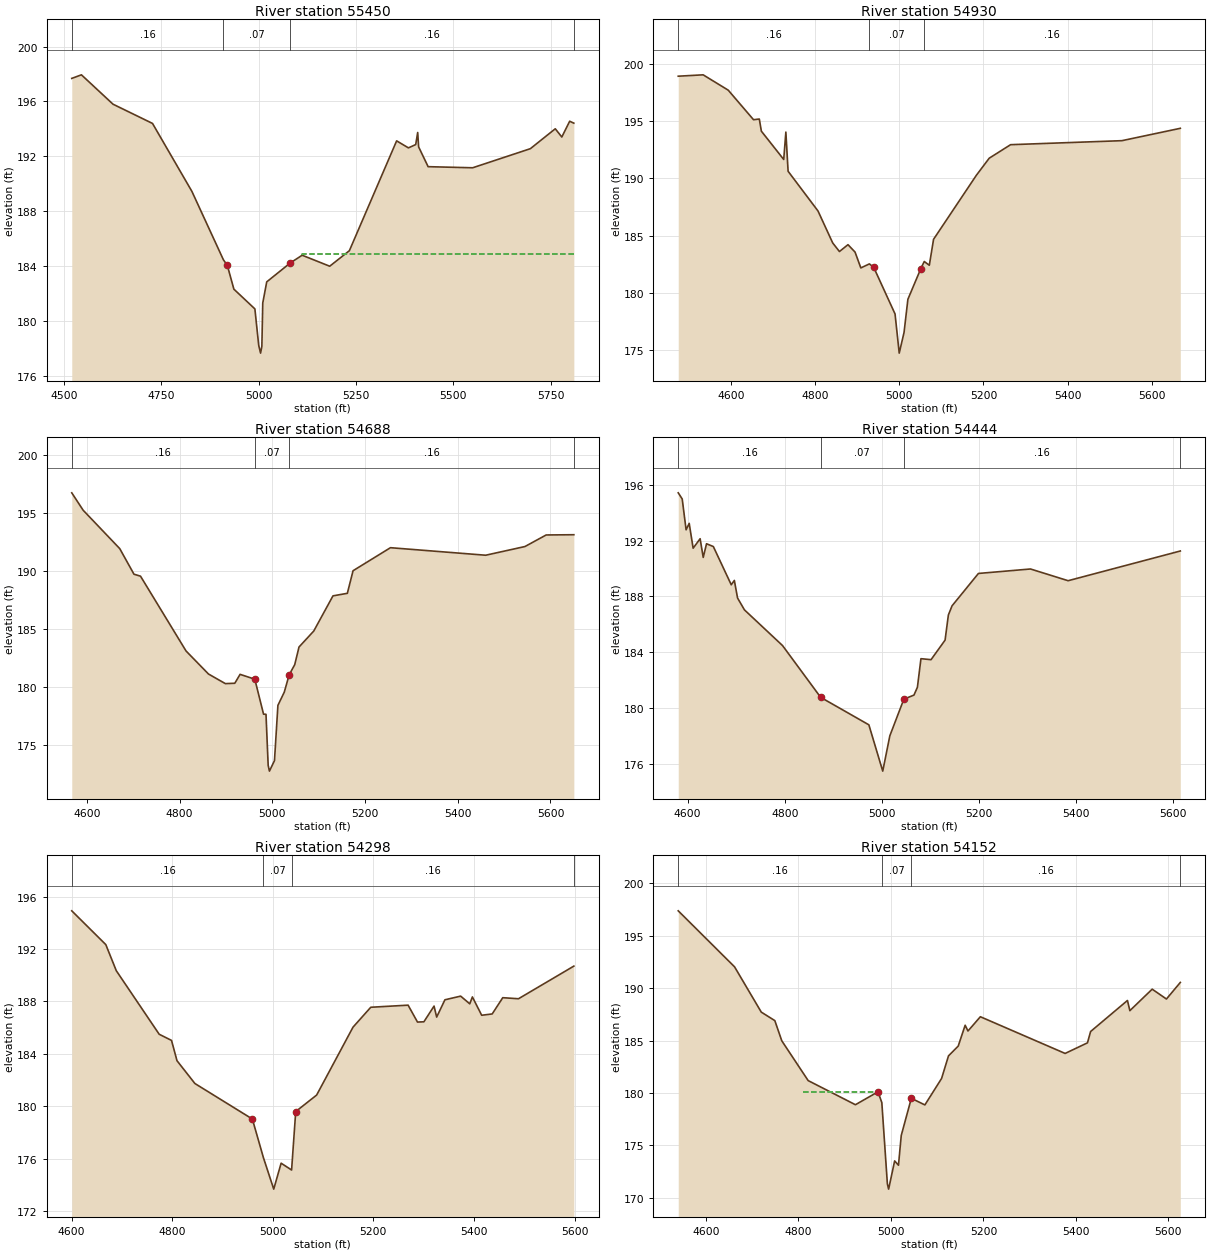
Type RM Length L Ch R = 1 ,55450   ,520,520,520
BEGIN DESCRIPTION:
PENITAS CREEK 96.0
END DESCRIPTION:
XS GIS Cut Line= 4
      2292595.96      13186931.3      2292633.46     13186712.55
      2292733.46     13186050.05      2292789.71     13185656.29
#Sta/Elev= 30
  4519.7  197.68  4544.5  197.94  4625.7   195.8  4727.1   194.4  4828.3  189.45
  4909.2  184.47  4919.3  184.06  4936.1  182.33  4990.1  180.89  4999.9  178.24
  5004.7  177.67    5008  178.17  5010.3  181.32  5020.5  182.86  5081.1  184.24
  5111.5   184.8  5182.3     184  5232.8  185.13  5354.2  193.13  5384.5  192.62
  5403.2  192.86  5408.3  193.74  5410.7  192.69  5435.1  191.25  5549.5  191.17
  5697.7  192.56  5761.7  194.01  5778.5  193.41  5798.7  194.56  5809.4  194.42
#Mann= 4 ,-1 , 0
  4519.7     .16       0  4909.2     .07       0  5081.1     .16       0
  5809.4      .1       0
#XS Ineff= 2 , 0
       0                  5111.3       0  184.87
Permanent Ineff=
       F       T
Bank Sta=4919.3,5081.1
XS Rating Curve= 0 ,0
Exp/Cntr=0.3,0.1

Type RM Length L Ch R = 1 ,54930   ,242,242,242
BEGIN DESCRIPTION:
PENITAS CREEK 95.0
END DESCRIPTION:
XS GIS Cut Line= 3
      2293045.98     13186981.26      2293120.96      13186806.3
      2293301.93     13185820.32
#Sta/Elev= 30
    4475  198.92  4534.2  199.04  4593.8   197.7  4653.9  195.12  4667.6  195.18
  4672.5  194.12  4725.6  191.65  4730.7  194.04    4736  190.62  4807.1  187.15
    4842  184.36    4858  183.61  4878.3  184.21  4895.1  183.56  4908.8  182.18
  4929.1  182.53  4939.3  182.24  4990.1  178.16    5000  174.74  5011.5  176.55
  5020.6  179.44  5051.1   182.1  5059.5  182.74  5071.5  182.41  5081.6  184.68
  5183.3  190.27  5213.8  191.76  5264.6  192.94    5529  193.29  5667.8  194.37
#Mann= 3 ,-1 , 0
    4475     .16       0  4929.1     .07       0  5059.5     .16       0
Bank Sta=4939.3,5051.1
XS Rating Curve= 0 ,0
Exp/Cntr=0.3,0.1

Type RM Length L Ch R = 1 ,54688   ,244,244,244
BEGIN DESCRIPTION:
PENITAS CREEK 94.0
END DESCRIPTION:
XS GIS Cut Line= 3
       2293239.7     13186912.57      2293333.46     13186762.55
       2293633.1     13185907.33
#Sta/Elev= 30
  4567.3  196.75  4591.8  195.25  4670.8  191.93  4701.5  189.72  4715.6  189.55
  4813.8  183.09  4862.2   181.1  4898.6  180.27    4919   180.3  4930.4  181.07
  4962.2  180.65    4981  177.63  4986.3  177.62    4991  173.21  4993.7  172.71
  5004.6  173.62    5012  178.39  5025.7  179.53  5036.3  181.03  5048.3  181.91
  5057.5  183.43  5089.3  184.81  5130.8  187.85  5161.8  188.07  5174.1  190.02
  5254.8  192.01  5460.2  191.36  5544.9  192.11  5590.7  193.11  5650.4  193.13
#Mann= 4 ,-1 , 0
  4567.3     .16       0  4962.2     .07       0  5036.3     .16       0
  5650.4      .1       0
Bank Sta=4962.2,5036.3
XS Rating Curve= 0 ,0
Exp/Cntr=0.3,0.1

Type RM Length L Ch R = 1 ,54444   ,146,146,146
BEGIN DESCRIPTION:
Mapping XS ad812bd2
END DESCRIPTION:
XS GIS Cut Line= 3
      2293370.99     13186962.52      2293758.46     13186475.05
        2293883.     13186082.75
#Sta/Elev= 30
  4580.7  195.42  4588.9  194.98  4596.9  192.77  4603.3  193.23  4611.4  191.45
  4625.8  192.13  4632.2  190.79    4639  191.77    4653  191.57  4689.9  188.83
  4696.3  189.14  4702.9  187.88  4717.1  187.03  4795.6  184.47  4874.1  180.76
  4973.4  178.79    5002  175.47  5016.6     178  5045.5  180.63  5066.3  180.92
  5073.4  181.48  5080.7  183.53  5101.5  183.46  5130.4  184.86  5137.2  186.66
  5144.8  187.32  5199.1  189.64  5306.4  189.96  5383.9  189.12    5615  191.25
#Mann= 4 ,-1 , 0
  4580.7     .16       0  4874.1     .07       0  5045.5     .16       0
    5615      .1       0
Bank Sta=4874.1,5045.5
XS Rating Curve= 0 ,0
Exp/Cntr=0.3,0.1

Type RM Length L Ch R = 1 ,54298   ,146,146,146
BEGIN DESCRIPTION:
Mapping XS 155d4f6a
END DESCRIPTION:
XS GIS Cut Line= 4
      2293508.43     13187031.34      2293627.21     13186875.05
      2293895.96      13186531.3      2294002.12      13186181.6
#Sta/Elev= 30
  4600.5  194.91  4668.2  192.33    4689  190.34  4774.3  185.49  4798.8  185.02
  4809.7  183.47  4845.3  181.73  4959.5  179.02  4981.5  176.07    5002  173.67
  5016.7  175.65  5037.5  175.13  5045.7  179.59  5087.3  180.85  5159.6  186.03
  5194.9  187.55  5269.1  187.71  5287.8  186.42  5300.5  186.44  5320.7  187.64
  5325.9   186.8  5342.3  188.12  5373.6   188.4  5391.7  187.81  5396.9  188.34
  5415.4  186.94  5436.3  187.04  5457.3  188.28  5488.6   188.2  5598.6  190.69
#Mann= 4 ,-1 , 0
  4600.5     .16       0  4981.5     .07       0  5037.5     .16       0
  5598.6      .1       0
Bank Sta=4959.5,5045.7
XS Rating Curve= 0 ,0
Exp/Cntr=0.3,0.1

Type RM Length L Ch R = 1 ,54152   ,408,408,408
BEGIN DESCRIPTION:
PENITAS CREEK 93.0
END DESCRIPTION:
XS GIS Cut Line= 3
      2293627.23     13187156.27      2293977.21      13186631.3
      2294077.21     13186187.56
#Sta/Elev= 30
  4540.1  197.37  4661.9  192.03  4719.7  187.71    4749   186.9    4764  184.98
  4821.1  181.18  4923.3  178.88  4972.1  180.11  4980.4  179.08  4992.4  171.33
  4995.1  170.83  5008.1  173.52  5016.4  173.11  5022.4  175.95  5044.2  179.49
  5073.5  178.86  5109.6  181.38  5124.6  183.54  5145.6  184.47  5160.6  186.46
  5166.7  185.91  5193.5  187.27  5376.8  183.77  5425.1  184.78  5431.9  185.86
  5511.6  188.82  5516.8  187.85  5565.1   189.9  5595.9  188.96  5625.9  190.54
#Mann= 4 ,-1 , 0
  4540.1     .16       0  4980.4     .07       0  5044.2     .16       0
  5625.9     .08       0
#XS Ineff= 1 ,-1
    4810 4968.75  180.11
Permanent Ineff=
       T
Bank Sta=4972.1,5044.2
XS Rating Curve= 0 ,0
Exp/Cntr=0.3,0.1

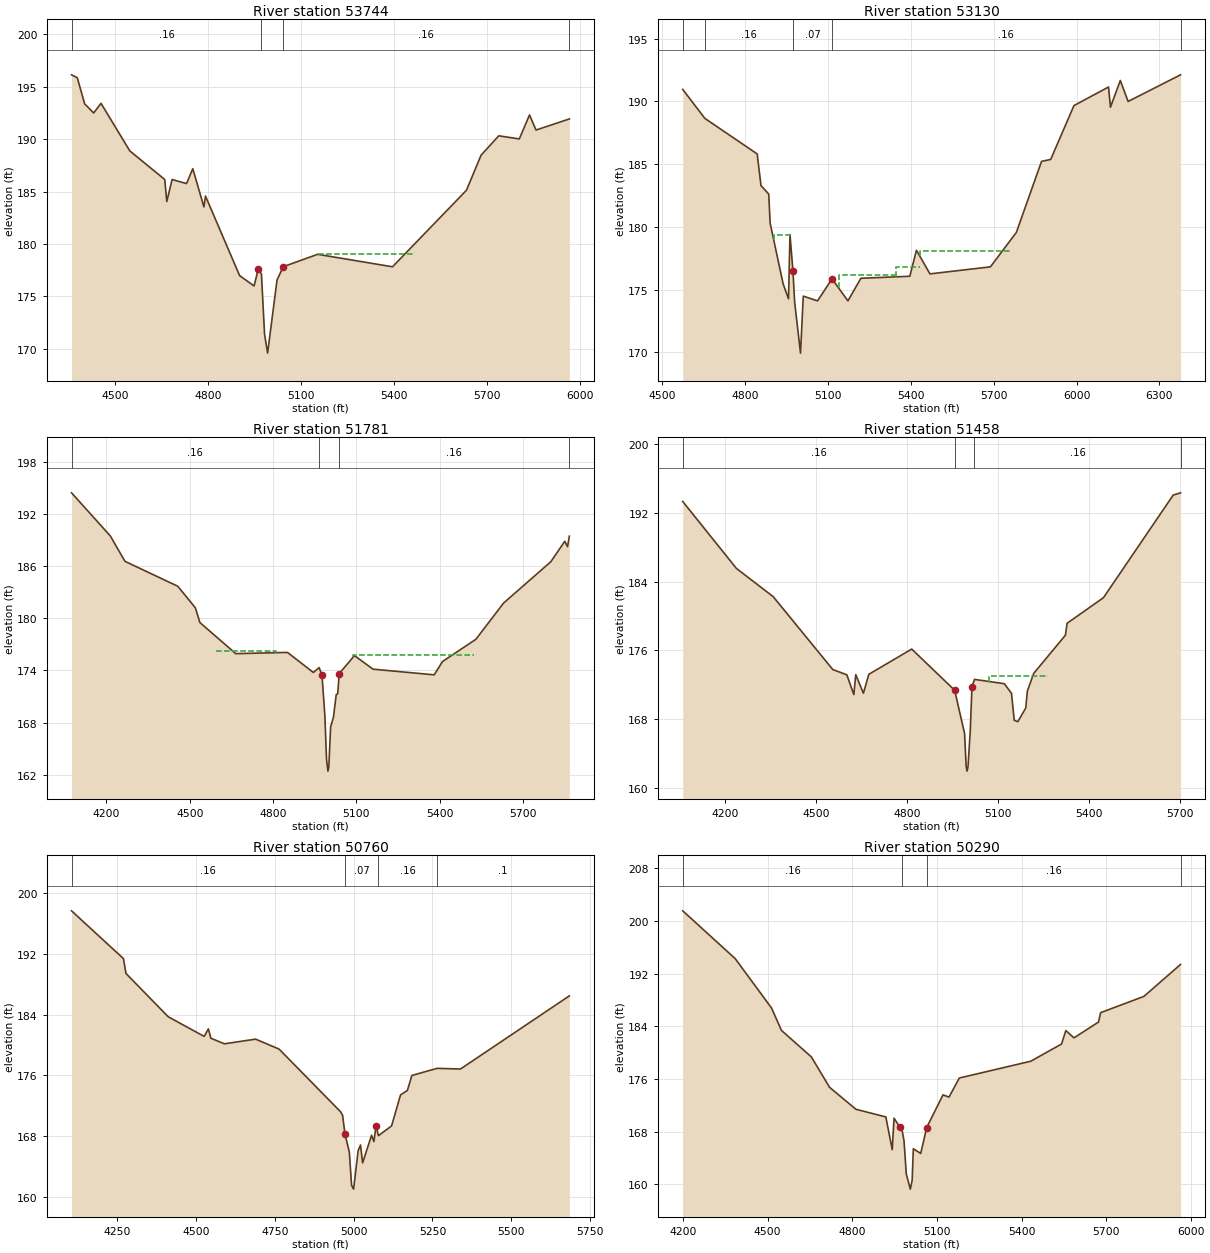
Type RM Length L Ch R = 1 ,53744   ,614,614,614
BEGIN DESCRIPTION:
PENITAS CREEK 92.0
END DESCRIPTION:
XS GIS Cut Line= 4
      2294095.95     13187500.08      2294233.46     13187175.05
      2294339.71      13186318.8      2294227.22     13185943.85
#Sta/Elev= 30
  4358.9  196.14  4377.5  195.86  4401.2  193.37  4430.3   192.5    4454  193.42
    4547  188.88  4659.8  186.15  4666.4  184.05  4683.5  186.15  4730.2  185.76
  4750.3  187.18  4786.3  183.53  4791.3  184.57  4901.5  176.98  4948.1  175.99
  4961.9  177.61    4972  177.12  4982.1  171.37  4991.9  169.58  5022.4  176.57
  5042.5  177.83  5153.4  179.01  5395.2  177.82  5633.9  185.12  5681.1  188.47
  5738.3  190.32  5804.5  190.02  5837.5  192.31  5858.6  190.87  5966.1  191.93
#Mann= 4 ,-1 , 0
  4358.9     .16       0    4972     .07       0  5042.5     .16       0
  5966.1      .1       0
#XS Ineff= 1 ,-1
 5154.64 5468.04  179.04
Permanent Ineff=
       T
Bank Sta=4961.9,5042.5
XS Rating Curve= 0 ,0
Exp/Cntr=0.3,0.1

Type RM Length L Ch R = 1 ,53130   ,1349,1349,1349
BEGIN DESCRIPTION:
PENITAS CREEK 91.0
END DESCRIPTION:
XS GIS Cut Line= 4
      2294914.71     13187493.84      2294902.21      13187281.3
      2294552.21     13186100.05      2294289.73     13185856.33
#Sta/Elev= 30
  4573.5  190.95  4653.2  188.65  4843.2  185.81  4856.9  183.29  4884.9  182.62
  4890.2  180.29  4937.1  175.47  4956.7  174.27  4961.9  179.39 4972.73  176.49
  4978.8  174.02  5000.1  169.95  5010.1  174.49  5061.6  174.11  5114.4  175.86
  5171.8  174.11  5218.7  175.91    5396  176.07  5420.1  178.14    5469  176.26
    5688  176.82  5781.9  179.56  5873.2  185.22  5906.4  185.37  5990.5  189.66
  6115.9  191.14  6122.8  189.53  6158.4  191.66  6186.8  189.99  6376.6  192.11
#Mann= 5 ,-1 , 0
  4573.5     .05       0  4653.2     .16       0 4972.73     .07       0
  5114.4     .16       0  6376.6      .1       0
#XS Ineff= 4 ,-1
 4903.27  4961.8  179.38 5139.29 5344.64  176.15 5344.64 5432.14   176.8
 5432.14 5764.29   178.1
Permanent Ineff=
       T       T       T       T
Bank Sta=4972.73,5114.4
XS Rating Curve= 0 ,0
Exp/Cntr=0.3,0.1

Type RM Length L Ch R = 1 ,51781   ,323,323,323
BEGIN DESCRIPTION:
PENITAS CREEK 90.0
END DESCRIPTION:
XS GIS Cut Line= 4
       2295064.7     13187568.82      2295214.71      13187131.3
      2295358.46      13186593.8      2295377.17     13185820.33
#Sta/Elev= 30
  4074.3  194.45  4213.8  189.49  4266.7  186.56  4456.9  183.69  4520.4   181.2
  4536.5  179.51  4665.6  175.93    4852  176.07  4945.1  173.76  4965.8  174.32
  4976.2  173.46  4986.5  168.81  4992.6  163.71  4997.6   162.4  5000.8   162.9
  5007.2  167.48  5017.6  168.64  5027.5  171.23  5032.7  171.29  5038.3  173.64
  5093.2   175.7  5160.2  174.14  5380.2  173.49  5410.2  175.02  5530.3  177.58
  5630.3  181.76  5800.4  186.52  5850.4  188.87  5860.4  188.25  5866.9  189.46
#Mann= 4 ,-1 , 0
  4074.3     .16       0  4965.8     .07       0  5038.3     .16       0
  5866.9     .08       0
#XS Ineff= 2 ,-1
 4594.64 4810.71  176.23 5089.29 5523.21  175.73
Permanent Ineff=
       T       T
Bank Sta=4976.2,5038.3
XS Rating Curve= 0 ,0
Exp/Cntr=0.3,0.1

Type RM Length L Ch R = 1 ,51458   ,698,698,698
BEGIN DESCRIPTION:
PENITAS CREEK 89.0
END DESCRIPTION:
XS GIS Cut Line= 3
      2295302.21     13187587.56      2295545.96      13187043.8
       2295852.2     13186043.83
#Sta/Elev= 30
  4059.7  193.33  4236.7  185.54  4358.1  182.25  4554.5  173.77  4600.9  173.15
    4624  170.85  4630.3  173.17  4655.6  171.01  4673.3  173.21  4814.9  176.15
  4956.4  171.36  4989.2  166.33  4994.5  162.44  4997.3  161.94  5000.5  162.44
    5008  166.66 5013.52  171.74  5021.9  172.62  5120.2  172.12  5143.9     171
    5153  167.85  5164.9   167.7    5191  169.29  5196.2  171.25  5217.2  173.32
  5321.7  177.76  5327.2  179.15  5447.2  182.13  5677.3  194.08  5701.4  194.34
#Mann= 4 ,-1 , 0
  4059.7     .16       0  4956.4     .07       0  5021.9     .16       0
  5701.4      .1       0
#XS Ineff= 2 ,-1
 4388.93 4816.43     176 5070.36 5263.21  173.05
Permanent Ineff=
       T       T
Bank Sta=4956.4,5013.52
XS Rating Curve= 0 ,0
Exp/Cntr=0.3,0.1

Type RM Length L Ch R = 1 ,50760   ,470,470,470
BEGIN DESCRIPTION:
PENITAS CREEK 88.0
END DESCRIPTION:
XS GIS Cut Line= 4
       2295339.7     13187731.31      2295758.46     13187225.05
      2296108.46      13186831.3       2296220.7     13186450.94
#Sta/Elev= 30
  4104.3  197.67  4269.1  191.37    4277  189.42  4411.1  183.71  4525.4  181.12
  4538.7  182.11  4546.6  180.88  4589.6  180.14  4688.6  180.76  4763.4  179.44
  4958.1   171.2  4964.8  170.72  4972.4  168.25  4986.3  165.85  4993.3   161.5
  4999.7  160.99  5014.2  166.06  5021.7  166.81  5028.4  164.45  5056.8  168.09
  5064.3  167.25    5071  169.37  5078.6  168.03  5120.4  169.33  5148.8  173.41
  5170.5  173.99  5184.8  175.97  5264.9  176.91  5339.1  176.82  5684.7  186.46
#Mann= 4 ,-1 , 0
  4104.3     .16       0  4972.4     .07       0  5078.6     .16       0
  5264.9      .1       0
Bank Sta=4972.4,5071
XS Rating Curve= 0 ,0
Exp/Cntr=0.3,0.1

Type RM Length L Ch R = 1 ,50290   ,566,566,566
BEGIN DESCRIPTION:
PENITAS CREEK 87.0
END DESCRIPTION:
XS GIS Cut Line= 3
       2295437.7     13187946.87      2296087.72     13187446.85
      2296887.73     13186946.85
#Sta/Elev= 30
  4199.5  201.53  4385.3  194.27    4514  186.77  4549.3  183.36  4655.3  179.33
  4719.6  174.72    4813  171.38    4919  170.22  4941.7  165.24    4948  170.03
  4969.1  168.64    4977  168.09  4983.3  166.64  4991.5  161.54  5005.8  159.25
  5012.3   160.6  5016.4  165.39  5042.6  164.67  5063.8  168.61  5121.6  173.57
  5142.8  173.23  5179.4  176.13  5432.3  178.68  5541.4  181.29  5556.7  183.34
  5585.6  182.23  5672.3  184.63    5680  186.06  5833.3  188.53    5963  193.38
#Mann= 4 ,-1 , 0
  4199.5     .16       0    4977     .07       0  5063.8     .16       0
    5963      .1       0
#XS Ineff= 1 ,-1
    4900 4948.21     170
Permanent Ineff=
       T
Bank Sta=4969.1,5063.8
XS Rating Curve= 0 ,0
Exp/Cntr=0.3,0.1

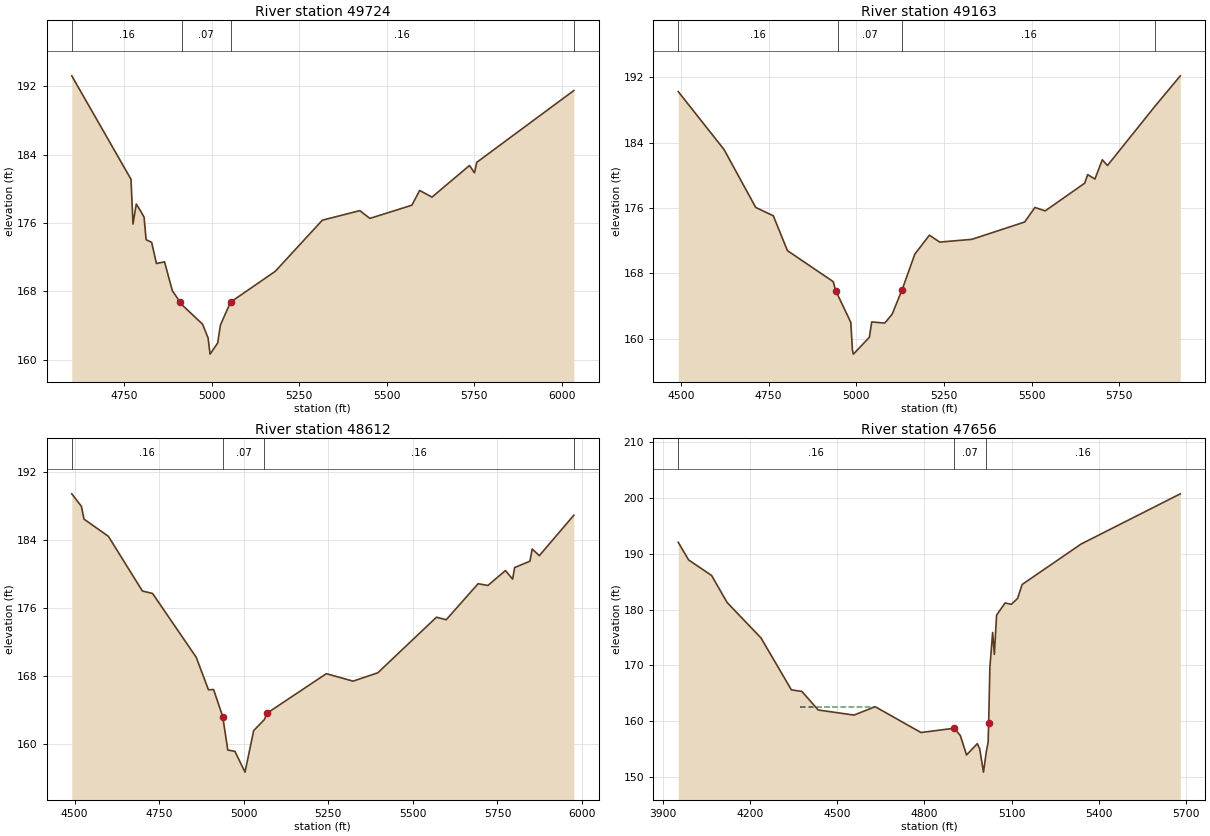
Type RM Length L Ch R = 1 ,49724   ,561,561,561
BEGIN DESCRIPTION:
PENITAS CREEK 86.0
END DESCRIPTION:
XS GIS Cut Line= 3
      2295937.76     13188146.83      2296287.72     13187946.85
      2297087.69     13187296.88
#Sta/Elev= 30
  4600.5  193.21  4769.6  181.11  4775.4  175.87  4784.7  178.21    4797   177.4
    4807  176.68  4812.8  174.04  4828.6  173.73  4842.3  171.25  4865.4  171.45
  4887.7  168.07  4909.3  166.77    4915  166.43  4974.1  164.15  4989.9  162.53
  4995.4  160.65  5017.2  161.95  5025.1  164.06  5053.9  166.73  5181.7  170.34
    5316  176.32  5423.1  177.44  5451.8  176.53  5571.7  178.07    5594   179.8
  5629.2  179.02  5736.3  182.72  5750.6  181.86  5757.1  183.09  6034.3  191.49
#Mann= 4 ,-1 , 0
  4600.5     .16       0    4915     .07       0  5053.9     .16       0
  6034.3      .1       0
Bank Sta=4909.3,5053.9
XS Rating Curve= 0 ,0
Exp/Cntr=0.3,0.1

Type RM Length L Ch R = 1 ,49163   ,551,551,551
BEGIN DESCRIPTION:
PENITAS CREEK 85.0
END DESCRIPTION:
XS GIS Cut Line= 3
      2296087.72     13188396.86      2296587.72     13188346.85
      2297337.68     13187796.88
#Sta/Elev= 30
    4492  190.23  4622.7  183.14  4713.1  176.05  4763.3  175.03  4803.5  170.77
  4934.2  166.97  4941.7  165.78  4946.8  165.37  4984.4  161.98    4989   158.6
  4991.7   158.1  5037.3  160.16  5044.1  162.04  5081.3   161.9  5102.2  162.98
  5130.9     166    5167  170.34  5208.7  172.66    5238  171.81  5329.9  172.15
  5480.4  174.27  5509.7  176.05    5539  175.63  5651.7  179.02  5660.2  180.07
    5681  179.53  5701.9  181.89  5716.6  181.18  5852.4  188.45  5924.5  192.16
#Mann= 4 ,-1 , 0
    4492     .16       0  4946.8     .07       0  5130.9     .16       0
  5852.4      .1       0
Bank Sta=4941.7,5130.9
XS Rating Curve= 0 ,0
Exp/Cntr=0.3,0.1

Type RM Length L Ch R = 1 ,48612   ,956,956,956
BEGIN DESCRIPTION:
PENITAS CREEK 84.0
END DESCRIPTION:
XS GIS Cut Line= 3
      2296387.71     13189096.86      2296837.72     13188796.85
       2297337.7     13187996.89
#Sta/Elev= 30
  4491.5  189.48  4520.1     188  4527.6   186.5  4599.7  184.47  4700.3  178.02
  4730.4  177.73  4859.6  170.19  4895.6  166.37  4910.7   166.4  4937.7  163.22
  4952.7  159.27  4973.8  159.11  5003.6  156.66  5029.3  161.56  5061.2  162.87
  5067.7  163.58    5244  168.27    5323  167.39  5396.1  168.37  5569.5  174.93
  5598.4  174.63  5692.7  178.88  5721.6  178.67  5773.5  180.43  5794.7  179.42
  5800.6  180.78    5846  181.54  5852.5  182.97  5873.7  182.19  5975.7  186.96
#Mann= 4 ,-1 , 0
  4491.5     .16       0  4937.7     .07       0  5061.2     .16       0
  5975.7     .16       0
Bank Sta=4937.7,5067.7
XS Rating Curve= 0 ,0
Exp/Cntr=0.3,0.1

Type RM Length L Ch R = 1 ,47656   ,212,212,212
BEGIN DESCRIPTION:
PENITAS CREEK 83.0
END DESCRIPTION:
XS GIS Cut Line= 3
      2296569.46     13189544.05      2297444.48     13189231.54
      2298131.98     13188825.29
#Sta/Elev= 30
  3953.1  192.02  3988.9  188.87  4068.1  186.08  4121.1  181.27    4238  174.92
  4342.5  165.64  4378.6  165.36  4434.9  162.04    4558  161.13  4630.8  162.63
  4788.5  158.01  4902.4  158.77  4923.8  157.48  4945.2     154  4982.3  156.02
  4990.5  155.09  5003.5  150.93  5013.6  154.72  5019.4  156.23 5021.35  159.71
  5025.4  169.57    5035   175.9  5040.9  171.99  5048.6  179.01  5077.9  181.18
  5099.4  180.93  5120.8  181.99  5136.5  184.48  5339.3  191.71  5680.8  200.69
#Mann= 3 ,-1 , 0
  3953.1     .16       0  4902.4     .07       0  5013.6     .16       0
#XS Ineff= 1 ,-1
 4373.21 4632.14  162.64
Permanent Ineff=
       T
Bank Sta=4902.4,5021.35
XS Rating Curve= 0 ,0
Exp/Cntr=0.3,0.1