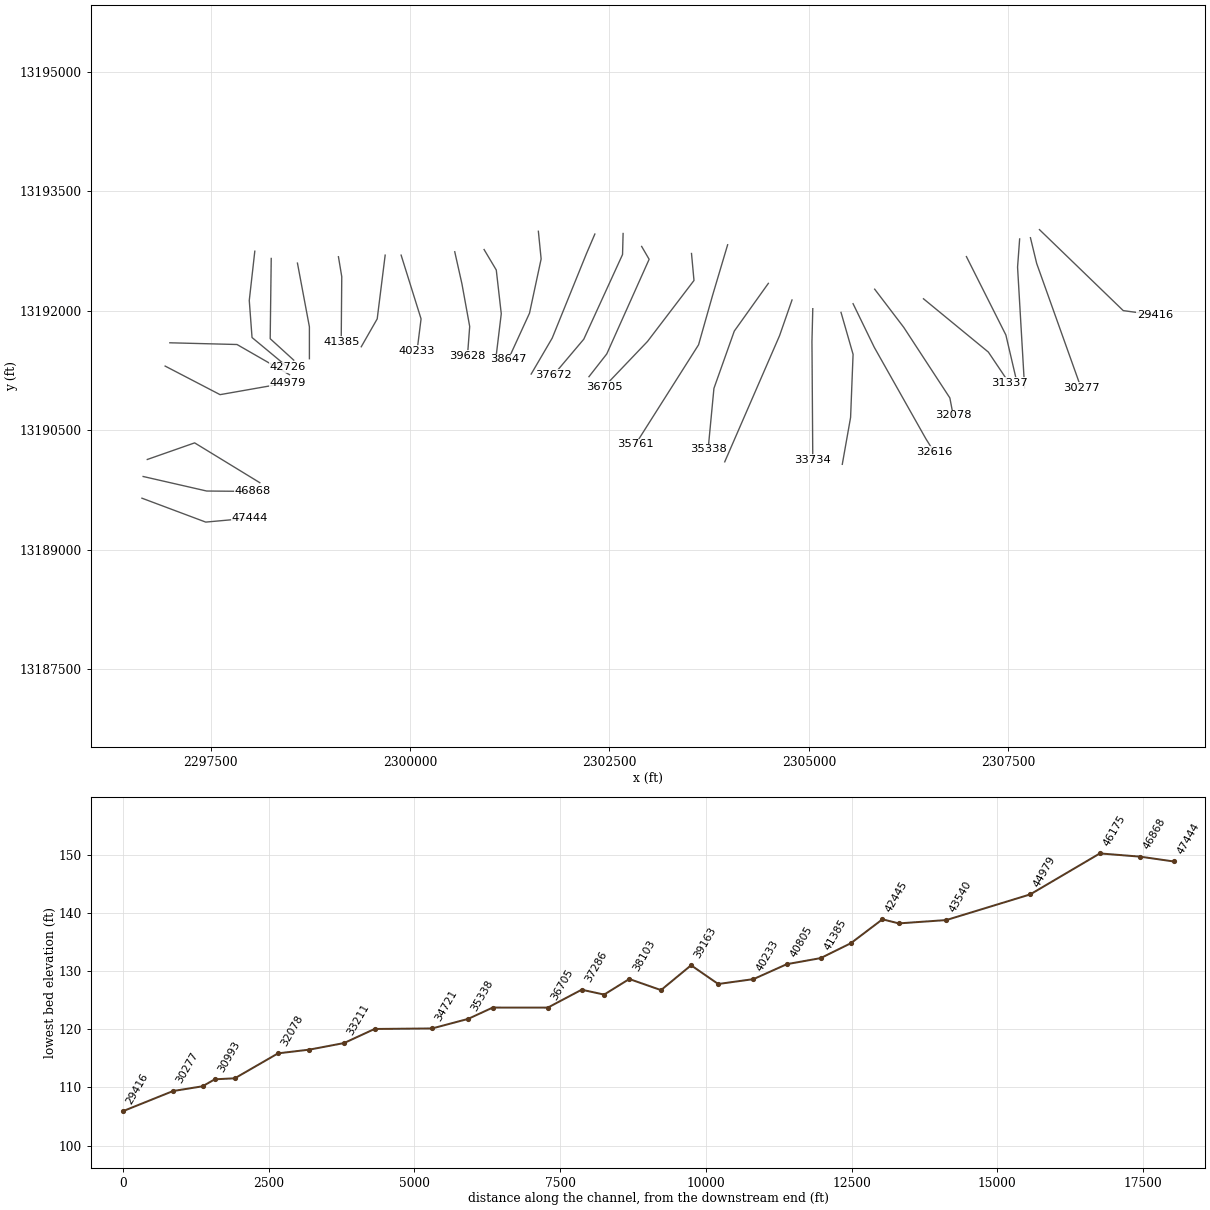
HEC-RAS study PENITAS CREEK.prj: PENITAS CREEK Base Level Engineering

--- PENITAS CREEK.g01 (geometry) --- (continued)

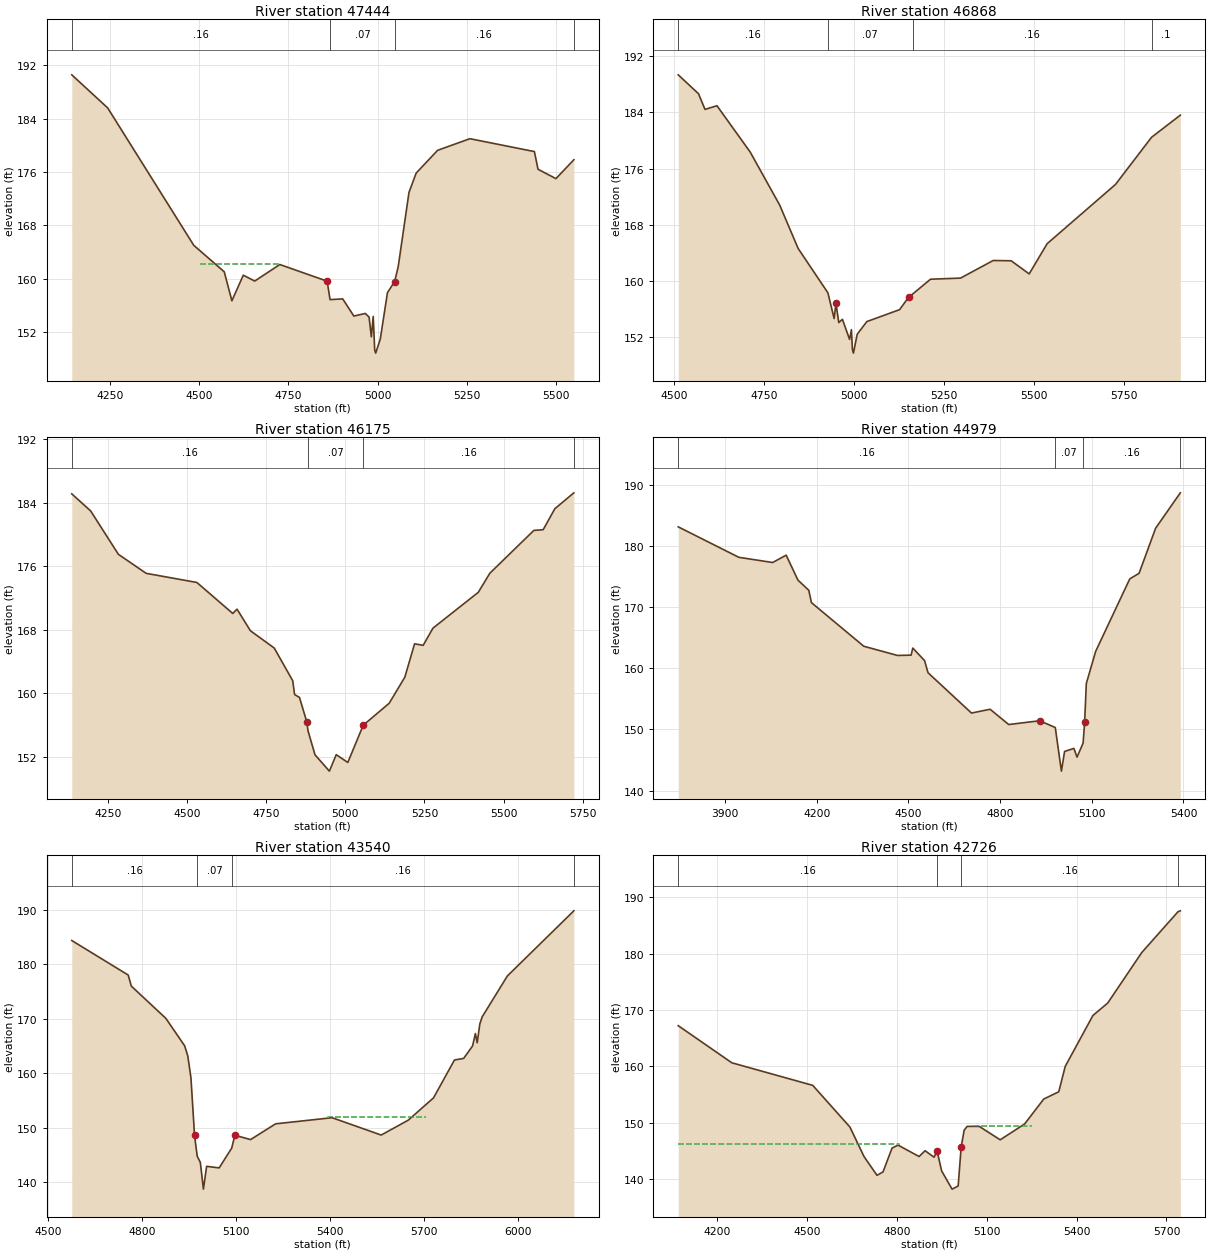
Type RM Length L Ch R = 1 ,47444   ,576,576,576
BEGIN DESCRIPTION:
PENITAS CREEK 82.0
END DESCRIPTION:
XS GIS Cut Line= 3
      2296637.72     13189646.85      2297437.72     13189346.85
      2297987.75     13189396.86
#Sta/Elev= 30
    4143  190.58  4243.6  185.62  4484.8  165.01  4570.2  161.04  4591.6  156.69
  4623.6  160.53  4655.6  159.65  4725.9  162.13  4858.6  159.63  4866.6  156.87
  4902.2  156.97  4933.3   154.4  4965.4  154.79    4976  154.25  4982.3  151.29
  4987.6  154.35  4991.7  149.34  4994.5  148.84  5007.4  150.94  5027.5  157.91
  5047.6  159.57  5057.6   161.8  5087.8  172.94  5107.9  175.84  5168.1  179.26
  5258.5     181  5439.2  179.07  5449.3  176.42  5499.5  175.01  5549.7  177.84
#Mann= 4 ,-1 , 0
    4143     .16       0  4866.6     .07       0  5047.6     .16       0
  5549.7      .1       0
#XS Ineff= 1 ,-1
 4501.43 4722.86  162.15
Permanent Ineff=
       T
Bank Sta=4858.6,5047.6
XS Rating Curve= 0 ,0
Exp/Cntr=0.3,0.1

Type RM Length L Ch R = 1 ,46868   ,693,693,693
BEGIN DESCRIPTION:
PENITAS CREEK 81.0
END DESCRIPTION:
XS GIS Cut Line= 3
      2296652.78     13189919.05      2297449.69     13189736.75
      2298027.77     13189731.54
#Sta/Elev= 30
  4512.2  189.36  4568.6  186.66  4586.6  184.43  4619.9  184.95  4712.2  178.35
  4794.2  170.79  4845.5   164.6 4928.23  158.27  4945.5  154.61  4950.7  156.78
  4958.4  154.03  4968.6  154.49  4988.5  151.62  4993.6  153.02  4996.4  150.17
  4999.2  149.67  5009.7  152.36  5036.5  154.17  5127.5  155.87  5153.3  157.69
  5163.5  158.08  5213.4  160.21  5296.9  160.37  5387.7  162.88  5437.7  162.84
  5487.7  160.97  5537.7  165.28  5727.7  173.73  5827.8  180.45  5907.8  183.61
#Mann= 4 ,-1 , 0
  4512.2     .16       0 4928.23     .07       0  5163.5     .16       0
  5827.8      .1       0
#XS Ineff= 1 ,-1
 5414.29 5564.29   162.8
Permanent Ineff=
       T
Bank Sta=4950.7,5153.3
XS Rating Curve= 0 ,0
Exp/Cntr=0.3,0.1

Type RM Length L Ch R = 1 ,46175   ,1196,1196,1196
BEGIN DESCRIPTION:
PENITAS CREEK 80.0
END DESCRIPTION:
XS GIS Cut Line= 3
      2296704.91     13190132.59      2297298.65     13190340.92
       2298115.6     13189841.38
#Sta/Elev= 30
  4135.5  185.12  4195.2  182.97  4282.9  177.51  4370.6  175.12  4530.9  173.97
  4644.3  170.07  4657.8  170.61  4700.2  167.89  4775.4  165.72  4833.9   161.6
  4839.7  159.87  4855.2   159.5 4878.44  156.41  4882.3  155.28  4904.3  152.28
  4949.7  150.23  4971.3   152.3    5008  151.32  5056.7  156.01  5138.7  158.77
  5188.1  162.05    5219  166.25  5246.1  166.06    5277  168.22  5420.3  172.73
    5457  175.14  5595.9  180.52  5625.4  180.61  5662.1  183.24  5722.3  185.25
#Mann= 4 ,-1 , 0
  4135.5     .16       0  4882.3     .07       0  5056.7     .16       0
  5722.3      .1       0
Bank Sta=4878.44,5056.7
XS Rating Curve= 0 ,0
Exp/Cntr=0.3,0.1

Type RM Length L Ch R = 1 ,44979   ,1439,1439,1439
BEGIN DESCRIPTION:
PENITAS CREEK 79.0
END DESCRIPTION:
XS GIS Cut Line= 3
      2296928.83     13191304.47      2297617.51     13190946.06
      2298470.55     13191096.13
#Sta/Elev= 30
  3747.2  183.18  3945.5  178.19    4056  177.34  4100.3  178.54  4138.8  174.46
  4174.3  172.79    4183  170.77  4354.2  163.63  4464.7  162.12    4509  162.17
  4514.6  163.33  4553.1  161.28  4564.4  159.29  4706.5  152.69  4767.5  153.31
  4828.4  150.81  4929.9  151.43  4980.7  150.32  5000.7  143.18  5011.1   146.4
  5041.6   146.9  5051.8  145.47  5071.7  147.77  5076.8  151.27  5082.2  157.52
  5112.7  162.78  5224.4  174.66  5254.8  175.57    5309  182.96  5389.7  188.75
#Mann= 4 ,-1 , 0
  3747.2     .16       0  4980.7     .07       0  5071.7     .16       0
  5389.7      .1       0
Bank Sta=4929.9,5076.8
XS Rating Curve= 0 ,0
Exp/Cntr=0.3,0.1

Type RM Length L Ch R = 1 ,43540   ,814,814,814
BEGIN DESCRIPTION:
PENITAS CREEK 78.0
END DESCRIPTION:
XS GIS Cut Line= 3
      2296987.74     13191596.85       2297829.9     13191575.29
      2298487.68     13191196.88
#Sta/Elev= 30
  4575.7  184.34  4755.7  178.01  4765.7  175.98  4875.8  170.07  4935.8  165.03
  4945.8  163.17  4955.8  159.17 4967.29  148.62  4975.8   144.8  4985.8  143.66
  4995.6  138.77  5005.8  142.95  5045.8  142.66  5085.8  146.29  5095.9  148.65
  5145.9  147.85  5225.9  150.74    5406  151.86  5562.6  148.68  5648.9  151.41
  5729.4  155.49  5796.3  162.44  5825.6  162.73    5854  165.01    5863  167.29
  5868.8   165.6  5877.1  169.04  5884.6  170.34    5965  177.84    6177  189.78
#Mann= 4 ,-1 , 0
  4575.7     .16       0  4975.8     .07       0  5085.8     .16       0
    6177      .1       0
#XS Ineff= 1 ,-1
 5391.61 5706.61  151.99
Permanent Ineff=
       T
Bank Sta=4967.29,5095.9
XS Rating Curve= 0 ,0
Exp/Cntr=0.3,0.1

Type RM Length L Ch R = 1 ,42726   ,281,281,281
BEGIN DESCRIPTION:
PENITAS CREEK 77.0
END DESCRIPTION:
XS GIS Cut Line= 4
      2298053.05     13192746.16       2297983.6     13192128.06
      2298018.33     13191662.79      2298469.72     13191287.78
#Sta/Elev= 30
  4070.9  167.23  4249.7  160.64  4519.8  156.63  4643.8  149.23    4691  143.97
  4734.2  140.65  4754.3  141.26  4784.3  145.48  4804.4  146.02  4874.6  143.99
  4894.7  145.02  4924.7  143.87  4934.8  144.97  4949.8  141.44  4984.7   138.2
    5005  138.75    5015  145.65    5025  148.66    5035  149.34  5075.2  149.35
  5145.3  146.96  5226.8  149.77  5290.6   154.2  5340.7  155.49  5362.3     160
  5454.7  169.04  5504.2  171.26  5617.5  180.21  5738.6  187.47  5746.3  187.63
#Mann= 4 ,-1 , 0
  4070.9     .16       0  4934.8     .07       0    5015     .16       0
  5738.6      .1       0
#XS Ineff= 2 ,-1
  4070.9 4805.91  146.22 5055.89 5250.36  149.46
Permanent Ineff=
       T       T
Bank Sta=4934.8,5015
XS Rating Curve= 0 ,0
Exp/Cntr=0.3,0.1

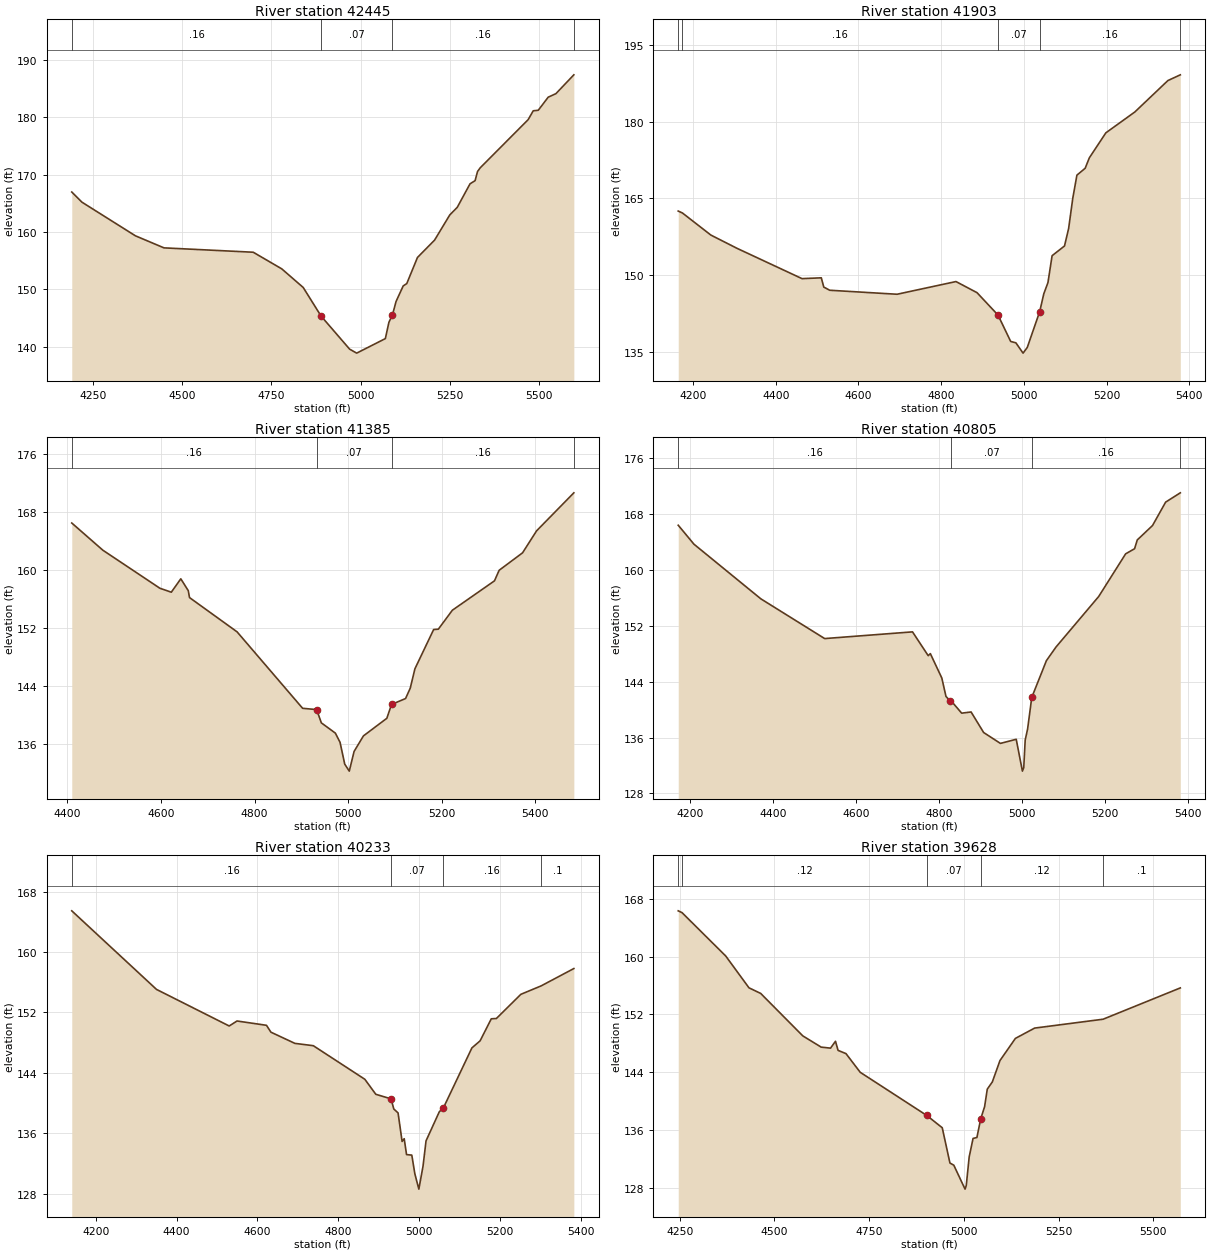
Type RM Length L Ch R = 1 ,42445   ,542,542,542
BEGIN DESCRIPTION:
PENITAS CREEK 76.0
END DESCRIPTION:
XS GIS Cut Line= 3
      2298258.98     13192655.14      2298245.96     13191648.21
      2298541.08     13191379.12
#Sta/Elev= 30
    4191  166.97  4219.3  165.21  4369.3  159.34  4449.3  157.24  4699.3  156.48
  4779.3  153.58  4839.3  150.34  4889.3  145.36  4969.4  139.59  4989.1   138.9
  5069.4  141.43  5079.4  144.28  5089.4  145.57  5099.4   147.9  5119.4  150.61
  5129.4  151.02  5159.4  155.57  5207.3  158.59  5249.9  162.98  5270.8   164.3
  5306.6   168.4  5320.8  168.95  5327.6  170.54    5335  171.18  5469.4  179.58
  5483.6  181.12  5497.8  181.22  5525.5  183.49  5547.2  184.11  5597.4  187.39
#Mann= 4 ,-1 , 0
    4191     .16       0  4889.3     .07       0  5089.4     .16       0
  5597.4      .1       0
Bank Sta=4889.3,5089.4
XS Rating Curve= 0 ,0
Exp/Cntr=0.3,0.1

Type RM Length L Ch R = 1 ,41903   ,518,518,518
BEGIN DESCRIPTION:
PENITAS CREEK 75.0
END DESCRIPTION:
XS GIS Cut Line= 3
      2298587.72     13192596.86      2298737.72     13191796.85
      2298737.72      13191396.9
#Sta/Elev= 30
  4164.2  162.54  4174.4  162.16  4243.1  157.85  4306.6  155.25  4463.5  149.34
  4510.1   149.5  4516.1  147.69  4530.5  147.07  4693.3  146.29  4835.7  148.77
  4886.6   146.6  4937.4  142.22    4968  137.07  4980.6   136.8  4997.9  134.79
  5008.1   135.9  5038.1  142.89  5048.1  146.39  5058.1  148.57  5068.1  153.82
  5098.1  155.72  5108.1  159.14  5118.1  165.03  5128.1  169.55  5148.1   170.9
  5158.1  172.93  5198.1  177.82  5268.1  181.89  5348.1  188.03  5378.1  189.15
#Mann= 5 ,-1 , 0
  4164.2      .1       0  4174.4     .16       0  4937.4     .07       0
  5038.1     .16       0  5378.1      .1       0
#XS Ineff= 1 ,-1
 4487.08 4827.36  148.51
Permanent Ineff=
       F
Bank Sta=4937.4,5038.1
XS Rating Curve= 0 ,0
Exp/Cntr=0.3,0.1

Type RM Length L Ch R = 1 ,41385   ,580,580,580
BEGIN DESCRIPTION:
PENITAS CREEK 74.0
END DESCRIPTION:
XS GIS Cut Line= 3
      2299101.66     13192676.68      2299143.33     13192426.68
      2299136.38     13191607.26
#Sta/Elev= 30
  4409.5  166.51    4476  162.75  4597.7   157.5  4622.2  156.95  4642.5   158.8
  4658.5  157.16  4661.1  156.21  4762.8  151.47  4902.8  140.91  4932.8  140.73
  4942.8   138.9  4972.8  137.48  4982.8  136.21  4992.8   133.2  5002.5  132.23
  5012.8  134.95  5032.8   137.1  5082.8  139.53  5092.8  141.44  5122.8  142.26
  5132.8  143.69  5142.8  146.37  5182.8  151.79  5192.8  151.84  5222.8  154.46
  5312.8  158.52  5322.8  159.98  5372.8  162.39  5402.8  165.43  5482.4  170.68
#Mann= 4 ,-1 , 0
  4409.5     .16       0  4932.8     .07       0  5092.8     .16       0
  5482.4      .1       0
Bank Sta=4932.8,5092.8
XS Rating Curve= 0 ,0
Exp/Cntr=0.3,0.1

Type RM Length L Ch R = 1 ,40805   ,572,572,572
BEGIN DESCRIPTION:
PENITAS CREEK 73.0
END DESCRIPTION:
XS GIS Cut Line= 3
      2299687.72     13192696.82      2299587.72     13191896.85
      2299387.72     13191546.86
#Sta/Elev= 30
  4172.2   166.4    4210  163.69  4371.2  155.86  4524.9  150.17  4736.5  151.13
  4774.3  147.72  4779.4  148.02  4807.1  144.52  4817.1  141.88  4827.2  141.25
  4830.2   141.2  4854.9  139.49  4877.6  139.66  4907.8  136.72  4948.2  135.16
  4986.3  135.75  5001.2  131.19  5004.4  131.69  5007.9  135.65  5013.7  137.22
  5023.7  141.74    5059  147.01  5082.1  148.96    5185   156.2  5249.8   162.3
  5271.4  163.04  5277.8  164.29  5314.6  166.36  5346.2  169.71  5381.5  171.04
#Mann= 4 ,-1 , 0
  4172.2     .16       0  4830.2     .07       0  5023.7     .16       0
  5381.5     .08       0
Bank Sta=4827.2,5023.7
XS Rating Curve= 0 ,0
Exp/Cntr=0.3,0.1

Type RM Length L Ch R = 1 ,40233   ,605,605,605
BEGIN DESCRIPTION:
PENITAS CREEK 72.0
END DESCRIPTION:
XS GIS Cut Line= 3
      2299887.72     13192696.85      2300137.72     13191896.85
      2300087.72     13191496.82
#Sta/Elev= 30
    4141  165.45  4350.5  155.05  4530.2  150.21  4549.6  150.87  4622.4   150.3
  4633.4  149.39  4692.6  147.91  4738.2   147.6  4865.5  143.16  4892.7  141.17
  4930.4  140.57  4937.2  139.22  4947.7  138.71  4957.7  134.93  4962.9  135.29
  4968.7  133.19  4981.7  133.12  4989.2  130.65  4999.1  128.62  5009.4  131.65
  5016.9  135.01  5049.7  138.86  5059.8  139.37  5130.3  147.31  5150.5  148.24
  5178.2  151.16  5190.8   151.2  5251.3   154.4  5301.6  155.52  5382.3  157.81
#Mann= 4 ,-1 , 0
    4141     .16       0  4930.4     .07       0  5059.8     .16       0
  5301.6      .1       0
Bank Sta=4930.4,5059.8
XS Rating Curve= 0 ,0
Exp/Cntr=0.3,0.1

Type RM Length L Ch R = 1 ,39628   ,465,465,465
BEGIN DESCRIPTION:
PENITAS CREEK 71.0
END DESCRIPTION:
XS GIS Cut Line= 4
        2300560.     13192739.16      2300650.27      13192336.4
      2300747.49     13191801.68      2300719.72     13191433.67
#Sta/Elev= 30
  4246.1  166.37  4256.1  166.12  4371.4  160.11  4432.9  155.69  4463.7  154.92
  4574.9  149.03  4623.4  147.47  4648.1  147.33  4661.2  148.28    4668  147.02
  4688.9  146.57  4726.5  143.98  4902.3  137.99    4943  136.29  4963.3   131.4
  4973.5   131.1  5003.2  127.78  5006.4  128.28  5014.1  132.24  5024.3  134.81
  5034.5  134.94  5044.6  137.54  5054.8  139.21  5061.9  141.65  5075.1  142.63
  5095.4  145.61  5136.1  148.68  5186.9  150.11  5367.6  151.34  5571.4  155.68
#Mann= 5 ,-1 , 0
  4246.1     .08       0  4256.1     .12       0  4902.3     .07       0
  5044.6     .12       0  5367.6      .1       0
Bank Sta=4902.3,5044.6
XS Rating Curve= 0 ,0
Exp/Cntr=0.3,0.1

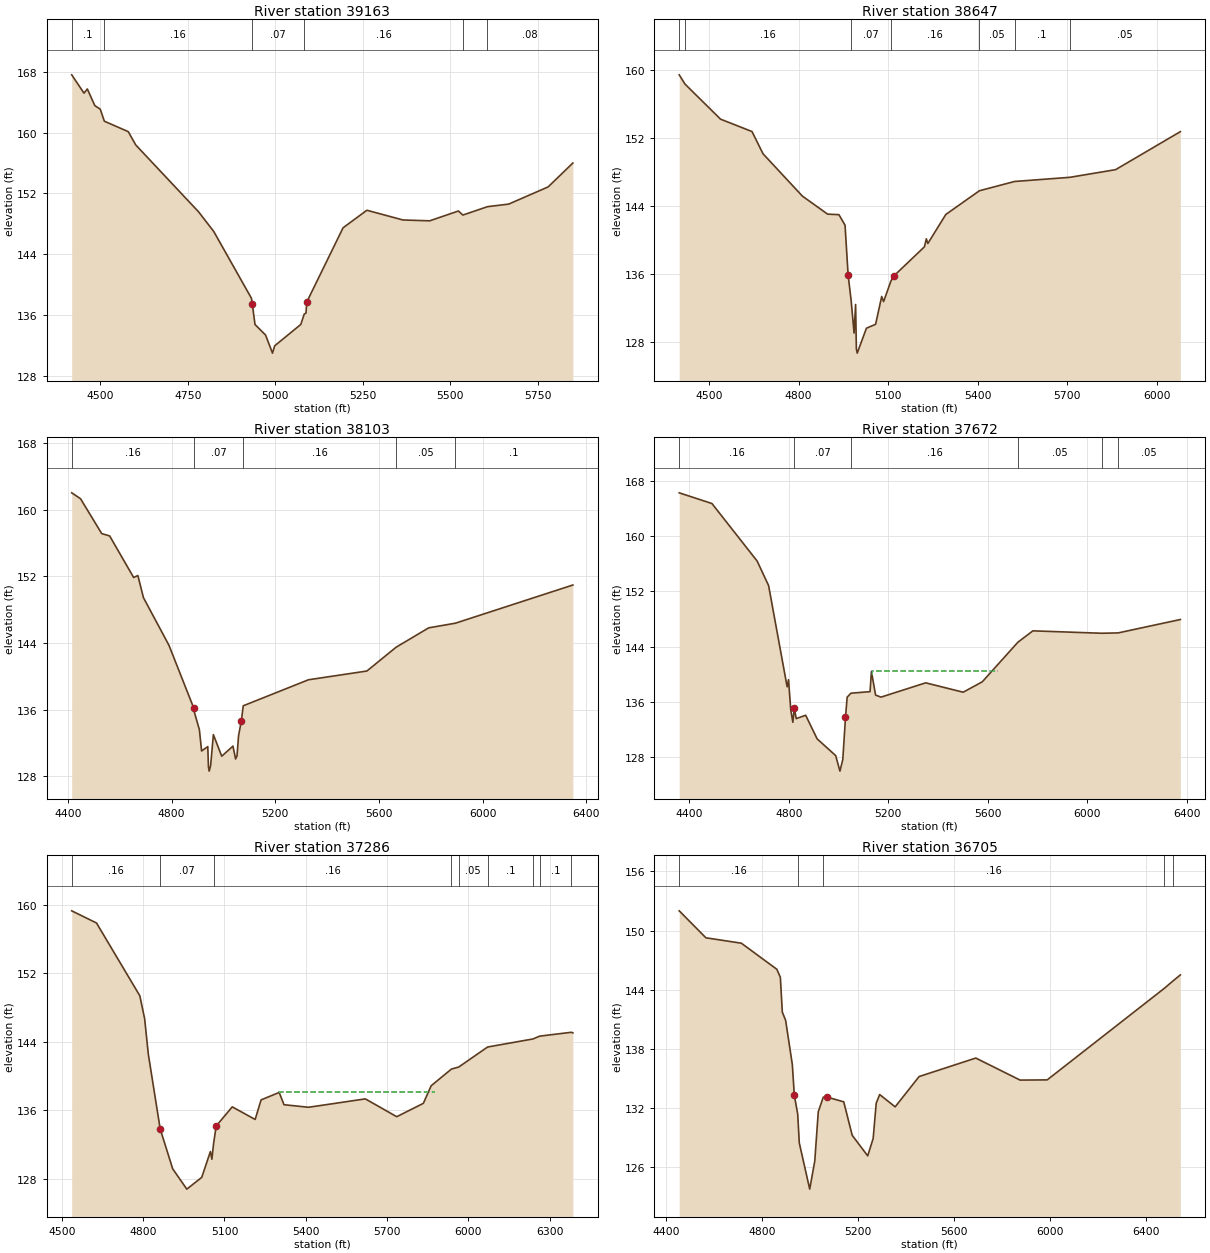
Type RM Length L Ch R = 1 ,39163   ,516,516,516
BEGIN DESCRIPTION:
PENITAS CREEK 70.0
END DESCRIPTION:
XS GIS Cut Line= 4
      2300928.03     13192766.99      2301080.83     13192510.01
      2301143.33      13191961.4      2301073.88       13191385.
#Sta/Elev= 30
  4418.6   167.6  4453.7  165.19  4463.2  165.74  4484.6  163.55  4500.2  163.08
  4511.8   161.5  4580.1  160.13  4601.5  158.38  4781.1  149.58  4824.5  146.99
  4932.1  138.21 4934.55  137.46  4942.2  134.77  4972.4  133.38  4992.2     131
  4998.4  131.96    5073  134.77  5082.9  136.14  5087.9  136.26    5090  137.71
  5193.8  147.48  5261.8  149.79    5365  148.51  5441.3   148.4  5523.3  149.69
  5536.2  149.16  5606.4  150.26  5667.1   150.6  5779.7  152.86  5850.3     156
#Mann= 6 ,-1 , 0
  4418.6      .1       0  4511.8     .16       0 4934.55     .07       0
  5082.9     .16       0  5536.2     .05       0  5606.4     .08       0
Bank Sta=4934.55,5090
XS Rating Curve= 0 ,0
Exp/Cntr=0.3,0.1

Type RM Length L Ch R = 1 ,38647   ,544,544,544
BEGIN DESCRIPTION:
PENITAS CREEK 69.0
END DESCRIPTION:
XS GIS Cut Line= 4
       2301608.6     13192996.13      2301643.33      13192648.9
      2301497.49     13191968.34       2301233.6     13191391.95
#Sta/Elev= 30
    4400  159.45  4419.4  158.36  4538.4  154.24  4643.9  152.78  4680.7  150.17
  4812.4   145.2  4897.2  143.07  4935.1  143.01  4955.6  141.77  4965.8  135.93
    4976  132.91  4985.8  129.09  4990.9  132.45  4993.5  127.23  4996.3  126.73
  5027.2  129.66  5057.9  130.12  5078.3  133.39  5084.7  132.79    5109  135.18
  5119.2  135.81  5221.5  139.23  5227.9  140.17    5233  139.62  5293.1  143.03
  5405.6  145.82  5523.3  146.91  5708.7   147.4  5861.9   148.3  6078.9  152.77
#Mann= 7 ,-1 , 0
    4400      .1       0  4419.4     .16       0    4976     .07       0
    5109     .16       0  5405.6     .05       0  5523.3      .1       0
  5708.7     .05       0
Bank Sta=4965.8,5119.2
XS Rating Curve= 0 ,0
Exp/Cntr=0.3,0.1

Type RM Length L Ch R = 1 ,38103   ,431,431,431
BEGIN DESCRIPTION:
PENITAS CREEK 68.0
END DESCRIPTION:
XS GIS Cut Line= 4
      2302316.94     13192961.41      2302212.77     13192718.34
      2301782.22     13191655.84      2301518.35     13191204.49
#Sta/Elev= 30
  4414.8  162.03  4448.9  161.32  4530.5  157.14  4561.2  156.86  4653.8  151.87
    4670  152.11  4691.6  149.45    4790  143.74  4885.9  136.19  4888.1  135.71
  4907.4  133.61  4915.9  131.06  4939.8  131.58  4942.4  129.14  4945.2  128.64
  4950.8   129.3  4961.4  133.02  4993.6  130.43  5036.9  131.64  5047.2   130.1
  5052.6  130.47  5058.5  132.88  5069.3  134.66  5076.7  136.48  5328.2   139.6
  5553.7  140.65  5666.3   143.5  5792.2  145.83  5895.5  146.39  6348.5  150.97
#Mann= 5 ,-1 , 0
  4414.8     .16       0  4888.1     .07       0  5076.7     .16       0
  5666.3     .05       0  5895.5      .1       0
Bank Sta=4885.9,5069.3
XS Rating Curve= 0 ,0
Exp/Cntr=0.3,0.1

Type RM Length L Ch R = 1 ,37672   ,386,386,386
BEGIN DESCRIPTION:
PENITAS CREEK 67.0
END DESCRIPTION:
XS GIS Cut Line= 4
       2302671.1     13192968.31      2302664.16     13192704.45
      2302178.05     13191641.95      2301803.03     13191197.49
#Sta/Elev= 30
  4359.6  166.27  4491.1  164.72  4672.7  156.39  4718.8  152.84  4793.3  138.17
  4798.8  139.21  4807.9  134.82  4816.3  133.03  4821.8  135.08  4829.8  133.57
  4867.8  134.05  4913.9  130.63  4988.4  128.21  5005.5  125.96  5016.9  127.64
  5027.8  133.74  5034.5  136.67  5049.8  137.25  5126.5  137.47    5132  140.39
  5148.8  136.97  5170.7  136.68  5350.1  138.75  5500.7  137.39  5577.6   138.9
  5720.6  144.63  5780.9  146.28  6057.9  145.93  6123.6  145.98  6373.5  147.92
#Mann= 6 ,-1 , 0
  4359.6     .16       0  4821.8     .07       0  5049.8     .16       0
  5720.6     .05       0  6057.9      .1       0  6123.6     .05       0
#XS Ineff= 1 ,-1
 5134.71  5639.9  140.51
Permanent Ineff=
       T
Bank Sta=4821.8,5027.8
XS Rating Curve= 0 ,0
Exp/Cntr=0.3,0.1

Type RM Length L Ch R = 1 ,37286   ,581,581,581
BEGIN DESCRIPTION:
PENITAS CREEK 66.0
END DESCRIPTION:
XS GIS Cut Line= 4
      2302903.75       13192806.      2302997.49     13192644.56
      2302466.24     13191457.06      2302242.97     13191171.48
#Sta/Elev= 30
    4536  159.27  4627.5  157.85  4787.4  149.36  4805.1   146.7  4818.8  142.55
  4862.6  133.82  4908.8  129.17  4960.9   126.8    5016  128.17    5048  131.19
  5053.5  130.29  5059.8  132.13 5069.32  134.16  5128.6   136.4  5213.2  134.93
  5235.1  137.21  5301.9  138.08  5319.7  136.65  5410.3  136.35    5620  137.33
  5735.9  135.25  5834.2  136.81  5862.9  138.86    5938  140.81  5964.5  141.04
  6071.3  143.38  6238.8  144.32  6263.7  144.65  6380.7   145.1  6386.1  145.03
#Mann= 9 ,-1 , 0
    4536     .16       0  4862.6     .07       0  5059.8     .16       0
    5938      .1       0  5964.5     .05       0  6071.3      .1       0
  6238.8     .05       0  6263.7      .1       0  6380.7     .05       0
#XS Ineff= 1 ,-1
 5302.07 5876.17   138.1
Permanent Ineff=
       T
Bank Sta=4862.6,5069.32
XS Rating Curve= 0 ,0
Exp/Cntr=0.3,0.1

Type RM Length L Ch R = 1 ,36705   ,944,944,944
BEGIN DESCRIPTION:
PENITAS CREEK 65.0
END DESCRIPTION:
XS GIS Cut Line= 4
      2303528.74     13192717.51      2303559.99     13192378.93
      2302976.66     13191613.31        2302435.      13191045.6
#Sta/Elev= 30
  4455.7     152  4566.8  149.26  4714.5  148.71  4862.3  146.06  4876.9  145.25
  4885.1  141.71  4898.9  140.87  4926.8  136.38    4935  133.28  4949.2  131.34
  4955.8  128.41  4999.2  123.72  5020.3  126.58  5034.8  131.58  5055.6  133.06
  5070.2  133.08  5140.9  132.59  5176.2  129.19  5240.7   127.1  5263.5  128.87
  5276.1  132.45  5290.6  133.33    5355  132.08  5454.8  135.16  5690.9  137.04
  5875.3   134.8  5988.3  134.82  6476.4  144.13  6511.1  144.85  6542.9  145.49
#Mann= 5 ,-1 , 0
  4455.7     .16       0  4949.2     .07       0  5055.6     .16       0
  6476.4      .1       0  6511.1     .05       0
#XS Ineff= 2 ,-1
 5103.63 5302.59  132.74 5681.87 6210.36  136.78
Permanent Ineff=
       T       T
Bank Sta=4935,5070.2
XS Rating Curve= 0 ,0
Exp/Cntr=0.3,0.1

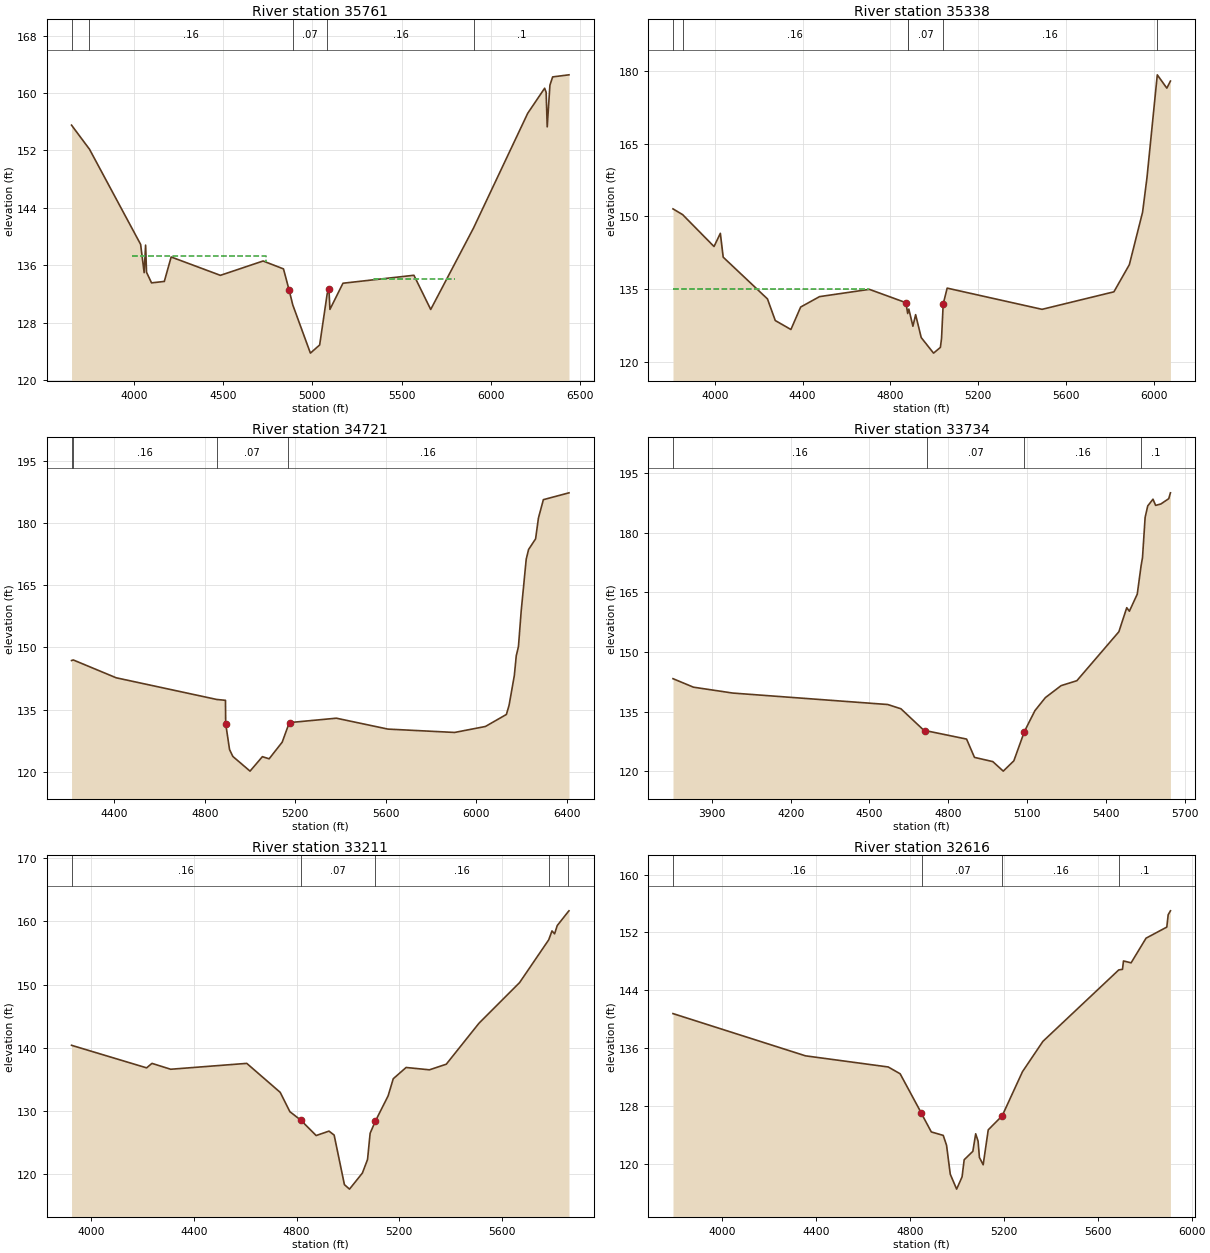
Type RM Length L Ch R = 1 ,35761   ,423,423,423
BEGIN DESCRIPTION:
PENITAS CREEK 64.0
END DESCRIPTION:
XS GIS Cut Line= 4
      2303981.86     13192826.81      2303794.37     13192196.64
      2303617.29     13191571.64      2302825.66     13190321.71
#Sta/Elev= 30
  3650.8  155.53  3751.4  152.17  4037.8   138.9  4057.6  134.95  4065.7   138.8
  4070.9  135.01  4098.9  133.53  4170.5  133.73  4208.9  137.14  4484.7  134.58
  4723.8  136.58  4838.1  135.48  4869.5  132.54  4890.1  130.46  4988.9  123.73
  5040.8  124.87  5083.2  132.05  5092.5  132.68  5098.4  129.83  5171.3  133.48
  5568.8  134.59  5662.9  129.82  5902.7  141.18  6206.4  157.19  6301.1  160.68
  6309.5  160.12  6315.5  155.29  6330.7  161.11    6346  162.26  6437.4  162.55
#Mann= 5 ,-1 , 0
  3650.8      .1       0  3751.4     .16       0  4890.1     .07       0
  5083.2     .16       0  5902.7      .1       0
#XS Ineff= 2 ,-1
 3991.19 4740.41  137.31 5346.63 5797.41   134.1
Permanent Ineff=
       T       T
Bank Sta=4869.5,5092.5
XS Rating Curve= 0 ,0
Exp/Cntr=0.3,0.1

Type RM Length L Ch R = 1 ,35338   ,617,617,617
BEGIN DESCRIPTION:
PENITAS CREEK 63.0
END DESCRIPTION:
XS GIS Cut Line= 4
       2304492.3      13192342.5       2304065.2     13191743.52
      2303809.99     13191024.77      2303737.21      13190260.5
#Sta/Elev= 30
  3809.7  151.52  3853.5  150.34  3996.6  143.76  4025.4  146.48  4038.4  141.56
    4240  132.96  4275.6   128.5  4346.9  126.65  4391.2  131.28  4477.2  133.43
  4704.3  134.93  4870.8  132.18  4878.8  129.95  4884.1  130.86  4902.6  127.32
    4915  129.71  4940.5  124.98  4996.7  121.78  5027.8  122.96  5033.1  124.83
  5040.6  131.91  5058.7  135.18    5491  130.81  5818.3  134.42  5888.6  140.02
  5948.9  150.84    5969  157.99  6015.9  179.16  6059.4  176.41  6075.8  177.87
#Mann= 6 ,-1 , 0
  3809.7     .05       0  3853.5     .16       0  4878.8      .1       0
  4878.8     .07       0  5040.6     .16       0  6015.9      .1       0
#XS Ineff= 2 ,-1
  3809.7 4699.28  135.06 5063.73 5912.44  135.08
Permanent Ineff=
       T       T
Bank Sta=4870.8,5040.6
XS Rating Curve= 0 ,0
Exp/Cntr=0.3,0.1

Type RM Length L Ch R = 1 ,34721   ,987,987,987
BEGIN DESCRIPTION:
PENITAS CREEK 62.0
END DESCRIPTION:
XS GIS Cut Line= 3
      2304789.15     13192134.12      2304632.91     13191686.22
      2303945.42     13190102.91
#Sta/Elev= 30
  4210.3  146.82    4218  146.96  4407.7  142.66  4852.5  137.43  4891.3  137.22
 4892.19  131.61  4909.3  125.34  4923.8  123.69  4999.9  120.14  5054.6  123.63
  5084.4  123.11  5142.2  127.13  5165.7  130.66  5174.6  131.85  5381.7  132.91
  5609.7  130.28    5905  129.47  6041.1  130.91  6133.9  133.81  6145.8  136.01
  6169.3  143.28  6177.6  147.96  6187.3  150.19  6199.4  158.74  6221.7  171.28
  6232.1  173.61  6263.1  176.17  6275.7  181.19  6297.5  185.63  6410.8  187.28
#Mann= 4 ,-1 , 0
  4210.3     .05       0    4218     .16       0  4852.5     .07       0
  5165.7     .16       0
#XS Ineff= 1 ,-1
  5388.6  6194.3  132.74
Permanent Ineff=
       T
Bank Sta=4892.19,5174.6
XS Rating Curve= 0 ,0
Exp/Cntr=0.3,0.1

Type RM Length L Ch R = 1 ,33734   ,523,523,523
BEGIN DESCRIPTION:
PENITAS CREEK 61.0
END DESCRIPTION:
XS GIS Cut Line= 3
      2305049.58     13192024.76      2305039.16     13191613.31
      2305049.57     13190130.43
#Sta/Elev= 30
  3751.7   143.3  3829.6  141.16  3979.7  139.68  4569.7   136.8  4619.8  135.73
  4709.8  130.15  4719.8  130.15  4869.8  128.11  4899.8  123.51  4969.8  122.44
  5009.5  120.05  5049.8  122.64  5089.8  129.97  5129.8  135.23  5169.8  138.53
  5229.8  141.55  5289.8  142.79  5449.8   155.1  5479.8  161.15  5489.8  160.27
  5519.8  164.55  5534.5  171.73  5539.8  173.74  5549.8  183.85  5559.8  186.76
  5579.8  188.44  5589.8  186.88  5609.8  187.24  5639.8  188.57  5646.2  190.04
#Mann= 4 ,-1 , 0
  3751.7     .16       0  4719.8     .07       0  5089.8     .16       0
  5534.5      .1       0
Bank Sta=4709.8,5089.8
XS Rating Curve= 0 ,0
Exp/Cntr=0.3,0.1

Type RM Length L Ch R = 1 ,33211   ,595,595,595
BEGIN DESCRIPTION:
PENITAS CREEK 60.0
END DESCRIPTION:
XS GIS Cut Line= 4
      2305403.73     13191977.93      2305554.79     13191451.85
      2305523.54     13190660.18      2305419.39     13190071.75
#Sta/Elev= 30
  3923.3  140.39  4215.7  136.82  4236.5  137.53  4309.4   136.6  4605.7  137.53
  4735.8  132.95  4773.7  129.88  4815.9  128.56  4875.9  126.11    4926  126.81
    4946  126.18    4986  118.34  5005.8  117.63  5056.1  120.18  5076.1  122.33
  5086.1  126.47  5106.1  128.35  5156.2  132.39  5176.2   135.1  5226.2  136.88
  5317.1  136.51  5382.7   137.4    5510  143.88  5668.3  150.32  5781.6  157.08
  5794.4  158.49  5804.5  158.03  5814.7  159.33  5856.8   161.5  5860.5  161.67
#Mann= 5 ,-1 , 0
  3923.3     .16       0  4815.9     .07       0  5106.1     .16       0
  5781.6     .16       0  5856.8      .1       0
Bank Sta=4815.9,5106.1
XS Rating Curve= 0 ,0
Exp/Cntr=0.3,0.1

Type RM Length L Ch R = 1 ,32616   ,538,538,538
BEGIN DESCRIPTION:
PENITAS CREEK 59.0
END DESCRIPTION:
XS GIS Cut Line= 4
      2305554.78     13192087.28      2305820.41     13191540.39
      2306466.24     13190394.56      2306570.39     13190227.92
#Sta/Elev= 30
  3789.8  140.77  4354.5  134.93    4707  133.39  4757.7  132.45  4847.2  127.07
  4852.9   126.7  4890.5  124.41  4941.4  123.93  4955.5  122.57  4971.4  118.56
  4998.5   116.5  5021.7   118.2  5030.6  120.56  5067.6  121.73  5079.7  124.15
  5089.9  123.13  5095.6  120.88  5111.6  119.87  5133.2   124.7  5192.5  126.63
  5279.1  132.74  5366.1  136.93  5689.4  146.81  5705.3  146.89  5709.5  148.05
    5742  147.79  5805.7   151.2  5894.1  152.73    5900  154.44  5909.6  154.98
#Mann= 4 ,-1 , 0
  3789.8     .16       0  4852.9     .07       0  5192.5     .16       0
  5689.4      .1       0
Bank Sta=4847.2,5192.5
XS Rating Curve= 0 ,0
Exp/Cntr=0.3,0.1

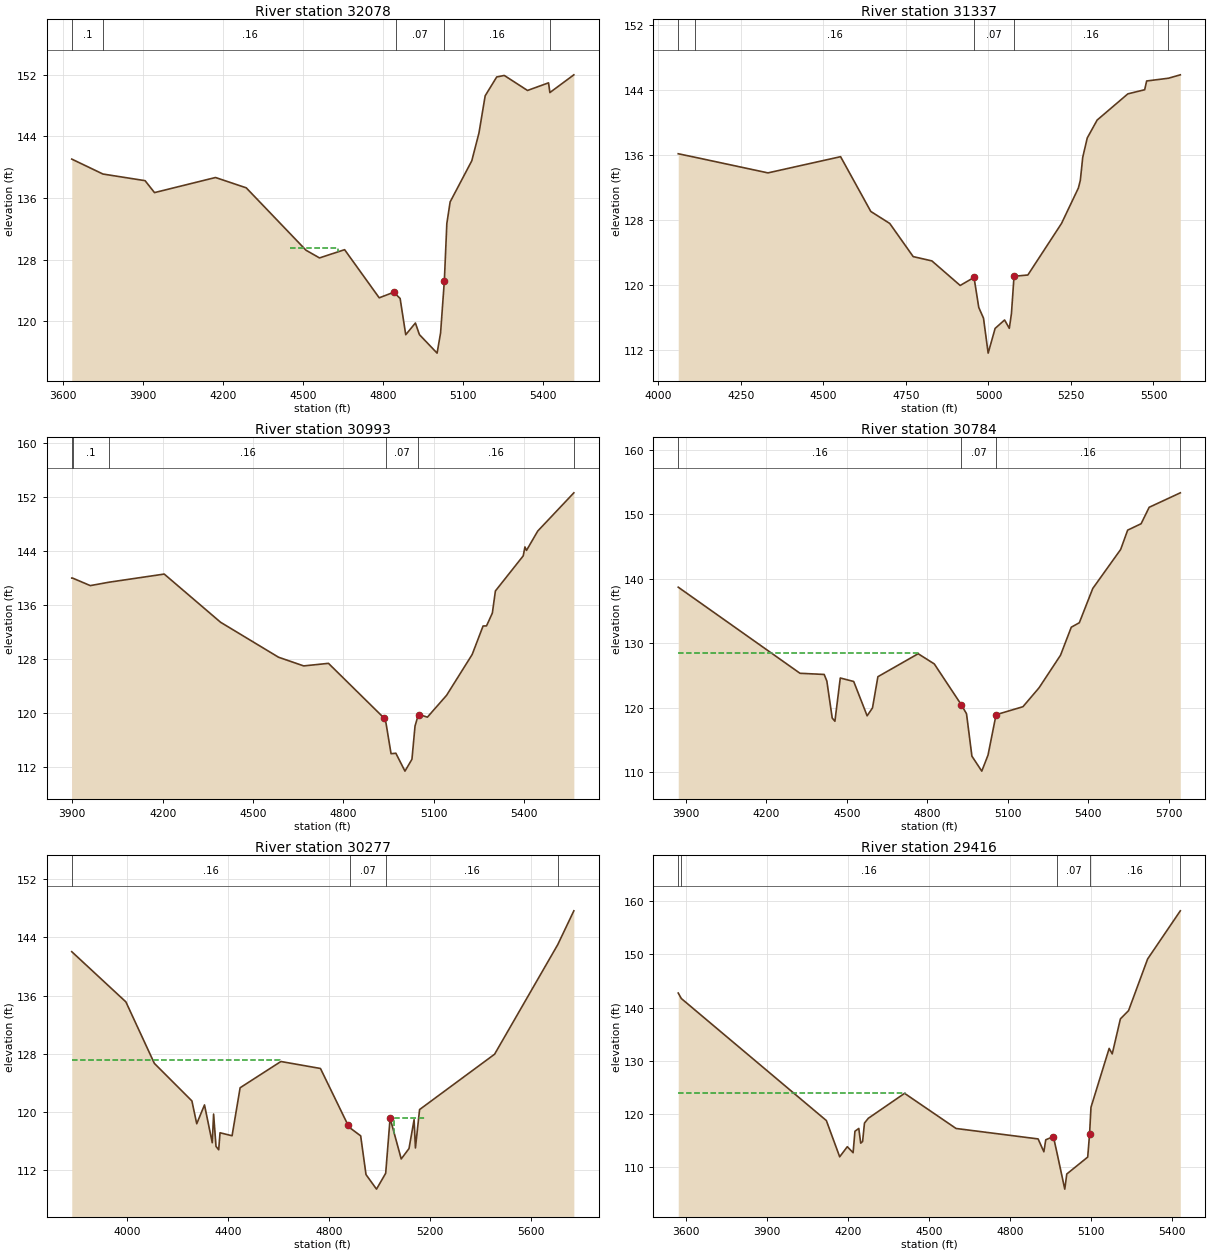
Type RM Length L Ch R = 1 ,32078   ,741,741,741
BEGIN DESCRIPTION:
PENITAS CREEK 58.0
END DESCRIPTION:
XS GIS Cut Line= 4
      2305825.59     13192269.59       2306190.2     13191790.39
      2306768.33     13190904.97        2306810.     13190686.19
#Sta/Elev= 30
    3633  141.05  3749.9  139.11  3907.8  138.25  3943.2   136.7  4171.9  138.66
  4287.1  137.32  4511.1  129.22  4561.8  128.22  4655.9  129.29  4785.6  123.04
  4842.9   123.8  4849.3  123.45    4864  122.96  4885.1  118.25  4921.3  119.77
  4936.4  118.26  5002.6  115.86  5015.7  118.48  5029.9  125.28  5039.1  132.67
  5051.5  135.49  5132.6  140.82  5159.6  144.44  5182.9  149.27  5226.1  151.71
  5254.5  151.91  5341.6  149.96  5420.4  150.95  5425.5  149.69  5515.3  151.99
#Mann= 5 ,-1 , 0
    3633      .1       0  3749.9     .16       0  4849.3     .07       0
  5029.9     .16       0  5425.5      .1       0
#XS Ineff= 1 ,-1
 4450.78 4632.12  129.56
Permanent Ineff=
       T
Bank Sta=4842.9,5029.9
XS Rating Curve= 0 ,0
Exp/Cntr=0.3,0.1

Type RM Length L Ch R = 1 ,31337   ,344,344,344
BEGIN DESCRIPTION:
PENITAS CREEK 57.0
END DESCRIPTION:
XS GIS Cut Line= 3
      2306437.67     13192148.96      2307251.11     13191480.31
      2307512.46     13191091.46
#Sta/Elev= 30
  4059.9  136.17  4111.7  135.73  4331.8  133.81  4551.9  135.81  4643.5  129.05
  4700.9  127.57  4771.9  123.48  4828.6  122.95  4914.3  119.92  4956.3  120.91
  4970.6  117.21    4985  115.88  4999.1  111.57  5020.2  114.62  5048.9  115.66
  5063.2  114.63  5069.7  116.46  5077.5  121.05  5119.4  121.21  5221.4  127.57
  5272.4  131.93  5278.4  132.89  5285.7  135.73  5299.4  138.12  5329.4  140.33
  5422.4  143.56  5473.4  144.07  5479.4  145.15  5545.4  145.49  5581.4  145.91
#Mann= 5 ,-1 , 0
  4059.9     .05       0  4111.7     .16       0  4956.3     .07       0
  5077.5     .16       0  5545.4      .1       0
Bank Sta=4956.3,5077.5
XS Rating Curve= 0 ,0
Exp/Cntr=0.3,0.1

Type RM Length L Ch R = 1 ,30993   ,209,209,209
BEGIN DESCRIPTION:
PENITAS CREEK 56.0
END DESCRIPTION:
XS GIS Cut Line= 3
      2306975.85      13192678.5      2307470.94      13191694.2
      2307599.51      13191143.2
#Sta/Elev= 30
  3898.2  139.99  3900.7  139.99  3959.8  138.87  4021.2  139.37  4205.3  140.58
  4392.6  133.44  4584.8  128.27  4668.5  126.98  4750.8  127.36  4936.3  119.22
  4941.9  118.51  4958.7  113.98  4974.6  114.05  5004.9   111.4  5028.1  113.16
  5038.3  118.07  5047.7  119.51  5052.8  119.78  5079.4  119.39    5143  122.62
  5228.1  128.67  5264.3  132.89  5275.8  132.91  5295.1   134.8  5305.3  138.08
  5397.7  143.28  5403.4   144.6  5408.5  144.08  5445.9  146.95  5565.8  152.61
#Mann= 6 ,-1 , 0
  3898.2     .16       0  3900.7      .1       0  4021.2     .16       0
  4941.9     .07       0  5047.7     .16       0  5565.8     .05       0
Bank Sta=4936.3,5052.8
XS Rating Curve= 0 ,0
Exp/Cntr=0.3,0.1

Type RM Length L Ch R = 1 ,30784   ,507,507,507
BEGIN DESCRIPTION:
PENITAS CREEK 55.0
END DESCRIPTION:
XS GIS Cut Line= 3
      2307643.33      13192899.8      2307617.29      13192545.6
      2307705.77     13191030.93
#Sta/Elev= 30
  3871.2   138.7  4325.3  125.36  4415.4  125.18  4425.4  124.16  4445.5  118.42
  4455.5  117.93  4475.5  124.63  4525.6  124.09  4575.7  118.77  4595.7     120
  4615.8  124.83    4766  128.39  4826.1  126.81  4926.3  120.52  4946.3  119.09
  4966.4  112.52  5003.2   110.2  5026.5  112.68  5056.5  118.94  5156.7  120.18
  5216.8  123.11  5296.9  128.16    5337   132.5    5367  133.19  5417.1   138.5
  5521.1  144.54  5547.3  147.54  5597.4  148.53  5627.5  151.08  5743.6  153.32
#Mann= 4 ,-1 , 0
  3871.2     .16       0  4926.3     .07       0  5056.5     .16       0
  5743.6     .05       0
#XS Ineff= 2 , 0
       0 4767.05  128.46               0
Permanent Ineff=
       T       F
Bank Sta=4926.3,5056.5
XS Rating Curve= 0 ,0
Exp/Cntr=0.3,0.1

Type RM Length L Ch R = 1 ,30277   ,861,861,861
BEGIN DESCRIPTION:
PENITAS CREEK 54.0
END DESCRIPTION:
XS GIS Cut Line= 3
      2307778.75     13192915.36      2307856.87     13192592.47
      2308413.82     13191030.92
#Sta/Elev= 30
  3780.9  142.03  3995.4  135.13  4108.3  126.67  4257.1  121.51  4276.2  118.37
    4307  120.96  4337.8  115.76  4343.1   119.7  4352.6  115.26  4363.3  114.79
  4368.6  117.13  4416.3  116.72  4448.2  123.32  4609.8  126.93  4766.7  125.97
  4876.4  118.14  4884.9  117.77    4926  116.71  4947.2  111.38  4988.8  109.38
  5025.2  111.56  5042.7  119.14  5086.8  113.53  5117.6  114.96  5137.8  118.93
  5143.1  115.04  5159.5  120.32  5456.8  127.93  5707.2     143    5771  147.65
#Mann= 4 ,-1 , 0
  3780.9     .16       0  4884.9     .07       0  5025.2     .16       0
  5707.2      .1       0
#XS Ineff= 2 ,-1
  3780.9 4607.95  127.16 5059.59 5186.53   119.1
Permanent Ineff=
       T       T
Bank Sta=4876.4,5042.7
XS Rating Curve= 0 ,0
Exp/Cntr=0.3,0.1

Type RM Length L Ch R = 1 ,29416   ,598,598,598
BEGIN DESCRIPTION:
PENITAS CREEK 53.0
END DESCRIPTION:
XS GIS Cut Line= 3
      2307891.66     13193017.02      2308942.44     13192000.57
      2309337.75     13191946.85
#Sta/Elev= 30
  3570.5  142.74  3581.9  141.71  4119.5  118.79  4168.9  111.98  4197.2  113.88
  4218.6  112.75  4225.5  116.78  4239.7  117.31  4246.8  114.55  4253.8  114.84
  4260.8  118.32  4274.9  119.21  4409.4   123.9  4600.3   117.3  4904.4  115.34
  4925.7  112.92  4932.7  115.18    4961  115.78  4975.1  112.54  5003.2  105.91
  5010.6  108.75  5088.2  111.93  5095.2  116.34  5100.3  121.28  5167.7  132.34
  5179.1  131.31  5209.3  137.88  5239.6  139.44  5310.3  149.14  5431.4  158.18
#Mann= 5 ,-1 , 0
  3570.5     .05       0  3581.9     .16       0  4975.1     .07       0
  5095.2     .16       0  5431.4      .1       0
#XS Ineff= 2 , 0
       0 4411.36  124.03               0
Permanent Ineff=
       T       F
Bank Sta=4961,5095.2
XS Rating Curve= 0 ,0
Exp/Cntr=0.3,0.1