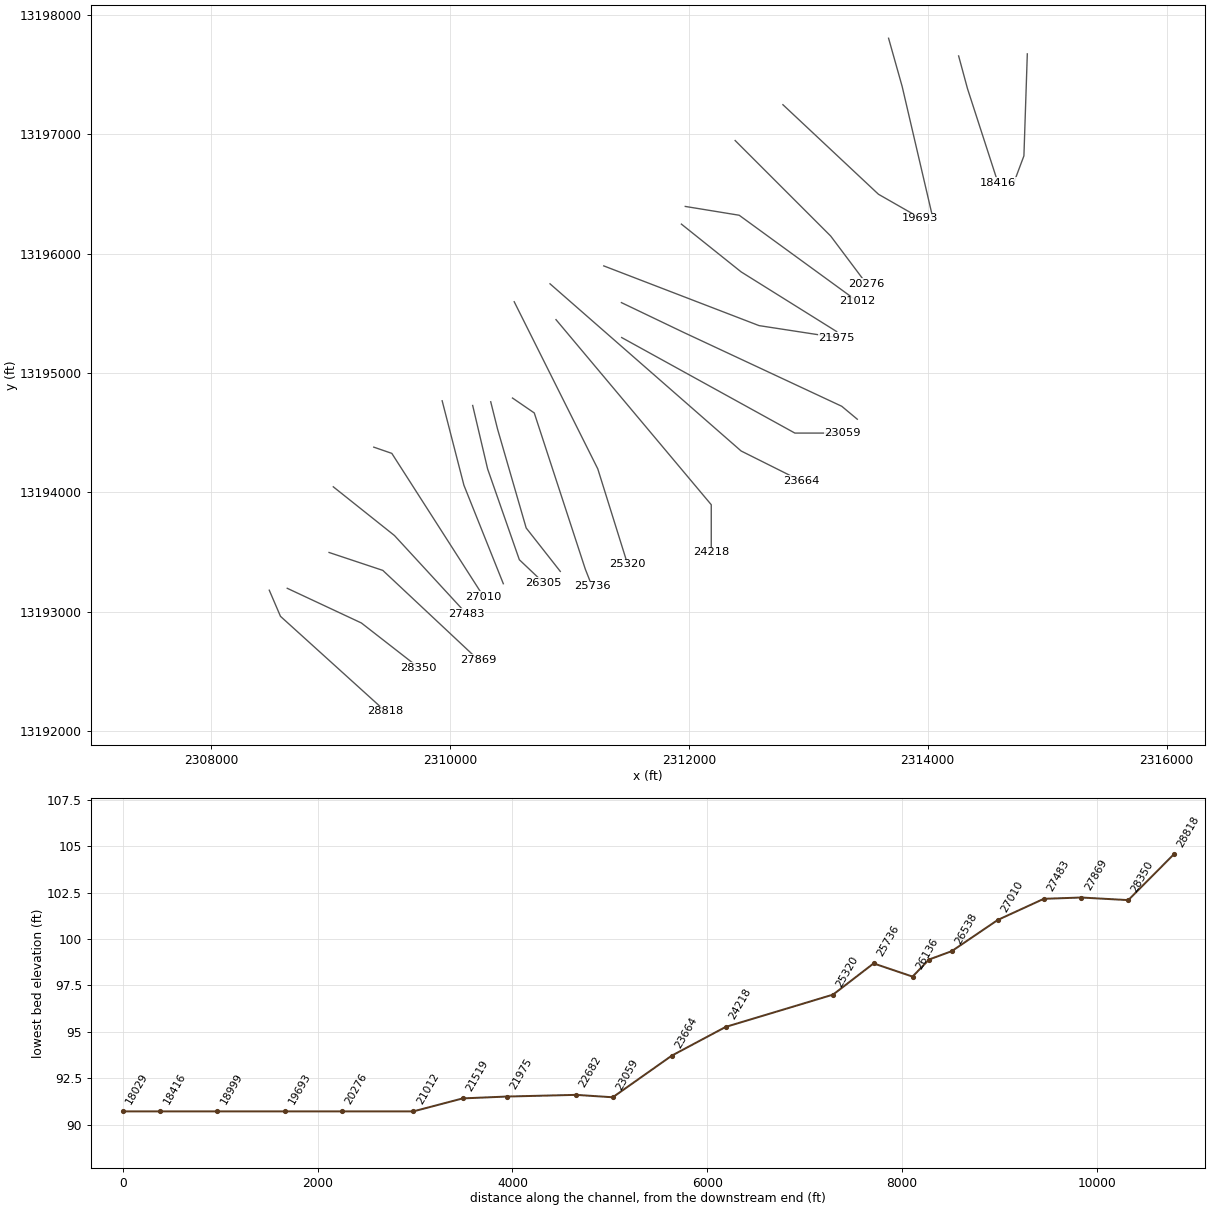
HEC-RAS study PENITAS CREEK.prj: PENITAS CREEK Base Level Engineering

--- PENITAS CREEK.g01 (geometry) --- (continued)

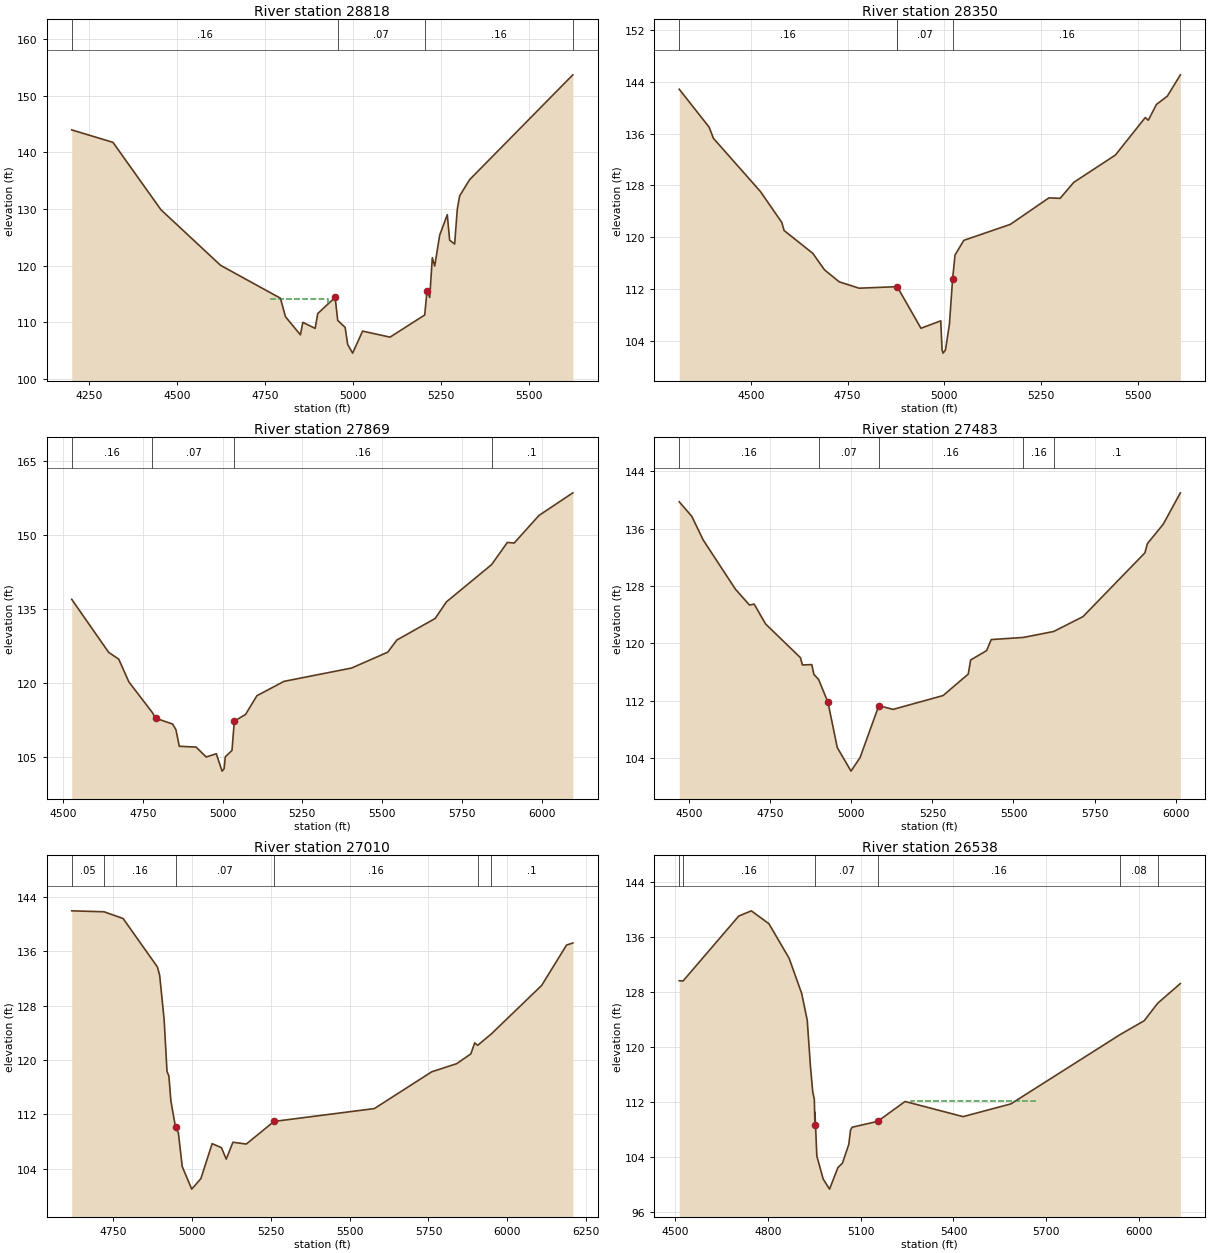
Type RM Length L Ch R = 1 ,28818   ,468,468,468
BEGIN DESCRIPTION:
PENITAS CREEK 52.0
END DESCRIPTION:
XS GIS Cut Line= 3
      2308487.08     13193181.01      2308580.83     13192962.27
      2309461.01     13192165.41
#Sta/Elev= 30
  4199.9  143.97  4317.2  141.77  4453.7  129.87  4623.3  120.06  4793.6  114.25
  4807.8  110.99  4850.4  107.79  4857.2  109.99  4892.3  108.93  4899.7  111.55
  4949.1   114.4  4956.5  110.33  4977.5  109.11  4984.9  106.07  4998.9  104.56
  5027.2  108.45  5105.2  107.38  5203.9  111.29 5210.49  115.57  5218.1  114.39
  5225.5   121.4  5232.3  119.93  5246.5  125.38  5268.1     129  5274.8  124.51
    5289  123.82  5296.5  129.95  5303.2  132.31  5331.6  135.18  5625.2  153.69
#Mann= 4 ,-1 , 0
  4199.9     .16       0  4956.5     .07       0  5203.9     .16       0
  5625.2      .1       0
#XS Ineff= 1 ,-1
 4764.77 4928.91  114.15
Permanent Ineff=
       T
Bank Sta=4949.1,5210.49
XS Rating Curve= 0 ,0
Exp/Cntr=0.3,0.1

Type RM Length L Ch R = 1 ,28350   ,481,481,481
BEGIN DESCRIPTION:
PENITAS CREEK 51.0
END DESCRIPTION:
XS GIS Cut Line= 3
      2308637.68     13193196.87       2309258.1     13192906.52
      2309739.27     13192532.07
#Sta/Elev= 30
    4315  142.86  4392.2     137  4403.4  135.27  4524.8  127.05    4580  122.28
  4585.9  121.03    4660  117.51  4690.4  114.95  4728.5   113.1  4779.7  112.12
  4878.1  112.36  4939.5  105.93  4990.7  107.08    4994  102.59  4996.8  102.09
  5002.9  102.59  5013.1  106.58  5021.2  113.49  5027.5  117.24  5050.2  119.51
  5170.5  121.98    5270  126.07    5299     126  5334.3  128.47  5441.9  132.69
    5519  138.48    5527  138.07  5547.8   140.5  5576.1  141.79  5609.7  145.08
#Mann= 5 ,-1 , 0
    4315     .16       0  4878.1     .12       0  4878.1     .07       0
  5021.2     .16       0  5609.7      .1       0
Bank Sta=4878.1,5021.2
XS Rating Curve= 0 ,0
Exp/Cntr=0.3,0.1

Type RM Length L Ch R = 1 ,27869   ,386,386,386
BEGIN DESCRIPTION:
PENITAS CREEK 50.0
END DESCRIPTION:
XS GIS Cut Line= 3
      2308987.76     13193496.84      2309437.72     13193346.85
      2310237.73     13192596.84
#Sta/Elev= 30
  4527.3  137.02  4643.2  126.28  4674.8   124.9  4706.4  120.31  4780.2  114.08
  4790.8  112.93  4843.5  111.77    4854  110.62  4864.6  107.26  4917.3   107.1
  4948.9  105.09  4980.5  105.75  4998.7  102.23    5005  102.73  5008.7  105.12
  5029.7  106.44    5037  112.34  5072.2  113.71  5107.8   117.5  5192.8  120.41
  5404.8  123.11  5518.1  126.32  5546.5  128.78  5666.6  133.14  5701.8   136.5
  5843.5  144.05  5892.8  148.54  5914.3  148.42  5991.9     154  6098.2  158.59
#Mann= 4 ,-1 , 0
  4527.3     .16       0  4780.2     .07       0    5037     .16       0
  5843.5      .1       0
Bank Sta=4790.8,5037
XS Rating Curve= 0 ,0
Exp/Cntr=0.3,0.1

Type RM Length L Ch R = 1 ,27483   ,473,473,473
BEGIN DESCRIPTION:
PENITAS CREEK 49.0
END DESCRIPTION:
XS GIS Cut Line= 3
      2309023.15      13194046.8      2309535.28     13193638.83
      2310138.55     13192983.48
#Sta/Elev= 30
  4469.2  139.77  4508.1  137.72  4543.3  134.42  4642.6  127.56  4685.9  125.35
  4700.3  125.48  4735.5  122.71  4842.8  118.01  4849.2  116.99  4878.1  117.03
  4884.5  115.66  4898.9  114.97  4927.7   111.8  4956.6  105.45    4999  102.16
    5027  104.06  5084.7   111.3  5128.7  110.78  5282.8  112.71  5360.5  115.71
  5367.9  117.68  5417.2  118.99  5431.4  120.53  5530.6  120.83  5624.1  121.66
  5714.3  123.73  5905.5  132.65  5912.8  133.91  5962.2  136.66  6014.7  141.02
#Mann= 5 ,-1 , 0
  4469.2     .16       0  4898.9     .07       0  5084.7     .16       0
  5530.6     .16       0  5624.1      .1       0
Bank Sta=4927.7,5084.7
XS Rating Curve= 0 ,0
Exp/Cntr=0.3,0.1

Type RM Length L Ch R = 1 ,27010   ,472,472,472
BEGIN DESCRIPTION:
PENITAS CREEK 48.0
END DESCRIPTION:
XS GIS Cut Line= 3
      2309362.06     13194378.94      2309513.12     13194326.85
      2310283.32     13193124.71
#Sta/Elev= 30
  4619.9  141.96  4722.1  141.82  4782.7  140.83  4891.3  133.71  4898.4  132.51
  4912.5  126.06  4921.8  118.31  4927.7  117.68  4934.1  113.97  4948.8  110.12
  4957.8   109.3    4970  104.34  5000.1  101.02  5029.1  102.57  5064.7  107.71
  5094.2  107.12  5109.4  105.44  5130.6  107.92  5172.9  107.65  5260.8  110.98
  5578.7  112.87  5760.4  118.28  5839.1  119.47  5884.2  120.91  5896.6  122.54
  5905.8  122.17  5949.4  123.86  6108.7  130.99  6187.4  136.92  6207.4  137.23
#Mann= 6 ,-1 , 0
  4619.9     .05       0  4722.1     .16       0  4948.8     .07       0
  5260.8     .16       0  5905.8     .08       0  5949.4      .1       0
Bank Sta=4948.8,5260.8
XS Rating Curve= 0 ,0
Exp/Cntr=0.3,0.1

Type RM Length L Ch R = 1 ,26538   ,233,233,233
BEGIN DESCRIPTION:
PENITAS CREEK 47.0
END DESCRIPTION:
XS GIS Cut Line= 3
      2309934.59     13194767.27      2310116.88     13194059.84
      2310446.73      13193235.2
#Sta/Elev= 30
  4514.2  129.61  4526.7  129.58  4706.4     139  4747.1  139.76  4803.8  137.89
  4869.1  132.88  4909.8  127.75  4927.7  123.86    4938  117.19  4945.4  113.48
  4950.5  112.41 4952.27  109.21 4952.42   110.5 4954.32  108.71  4958.7  104.14
  4979.3  100.79  4999.7   99.34  5026.7  102.47  5041.3  103.11  5061.9  105.84
  5067.4  107.89  5072.6  108.33  5154.9  109.18  5243.7  112.07    5431  109.87
  5585.4  111.72  5938.1  121.78  6016.2   123.8  6059.7  126.34  6132.9   129.2
#Mann= 6 ,-1 , 0
  4514.2     .12       0  4526.7     .16       0 4954.32     .07       0
  5154.9     .16       0  5938.1     .08       0  6059.7      .1       0
#XS Ineff= 1 ,-1
 5261.76 5666.53  112.18
Permanent Ineff=
       T
Bank Sta=4954.32,5154.9
XS Rating Curve= 0 ,0
Exp/Cntr=0.3,0.1

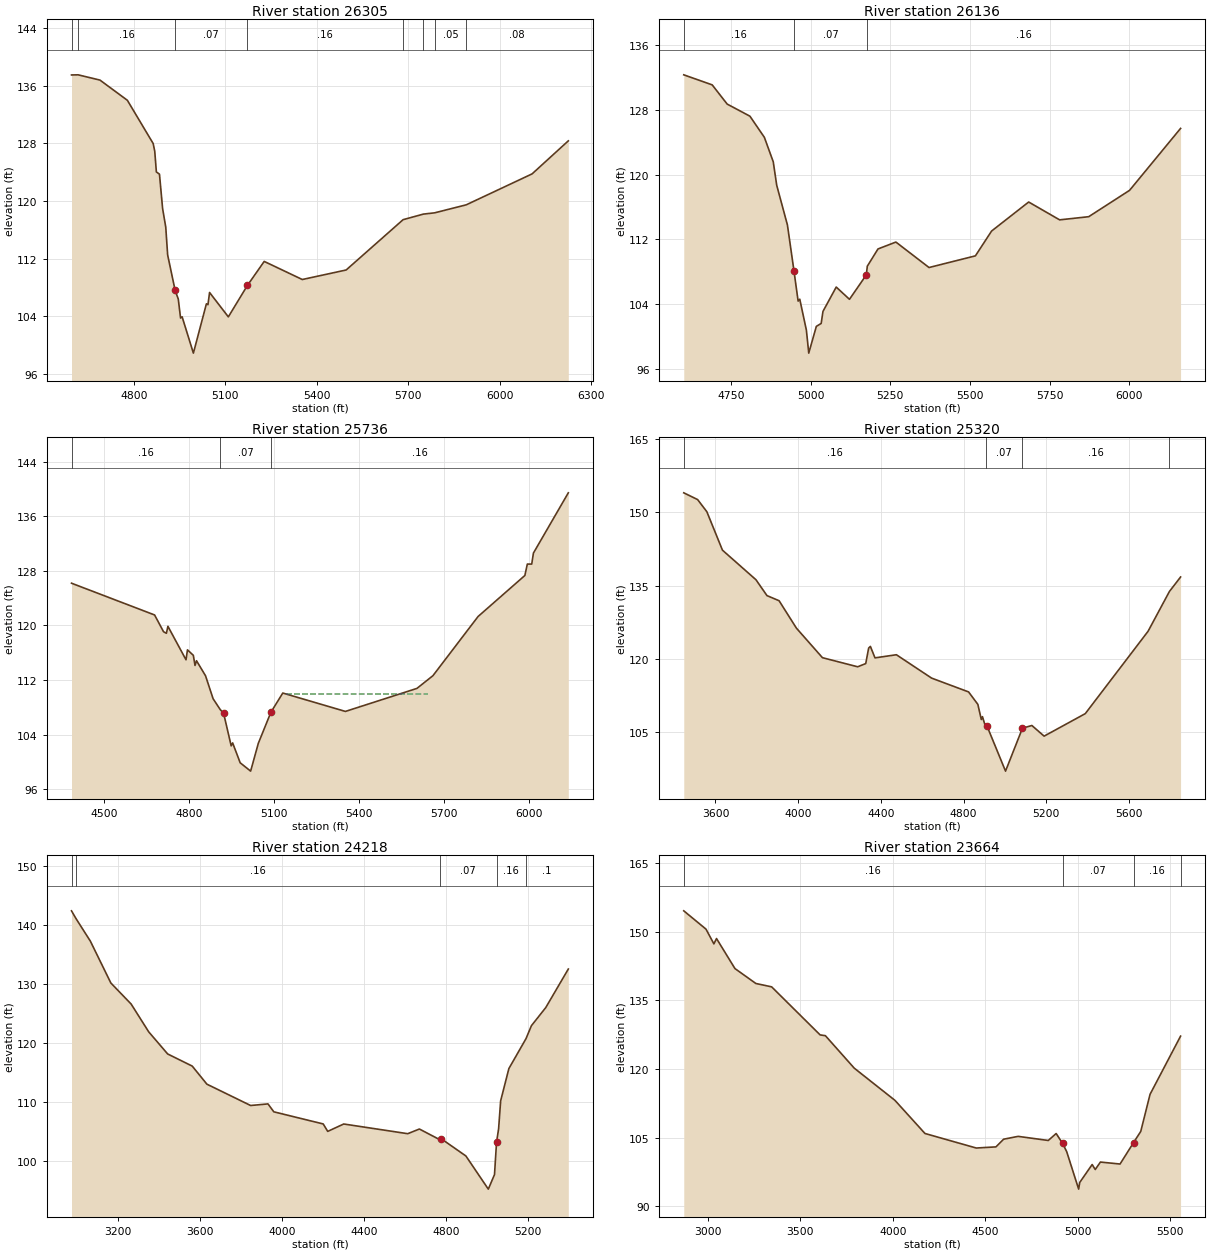
Type RM Length L Ch R = 1 ,26305   ,169,169,169
BEGIN DESCRIPTION:
Mapping XS a8e348b0
END DESCRIPTION:
XS GIS Cut Line= 4
       2310190.2     13194727.91       2310315.2     13194196.64
      2310580.83     13193436.22      2310783.34      13193244.1
#Sta/Elev= 30
  4595.2  137.47  4616.8  137.49  4688.6  136.76  4778.5  133.96  4863.2  127.96
  4868.4  126.89  4873.7  124.02  4883.9  123.71  4894.2  118.93  4904.5  116.37
  4910.7  112.51  4935.3  107.59  4945.6  106.39  4953.1  103.76  4958.2  103.93
  4995.2   98.89  5037.9  105.73    5043  105.61  5048.3   107.3  5109.9  103.92
  5172.5  108.28  5227.6  111.61  5352.6   109.1  5496.5  110.42  5683.4   117.4
  5749.7  118.17    5787  118.35  5890.7  119.46  6106.7  123.75  6225.6  128.33
#Mann= 8 ,-1 , 0
  4595.2     .08       0  4616.8     .16       0  4935.3     .07       0
  5172.5     .16       0  5683.4     .05       0  5749.7     .08       0
    5787     .05       0  5890.7     .08       0
#XS Ineff= 1 ,-1
 5231.09 5616.58  111.41
Permanent Ineff=
       T
Bank Sta=4935.3,5172.5
XS Rating Curve= 0 ,0
Exp/Cntr=0.3,0.1

Type RM Length L Ch R = 1 ,26136   ,400,400,400
BEGIN DESCRIPTION:
Mapping XS d180a482
END DESCRIPTION:
XS GIS Cut Line= 4
      2310341.24     13194759.14      2310398.54     13194529.97
      2310638.12     13193701.85      2310923.67     13193338.42
#Sta/Elev= 30
  4601.1   132.3  4690.4  131.06  4737.5  128.69  4808.9   127.2  4854.3  124.59
  4882.2  121.57  4893.1  118.67  4926.7  113.78 4947.27  108.12  4960.3  104.39
  4965.5  104.62  4986.3   100.8  4993.7   97.97  5017.5  101.27  5032.7  101.63
  5038.4  103.12    5080  106.12  5121.6  104.61 5174.55  107.62  5177.6  108.69
  5211.2  110.82  5267.4  111.67  5371.5  108.53  5517.2  109.97    5568  113.03
  5684.5  116.61  5781.7  114.41  5873.1   114.8  6001.4  118.05  6161.6  125.69
#Mann= 3 ,-1 , 0
  4601.1     .16       0 4947.27     .07       0  5177.6     .16       0
#XS Ineff= 1 ,-1
 5269.84 5566.63  111.51
Permanent Ineff=
       T
Bank Sta=4947.27,5174.55
XS Rating Curve= 0 ,0
Exp/Cntr=0.3,0.1

Type RM Length L Ch R = 1 ,25736   ,416,416,416
BEGIN DESCRIPTION:
PENITAS CREEK 46.0
END DESCRIPTION:
XS GIS Cut Line= 4
      2310523.51     13194790.41      2310705.83     13194665.39
      2311132.91      13193358.1      2311190.19      13193212.3
#Sta/Elev= 30
  4384.2  126.19  4677.4  121.54  4708.9  119.09  4719.1  118.86  4724.4  119.88
  4788.2  114.98  4793.4  116.43  4814.1  115.63    4820  114.15  4825.3  114.84
  4857.2  112.63  4883.8  109.28  4908.8   107.7  4920.9  107.15  4947.6  102.38
  4952.8  102.81  4979.4    99.9  5016.3   98.68  5043.2  102.73  5087.7  107.29
  5129.7  110.11  5350.7  107.42  5603.1  110.79  5659.5  112.65  5818.9  121.32
  5983.9  127.32  5992.6  128.99  6008.1  128.99  6014.1   130.6  6137.2  139.42
#Mann= 3 ,-1 , 0
  4384.2     .16       0  4908.8     .07       0  5087.7     .16       0
#XS Ineff= 1 ,-1
  5139.9 5642.49     110
Permanent Ineff=
       T
Bank Sta=4920.9,5087.7
XS Rating Curve= 0 ,0
Exp/Cntr=0.3,0.1

Type RM Length L Ch R = 1 ,25320   ,1102,1102,1102
BEGIN DESCRIPTION:
PENITAS CREEK 45.0
END DESCRIPTION:
XS GIS Cut Line= 3
      2310537.74     13195596.82      2311237.72     13194196.85
      2311487.73     13193396.82
#Sta/Elev= 30
  3446.5  154.03  3513.5  152.65  3558.3  150.15  3633.7  142.28  3795.8  136.22
    3849  132.97  3907.6  131.92  3991.5   126.3  4117.3  120.25  4287.8  118.38
  4326.9  119.04  4340.9  122.21  4349.3  122.56  4371.6  120.21  4475.1  120.85
  4645.6  116.06  4824.4  113.23  4869.2  110.68  4885.9  107.58  4891.5  108.16
  4908.3  105.81  4913.9   106.2  5003.1      97    5085   105.8  5130.6  106.35
  5189.8  104.17  5388.9  108.78  5692.7  125.66  5795.9  133.81  5849.9  136.78
#Mann= 4 ,-1 , 0
  3446.5     .16       0  4908.3     .07       0    5085     .16       0
  5795.9      .1       0
Bank Sta=4913.9,5085
XS Rating Curve= 0 ,0
Exp/Cntr=0.3,0.1

Type RM Length L Ch R = 1 ,24218   ,554,554,554
BEGIN DESCRIPTION:
PENITAS CREEK 44.0
END DESCRIPTION:
XS GIS Cut Line= 3
      2310887.71     13195446.87      2312187.72     13193896.85
      2312187.72     13193496.87
#Sta/Elev= 30
  2973.6  142.35  2995.1  141.06  3065.4  137.23  3165.5  130.14  3264.4  126.58
  3350.2  121.87  3442.6  118.13  3562.3  116.08  3633.9  113.02  3847.2  109.41
  3931.8  109.68  3960.4  108.34  4201.1  106.29  4223.2  105.03  4301.2  106.28
  4613.5  104.64  4670.3  105.43  4769.6  103.63  4776.1   103.8  4897.1  100.87
  5006.4   95.26  5036.6   97.72  5046.6   103.2  5056.6  105.46  5066.6   110.2
  5106.6  115.65  5190.2  120.72  5216.6  122.91  5286.6  125.98  5396.6   132.5
#Mann= 5 ,-1 , 0
  2973.6     .05       0  2995.1     .16       0  4769.6     .07       0
  5046.6     .16       0  5190.2      .1       0
Bank Sta=4776.1,5046.6
XS Rating Curve= 0 ,0
Exp/Cntr=0.3,0.1

Type RM Length L Ch R = 1 ,23664   ,605,605,605
BEGIN DESCRIPTION:
PENITAS CREEK 43.0
END DESCRIPTION:
XS GIS Cut Line= 3
      2310837.72     13195746.86      2312437.72     13194346.85
      2312937.68     13194096.88
#Sta/Elev= 30
  2870.5  154.58  2990.6  150.58  3033.3  147.35  3047.5  148.52  3147.2  141.95
  3260.1  138.69  3345.5  137.95  3607.5  127.44    3636  127.27  3791.6  120.18
  4011.8  113.13  4174.1  105.88  4451.3   102.7  4557.6  102.95  4599.3  104.63
  4677.6  105.25  4840.4  104.35  4883.1  105.87  4918.2  103.69  4940.1   101.9
  5004.7   93.71  5010.5   95.17  5077.6   99.09  5094.4      98  5122.3   99.63
  5228.5    99.2  5301.2  103.88  5340.3  106.33  5390.6  114.45  5555.5  127.17
#Mann= 4 ,-1 , 0
  2870.5     .16       0  4918.2     .07       0  5301.2     .16       0
  5555.5      .1       0
Bank Sta=4918.2,5301.2
XS Rating Curve= 0 ,0
Exp/Cntr=0.3,0.1

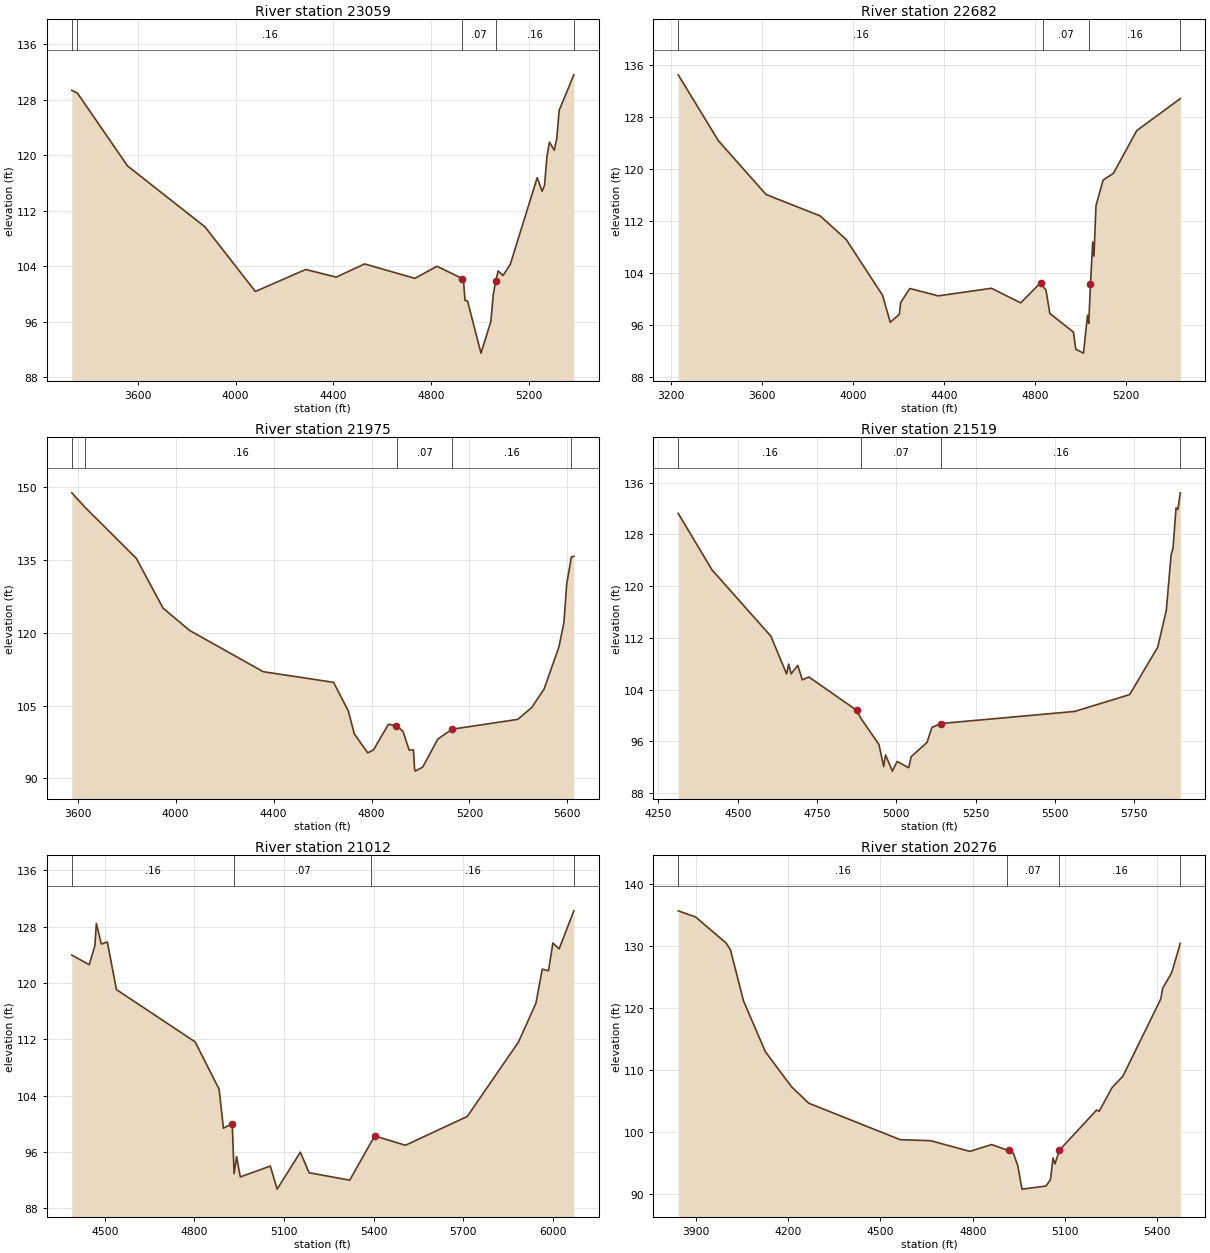
Type RM Length L Ch R = 1 ,23059   ,377,377,377
BEGIN DESCRIPTION:
PENITAS CREEK 42.0
END DESCRIPTION:
XS GIS Cut Line= 3
      2311437.69     13195296.87      2312887.72     13194496.85
      2313287.74     13194496.85
#Sta/Elev= 30
  3329.4  129.33  3352.3  128.94  3557.9  118.43    3875  109.66  4081.3  100.35
  4287.5  103.52  4412.5  102.42  4528.6  104.32  4734.2  102.24  4825.1  103.98
  4928.2  102.22  4933.9  101.75  4939.8   99.06    4950      99  5005.2   91.47
  5045.5   96.01  5055.5   99.88  5065.5  101.84  5075.5  103.31  5095.5  102.65
  5125.5  104.29  5235.5  116.75  5255.5  114.79  5265.5  115.64  5275.5  119.86
  5285.5  121.86  5305.5   120.7  5315.5  122.38  5325.5  126.46  5385.5  131.56
#Mann= 5 ,-1 , 0
  3329.4     .05       0  3352.3     .16       0  4928.2     .07       0
  5065.5     .16       0  5385.5     .08       0
Bank Sta=4928.2,5065.5
XS Rating Curve= 0 ,0
Exp/Cntr=0.3,0.1

Type RM Length L Ch R = 1 ,22682   ,707,707,707
BEGIN DESCRIPTION:
PENITAS CREEK 41.0
END DESCRIPTION:
XS GIS Cut Line= 4
      2311435.51     13195589.44      2311956.39     13195339.85
      2313280.18     13194721.36      2313410.37     13194612.87
#Sta/Elev= 30
  3231.6  134.43  3408.5  124.27    3618  116.01    3856  112.72  3970.3  109.09
  4130.2  100.51  4164.1   96.34  4204.3   97.59  4209.8   99.37    4250  101.55
  4375.3  100.41  4609.3  101.58  4737.8   99.33  4826.1  102.46  4837.2  101.82
  4848.8  101.32  4866.1    97.7  4969.6   94.84  4980.4   92.19    5014    91.6
  5031.6   97.41  5037.1   96.19  5044.7  102.22  5054.5  108.71    5060  106.52
  5068.9  114.29  5100.2  118.23  5145.9  119.29  5248.3  125.85  5439.8  130.77
#Mann= 4 ,-1 , 0
  3231.6     .16       0  4837.2     .07       0  5037.1     .16       0
  5439.8     .08       0
Bank Sta=4826.1,5044.7
XS Rating Curve= 0 ,0
Exp/Cntr=0.3,0.1

Type RM Length L Ch R = 1 ,21975   ,456,456,456
BEGIN DESCRIPTION:
PENITAS CREEK 40.0
END DESCRIPTION:
XS GIS Cut Line= 3
      2311287.71     13195896.86      2312587.72     13195396.85
      2313237.72     13195296.86
#Sta/Elev= 30
  3575.8  148.87  3629.4  145.92  3839.4  135.37  3948.7  125.09    4058  120.48
  4357.9     112  4645.1  109.81  4705.1  103.93  4729.7    99.2  4784.4   95.28
  4807.9   95.87    4869  101.16  4900.4  100.89  4904.4  100.86    4929   99.64
  4953.7   95.84  4971.2   95.88  4975.8   92.01  4978.5   91.51  5009.1   92.35
  5071.1   98.14  5129.3  100.15  5397.4  102.18  5454.3  104.62  5504.9  108.45
  5565.6  117.14  5585.8  122.14  5597.2  130.12  5616.2  135.65  5626.3  135.79
#Mann= 5 ,-1 , 0
  3575.8     .05       0  3629.4     .16       0  4904.4     .07       0
  5129.3     .16       0  5616.2      .1       0
Bank Sta=4900.4,5129.3
XS Rating Curve= 0 ,0
Exp/Cntr=0.3,0.1

Type RM Length L Ch R = 1 ,21519   ,507,507,507
BEGIN DESCRIPTION:
PENITAS CREEK 39.0
END DESCRIPTION:
XS GIS Cut Line= 3
      2311937.71     13196246.86      2312437.72     13195846.85
       2313237.7     13195346.87
#Sta/Elev= 30
  4312.3  131.25  4418.8  122.52  4604.5  112.27  4654.1  106.44  4660.5  107.95
  4668.5  106.45  4689.3  107.76  4703.7  105.52  4724.5  105.96    4875  100.82
  4888.6   99.56  4945.4   95.53  4960.3   92.11  4966.2   93.93  4987.8   91.41
  5002.7   92.91  5039.3   91.93    5047   93.64  5097.1   95.85  5112.4   98.16
  5141.3   98.77  5562.9  100.64  5736.2  103.24  5824.7  110.57  5851.8  116.24
  5867.1  124.92    5873  125.84  5882.5   132.1  5888.4  131.86    5896  134.43
#Mann= 4 ,-1 , 0
  4312.3     .16       0  4888.6     .07       0  5141.3     .16       0
    5896      .1       0
Bank Sta=4875,5141.3
XS Rating Curve= 0 ,0
Exp/Cntr=0.3,0.1

Type RM Length L Ch R = 1 ,21012   ,736,736,736
BEGIN DESCRIPTION:
PENITAS CREEK 38.0
END DESCRIPTION:
XS GIS Cut Line= 3
      2311970.14     13196394.92      2312421.56     13196321.13
      2313410.34     13195601.23
#Sta/Elev= 30
  4389.8  123.96  4448.1   122.6  4467.1  125.29  4472.1  128.46  4488.7  125.53
  4508.9  125.82  4539.3  119.06  4802.8  111.63  4882.9  104.91  4897.5   99.35
  4926.9  100.03  4933.1   92.91  4941.4   95.33  4953.9   92.44  5054.4   93.99
  5077.2   90.71  5154.8   95.96  5184.2   93.04  5320.2   91.98  5391.3   97.35
    5406   98.25  5506.4   96.94  5713.5  101.03    5885  111.61  5943.4  117.11
  5964.6  121.96  5985.5  121.73  6000.1  125.67    6021  124.84  6070.3  130.25
#Mann= 4 ,-1 , 0
  4389.8     .16       0  4933.1     .07       0  5391.3     .16       0
  6070.3     .05       0
Bank Sta=4926.9,5406
XS Rating Curve= 0 ,0
Exp/Cntr=0.3,0.1

Type RM Length L Ch R = 1 ,20276   ,583,583,583
BEGIN DESCRIPTION:
PENITAS CREEK 37.0
END DESCRIPTION:
XS GIS Cut Line= 3
      2312387.73     13196946.85      2313187.72     13196146.85
      2313487.74     13195746.83
#Sta/Elev= 30
  3843.1  135.68  3899.7  134.68  3998.7  130.47  4012.8  129.37  4055.2  121.13
  4125.9  112.94  4210.8  107.27  4267.4  104.59  4564.3    98.7  4663.3   98.54
  4790.6   96.81  4861.3   97.91  4911.2   97.04  4917.9      97    4932   96.48
  4946.2   94.55  4960.1   90.71    5038   91.21  5052.6   92.24  5060.9   95.76
  5067.2   94.78  5081.8   97.01  5202.6  103.49  5210.9  103.29  5252.6   107.1
    5288  108.96  5410.9  121.42  5417.2  123.18  5446.3  125.65  5474.5  130.44
#Mann= 4 ,-1 , 0
  3843.1     .16       0  4911.2     .07       0  5081.8     .16       0
  5474.5     .05       0
Bank Sta=4917.9,5081.8
XS Rating Curve= 0 ,0
Exp/Cntr=0.3,0.1

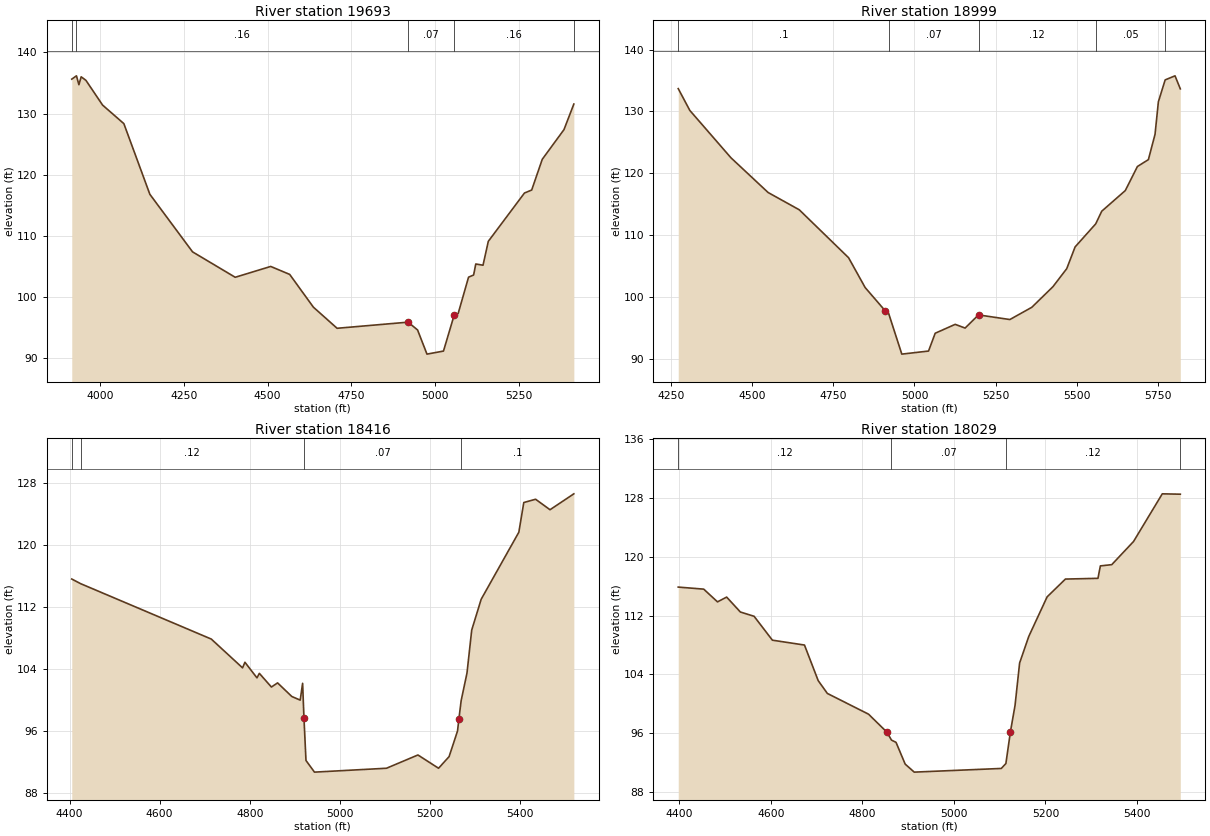
Type RM Length L Ch R = 1 ,19693   ,694,694,694
BEGIN DESCRIPTION:
PENITAS CREEK 36.0
END DESCRIPTION:
XS GIS Cut Line= 3
      2312787.69     13197246.88      2313587.72     13196496.85
      2313937.69     13196296.87
#Sta/Elev= 30
  3914.9  135.62  3928.9  136.16  3936.2  134.71    3943     136  3957.2  135.42
    4007  131.38  4070.5  128.35  4148.2  116.81  4275.7  107.41  4403.1  103.26
  4509.1  105.03  4565.8  103.73  4636.6   98.38  4707.4   94.93  4919.5   95.93
  4947.8   94.66  4975.9   90.71  5025.2   91.21  5056.9   97.03  5069.1   97.35
  5100.1  103.28  5115.2  103.63  5121.7  105.43  5143.3  105.23  5159.1  109.13
  5267.1  117.02  5288.7  117.51  5320.3  122.53  5385.1  127.37  5414.6  131.55
#Mann= 5 ,-1 , 0
  3914.9     .05       0  3928.9     .16       0  4919.5     .07       0
  5056.9     .16       0  5414.6     .05       0
Bank Sta=4919.5,5056.9
XS Rating Curve= 0 ,0
Exp/Cntr=0.3,0.1

Type RM Length L Ch R = 1 ,18999   ,583,583,583
BEGIN DESCRIPTION:
PENITAS CREEK 35.0
END DESCRIPTION:
XS GIS Cut Line= 3
      2313672.29      13197803.5      2313786.17     13197399.21
      2314042.24     13196300.99
#Sta/Elev= 30
  4271.7   133.7  4307.4  130.17  4434.4  122.49  4548.7  116.88  4644.8  114.08
  4796.8  106.32  4847.9  101.49  4909.8   97.72    4920   97.35  4960.9   90.71
  5043.3   91.21  5063.8   94.09  5125.4   95.53    5156   94.93  5197.3   97.06
    5294   96.31  5361.6   98.29  5426.8  101.63  5469.3  104.55  5495.1  108.07
  5558.6   111.8  5577.2  113.85  5649.8  117.19  5687.2  121.09    5721   122.2
  5741.5   126.3  5751.8  131.57  5772.7  135.11  5803.1  135.77  5819.4  133.66
#Mann= 5 ,-1 , 0
  4271.7      .1       0    4920     .07       0  5197.3     .12       0
  5558.6     .05       0  5772.7      .1       0
Bank Sta=4909.8,5197.3
XS Rating Curve= 0 ,0
Exp/Cntr=0.3,0.1

Type RM Length L Ch R = 1 ,18416   ,387,387,387
BEGIN DESCRIPTION:
PENITAS CREEK 34.0
END DESCRIPTION:
XS GIS Cut Line= 3
      2314258.82     13197655.43      2314332.84     13197382.13
       2314588.9     13196591.19
#Sta/Elev= 30
    4405   115.6  4424.7     115  4714.7  107.86  4784.1  104.15  4789.4  104.87
  4816.1  102.86  4821.4  103.44  4848.1  101.68  4861.9  102.21  4893.4  100.46
  4912.1   99.99  4917.4  102.16 4920.47   97.63  4924.9   92.21  4943.8   90.71
  5103.6   91.21  5173.4   92.92  5219.2   91.21  5242.6   92.71  5261.3   96.01
 5264.38   97.58  5269.4   99.94  5282.3  103.48  5292.8  109.02  5313.8  112.99
  5397.4  121.63  5408.4  125.46  5434.6  125.88  5466.6  124.53  5519.5  126.58
#Mann= 4 ,-1 , 0
    4405      .1       0  4424.7     .12       0 4920.47     .07       0
  5269.4      .1       0
Bank Sta=4920.47,5264.38
XS Rating Curve= 0 ,0
Exp/Cntr=0.3,0.1

Type RM Length L Ch R = 1 ,18029   ,623,623,623
BEGIN DESCRIPTION:
PENITAS CREEK 33.0
END DESCRIPTION:
XS GIS Cut Line= 3
      2314833.95     13197672.57      2314805.48     13196818.38
      2314720.29     13196591.19
#Sta/Elev= 30
  4397.6  115.87  4453.3  115.59  4483.4  113.86  4503.4  114.51  4533.4  112.48
  4563.4   111.9  4603.4  108.65  4673.5  107.99  4703.5  103.15  4723.5  101.41
  4813.5   98.59  4853.6   96.15  4863.6   95.07  4873.6   94.76  4893.6    91.8
  4913.4   90.71  5103.7   91.21  5113.7   91.88  5123.7   96.23  5133.7   99.78
  5143.7  105.55  5163.7  109.16  5203.8  114.54  5243.8  116.96  5314.9  117.06
  5320.2  118.75  5345.1  118.92  5392.7  122.07  5455.5  128.55  5494.9   128.5
#Mann= 4 ,-1 , 0
  4397.6     .12       0  4863.6     .07       0  5113.7     .12       0
  5494.9      .1       0
Bank Sta=4853.6,5123.7
XS Rating Curve= 0 ,0
Exp/Cntr=0.3,0.1