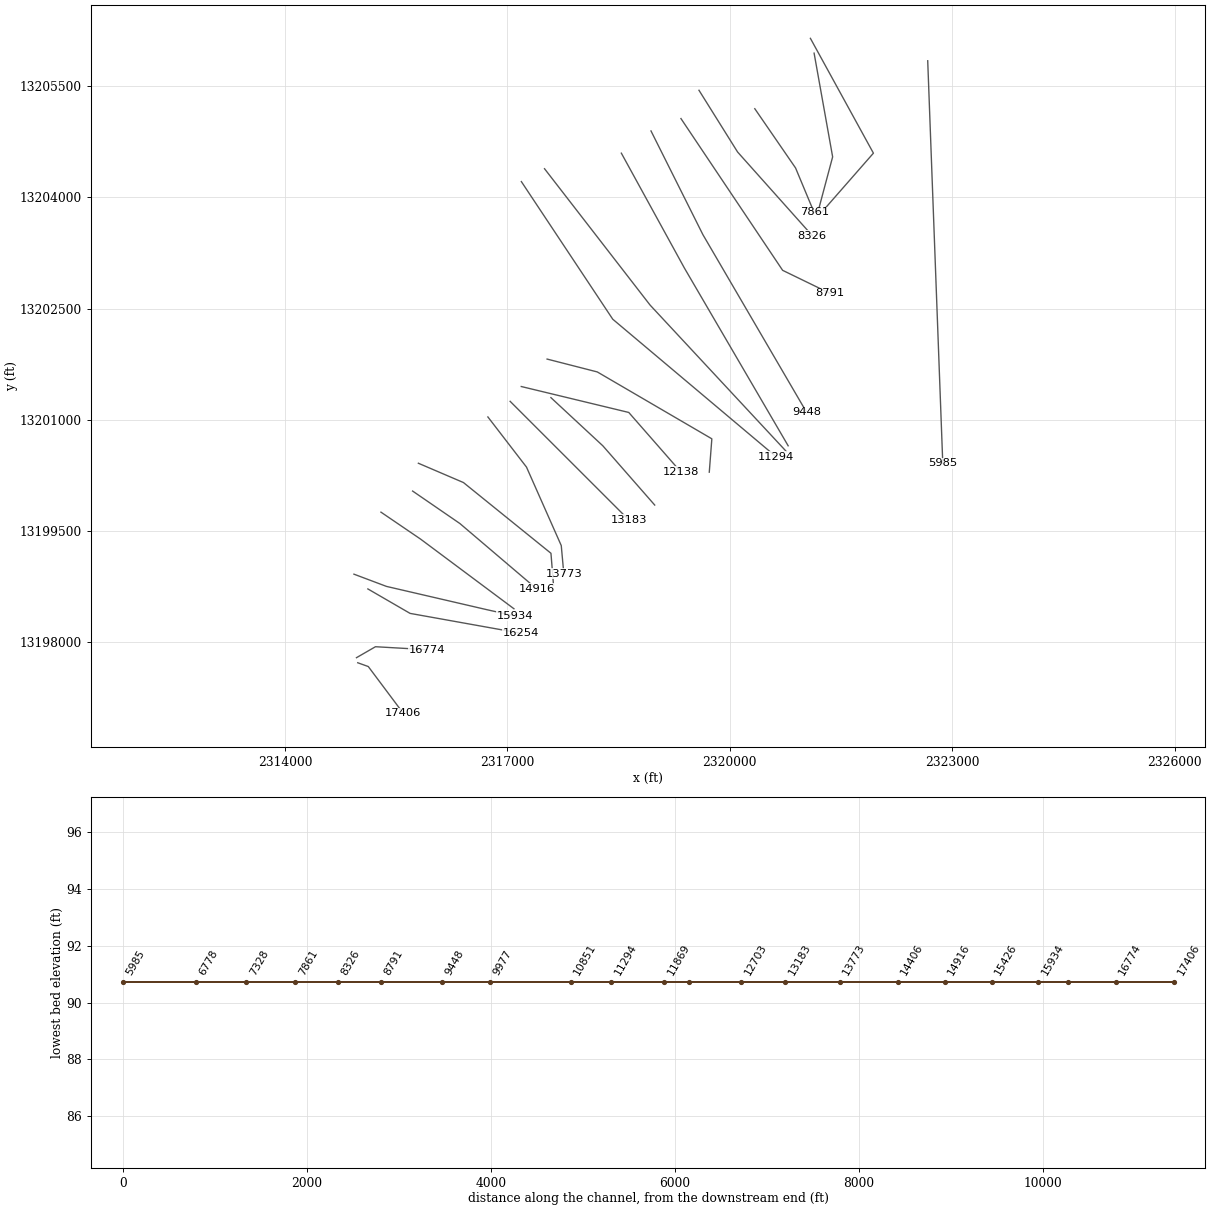
HEC-RAS study PENITAS CREEK.prj: PENITAS CREEK Base Level Engineering

--- PENITAS CREEK.g01 (geometry) --- (continued)

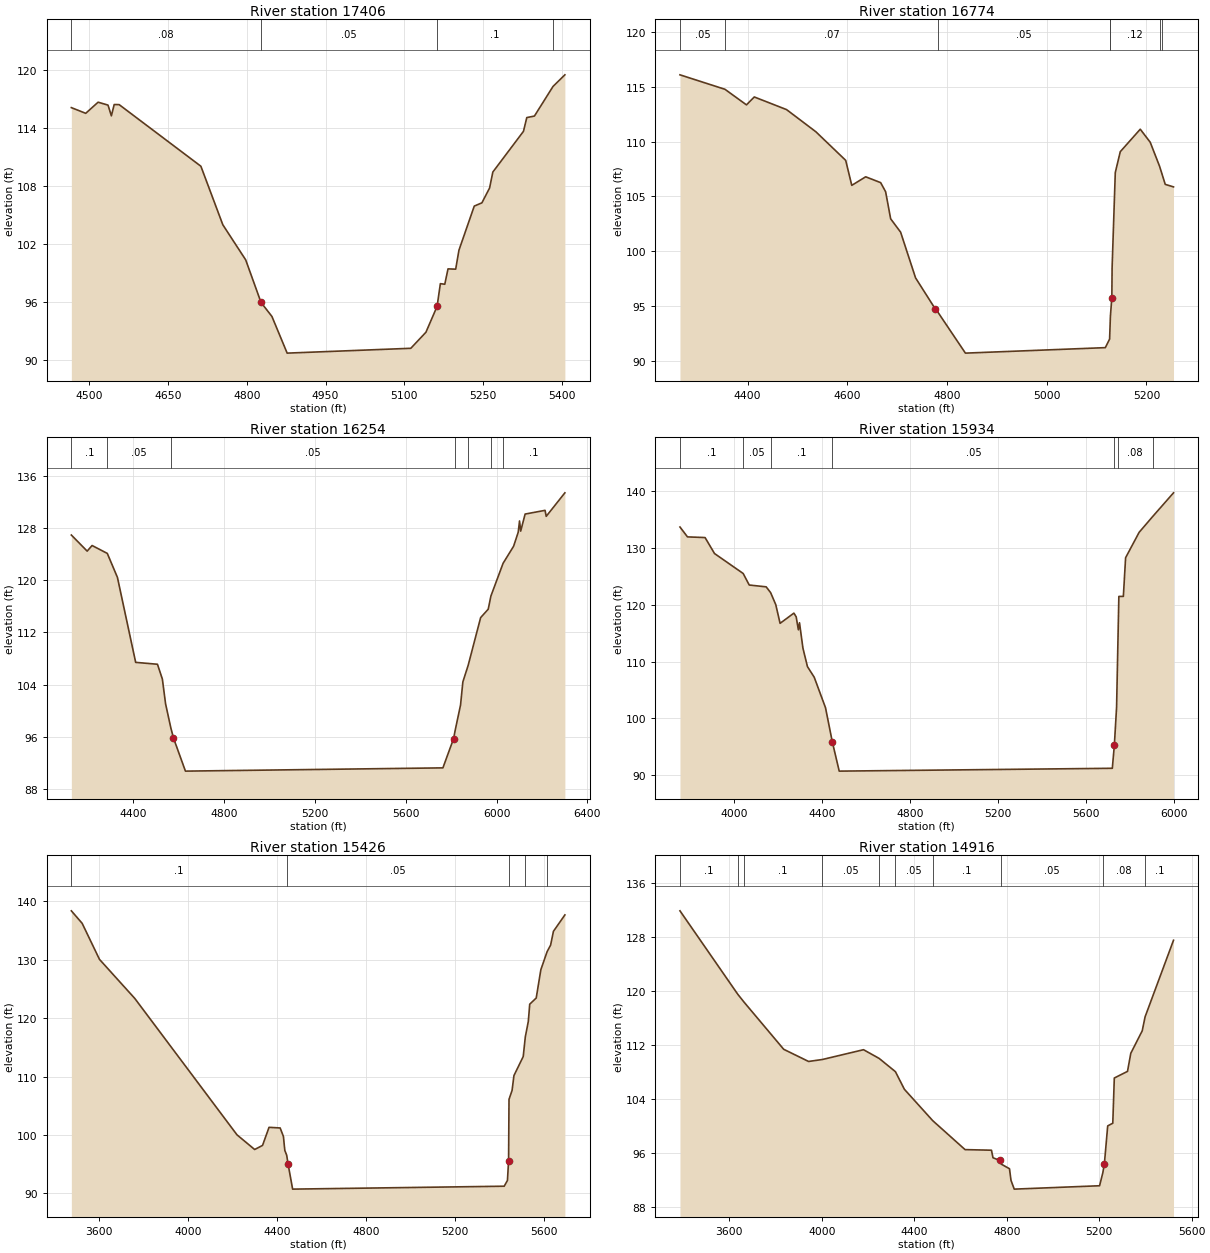
Type RM Length L Ch R = 1 ,17406   ,632,632,632
BEGIN DESCRIPTION:
PENITAS CREEK 32.0
END DESCRIPTION:
XS GIS Cut Line= 3
      2314981.98     13197718.11      2315124.37     13197666.85
      2315597.02     13197034.75
#Sta/Elev= 30
  4465.6  116.09    4493   115.5  4516.6  116.65  4535.5  116.35  4541.9  115.24
  4547.3  116.41  4556.7   116.4  4712.5  110.03  4754.3  103.98  4797.9  100.35
  4827.1   95.95  4847.9    94.5  4876.9   90.71  5112.6   91.21  5141.4   92.87
  5162.7   95.55  5168.9   97.89  5177.3   97.83  5183.5   99.42  5198.1   99.39
  5204.3  101.35  5233.5  105.91  5248.1  106.25  5262.7  107.78  5268.9  109.43
  5327.3  113.64  5333.6  115.06  5348.2  115.22  5383.6  118.28  5406.2  119.48
#Mann= 4 ,-1 , 0
  4465.6     .08       0  4827.1     .05       0  5162.7      .1       0
  5383.6      .1       0
Bank Sta=4827.1,5162.7
XS Rating Curve= 0 ,0
Exp/Cntr=0.3,0.1

Type RM Length L Ch R = 1 ,16774   ,520,520,520
BEGIN DESCRIPTION:
PENITAS CREEK 31.0
END DESCRIPTION:
XS GIS Cut Line= 3
      2314964.96     13197786.45      2315221.17     13197934.49
      2315914.32     13197894.72
#Sta/Elev= 30
  4264.2  116.09  4354.5  114.77  4397.6  113.35  4413.3  114.07    4478  112.92
  4536.8   110.9  4596.7  108.29  4608.9  106.01  4636.8  106.79  4666.8  106.26
  4676.8  105.43  4686.9  102.96  4706.9  101.74  4736.9   97.57  4776.3   94.75
  4781.3   94.47  4836.9   90.71  5117.6   91.21  5126.2   91.99  5127.8   94.07
 5130.68   95.78  5131.2   98.48  5137.6  107.18  5147.6  109.08  5187.7  111.13
  5207.7  109.94  5226.3  107.77  5230.4  107.18  5237.8   106.1  5254.4  105.87
#Mann= 7 ,-1 , 0
  4264.2     .05       0  4354.5     .07       0  4781.3     .05       0
  5126.2     .05       0  5127.8     .12       0  5226.3      .1       0
  5230.4     .05       0
Bank Sta=4776.3,5130.68
XS Rating Curve= 0 ,0
Exp/Cntr=0.3,0.1

Type RM Length L Ch R = 1 ,16254   ,320,320,320
BEGIN DESCRIPTION:
PENITAS CREEK 30.0
END DESCRIPTION:
XS GIS Cut Line= 3
      2315118.66     13198714.63      2315688.12     13198384.35
       2317180.1      13198116.7
#Sta/Elev= 30
  4126.9  126.96  4196.6  124.49  4218.3  125.35  4285.3  124.14  4329.9  120.46
  4410.3  107.41  4506.3  107.12  4527.9  104.84    4542  101.05  4565.1   97.36
  4576.7   95.81  4629.5   90.71  5763.7   91.21  5810.9   95.71  5817.4   96.91
  5841.4  100.87  5851.6  104.41    5875  106.96  5929.9  114.28  5963.3  115.57
  5975.2   117.6  6028.8  122.62  6075.1  125.24  6095.4  127.38  6101.2  129.12
  6106.3  127.56  6125.9  130.18  6213.7  130.75  6218.8  129.83    6301  133.44
#Mann= 7 ,-1 , 0
  4126.9      .1       0  4285.3     .05       0  4565.1     .05       0
  5817.4     .12       0    5875      .1       0  5975.2     .08       0
  6028.8      .1       0
Bank Sta=4576.7,5810.9
XS Rating Curve= 0 ,0
Exp/Cntr=0.3,0.1

Type RM Length L Ch R = 1 ,15934   ,508,508,508
BEGIN DESCRIPTION:
PENITAS CREEK 29.0
END DESCRIPTION:
XS GIS Cut Line= 4
      2314930.74     13198913.94      2315369.23     13198748.79
      2316718.81      13198435.6      2317100.36     13198350.18
#Sta/Elev= 30
  3754.7  133.71  3788.9  131.97  3868.9  131.85  3911.8  129.04  4042.3  125.52
  4069.7  123.49  4146.8  123.17  4167.3  122.14  4190.6  120.02  4210.1  116.74
    4273  118.54  4283.3  117.89  4293.3   115.6  4298.4  116.85  4314.1  112.36
  4334.6  109.12  4365.4  107.25  4416.8  101.87  4447.6   95.88  4479.1   90.71
  5721.4   91.21  5730.6   95.27  5740.8  101.98  5745.9  111.64  5751.1  121.48
  5771.6  121.49  5781.8   128.3  5843.3  132.77  5904.9  135.55  5999.7  139.73
#Mann= 7 ,-1 , 0
  3754.7      .1       0  4042.3     .05       0  4167.3      .1       0
  4447.6     .05       0  5730.6     .05       0  5745.9     .08       0
  5904.9      .1       0
Bank Sta=4447.6,5730.6
XS Rating Curve= 0 ,0
Exp/Cntr=0.3,0.1

Type RM Length L Ch R = 1 ,15426   ,510,510,510
BEGIN DESCRIPTION:
PENITAS CREEK 28.0
END DESCRIPTION:
XS GIS Cut Line= 3
      2315295.19     13199751.02      2315830.48     13199386.57
      2317088.94     13198446.99
#Sta/Elev= 30
  3474.1   138.4  3522.7  136.26  3600.6  130.08  3759.2  123.39  4218.7  100.01
    4298    97.5  4333.4    98.2  4362.6   101.3  4412.6  101.19  4427.2   99.74
  4433.5   97.34  4441.8   96.55    4448   95.05  4468.6   90.71  5419.5   91.21
  5434.1    92.2  5439.2   95.57  5441.1  106.09  5454.9  107.63  5463.3  110.17
    5505  113.43  5514.4   116.8  5527.9  119.46  5534.2   122.4  5563.4  123.46
  5584.2  128.31  5612.4  131.41    5628  132.52  5640.8  134.89  5692.2   137.7
#Mann= 5 ,-1 , 0
  3474.1      .1       0  4441.8     .05       0  5441.1     .05       0
  5514.4     .08       0  5612.4      .1       0
Bank Sta=4448,5439.2
XS Rating Curve= 0 ,0
Exp/Cntr=0.3,0.1

Type RM Length L Ch R = 1 ,14916   ,510,510,510
BEGIN DESCRIPTION:
PENITAS CREEK 27.0
END DESCRIPTION:
XS GIS Cut Line= 3
       2315722.3     13200035.73      2316360.06     13199597.27
      2317396.42     13198714.66
#Sta/Elev= 30
  3386.3  131.91  3636.6  119.55  3662.4  118.44  3835.1  111.41  3942.7  109.61
  4002.5   109.9  4180.4  111.35    4248  110.06  4318.4   108.1  4357.2  105.49
  4479.7  100.85  4619.7   96.56  4733.9   96.47  4740.5   95.36    4769   94.96
  4776.8    94.4  4811.9   93.73  4818.4   92.01  4832.5   90.71  5201.7   91.21
  5215.9   93.17  5222.5   94.48  5236.8  100.07  5258.8  100.47  5265.4  107.16
  5322.5  108.14  5336.7  110.82  5386.2  114.15  5398.5  116.21  5521.5  127.55
#Mann= 10 ,-1 , 0
  3386.3      .1       0  3636.6     .05       0  3662.4      .1       0
  4002.5     .05       0    4248      .1       0  4318.4     .05       0
  4479.7      .1       0  4776.8     .05       0  5215.9     .08       0
  5398.5      .1       0
Bank Sta=4769,5222.5
XS Rating Curve= 0 ,0
Exp/Cntr=0.3,0.1

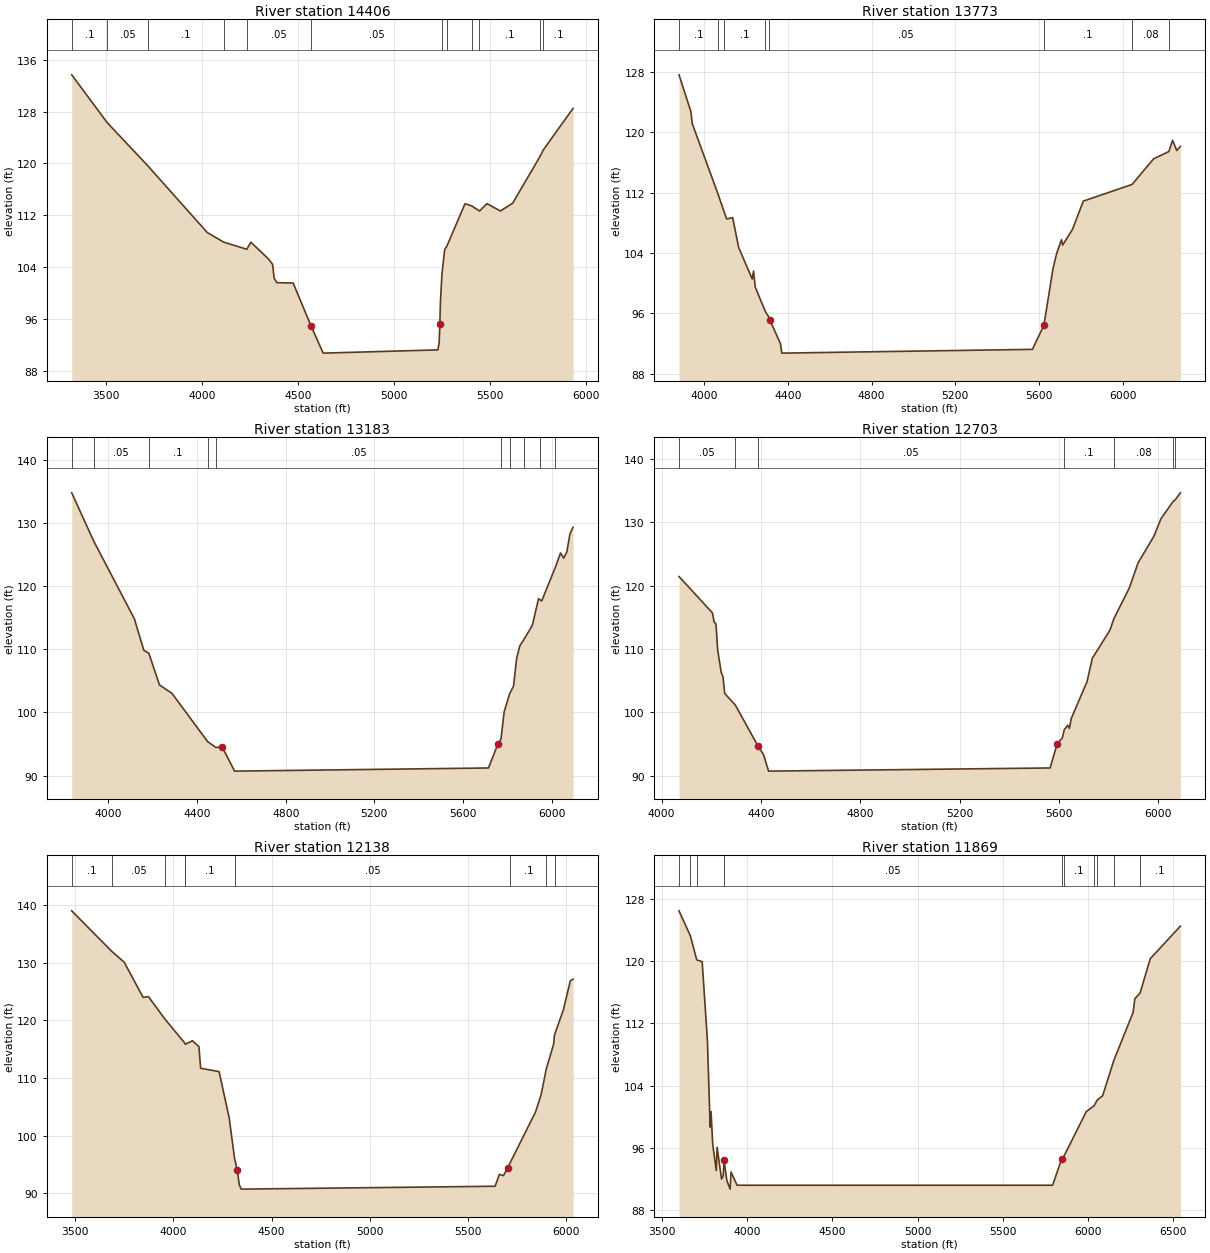
Type RM Length L Ch R = 1 ,14406   ,633,633,633
BEGIN DESCRIPTION:
PENITAS CREEK 26.0
END DESCRIPTION:
XS GIS Cut Line= 4
      2315800.02      13200411.1       2316407.7     13200150.67
      2317588.26     13199195.81      2317622.85      13198763.4
#Sta/Elev= 30
  3319.3  133.66  3504.5  126.27  3714.3  119.67  4025.9  109.32  4111.4  107.84
  4232.1  106.74  4252.9  107.84  4345.6  105.22  4366.5   104.4  4374.4  102.27
  4388.8  101.58  4473.6  101.53  4566.3   94.94    4630   90.71    5228   91.21
  5234.6   92.34 5238.07   95.13    5241   98.44    5249  102.85  5263.4   106.7
    5275  107.24  5369.5  113.77  5404.3  113.43  5444.8  112.64    5484  113.78
  5553.9  112.65  5618.1  113.86  5760.3  121.06  5778.2   122.1  5932.6  128.49
#Mann= 12 ,-1 , 0
  3319.3      .1       0  3504.5     .05       0  3714.3      .1       0
  4111.4     .08       0  4232.1     .05       0  4566.3     .05       0
    5249     .05       0    5275      .1       0  5404.3     .05       0
  5444.8      .1       0  5760.3     .08       0  5778.2      .1       0
Bank Sta=4566.3,5238.07
XS Rating Curve= 0 ,0
Exp/Cntr=0.3,0.1

Type RM Length L Ch R = 1 ,13773   ,590,590,590
BEGIN DESCRIPTION:
PENITAS CREEK 25.0
END DESCRIPTION:
XS GIS Cut Line= 4
      2316737.55      13201036.1       2317258.4       13200359.
      2317727.15     13199299.97       2317761.7     13198919.93
#Sta/Elev= 30
  3880.5   127.6  3937.3  122.72  3943.6  121.14  4065.9  111.86  4093.5  109.64
  4107.6   108.5  4136.6  108.66  4165.6   104.7    4230  100.54  4236.3  101.58
  4244.5   99.46  4293.1    96.2  4308.5   95.54  4315.1   95.05  4364.9   91.97
  4371.3   90.71  5568.2   91.21  5622.9    94.4  5666.6  101.95  5683.7  103.91
    5707  105.75  5712.4  105.03    5759  107.09  5811.1  110.86  6043.9  113.07
    6147  116.47  6219.6  117.43  6237.4  118.92  6257.5  117.56  6274.5  118.11
#Mann= 8 ,-1 , 0
  3880.5      .1       0  4065.9     .05       0  4093.5      .1       0
  4293.1     .16       0  4308.5     .05       0  5622.9      .1       0
  6043.9     .08       0  6219.6      .1       0
Bank Sta=4315.1,5622.9
XS Rating Curve= 0 ,0
Exp/Cntr=0.3,0.1

Type RM Length L Ch R = 1 ,13183   ,480,480,480
BEGIN DESCRIPTION:
PENITAS CREEK 24.0
END DESCRIPTION:
XS GIS Cut Line= 3
      2317037.76     13201246.82      2317837.72     13200446.85
      2318637.73     13199646.85
#Sta/Elev= 30
  3834.2  134.78  3932.8  127.18    4117  114.82  4159.4  109.85  4182.2  109.38
  4230.1  104.37  4286.7  103.02  4447.7   95.38  4484.7   94.46    4513   94.56
  4569.3   90.71  5715.1   91.21  5757.5   94.98  5771.6   95.78  5785.8  100.07
    5811     103  5828.2  104.17  5842.3  108.59  5856.5  110.55  5873.9  111.48
    5913  113.79  5941.3  118.02  5946.8  117.88  5955.5  117.67  6016.9  122.99
  6040.3  125.25  6054.5  124.44  6068.6   125.4  6082.8  128.26  6096.9  129.33
#Mann= 10 ,-1 , 0
  3834.2      .1       0  3932.8     .05       0  4182.2      .1       0
  4447.7     .16       0  4484.7     .05       0  5771.6     .16       0
    5811      .1       0  5873.9     .16       0  5946.8     .08       0
  6016.9      .1       0
Bank Sta=4513,5757.5
XS Rating Curve= 0 ,0
Exp/Cntr=0.3,0.1

Type RM Length L Ch R = 1 ,12703   ,565,565,565
BEGIN DESCRIPTION:
PENITAS CREEK 23.0
END DESCRIPTION:
XS GIS Cut Line= 3
      2317587.74     13201296.84      2318287.72     13200646.85
      2318987.69     13199846.89
#Sta/Elev= 30
  4070.3  121.42  4204.9  115.68  4211.7  114.25  4219.1  113.93  4225.9  109.83
  4240.1   106.3  4247.4  105.61  4254.2  102.97    4297  101.13  4388.6   94.64
  4410.1   93.36  4430.9   90.71  5564.2   91.21  5592.6   95.01  5613.5   95.95
  5621.1   97.25  5635.3   97.95    5642   97.47  5649.6   99.03  5713.2  104.87
    5734   108.5  5805.2  112.97  5821.1  114.78  5883.1  119.62  5918.2  123.56
  5982.2   127.8  6010.2  130.53  6060.8  133.34  6066.9  133.47  6088.5  134.63
#Mann= 7 ,-1 , 0
  4070.3     .05       0    4297      .1       0  4388.6     .05       0
  5621.1      .1       0  5821.1     .08       0  6060.8      .1       0
  6066.9     .05       0
Bank Sta=4388.6,5592.6
XS Rating Curve= 0 ,0
Exp/Cntr=0.3,0.1

Type RM Length L Ch R = 1 ,12138   ,269,269,269
BEGIN DESCRIPTION:
PENITAS CREEK 22.0
END DESCRIPTION:
XS GIS Cut Line= 3
      2317187.73     13201446.85      2318637.72     13201096.85
      2319337.75     13200296.82
#Sta/Elev= 30
  3481.8  138.97  3685.5  131.95  3749.3  130.06  3845.5  123.96  3872.7  124.09
  3957.4  120.17  4059.1  115.99  4060.7  115.82  4096.8  116.44  4129.9  115.42
  4138.7  111.67  4232.8  111.09  4284.2  103.05  4311.4   96.08  4325.3   94.03
  4335.6   91.46  4345.7   90.71  5639.2   91.21  5661.1   93.26    5682   93.05
  5703.8   94.43  5717.5   95.38  5845.2  104.08  5873.7  107.08  5899.8  111.52
  5937.3  115.83    5942  117.46  5986.6  121.74  6022.7  126.84  6036.5  127.13
#Mann= 9 ,-1 , 0
  3481.8      .1       0  3685.5     .05       0  3957.4      .1       0
  4059.1     .05       0  4060.7      .1       0  4311.4     .05       0
  5717.5      .1       0  5899.8     .05       0    5942      .1       0
Bank Sta=4325.3,5703.8
XS Rating Curve= 0 ,0
Exp/Cntr=0.3,0.1

Type RM Length L Ch R = 1 ,11869   ,575,575,575
BEGIN DESCRIPTION:
PENITAS CREEK 21.0
END DESCRIPTION:
XS GIS Cut Line= 4
      2317536.21     13201817.33      2318213.26     13201643.72
       2319758.4     13200740.95      2319723.76     13200290.67
#Sta/Elev= 30
    3601  126.44  3667.9  123.21  3704.8  120.14  3736.8  119.91  3767.7  109.75
  3783.6   98.67  3788.8  100.67  3798.7   96.46  3819.3    93.1  3824.4   96.08
  3850.3   92.01    3860   92.42  3865.2   94.39  3881.3   91.82  3900.6   90.71
    3906   92.91  3941.6   91.21  5791.9   91.21  5844.8   94.55  5858.9   94.96
  5989.4  100.66  6035.6  101.43  6054.2  102.16  6085.3   102.7  6152.1   107.3
  6264.1   113.4  6274.1  115.16    6305  115.88  6364.4  120.29  6541.1  124.47
#Mann= 10 ,-1 , 0
    3601      .1       0  3667.9     .08       0  3704.8      .1       0
  3865.2     .05       0  5844.8     .07       0  5858.9      .1       0
  6035.6     .08       0  6054.2     .16       0  6152.1     .08       0
    6305      .1       0
Bank Sta=3865.2,5844.8
XS Rating Curve= 0 ,0
Exp/Cntr=0.3,0.1

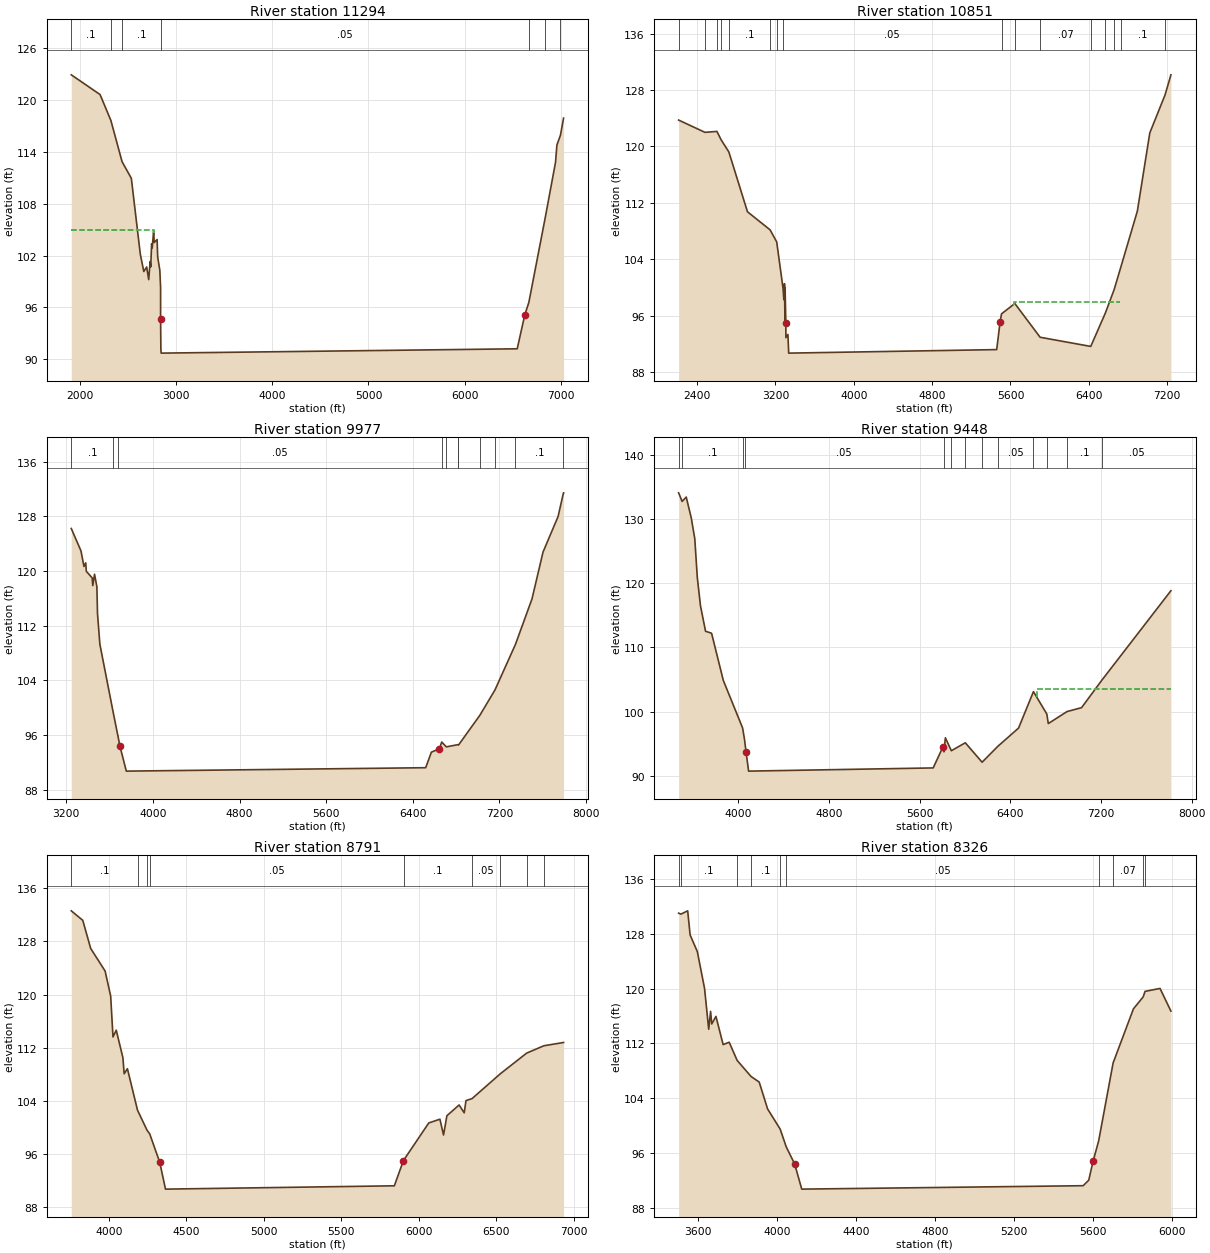
Type RM Length L Ch R = 1 ,11294   ,443,443,443
BEGIN DESCRIPTION:
PENITAS CREEK 20.0
END DESCRIPTION:
XS GIS Cut Line= 3
      2317188.98     13204213.13      2318421.59     13202355.53
      2320626.42     13200497.92
#Sta/Elev= 30
    1914   122.9  2212.9  120.62  2325.3  117.62  2441.2  112.86  2537.6  110.93
  2630.9  102.15    2667  100.15    2697  100.67  2718.1   99.21  2733.1   101.3
  2739.1  100.69  2748.2  103.36  2754.2  102.87  2769.2   104.8  2775.2   103.5
  2805.3  103.85  2811.3  101.83  2833.6  100.29  2841.4    98.3 2841.48   94.64
  2844.4   91.21  2847.2   90.71    6545   91.21    6623    95.1  6665.9   96.58
  6838.4  106.52  6942.9  112.79  6957.2  114.78  6993.7  115.91  7026.4  117.89
#Mann= 7 ,-1 , 0
    1914      .1       0  2325.3     .05       0  2441.2      .1       0
 2841.48     .05       0  6665.9     .05       0  6838.4      .1       0
  6993.7     .05       0
#XS Ineff= 2 , 0
       0 2769.95   104.9               0
Permanent Ineff=
       T       F
Bank Sta=2841.48,6623
XS Rating Curve= 0 ,0
Exp/Cntr=0.3,0.1

Type RM Length L Ch R = 1 ,10851   ,874,874,874
BEGIN DESCRIPTION:
PENITAS CREEK 19.0
END DESCRIPTION:
XS GIS Cut Line= 3
      2317501.43     13204386.81      2318925.06      13202546.5
      2320764.03     13200568.74
#Sta/Elev= 30
  2211.1  123.74  2479.8     122    2602  122.13  2645.1  120.94  2724.1  119.22
  2914.3  110.74  3145.3  108.18  3212.7  106.47  3277.4    99.9  3285.6   98.28
  3291.9  100.55 3297.55   95.01  3298.3     100 3305.91   94.92  3306.4    92.9
  3327.2   93.36  3335.2   90.71  5459.3   91.21  5494.4   95.19  5508.6   96.28
  5644.7   97.74  5902.5   92.96  6419.8   91.66  6568.6   96.38  6658.8   99.72
  6731.4  103.11  6895.7  110.84  7022.8  121.92  7178.1  127.29  7238.4  130.15
#Mann= 16 ,-1 , 0
  2211.1     .05       0  2479.8      .1       0    2602     .05       0
  2645.1     .08       0  2724.1      .1       0  3145.3     .08       0
  3212.7      .1       0  3277.4     .05       0  5508.6     .07       0
  5644.7     .12       0  5902.5     .07       0  6419.8     .05       0
  6568.6     .16       0  6658.8     .05       0  6731.4      .1       0
  7178.1     .05       0
#XS Ineff= 1 ,-1
 5631.09 6719.17   97.95
Permanent Ineff=
       T
Bank Sta=3305.91,5494.4
XS Rating Curve= 0 ,0
Exp/Cntr=0.3,0.1

Type RM Length L Ch R = 1 ,9977    ,529,529,529
BEGIN DESCRIPTION:
PENITAS CREEK 18.0
END DESCRIPTION:
XS GIS Cut Line= 3
      2318537.73     13204596.84      2319387.72     13203046.85
       2320787.7     13200646.89
#Sta/Elev= 30
    3246  126.21  3335.5  122.94  3363.1  120.66  3379.2  121.18  3384.9  119.94
  3438.9  118.99  3444.6  117.86  3460.7  119.52  3482.5  117.69  3488.2  113.76
    3510  109.28  3633.3   99.29  3679.4   95.65  3694.8   94.39  3754.3   90.71
  6518.8   91.21  6571.3   93.48  6645.7   93.99  6667.2   94.97  6709.2   94.26
    6815   94.58  6821.7   94.52    7020    98.9  7159.1   102.6  7347.7  109.25
  7500.7  115.91  7602.5  122.76  7741.4  127.96  7791.2  131.43  7792.2  131.43
#Mann= 11 ,-1 , 0
    3246      .1       0  3633.3     .16       0  3679.4     .05       0
  6667.2     .12       0  6709.2     .05       0    6815      .1       0
  6821.7     .05       0    7020      .1       0  7159.1     .16       0
  7347.7      .1       0  7791.2     .05       0
Bank Sta=3694.8,6645.7
XS Rating Curve= 0 ,0
Exp/Cntr=0.3,0.1

Type RM Length L Ch R = 1 ,9448    ,657,657,657
BEGIN DESCRIPTION:
PENITAS CREEK 17.0
END DESCRIPTION:
XS GIS Cut Line= 3
      2318937.72     13204896.85      2319637.72     13203496.85
       2321037.7     13201096.88
#Sta/Elev= 30
  3473.3  134.12  3504.2  132.78  3540.4  133.46  3585.1  130.18  3615.8  126.97
  3638.2   120.9  3666.2  116.49  3710.9  112.53    3764  112.22  3867.4  104.87
  4037.9   97.44  4054.7   95.64  4068.7   93.66  4090.8   90.71  5719.5   91.21
  5805.5   94.49  5814.2   93.72    5827   95.91  5879.7   93.89  6002.8   95.13
  6151.1    92.1  6289.8   94.58  6472.9   97.43  6604.1  103.11  6722.2   99.61
    6735   98.13  6900.3     100  7028.6  100.61  7209.6  104.94    7817  118.85
#Mann= 13 ,-1 , 0
  3473.3     .05       0  3504.2      .1       0  4037.9     .12       0
  4054.7     .05       0  5814.2     .07       0  5879.7     .12       0
  6002.8     .16       0  6151.1     .07       0  6289.8     .05       0
  6604.1      .1       0  6722.2     .05       0  6900.3      .1       0
  7209.6     .05       0
#XS Ineff= 2 , 0
       0                 6632.12       0  103.46
Permanent Ineff=
       F       T
Bank Sta=4068.7,5805.5
XS Rating Curve= 0 ,0
Exp/Cntr=0.3,0.1

Type RM Length L Ch R = 1 ,8791    ,465,465,465
BEGIN DESCRIPTION:
PENITAS CREEK 16.0
END DESCRIPTION:
XS GIS Cut Line= 3
      2319341.72     13205063.87      2320713.26     13203015.25
      2321354.19     13202703.45
#Sta/Elev= 30
  3757.6  132.61  3831.8  131.18  3882.8  126.95  3975.9  123.55  4011.9  119.78
  4026.9  113.62  4047.9  114.64    4091  110.48    4099  108.08    4120  108.84
  4185.2   102.6  4246.5   99.59  4264.1   99.02 4328.53   94.76  4365.9   90.71
  5843.2   91.21  5900.3   94.91  5908.1   95.23  6065.4  100.67  6137.5  101.24
  6160.8   98.86  6182.5  101.76  6261.3  103.38  6294.2   102.2  6305.8  104.04
    6345  104.34    6527  108.07  6697.5  111.19  6808.2  112.29  6935.7  112.79
#Mann= 9 ,-1 , 0
  3757.6      .1       0  4185.2     .05       0  4246.5      .1       0
  4264.1     .05       0  5908.1      .1       0    6345     .05       0
    6527      .1       0  6697.5     .05       0  6808.2      .1       0
Bank Sta=4328.53,5900.3
XS Rating Curve= 0 ,0
Exp/Cntr=0.3,0.1

Type RM Length L Ch R = 1 ,8326    ,465,465,465
BEGIN DESCRIPTION:
PENITAS CREEK 15.0
END DESCRIPTION:
XS GIS Cut Line= 3
      2319584.77     13205445.83      2320105.62     13204612.47
      2321112.53     13203484.04
#Sta/Elev= 30
  3500.9     131  3512.5  130.86  3546.9  131.34  3559.1  127.82  3595.7  125.39
  3632.2  120.03  3653.4  114.05  3662.9  116.66  3668.8  114.82    3690  115.93
  3726.5  111.81  3757.2  112.16  3797.5   109.5  3867.9  107.16  3909.3  106.34
  3951.8  102.42  4015.6   99.47  4046.1    96.9  4089.3   94.36  4124.9   90.71
  5551.2   91.21  5579.6   92.02  5601.3   94.76  5629.7   97.74  5703.1  109.14
  5806.2  117.04  5855.5  118.78  5864.9  119.58  5940.8  120.01    5996   116.7
#Mann= 10 ,-1 , 0
  3500.9     .05       0  3512.5      .1       0  3797.5     .16       0
  3867.9      .1       0  4015.6     .05       0  4046.1     .05       0
  5629.7     .05       0  5703.1     .07       0  5855.5     .08       0
  5864.9     .05       0
Bank Sta=4089.3,5601.3
XS Rating Curve= 0 ,0
Exp/Cntr=0.3,0.1

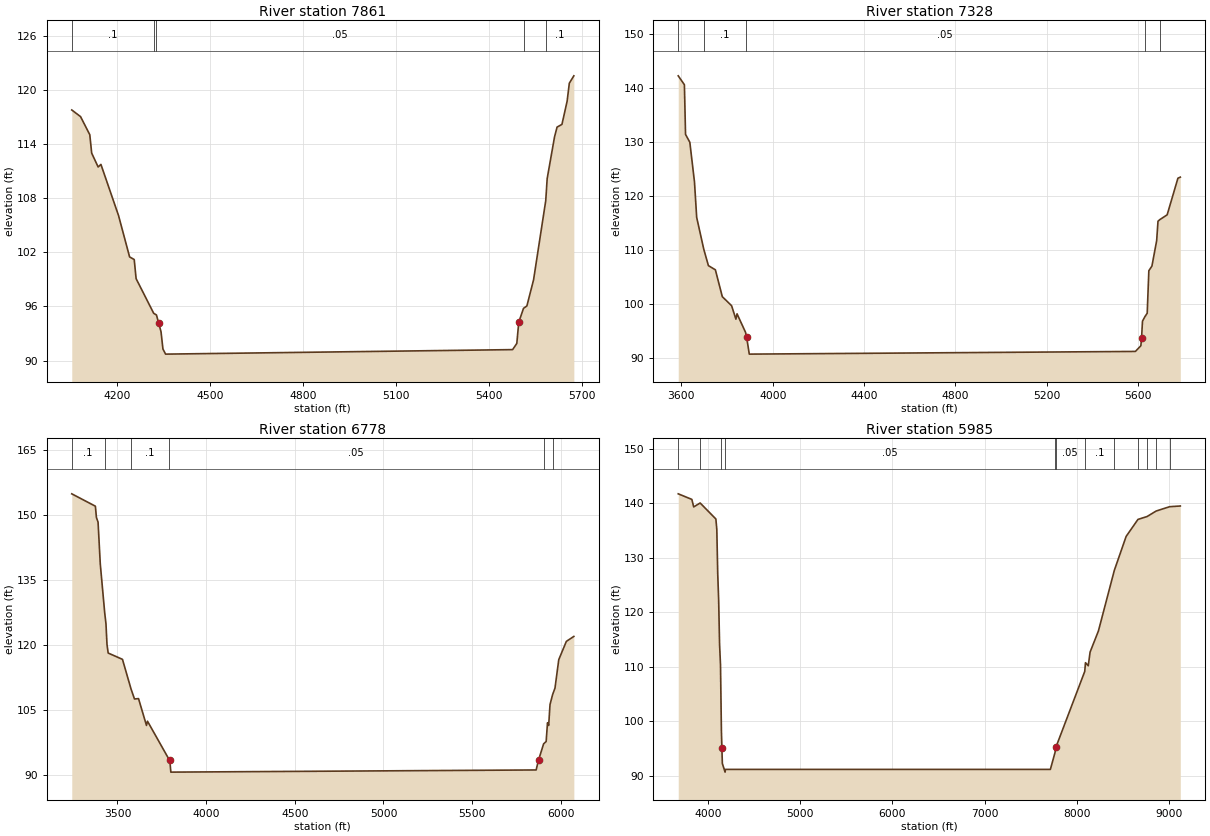
Type RM Length L Ch R = 1 ,7861    ,533,533,533
BEGIN DESCRIPTION:
PENITAS CREEK 14.0
END DESCRIPTION:
XS GIS Cut Line= 3
      2320337.72     13205196.86      2320887.72     13204396.85
      2321137.71     13203796.88
#Sta/Elev= 30
  4052.5  117.81  4080.9  117.07  4110.7  115.06  4116.8  113.02  4137.7  111.48
  4146.6  111.77  4203.4   106.1  4239.2   101.5  4254.1  101.21  4260.2   99.09
    4317   95.24  4325.8   95.06 4333.26   94.15  4340.7   93.18  4346.8   91.28
  4355.4   90.71  5475.6   91.21  5489.2    91.9 5495.44   94.25  5510.8   95.79
  5521.7   96.06  5543.3   98.96  5582.6  107.75  5587.2  110.19    5611  114.83
  5619.2  115.91  5634.9  116.21  5651.7   118.8  5658.7  120.78  5673.3   121.6
#Mann= 5 ,-1 , 0
  4052.5      .1       0    4317     .16       0  4325.8     .05       0
  5510.8     .07       0  5582.6      .1       0
Bank Sta=4333.26,5495.44
XS Rating Curve= 0 ,0
Exp/Cntr=0.3,0.1

Type RM Length L Ch R = 1 ,7328    ,550,550,550
BEGIN DESCRIPTION:
PENITAS CREEK 13.0
END DESCRIPTION:
XS GIS Cut Line= 3
      2321137.71     13205946.89      2321387.72     13204546.85
      2321187.72     13203796.84
#Sta/Elev= 30
  3586.3  142.29  3613.3  140.64  3618.3  131.43  3637.1  129.97  3657.4  122.65
  3667.1  116.05  3698.1  110.16  3718.4  107.11  3748.9  106.34  3779.3  101.36
    3820   99.68  3838.8   97.19  3843.8   98.18  3880.9   94.76  3885.8   93.85
  3897.4   90.71    5588   91.21    5612   92.26 5615.17   93.78  5619.1   96.82
  5629.4   97.63  5639.8    98.3  5646.9  106.16  5660.5  107.04  5681.2  111.75
    5687  115.34  5694.7  115.63  5727.1  116.53  5774.3  123.32  5784.7  123.51
#Mann= 5 ,-1 , 0
  3586.3     .08       0  3698.1      .1       0  3880.9     .05       0
  5629.4     .07       0  5694.7      .1       0
Bank Sta=3885.8,5615.17
XS Rating Curve= 0 ,0
Exp/Cntr=0.3,0.1

Type RM Length L Ch R = 1 ,6778    ,793,793,793
BEGIN DESCRIPTION:
PENITAS CREEK 12.0
END DESCRIPTION:
XS GIS Cut Line= 3
      2321087.72     13206146.86      2321937.72     13204596.85
      2321237.72     13203796.85
#Sta/Elev= 30
  3242.6  154.84  3375.8  151.99  3381.5   149.4  3390.9   148.3  3403.3  138.71
  3428.2  127.49  3435.5  124.86  3441.2  120.13  3447.9  118.15  3528.4   116.7
  3576.9  109.85  3596.2  107.57    3619  107.65  3663.9  101.47  3669.6  102.44
    3789   93.79 3795.37   93.45  3801.2   90.71  5860.8   91.21 5874.44    93.5
    5903   97.23  5917.3   97.77  5924.9  102.09  5931.5  101.47  5939.1  106.29
  5953.7  108.58  5967.1  110.07  5988.4  116.63  6031.2  120.84  6073.4  121.98
#Mann= 6 ,-1 , 0
  3242.6      .1       0  3428.2     .08       0  3576.9      .1       0
    3789     .05       0    5903     .07       0  5953.7      .1       0
Bank Sta=3795.37,5874.44
XS Rating Curve= 0 ,0
Exp/Cntr=0.3,0.1

Type RM Length L Ch R = 1 ,5985    ,0,0,0
BEGIN DESCRIPTION:
PENITAS CREEK 1.0
END DESCRIPTION:
XS GIS Cut Line= 2
      2322670.11     13205844.24      2322873.24     13200410.64
#Sta/Elev= 30
  3680.6   141.7  3828.1  140.68  3848.1   139.3  3917.9  140.02  4088.3  137.09
  4098.3   135.2  4108.3  127.08  4118.3   122.3  4128.3  114.08  4138.3  110.39
  4148.3   98.17  4153.5   95.12  4158.3    92.3  4188.1   90.71  4191.3   91.21
  7710.8   91.21  7760.7   94.27  7770.3   95.25    8083  109.16  8091.1  110.76
  8121.1   110.2  8141.1  112.71  8231.2  116.58  8403.2  127.66  8531.4   133.9
  8659.3  137.01    8758  137.54  8856.8  138.55  9001.9  139.34    9118  139.47
#Mann= 12 ,-1 , 0
  3680.6     .08       0  3917.9      .1       0  4148.3    .033       0
  4191.3     .05       0  7760.7     .08       0  7770.3     .05       0
    8083      .1       0  8403.2     .05       0  8659.3      .1       0
    8758     .05       0  8856.8      .1       0  9001.9     .05       0
Bank Sta=4153.5,7770.3
XS Rating Curve= 0 ,0
Exp/Cntr=0.3,0.1

Chan Stop Cuts=-1
Use User Specified Reach Order=0
Composite Channel Slope=5