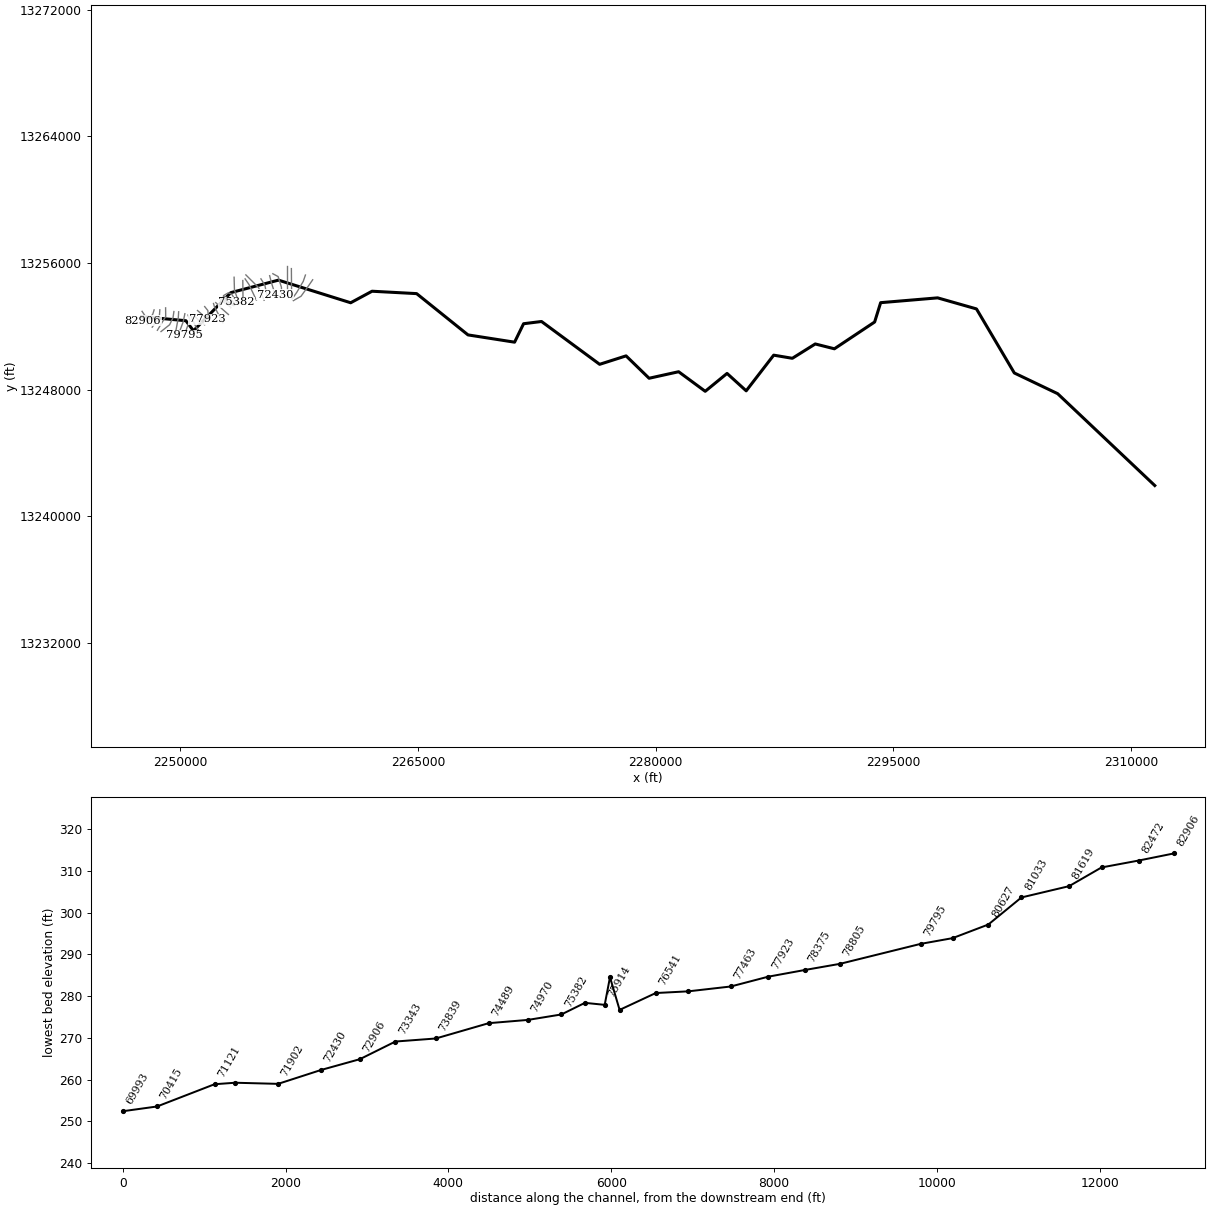
--- UNT001 IN PECR.prj (project) ---

Proj Title=UNT001 IN PECR Base Level Engineering
Current Plan=p01
Default Exp/Contr=0.3,0.1
English Units
Geom File=g01
Flow File=f01
Plan File=p01
Y Axis Title=Elevation
X Axis Title(PF)=Main Channel Distance
X Axis Title(XS)=Station
BEGIN DESCRIPTION:
UNT001 IN PECR
END DESCRIPTION:
DSS Export Rating Curves= 0
DSS Export Rating Curve Sorted= 0
DSS Export Volume Flow Curves= 0
DXF OffsetX= 0
DXF OffsetY= 0
DXF ScaleX= 1
DXF ScaleY= 10

--- UNT001 IN PECR.p01 (plan) ---

Plan Title=Multiple Run
Short Identifier=Multiple
Geom File=g01
Flow File=f01
Subcritical Flow
K Sum by GR= 0
Std Step Tol= 0.01
Critical Tol= 0.01
Num of Std Step Trials= 20
Max Error Tol= 0.3
Flow Tol Ratio= 0.001
Split Flow NTrial= 30
Split Flow Tol= 0.02
Split Flow Ratio= 0.02
Log Output Level= 0
Friction Slope Method= 1
Unsteady Friction Slope Method= 2
Unsteady Bridges Friction Slope Method= 1
Parabolic Critical Depth
Global Vel Dist=  1 , 1 , 1
Global Log Level= 0
CheckData=True
Encroach Param= -1, 0, 0, 0
BEGIN DESCRIPTION:
Multiple Run
END DESCRIPTION:

--- UNT001 IN PECR.f01 (steady flow) ---

Flow Title=Multiple
Program Version=4.10
Number of Profiles= 7
Profile Names=10-year,25-year,50-year,1pct_min,100-year,1pct_plu,500-year
River Rch & RM=UNT001 IN PECR,Reach-1         ,82906
     189     259     316     284     384     519     577
River Rch & RM=UNT001 IN PECR,Reach-1         ,82472
     286     400     494     449     607     821     932
River Rch & RM=UNT001 IN PECR,Reach-1         ,74970
     448     638     800     737     996    1347    1569
River Rch & RM=UNT001 IN PECR,Reach-1         ,71374
     641     926    1171    1087    1470    1988    2352
River Rch & RM=UNT001 IN PECR,Reach-1         ,63281
     914    1335    1702    1589    2149    2906    3482
River Rch & RM=UNT001 IN PECR,Reach-1         ,51909
    1183    1737    2223    2083    2816    3809    4590
River Rch & RM=UNT001 IN PECR,Reach-1         ,41391
    1310    1929    2472    2319    3136    4241    5125
River Rch & RM=UNT001 IN PECR,Reach-1         ,37147
    1435    2120    2722    2558    3459    4678    5672
River Rch & RM=UNT001 IN PECR,Reach-1         ,30727
    1584    2341    3009    2828    3824    5172    6269
River Rch & RM=UNT001 IN PECR,Reach-1         ,22264
    1822    2697    3468    3258    4406    5959    7208
River Rch & RM=UNT001 IN PECR,Reach-1         ,10257
    2082    3090    3980    3742    5060    6843    8285
River Rch & RM=UNT001 IN PECR,Reach-1         ,5544
    2071    3067    3945    3702    5007    6771    8170
Boundary for River Rch & Prof#=UNT001 IN PECR,Reach-1         , 1
Up Type= 0
Dn Type= 3
Dn Slope=0.0003
Boundary for River Rch & Prof#=UNT001 IN PECR,Reach-1         , 2
Up Type= 0
Dn Type= 3
Dn Slope=0.0003
Boundary for River Rch & Prof#=UNT001 IN PECR,Reach-1         , 3
Up Type= 0
Dn Type= 3
Dn Slope=0.0003
Boundary for River Rch & Prof#=UNT001 IN PECR,Reach-1         , 4
Up Type= 0
Dn Type= 3
Dn Slope=0.0003
Boundary for River Rch & Prof#=UNT001 IN PECR,Reach-1         , 5
Up Type= 0
Dn Type= 3
Dn Slope=0.0003
Boundary for River Rch & Prof#=UNT001 IN PECR,Reach-1         , 6
Up Type= 0
Dn Type= 3
Dn Slope=0.0003
Boundary for River Rch & Prof#=UNT001 IN PECR,Reach-1         , 7
Up Type= 0
Dn Type= 3
Dn Slope=0.0003
DSS Import GetInterval= 0
DSS Import GetPeak= 0
DSS Import FillOption= 0

--- UNT001 IN PECR.g01 (geometry) ---

Geom Title=Existing Conditions
Program Version=4.10

River Reach=UNT001 IN PECR  ,Reach-1
Reach XY= 30
      2247571.98     13252609.73      2250352.91     13252353.82
      2250832.17     13251719.13      2253187.72     13254126.86
      2256191.78     13254916.14      2260750.54     13253487.48
      2262097.86     13254215.63      2264911.88     13254064.84
      2268153.35      13251457.6      2271092.15     13250998.66
      2271659.56     13252163.88      2272791.89     13252304.86
      2276459.23      13249600.5      2278126.46     13250133.82
      2279579.14     13248720.28      2281442.52     13249132.64
      2283120.06     13247896.45       2284497.8     13249025.57
      2285705.86     13247926.93       2287441.6     13250178.87
      2288617.67      13249980.6      2290062.57     13250886.12
      2291270.65     13250581.19      2293809.66     13252272.11
      2294189.14     13253493.44       2297784.3     13253796.97
      2300235.52     13253099.22      2302623.75     13249053.39
      2305357.72     13247746.86      2311485.24     13241946.85

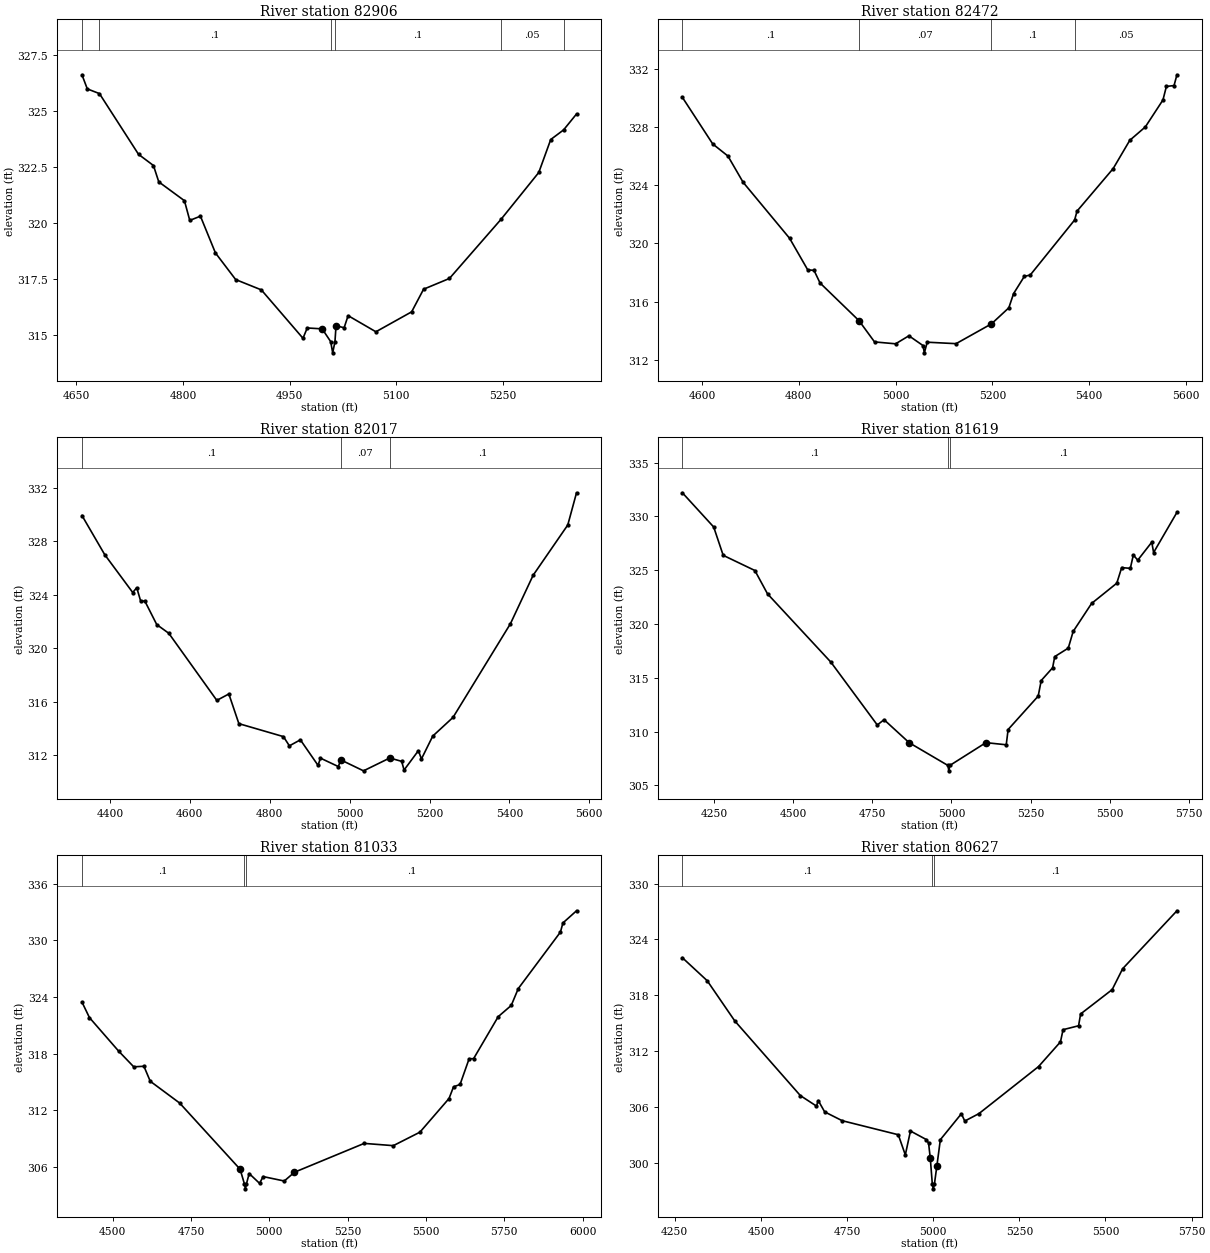
Type RM Length L Ch R = 1 ,82906   ,434,434,434
BEGIN DESCRIPTION:
UNT001 IN PECR 158.0
END DESCRIPTION:
XS GIS Cut Line= 3
      2247587.74     13252946.83      2247787.72     13252646.85
      2247637.74     13252346.89
#Sta/Elev= 30
  4657.7  326.61  4665.2  325.98  4682.3  325.77  4737.3  323.06  4758.3  322.56
  4765.8  321.83  4801.9  320.99  4809.4  320.11  4824.4   320.3  4845.5  318.66
    4874  317.47  4910.1  317.01  4968.7  314.85  4974.7  315.31  4995.7  315.27
  5007.7   314.7  5010.5   314.2  5013.7   314.7  5015.2  315.41  5026.6  315.32
  5032.2  315.86  5071.3  315.14  5121.6  316.03  5138.4  317.04  5174.8  317.52
  5247.4  320.16  5300.5  322.25  5317.3  323.72  5335.4  324.15  5353.6  324.86
#Mann= 6 ,-1 , 0
  4657.7     .05       0  4682.3      .1       0  5007.7     .07       0
  5013.7      .1       0  5247.4     .05       0  5335.4      .1       0
Bank Sta=4995.7,5015.2
XS Rating Curve= 0 ,0
Exp/Cntr=0.3,0.1

Type RM Length L Ch R = 1 ,82472   ,455,455,455
BEGIN DESCRIPTION:
UNT001 IN PECR 157.0
END DESCRIPTION:
XS GIS Cut Line= 3
      2248346.51     13253036.81      2248270.11     13252786.77
      2247902.86     13252121.56
#Sta/Elev= 30
  4559.7  330.03  4622.4  326.83  4653.8     326  4685.1   324.2  4781.2  320.35
  4818.5  318.19  4831.6  318.15  4843.9  317.29  4924.4   314.7  4956.5  313.24
    5000  313.11  5027.5  313.66  5056.6  312.99  5059.4  312.49  5065.3  313.22
  5124.9  313.12    5198  314.48  5233.8  315.58  5243.7  316.56  5265.9  317.74
    5278  317.83  5369.7  321.61  5374.7  322.22  5449.3  325.14  5483.6  327.08
  5515.7     328  5552.1  329.85  5559.2  330.78    5575  330.84    5581  331.58
#Mann= 4 ,-1 , 0
  4559.7      .1       0  4924.4     .07       0    5198      .1       0
  5369.7     .05       0
Bank Sta=4924.4,5198
XS Rating Curve= 0 ,0
Exp/Cntr=0.3,0.1

Type RM Length L Ch R = 1 ,82017   ,398,398,398
BEGIN DESCRIPTION:
UNT001 IN PECR 156.0
END DESCRIPTION:
XS GIS Cut Line= 3
      2248707.61      13253043.7      2248679.83     13252606.22
      2248228.46     13251946.52
#Sta/Elev= 30
  4330.2  329.94  4387.2  327.01  4457.3  324.18  4467.3  324.54  4477.3  323.52
  4487.4  323.55  4517.4  321.78  4547.5  321.13  4667.7  316.11  4697.8  316.59
  4722.9  314.37  4834.4   313.4  4849.3  312.71  4876.8  313.16    4921  311.25
  4927.1  311.79  4971.8  311.16  4977.9  311.66  5034.8  310.84  5100.5   311.8
  5130.3  311.55  5136.3   310.9  5172.2  312.35  5179.8  311.73  5208.1  313.44
  5258.9  314.84  5402.4  321.84  5459.3  325.47    5546  329.23  5567.9  331.64
#Mann= 3 , 0 , 0
  4330.2      .1       0  4977.9     .07       0  5100.5      .1       0
Bank Sta=4977.9,5100.5
XS Rating Curve= 0 ,0
Exp/Cntr=0.3,0.1

Type RM Length L Ch R = 1 ,81619   ,586,586,586
BEGIN DESCRIPTION:
UNT001 IN PECR 155.0
END DESCRIPTION:
XS GIS Cut Line= 3
      2249072.92     13253165.75      2249079.37     13252619.01
      2248553.22       13251751.
#Sta/Elev= 30
  4150.5  332.19  4249.4  329.01  4279.4  326.38  4379.4  324.97  4419.4   322.8
  4619.4  316.46    4766  310.62  4787.4  311.11  4866.9  308.97  4989.1  306.86
  4991.9  306.36  4995.1  306.86  5109.1  308.98  5173.2  308.78  5179.2   310.2
  5274.1   313.3  5283.7  314.75  5319.6  315.93  5326.4  316.97  5369.1  317.76
  5384.6  319.31  5442.8  321.91  5522.3  323.79  5537.8  325.24  5565.1  325.17
  5574.6  326.41  5588.5  325.93  5632.8   327.6  5638.6  326.64  5712.3  330.37
#Mann= 3 ,-1 , 0
  4150.5      .1       0  4989.1     .07       0  4995.1      .1       0
Bank Sta=4866.9,5109.1
XS Rating Curve= 0 ,0
Exp/Cntr=0.3,0.1

Type RM Length L Ch R = 1 ,81033   ,406,406,406
BEGIN DESCRIPTION:
UNT001 IN PECR 154.0
END DESCRIPTION:
XS GIS Cut Line= 4
      2249596.51     13252932.65      2249540.94     13252543.72
      2249325.67     13252099.27      2248783.97     13251668.69
#Sta/Elev= 30
  4401.8  323.46  4425.7  321.81  4518.8  318.26  4567.1  316.59  4599.6  316.65
  4619.8  315.06  4713.6  312.75  4906.6  305.73  4920.6  304.15  4923.4  303.65
  4926.6  304.15  4935.6  305.27  4968.8  304.23  4980.1  304.95  5047.6  304.48
  5080.1  305.41  5302.7  308.47  5395.7  308.23  5480.6  309.66  5573.5  313.23
  5587.9  314.47  5608.7  314.72  5637.6  317.44    5652  317.46  5730.5  321.91
  5772.1   323.1  5794.6  324.89  5929.1  330.88  5937.1  331.85  5980.5  333.14
#Mann= 3 ,-1 , 0
  4401.8      .1       0  4920.6     .07       0  4926.6      .1       0
Bank Sta=4906.6,5080.1
XS Rating Curve= 0 ,0
Exp/Cntr=0.3,0.1

Type RM Length L Ch R = 1 ,80627   ,440,440,440
BEGIN DESCRIPTION:
UNT001 IN PECR 153.0
END DESCRIPTION:
XS GIS Cut Line= 3
      2249895.11      13252918.7      2249874.28     13252536.77
      2249679.84     13251502.08
#Sta/Elev= 30
  4272.1  322.03  4344.1  319.56  4424.2  315.23  4614.5   307.2  4661.3  306.07
  4666.4  306.67    4685  305.45  4735.9   304.5  4898.7  302.99  4919.1  300.82
    4934  303.39  4980.1  302.47  4986.6  302.09  4991.6  300.45  4997.5  297.67
  5000.2  297.17  5003.5  297.67  5010.6  299.61  5020.8  302.46  5081.9  305.25
  5091.6  304.46  5132.7  305.26  5305.7  310.32  5369.4  312.98  5376.9  314.29
  5421.9  314.71  5427.8  315.98  5519.4   318.6  5549.9  320.85  5707.4  327.08
#Mann= 3 ,-1 , 0
  4272.1      .1       0  4997.5     .07       0  5003.5      .1       0
Bank Sta=4991.6,5010.6
XS Rating Curve= 0 ,0
Exp/Cntr=0.3,0.1

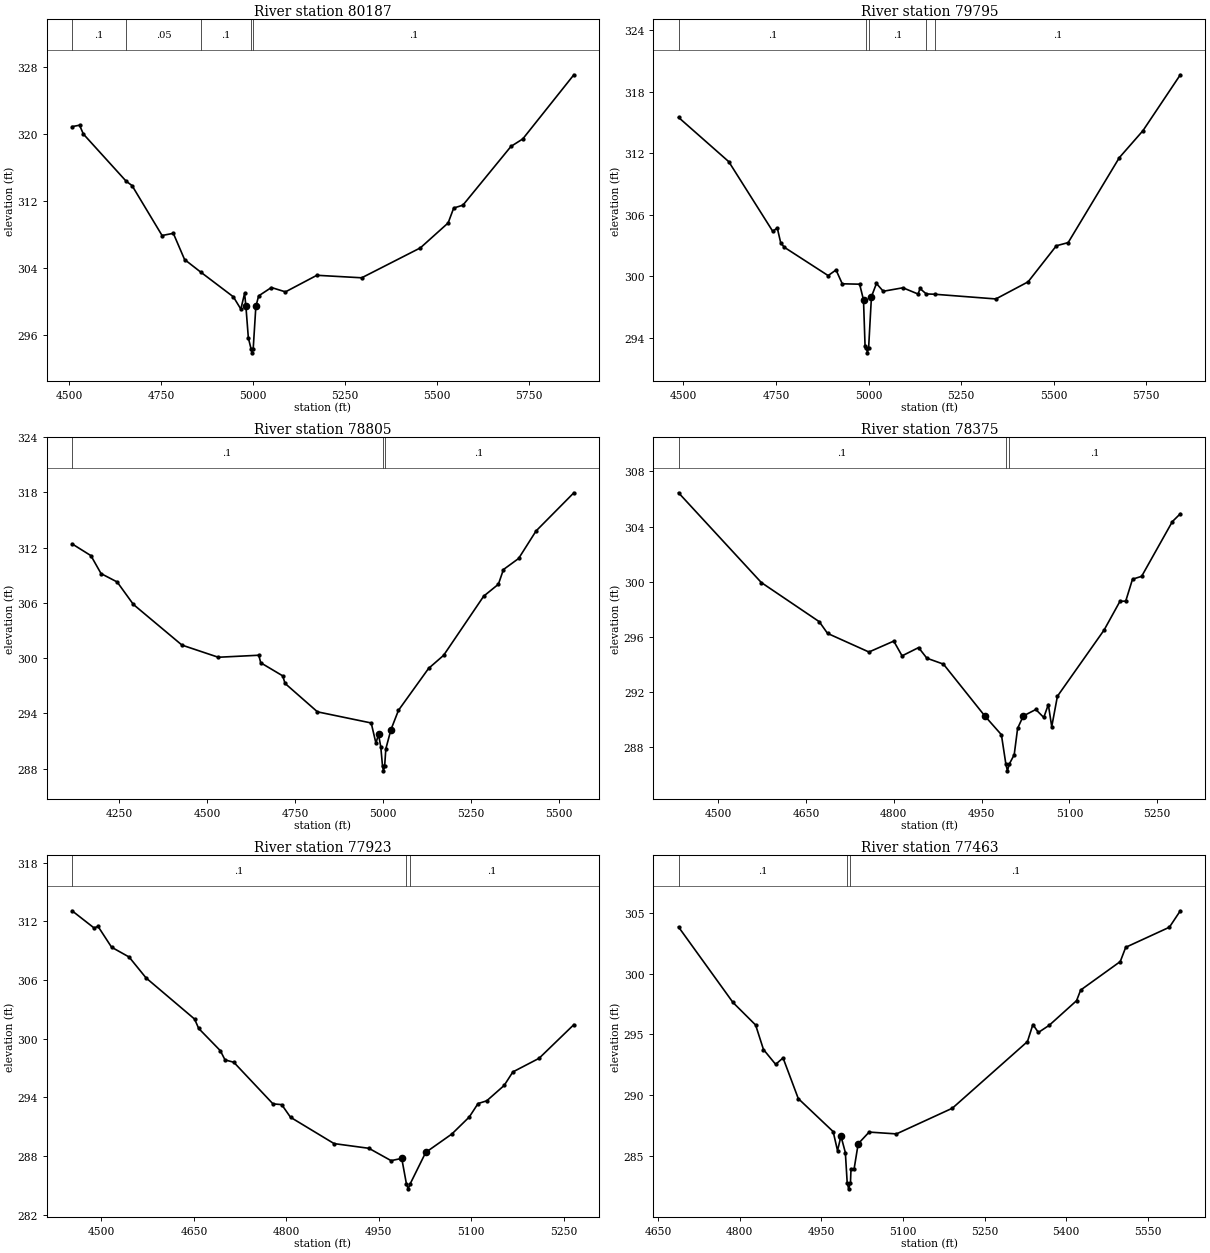
Type RM Length L Ch R = 1 ,80187   ,392,392,392
BEGIN DESCRIPTION:
UNT001 IN PECR 152.0
END DESCRIPTION:
XS GIS Cut Line= 3
      2250287.71     13252796.82      2250187.72     13252296.85
      2249887.71     13251496.83
#Sta/Elev= 30
  4507.4  320.91  4527.8  321.08    4538  320.03  4654.5  314.39  4670.5  313.87
  4752.1  307.91  4782.7  308.17  4813.3  305.04  4857.2  303.54  4945.9  300.59
  4966.3  299.12  4976.5  301.01    4980  299.46  4986.7  295.68  4993.9   294.4
  4996.6   293.9  4999.9   294.4  5007.1  299.44  5014.7   300.7  5049.3   301.7
  5087.6  301.18    5173  303.16  5294.9  302.86  5454.3  306.43  5529.9  309.41
    5545  311.19    5570  311.53  5700.8  318.55  5732.8  319.44  5871.7   327.1
#Mann= 5 ,-1 , 0
  4507.4      .1       0  4654.5     .05       0  4857.2      .1       0
  4993.9     .07       0  4999.9      .1       0
Bank Sta=4980,5007.1
XS Rating Curve= 0 ,0
Exp/Cntr=0.3,0.1

Type RM Length L Ch R = 1 ,79795   ,990,990,990
BEGIN DESCRIPTION:
UNT001 IN PECR 151.0
END DESCRIPTION:
XS GIS Cut Line= 3
      2250484.39     13252712.63      2250604.17      13252415.8
       2250255.2     13251441.81
#Sta/Elev= 30
    4487  315.51  4622.6  311.19  4741.2   304.4  4753.6  304.71  4762.8  303.28
  4772.3  302.84  4890.9  300.07  4912.2  300.62    4929  299.27  4975.9  299.23
 4986.36   297.7  4990.6  293.15  4994.2  293.03  4996.9  292.53  5000.2  293.03
  5007.8  298.01  5021.3   299.3  5039.7  298.54  5092.8  298.88  5133.7  298.27
    5139  298.81  5155.7  298.28  5178.2  298.25  5343.7  297.79  5430.7  299.46
    5507  302.98  5538.9  303.29    5677  311.58  5740.7  314.21  5841.7  319.67
#Mann= 5 ,-1 , 0
    4487      .1       0  4994.2     .07       0  5000.2      .1       0
  5155.7     .05       0  5178.2      .1       0
Bank Sta=4986.36,5007.8
XS Rating Curve= 0 ,0
Exp/Cntr=0.3,0.1

Type RM Length L Ch R = 1 ,78805   ,430,430,430
BEGIN DESCRIPTION:
UNT001 IN PECR 150.0
END DESCRIPTION:
XS GIS Cut Line= 3
      2250651.06      13252691.8      2250973.96      13251983.5
       2251380.2      13251478.3
#Sta/Elev= 30
  4115.2  312.41  4168.8  311.13  4197.6  309.18  4243.4  308.27  4289.5  305.83
  4427.7  301.41  4530.9  300.09  4646.1  300.31  4651.6  299.49  4714.1  298.07
  4720.7  297.25  4812.9  294.16  4965.7  292.95  4979.1  290.76  4986.5   291.7
  4992.9  290.37  4997.9  288.25  5000.6  287.75  5003.9  288.25  5007.3  290.14
  5021.7  292.21  5043.3  294.33  5128.9  298.88  5171.6   300.3  5285.6  306.73
  5327.3  308.02  5341.7  309.62  5384.8  310.82  5434.4  313.81  5541.9  317.96
#Mann= 3 ,-1 , 0
  4115.2      .1       0  4997.9     .07       0  5003.9      .1       0
Bank Sta=4986.5,5021.7
XS Rating Curve= 0 ,0
Exp/Cntr=0.3,0.1

Type RM Length L Ch R = 1 ,78375   ,452,452,452
BEGIN DESCRIPTION:
UNT001 IN PECR 149.0
END DESCRIPTION:
XS GIS Cut Line= 3
       2250887.7     13252646.87      2251287.72     13252246.85
      2251537.76     13252096.83
#Sta/Elev= 30
  4432.2  306.45  4573.6  299.94  4672.6   297.1  4686.8  296.25  4757.5   294.9
  4799.9  295.69  4814.1  294.62  4842.3  295.22  4856.5  294.45  4884.8  294.02
  4955.5  290.26  4983.8   288.9  4991.4  286.78  4994.1  286.28  4997.4  286.78
  5005.7  287.45  5011.5  289.36  5021.2  290.26  5042.6  290.73  5056.2  290.15
    5064  291.09  5069.8  289.48  5079.5  291.69  5159.2  296.49  5186.4  298.58
  5196.2  298.59  5207.8  300.18  5223.4  300.39  5275.9  304.36  5289.5  304.93
#Mann= 3 ,-1 , 0
  4432.2      .1       0  4991.4     .07       0  4997.4      .1       0
Bank Sta=4955.5,5021.2
XS Rating Curve= 0 ,0
Exp/Cntr=0.3,0.1

Type RM Length L Ch R = 1 ,77923   ,460,460,460
BEGIN DESCRIPTION:
UNT001 IN PECR 148.0
END DESCRIPTION:
XS GIS Cut Line= 3
      2251087.73     13252996.85      2251487.72     13252646.85
      2251687.69     13252446.88
#Sta/Elev= 30
  4452.3  313.07  4487.9  311.32  4494.5  311.47  4516.4  309.35  4544.8  308.35
  4572.4  306.21  4651.1  302.01  4657.8  301.05  4692.9  298.78  4700.5  297.84
  4714.7   297.6  4778.3  293.35  4792.5  293.27  4806.8  291.98  4877.5  289.29
    4934  288.81    4970  287.55  4987.3  287.78  4994.9  285.17  4997.7  284.67
  5000.9  285.17  5026.2  288.39  5068.6  290.27  5096.9  292.01  5111.1  293.38
  5125.2  293.66  5153.5  295.23  5167.6  296.61  5210.1     298  5266.6  301.44
#Mann= 3 ,-1 , 0
  4452.3      .1       0  4994.9     .07       0  5000.9      .1       0
Bank Sta=4987.3,5026.2
XS Rating Curve= 0 ,0
Exp/Cntr=0.3,0.1

Type RM Length L Ch R = 1 ,77463   ,521,521,521
BEGIN DESCRIPTION:
UNT001 IN PECR 147.0
END DESCRIPTION:
XS GIS Cut Line= 3
       2251537.7     13253246.89      2251737.72     13252996.85
      2251787.72     13252396.83
#Sta/Elev= 30
  4687.5  303.82  4787.6  297.62  4829.2  295.77  4843.6  293.76    4866  292.54
  4879.6  293.07  4907.6  289.73  4971.7  287.02  4979.7  285.46  4986.1  286.64
  4994.1   285.3  4997.5  282.82  5000.2  282.32  5003.5  282.82  5004.5  283.95
  5010.2  283.95  5017.7  286.02  5037.8  286.98    5088  286.83  5190.8  288.94
  5328.8  294.41  5338.8  295.81  5348.9  295.16  5368.9  295.75  5419.1  297.77
  5426.6  298.64  5499.4  300.98  5509.4  302.15  5589.7   303.8  5609.8  305.15
#Mann= 3 ,-1 , 0
  4687.5      .1       0  4997.5     .07       0  5003.5      .1       0
Bank Sta=4986.1,5017.7
XS Rating Curve= 0 ,0
Exp/Cntr=0.3,0.1

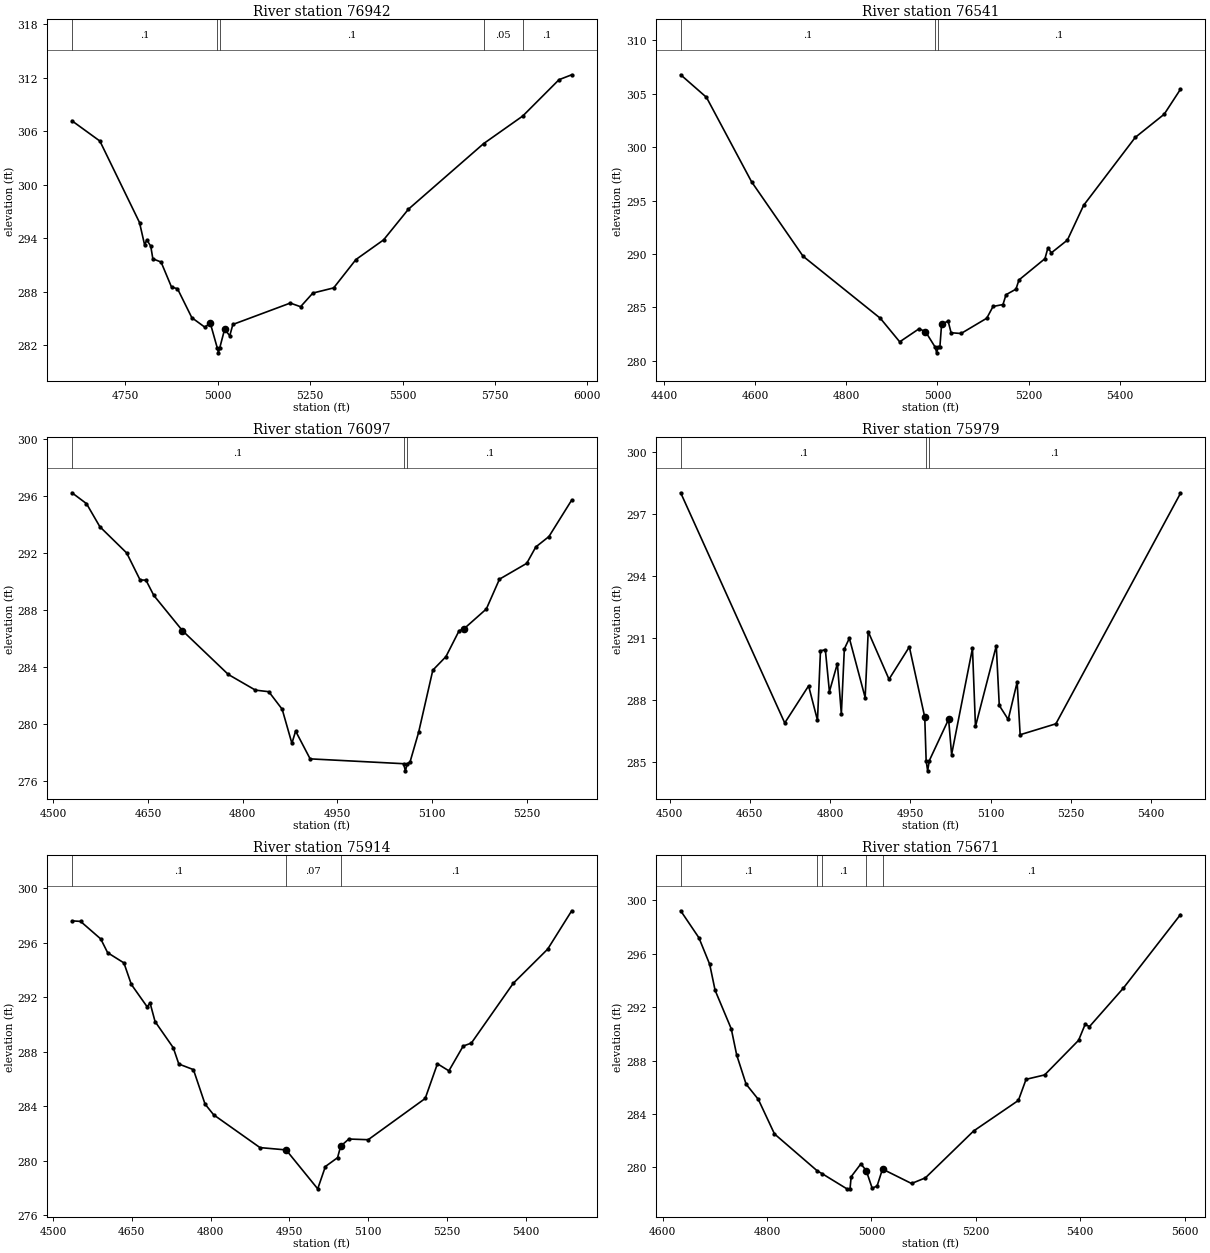
Type RM Length L Ch R = 1 ,76942   ,401,401,401
BEGIN DESCRIPTION:
UNT001 IN PECR 146.0
END DESCRIPTION:
XS GIS Cut Line= 3
       2252096.5     13253439.55      2252145.11     13253265.94
      2252679.84     13252224.26
#Sta/Elev= 30
  4606.3  307.17  4681.8   304.9  4788.9  295.77  4802.8  293.24  4808.5  293.82
  4819.3  293.12    4825   291.7  4847.2  291.34  4875.5  288.53  4891.6  288.35
  4930.4   285.1  4965.4  284.04  4980.3  284.49  4999.5  281.66  5002.3  281.16
  5005.5  281.66  5019.1  283.81  5032.9  283.07  5041.3  284.34  5196.6  286.74
  5224.4  286.33  5257.6  287.86  5313.9  288.44  5374.1  291.62  5448.8  293.82
  5516.2  297.27  5719.2  304.61  5825.2  307.71  5923.2  311.78  5957.5  312.33
#Mann= 5 ,-1 , 0
  4606.3      .1       0  4999.5     .07       0  5005.5      .1       0
  5719.2     .05       0  5825.2      .1       0
Bank Sta=4980.3,5019.1
XS Rating Curve= 0 ,0
Exp/Cntr=0.3,0.1

Type RM Length L Ch R = 1 ,76541   ,444,444,444
BEGIN DESCRIPTION:
UNT001 IN PECR 145.0
END DESCRIPTION:
XS GIS Cut Line= 3
      2252237.69     13253496.88      2252637.72     13253096.85
       2253037.7     13252746.88
#Sta/Elev= 30
  4436.3  306.77  4492.9  304.66  4591.9  296.76    4705  289.79  4874.7  283.98
  4917.2  281.78  4959.6     283  4973.7  282.74  4995.5  281.25  4998.2  280.75
  5001.5  281.25  5005.3  281.25  5009.1  283.41  5023.4  283.73    5030  282.63
  5051.9  282.56  5108.3  283.99  5122.1  285.09  5143.9  285.27  5150.6  286.19
  5172.4  286.71    5179  287.57    5236  289.56  5242.6  290.57  5250.2  290.11
  5285.3   291.3  5320.9  294.55  5434.3  300.91  5497.9  303.08  5533.5  305.41
#Mann= 3 ,-1 , 0
  4436.3      .1       0  4995.5     .07       0  5001.5      .1       0
Bank Sta=4973.7,5009.1
XS Rating Curve= 0 ,0
Exp/Cntr=0.3,0.1

Type RM Length L Ch R = 1 ,76097   ,118,118,118
BEGIN DESCRIPTION:
UNT001 IN PECR 144.0
END DESCRIPTION:
XS GIS Cut Line= 3
      2252537.71     13253646.86      2252937.72     13253396.85
      2253187.75     13253196.83
#Sta/Elev= 30
  4529.7  296.21  4552.7  295.45  4573.9  293.83  4616.4  291.99  4637.6   290.1
    4647  290.08  4659.4  289.01  4704.8  286.54  4777.4  283.47  4820.4  282.37
  4841.6  282.26  4862.8  281.03  4878.2  278.64  4884.1   279.5  4907.1  277.55
  5055.2  277.21    5058  276.71  5061.2  277.21  5065.4  277.33    5079  279.41
  5101.5  283.77  5122.3  284.72  5143.1  286.53  5151.1  286.68  5186.3  288.06
  5207.1  290.15  5250.3  291.26  5264.7  292.41  5285.5  293.14  5321.6   295.7
#Mann= 3 ,-1 , 0
  4529.7      .1       0  5055.2     .07       0  5061.2      .1       0
Bank Sta=4704.8,5151.1
XS Rating Curve= 0 ,0
Exp/Cntr=0.3,0.1

Type RM Length L Ch R = 1 ,75979   ,65,65,65
BEGIN DESCRIPTION:
Mapping XS 1456f8a8
END DESCRIPTION:
XS GIS Cut Line= 2
      2252536.43     13253728.31      2253369.82     13253306.41
#Sta/Elev= 30
  4520.7  298.03  4715.2  286.87  4759.8  288.67  4776.4     287    4782  290.37
  4791.1  290.42  4798.7  288.39  4813.6  289.75    4821   287.3  4826.6  290.46
    4836  290.98  4865.5   288.1  4871.2   291.3  4910.1  288.99  4948.1  290.56
  4976.9  287.15  4979.5  285.05  4982.3  284.55  4985.5  285.05  5021.5  287.05
  5027.1  285.34  5066.1  290.49  5071.7   286.7  5110.6  290.61  5116.2  287.72
  5132.9  287.04  5149.6  288.85  5155.2   286.3    5222  286.83  5454.8     298
#Mann= 3 ,-1 , 0
  4520.7      .1       0  4979.5     .07       0  4985.5      .1       0
Bank Sta=4976.9,5021.5
XS Rating Curve= 0 ,0
Exp/Cntr=0.3,0.1

Type RM Length L Ch R = 1 ,75914   ,243,243,243
BEGIN DESCRIPTION:
Mapping XS 9f63cb46
END DESCRIPTION:
XS GIS Cut Line= 3
      2252567.65     13253789.18      2252996.76     13253563.78
      2253396.97      13253323.9
#Sta/Elev= 30
  4536.2  297.61  4552.6  297.57    4591  296.28  4604.1  295.27  4635.1  294.52
  4649.2  292.94  4679.2   291.3  4684.9  291.57  4694.4  290.21    4729  288.29
  4739.6  287.09  4767.4  286.68  4789.5  284.15  4805.9  283.36  4894.1  280.95
  4943.8  280.78    5004  277.92  5018.6  279.56  5041.8  280.21  5047.6  281.05
  5063.2  281.58  5100.1  281.53  5208.6  284.56  5231.9  287.11  5253.7  286.59
  5280.9  288.41  5296.5  288.63  5376.2  293.02  5441.7  295.53  5487.5  298.35
#Mann= 3 , 0 , 0
  4536.2      .1       0  4943.8     .07       0  5047.6      .1       0
Bank Sta=4943.8,5047.6
XS Rating Curve= 0 ,0
Exp/Cntr=0.3,0.1

Type RM Length L Ch R = 1 ,75671   ,289,289,289
BEGIN DESCRIPTION:
Mapping XS ad278f49
END DESCRIPTION:
XS GIS Cut Line= 3
        2252724.     13253884.54      2253177.08     13253764.75
      2253463.56     13253368.89
#Sta/Elev= 30
  4634.5  299.22  4669.4   297.2  4690.1  295.21  4700.4  293.27  4731.4  290.38
  4741.8  288.42  4759.8  286.24  4783.2   285.1  4814.2  282.51  4896.3  279.74
  4905.7  279.53  4952.9   278.4  4958.9   278.4  4961.1  279.31  4979.7  280.27
    4990  279.76  5001.3  278.45  5010.7  278.61  5021.1  279.88  5076.7   278.8
  5103.2  279.22  5195.6  282.73  5281.4  285.02  5296.1   286.6  5331.7  286.93
  5396.7  289.52  5409.2  290.71  5417.6  290.55  5482.5  293.43  5591.8  298.93
#Mann= 5 ,-1 , 0
  4634.5      .1       0  4896.3     .05       0  4905.7      .1       0
    4990     .05       0  5021.1      .1       0
Bank Sta=4990,5021.1
XS Rating Curve= 0 ,0
Exp/Cntr=0.3,0.1

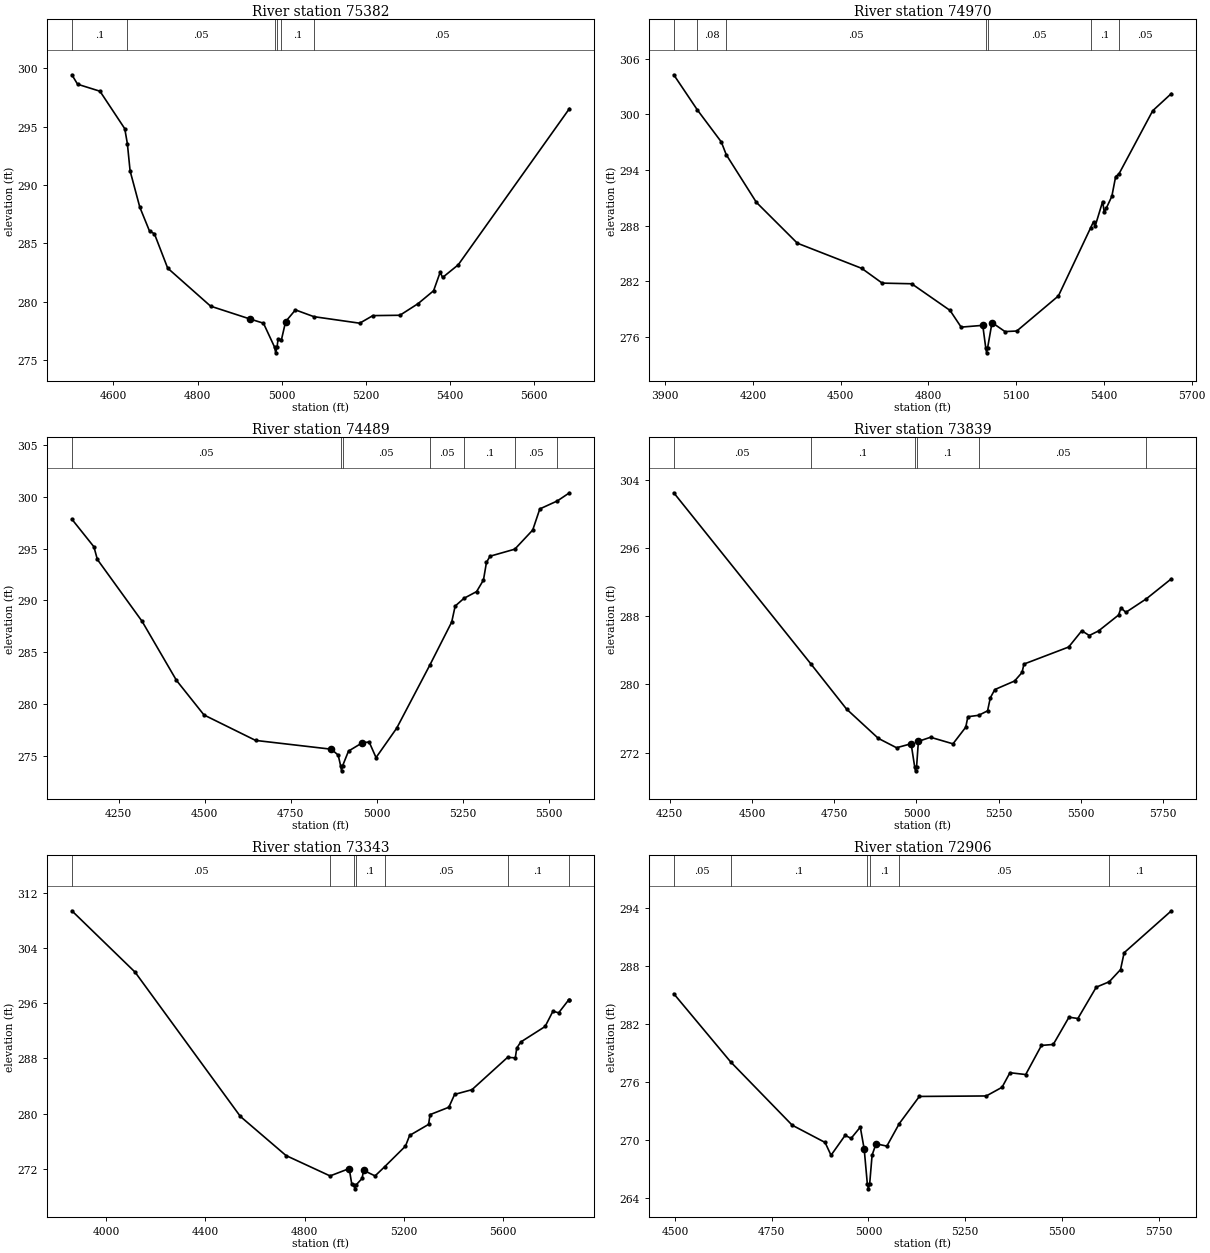
Type RM Length L Ch R = 1 ,75382   ,412,412,412
BEGIN DESCRIPTION:
UNT001 IN PECR 143.0
END DESCRIPTION:
XS GIS Cut Line= 4
      2252737.76     13253946.88      2253036.46     13254118.92
        2253250.     13254025.17      2253557.27     13253504.37
#Sta/Elev= 30
  4501.3  299.45  4514.9  298.64  4568.1  298.04    4627  294.83  4633.2  293.55
  4639.7  291.21  4662.8   288.1  4685.9  286.05  4697.4  285.83    4729  282.88
    4831  279.62  4923.8  278.53  4956.6  278.16  4982.9  276.12  4985.7  275.62
  4988.9  276.12  4991.4   276.8  4999.4  276.75  5009.3   278.3  5032.6   279.3
  5076.5  278.72  5185.3  278.16  5216.6  278.81  5280.9  278.84  5323.8  279.83
  5360.9  280.94  5376.5  282.52  5382.4  282.08  5419.4  283.16  5683.9  296.56
#Mann= 6 ,-1 , 0
  4501.3      .1       0  4633.2     .05       0  4982.9     .07       0
  4988.9     .05       0  4999.4      .1       0  5076.5     .05       0
Bank Sta=4923.8,5009.3
XS Rating Curve= 0 ,0
Exp/Cntr=0.3,0.1

Type RM Length L Ch R = 1 ,74970   ,481,481,481
BEGIN DESCRIPTION:
UNT001 IN PECR 142.0
END DESCRIPTION:
XS GIS Cut Line= 3
      2253395.11     13255099.29      2253415.94     13254300.66
      2253707.61     13253446.49
#Sta/Elev= 30
  3929.2  304.26    4010  300.47  4091.7  297.03  4108.7  295.65  4211.7  290.52
  4351.8  286.12  4571.9  283.41  4641.9  281.82  4742.7  281.75  4873.8  278.88
  4911.8  277.08  4985.7  277.27  4996.1  274.81  4998.9  274.31  5002.1  274.81
  5017.4  277.57  5061.8   276.6    5102  276.66  5244.4  280.44  5354.3  287.76
  5364.4  288.43  5369.7  287.92  5395.7  290.61    5401  289.47  5408.4  289.91
  5427.1  291.17  5440.1  293.29  5451.9  293.61  5566.9  300.39  5630.7  302.24
#Mann= 7 ,-1 , 0
  3929.2     .05       0    4010     .08       0  4108.7     .05       0
  4996.1    .035       0  5002.1     .05       0  5354.3      .1       0
  5451.9     .05       0
Bank Sta=4985.7,5017.4
XS Rating Curve= 0 ,0
Exp/Cntr=0.3,0.1

Type RM Length L Ch R = 1 ,74489   ,650,650,650
BEGIN DESCRIPTION:
UNT001 IN PECR 141.0
END DESCRIPTION:
XS GIS Cut Line= 3
      2253943.72     13254890.96      2253957.61     13253717.33
      2253888.16     13253453.43
#Sta/Elev= 30
  4114.1  297.85  4178.2  295.18  4188.2  293.96  4318.2  287.98  4418.2  282.27
  4498.2  278.93  4648.2  276.47  4868.3  275.62  4888.3  275.05  4895.3  274.03
    4898  273.53  4901.3  274.03  4918.3  275.44  4958.3  276.24  4978.3  276.32
  4998.3  274.81  5058.3  277.65  5155.2  283.78  5218.3  287.91  5228.3  289.45
  5253.9   290.2  5290.6  290.85  5310.6  291.97  5319.3  293.67  5329.7  294.27
  5401.7  294.95  5453.8   296.8  5474.4  298.84  5525.2  299.61  5560.7   300.4
#Mann= 7 ,-1 , 0
  4114.1     .05       0  4895.3     .07       0  4901.3     .05       0
  5155.2     .05       0  5253.9      .1       0  5401.7     .05       0
  5525.2      .1       0
Bank Sta=4868.3,4958.3
XS Rating Curve= 0 ,0
Exp/Cntr=0.3,0.1

Type RM Length L Ch R = 1 ,73839   ,496,496,496
BEGIN DESCRIPTION:
UNT001 IN PECR 139.0
END DESCRIPTION:
XS GIS Cut Line= 3
      2254089.58     13254995.06      2254332.61     13254640.94
      2254797.85     13253661.85
#Sta/Elev= 30
    4262  302.49    4679  282.41  4787.5  277.11  4884.2  273.67  4939.6  272.57
  4983.9  273.04  4994.6  270.36  4997.3  269.86  5000.6  270.36    5006  273.32
    5043   273.8  5111.2  273.03    5150  274.98  5156.6  276.21  5189.6  276.38
  5216.4   276.9  5224.8  278.43  5238.5   279.4  5298.5   280.4  5321.2   281.4
  5327.1  282.39  5463.1  284.39    5503   286.3  5525.7  285.74    5554  286.28
    5615  288.15  5622.1  288.98  5637.1  288.46  5699.4  290.05  5775.5   292.4
#Mann= 6 ,-1 , 0
    4262     .05       0    4679      .1       0  4994.6     .07       0
  5000.6      .1       0  5189.6     .05       0  5699.4      .1       0
Bank Sta=4983.9,5006
XS Rating Curve= 0 ,0
Exp/Cntr=0.3,0.1

Type RM Length L Ch R = 1 ,73343   ,437,437,437
BEGIN DESCRIPTION:
UNT001 IN PECR 138.0
END DESCRIPTION:
XS GIS Cut Line= 3
      2254137.72     13255246.86      2254937.72     13254446.85
      2255287.73     13253646.84
#Sta/Elev= 30
  3862.6  309.38  4117.2   300.5  4541.4  279.61  4725.3  273.95  4902.7     271
  4979.8  272.06  4990.4  269.77  4999.9  269.63  5002.7  269.13  5005.9  269.63
  5031.8  270.64  5037.6  271.81    5084     271  5122.6  272.33  5206.4  275.31
  5223.2  276.86  5299.6  278.46  5305.4  279.87  5381.1  280.94  5404.5   282.8
  5474.2  283.48  5617.7  288.16  5648.9  288.09  5654.7   289.5  5670.7  290.38
    5769  292.63  5800.5  294.84  5823.5  294.61  5864.6  296.51  5867.2  296.51
#Mann= 7 ,-1 , 0
  3862.6     .05       0  4902.7      .1       0  4999.9     .07       0
  5005.9      .1       0  5122.6     .05       0  5617.7      .1       0
  5864.6     .05       0
Bank Sta=4979.8,5037.6
XS Rating Curve= 0 ,0
Exp/Cntr=0.3,0.1

Type RM Length L Ch R = 1 ,72906   ,476,476,476
BEGIN DESCRIPTION:
UNT001 IN PECR 137.0
END DESCRIPTION:
XS GIS Cut Line= 3
      2255087.72     13254996.85      2255337.72     13254596.85
      2255487.71     13253796.89
#Sta/Elev= 30
  4496.9  285.13  4643.7  278.07  4802.9   271.5  4887.8  269.71  4903.2  268.38
  4939.7  270.45    4955  270.13  4978.8   271.3  4988.9  269.02    4997   265.4
  4999.7   264.9    5003   265.4  5009.3   268.4  5019.5  269.57  5047.4  269.33
  5079.6  271.67  5131.4  274.48  5304.3  274.53    5345  275.43  5365.4  276.94
  5406.1  276.75  5446.8  279.77  5477.3  279.87    5518   282.7  5540.9  282.56
  5588.4  285.81  5621.9  286.37  5651.1  287.63  5660.4  289.38  5782.5  293.73
#Mann= 6 ,-1 , 0
  4496.9     .05       0  4643.7      .1       0    4997     .07       0
    5003      .1       0  5079.6     .05       0  5621.9      .1       0
Bank Sta=4988.9,5019.5
XS Rating Curve= 0 ,0
Exp/Cntr=0.3,0.1

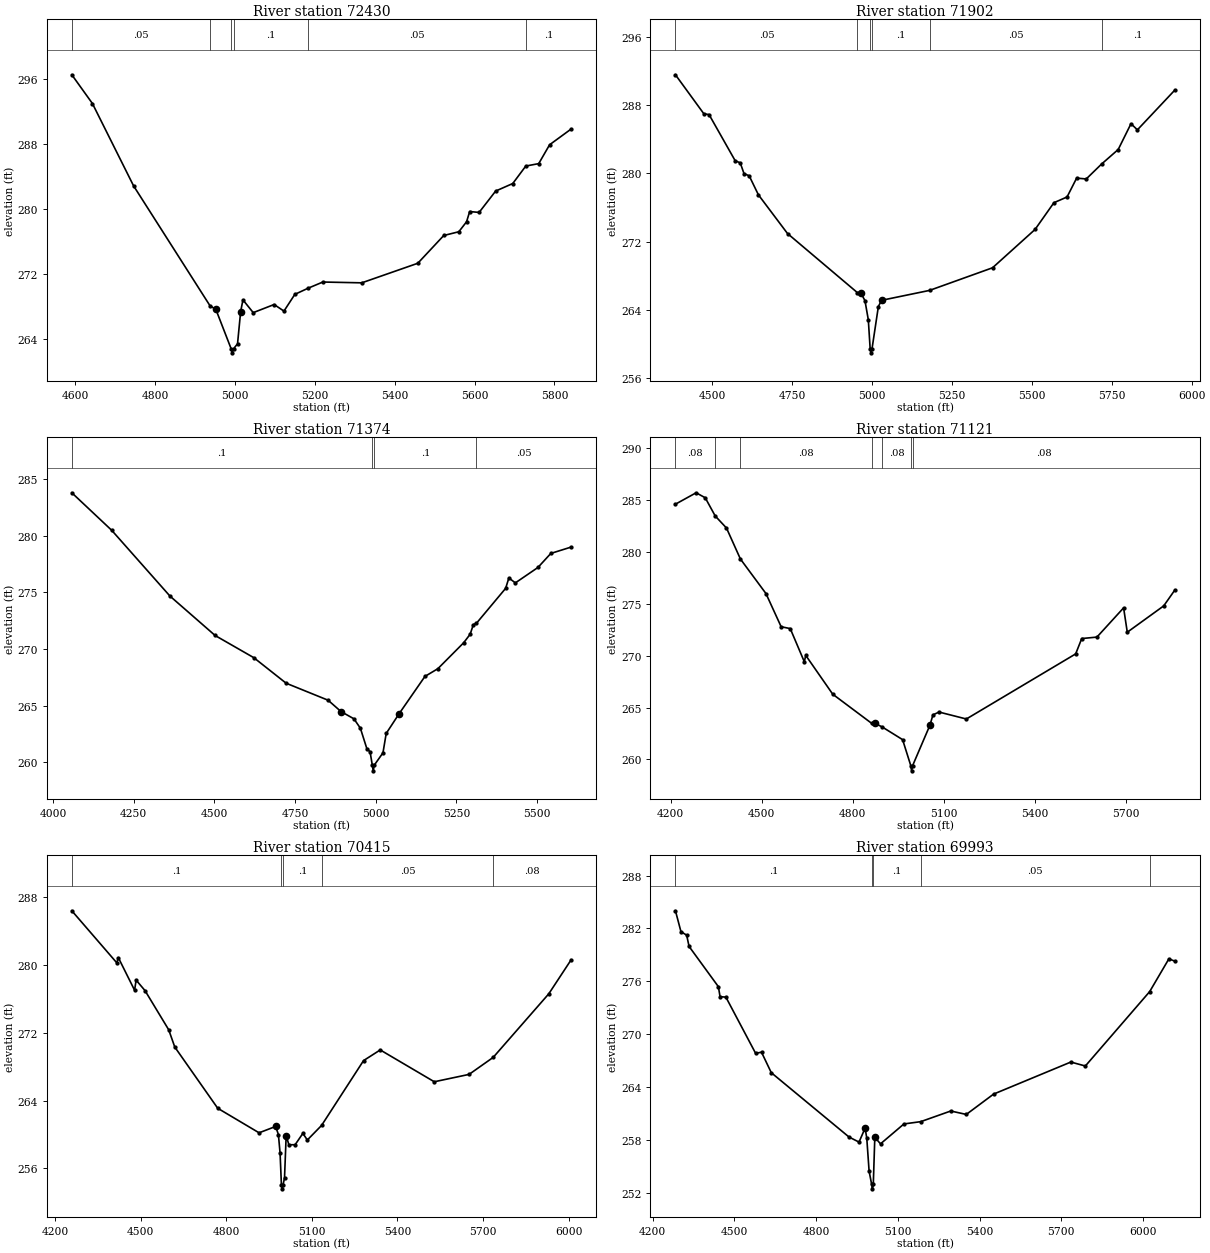
Type RM Length L Ch R = 1 ,72430   ,528,528,528
BEGIN DESCRIPTION:
UNT001 IN PECR 136.0
END DESCRIPTION:
XS GIS Cut Line= 3
      2255637.71     13255196.89      2255737.72     13254796.85
      2255987.72     13253996.85
#Sta/Elev= 30
  4591.2  296.56  4642.8  293.02  4745.9  282.88  4937.1  268.13    4952  267.66
  4990.2  262.82    4993  262.32  4996.2  262.82  5006.2  263.43    5014  267.41
  5019.8  268.84  5045.5  267.27  5097.8  268.27  5122.5  267.46  5149.7  269.52
    5183  270.28  5219.9  271.04  5317.3  270.94  5457.7  273.35  5522.7  276.77
  5560.4  277.23  5579.8  278.46  5587.6  279.72  5611.2  279.61  5652.6  282.24
  5695.5  283.17  5728.1  285.32  5760.5  285.62  5787.7  287.94  5841.7  289.88
#Mann= 6 ,-1 , 0
  4591.2     .05       0  4937.1      .1       0  4990.2     .07       0
  4996.2      .1       0    5183     .05       0  5728.1      .1       0
Bank Sta=4952,5014
XS Rating Curve= 0 ,0
Exp/Cntr=0.3,0.1

Type RM Length L Ch R = 1 ,71902   ,528,528,528
BEGIN DESCRIPTION:
UNT001 IN PECR 135.0
END DESCRIPTION:
XS GIS Cut Line= 4
      2255839.55      13255321.5      2256172.89     13255140.94
      2256381.22     13254467.33      2256388.14     13253989.97
#Sta/Elev= 30
  4385.6  291.55  4474.5  286.98  4490.7  286.89  4572.5  281.48  4588.2  281.24
    4600  279.98  4616.2  279.72  4645.1  277.49  4736.1  272.96  4954.6  266.04
  4964.9  266.04  4978.3   265.1  4988.8  262.86  4994.5  259.49  4997.3  258.99
  5000.5  259.49  5020.2  264.41  5030.2  265.14  5180.2   266.3  5377.3  268.95
  5510.3  273.44  5569.2  276.57  5610.3  277.24  5640.3  279.45  5670.3  279.35
  5718.1  281.09  5770.3   282.8  5810.3  285.82  5830.3   285.1  5947.2  289.75
#Mann= 6 ,-1 , 0
  4385.6     .05       0  4954.6      .1       0  4994.5     .07       0
  5000.5      .1       0  5180.2     .05       0  5718.1      .1       0
Bank Sta=4964.9,5030.2
XS Rating Curve= 0 ,0
Exp/Cntr=0.3,0.1

Type RM Length L Ch R = 1 ,71374   ,253,253,253
BEGIN DESCRIPTION:
UNT001 IN PECR 134.0
END DESCRIPTION:
XS GIS Cut Line= 2
      2256763.89     13255790.76      2256763.89     13254243.96
#Sta/Elev= 30
  4058.5  283.79  4182.4  280.47  4362.4  274.68  4502.4   271.2  4622.4  269.24
  4722.4  266.99  4852.4  265.49  4892.4  264.49  4932.4  263.85  4952.4  263.02
  4972.4  261.22  4982.4  260.94  4989.4  259.76  4992.2  259.26  4995.4  259.76
  5022.4  260.85  5032.4  262.56  5072.4   264.3  5152.4  267.59  5192.4  268.27
  5272.4  270.56  5292.4  271.31  5302.4  272.16    5312  272.28  5402.4  275.36
  5412.4  276.28  5432.4  275.84  5502.4   277.2  5542.4  278.44  5605.3     279
#Mann= 4 ,-1 , 0
  4058.5      .1       0  4989.4     .07       0  4995.4      .1       0
    5312     .05       0
Bank Sta=4892.4,5072.4
XS Rating Curve= 0 ,0
Exp/Cntr=0.3,0.1

Type RM Length L Ch R = 1 ,71121   ,706,706,706
BEGIN DESCRIPTION:
UNT001 IN PECR 133.0
END DESCRIPTION:
XS GIS Cut Line= 2
      2257008.68     13255644.92      2257024.29     13254000.49
#Sta/Elev= 30
    4216  284.62  4284.1  285.72  4314.1  285.24    4347  283.48  4384.1  282.32
    4430  279.33  4514.1     276  4564.1   272.8  4594.1  272.62  4640.3  269.43
  4645.3  270.03  4734.1  266.29  4861.9  263.49  4874.1  263.47    4897  263.13
  4964.1  261.91  4991.1   259.4  4993.8   258.9  4997.1   259.4  5054.1   263.3
  5064.1   264.3  5084.1  264.57  5174.1   263.9  5534.1  270.18  5554.1  271.66
  5604.1   271.8    5692  274.62  5704.1  272.27  5824.1  274.81  5860.5  276.33
#Mann= 7 ,-1 , 0
    4216     .08       0    4347     .05       0    4430     .08       0
  4861.9     .05       0    4897     .08       0  4991.1     .07       0
  4997.1     .08       0
Bank Sta=4874.1,5054.1
XS Rating Curve= 0 ,0
Exp/Cntr=0.3,0.1

Type RM Length L Ch R = 1 ,70415   ,422,422,422
BEGIN DESCRIPTION:
UNT001 IN PECR 132.0
END DESCRIPTION:
XS GIS Cut Line= 4
      2257895.11     13255238.14      2257756.22     13254835.38
       2257346.5     13254140.94       2257047.9     13253717.34
#Sta/Elev= 30
  4258.2  286.42  4415.9  280.27  4421.2  280.89  4478.3  277.03  4483.6  278.23
  4514.8  276.99  4597.9  272.36  4619.2  270.32  4769.7  263.09  4914.7  260.19
  4972.8  260.94  4982.5  259.98  4988.3   257.8    4993  254.07  4995.8  253.57
    4999  254.07  5003.9  254.86  5009.7  259.86  5019.2  258.78    5041  258.78
  5068.3  260.12  5083.9  259.34  5133.8  261.06    5281  268.72  5339.5  269.98
    5529  266.22  5650.9  267.09  5735.5   269.1  5930.4  276.61  6008.8  280.63
#Mann= 5 ,-1 , 0
  4258.2      .1       0    4993     .07       0    4999      .1       0
  5133.8     .05       0  5735.5     .08       0
Bank Sta=4972.8,5009.7
XS Rating Curve= 0 ,0
Exp/Cntr=0.3,0.1

Type RM Length L Ch R = 1 ,69993   ,380,380,380
BEGIN DESCRIPTION:
UNT001 IN PECR 131.0
END DESCRIPTION:
XS GIS Cut Line= 4
      2258353.44     13254939.54      2258110.39     13254585.38
      2257617.33     13253897.88      2257133.51     13253621.41
#Sta/Elev= 30
  4283.7  284.01  4303.9  281.64  4324.9  281.24  4333.7  279.96  4441.3  275.39
  4447.4  274.26  4468.9   274.2    4578  267.82  4599.6  267.95  4635.5  265.62
    4921  258.31  4957.5  257.74  4979.9  259.33    4986  258.18  4994.5  254.45
  5003.9  252.93  5006.7  252.43  5009.9  252.93  5015.5  258.28  5036.4  257.54
  5122.4   259.8    5184  260.06  5294.3  261.27  5351.3  260.88  5451.5  263.19
    5735  266.83  5788.3  266.38  6024.4  274.83  6094.9  278.55  6116.5  278.29
#Mann= 5 ,-1 , 0
  4283.7      .1       0  5003.9     .07       0  5009.9      .1       0
    5184     .05       0  6024.4     .08       0
Bank Sta=4979.9,5015.5
XS Rating Curve= 0 ,0
Exp/Cntr=0.3,0.1