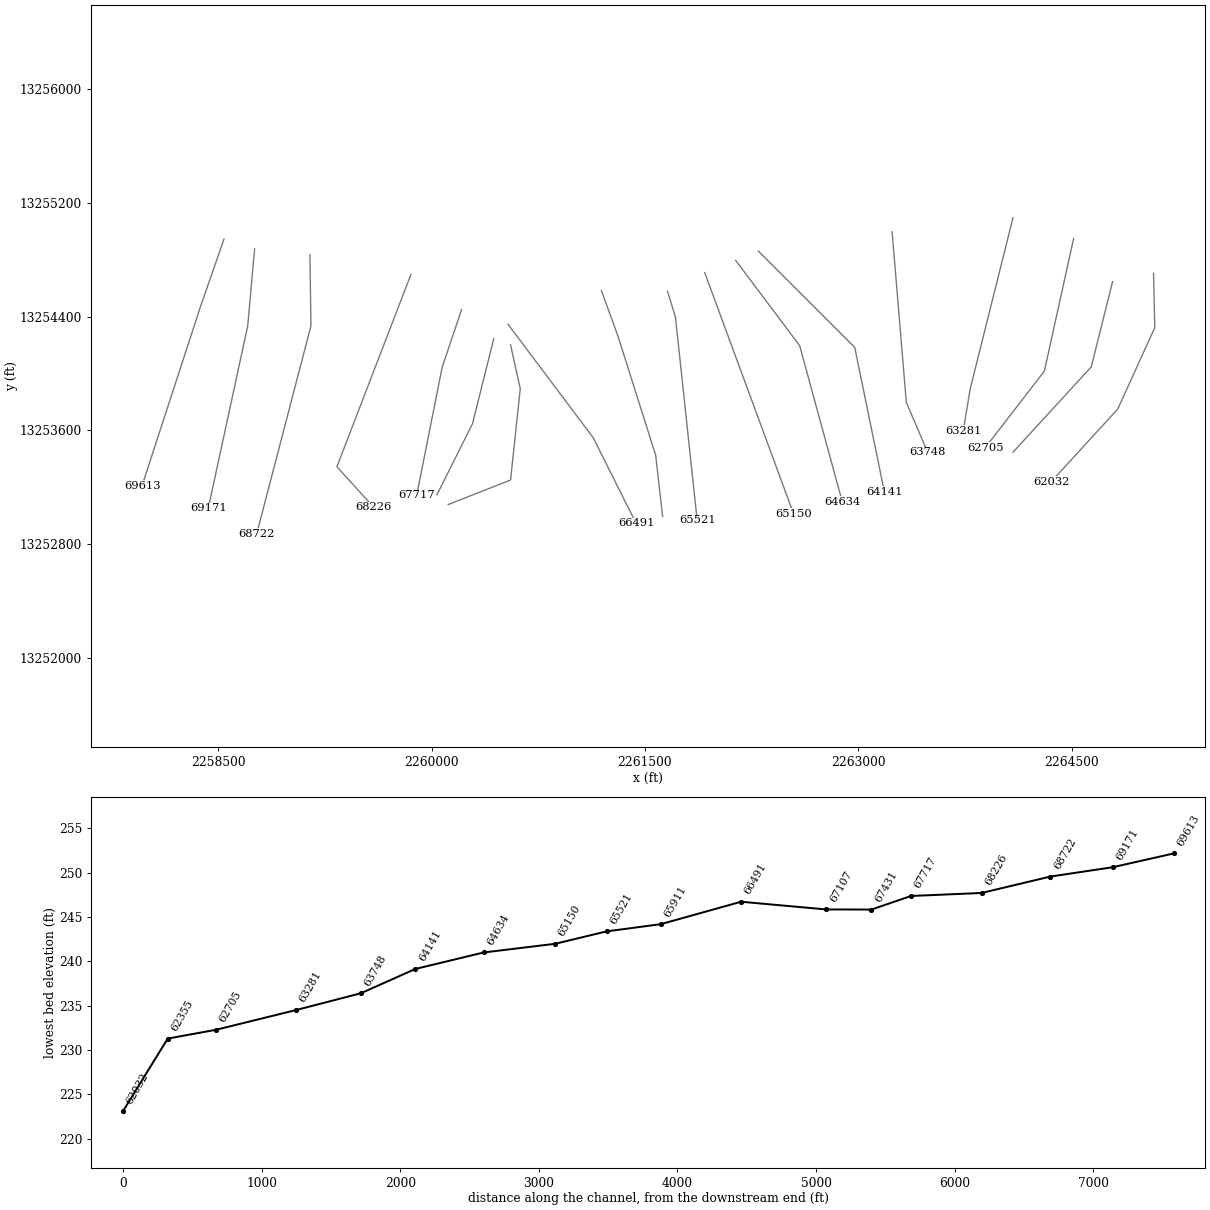
HEC-RAS study UNT001 IN PECR.prj: UNT001 IN PECR Base Level Engineering

--- UNT001 IN PECR.g01 (geometry) --- (continued)

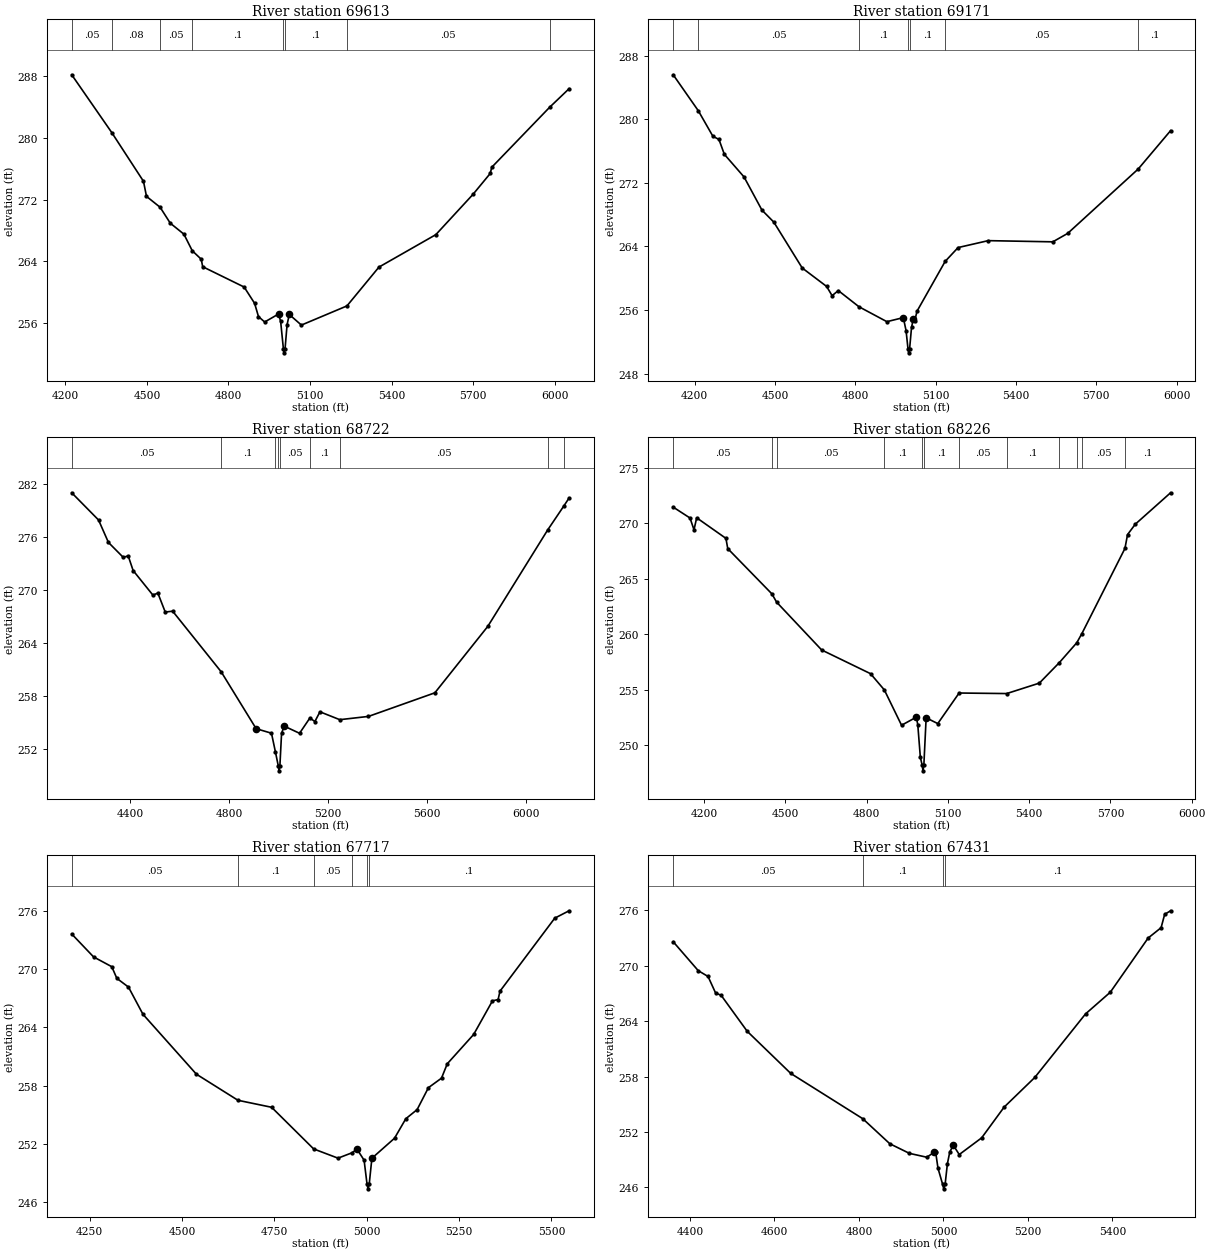
Type RM Length L Ch R = 1 ,69613   ,442,442,442
BEGIN DESCRIPTION:
UNT001 IN PECR 130.0
END DESCRIPTION:
XS GIS Cut Line= 3
      2258540.95      13254946.5      2258374.28     13254467.33
      2257964.79     13253211.11
#Sta/Elev= 30
  4223.6  288.15  4370.9  280.67  4487.4  274.37  4498.5  272.42  4548.6  271.01
    4586  268.95  4636.1  267.53  4666.7  265.39  4699.7  264.29  4705.1  263.32
  4857.6  260.69  4895.9  258.59  4910.2  256.87    4933  256.17  4983.9   257.2
  4991.6  256.28  5001.9  252.68  5004.6  252.18  5007.9  252.68  5015.4  255.83
  5023.5  257.14    5068  255.77  5235.5  258.25  5353.1  263.27  5562.3  267.47
  5698.9  272.68  5762.2  275.38    5768  276.19  5980.5  283.94  6052.2  286.35
#Mann= 8 ,-1 , 0
  4223.6     .05       0  4370.9     .08       0  4548.6     .05       0
  4666.7      .1       0  5001.9     .07       0  5007.9      .1       0
  5235.5     .05       0  5980.5      .1       0
Bank Sta=4983.9,5023.5
XS Rating Curve= 0 ,0
Exp/Cntr=0.3,0.1

Type RM Length L Ch R = 1 ,69171   ,449,449,449
BEGIN DESCRIPTION:
UNT001 IN PECR 129.0
END DESCRIPTION:
XS GIS Cut Line= 3
      2258756.22     13254877.07      2258707.61     13254335.38
      2258429.96     13253051.22
#Sta/Elev= 30
  4120.1  285.59  4213.8  281.07  4268.5  277.85    4291  277.46  4311.1  275.59
  4384.7  272.74  4451.6  268.57  4495.9  267.06    4602  261.29  4693.2  258.97
  4713.6  257.81  4736.8  258.45  4813.8  256.42  4918.2  254.54  4979.6  255.05
  4989.9  253.41  4997.1  251.12  4999.8  250.62  5003.1  251.12  5010.3  253.82
  5016.9  254.88    5022   254.6  5030.8  255.86  5135.9  262.12  5184.2  263.86
  5296.8  264.73    5538  264.58  5593.5  265.64    5857  273.74  5977.8  278.56
#Mann= 7 ,-1 , 0
  4120.1      .1       0  4213.8     .05       0  4813.8      .1       0
  4997.1     .07       0  5003.1      .1       0  5135.9     .05       0
    5857      .1       0
Bank Sta=4979.6,5016.9
XS Rating Curve= 0 ,0
Exp/Cntr=0.3,0.1

Type RM Length L Ch R = 1 ,68722   ,496,496,496
BEGIN DESCRIPTION:
UNT001 IN PECR 128.0
END DESCRIPTION:
XS GIS Cut Line= 3
      2259145.11     13254835.42      2259152.06     13254335.38
      2258770.35       13252871.
#Sta/Elev= 30
  4162.9  281.04  4271.5  277.96  4311.5  275.42  4371.5  273.73  4391.5   273.9
  4411.5  272.24  4491.5  269.46  4511.5  269.69  4541.5  267.54  4571.5  267.64
  4767.9  260.78  4909.5  254.34  4971.5  253.83  4987.6   251.7  4999.5  250.07
  5002.2  249.57  5005.5  250.07  5012.4  253.83  5023.2  254.63  5085.2  253.82
    5127  255.55  5147.2  255.15  5167.8  256.25    5248  255.36  5364.2  255.73
  5632.9   258.4  5847.2  265.92  6089.1  276.81  6154.9  279.54  6176.3  280.45
#Mann= 9 ,-1 , 0
  4162.9     .05       0  4767.9      .1       0  4987.6     .05       0
  4999.5     .04       0  5005.5     .05       0    5127      .1       0
    5248     .05       0  6089.1      .1       0  6154.9     .05       0
Bank Sta=4909.5,5023.2
XS Rating Curve= 0 ,0
Exp/Cntr=0.3,0.1

Type RM Length L Ch R = 1 ,68226   ,509,509,509
BEGIN DESCRIPTION:
UNT001 IN PECR 127.0
END DESCRIPTION:
XS GIS Cut Line= 3
      2259855.49     13254698.55      2259334.66     13253344.37
      2259593.91     13253059.19
#Sta/Elev= 30
  4085.8  271.44  4147.9  270.46  4162.6   269.4  4172.5  270.48  4280.5  268.63
  4287.2  267.71  4450.1  263.64  4467.7  262.89    4634  258.59  4814.3  256.46
  4865.3     255  4928.9  251.82  4983.6  252.55  4988.9  251.85  4998.3  248.93
  5005.2  248.22    5008  247.72  5011.2  248.22  5019.7  252.49  5062.6  251.97
  5141.4  254.72  5317.1  254.67  5437.6  255.61  5511.3  257.45  5575.8  259.24
  5594.6  260.06  5753.6  267.72  5763.3  268.97  5791.7   269.9  5922.1  272.73
#Mann= 12 ,-1 , 0
  4085.8     .05       0  4450.1      .1       0  4467.7     .05       0
  4865.3      .1       0  5005.2     .07       0  5011.2      .1       0
  5141.4     .05       0  5317.1      .1       0  5511.3     .05       0
  5575.8      .1       0  5594.6     .05       0  5753.6      .1       0
Bank Sta=4983.6,5019.7
XS Rating Curve= 0 ,0
Exp/Cntr=0.3,0.1

Type RM Length L Ch R = 1 ,67717   ,286,286,286
BEGIN DESCRIPTION:
UNT001 IN PECR 126.0
END DESCRIPTION:
XS GIS Cut Line= 3
      2260210.96     13254449.57      2260074.59     13254044.08
      2259895.19     13253143.48
#Sta/Elev= 30
  4201.7  273.63  4260.8  271.27  4310.1  270.26  4323.8  269.06  4355.3  268.16
  4394.5  265.36  4539.1  259.19  4651.7   256.5  4742.7  255.78  4856.5  251.49
  4922.4  250.54  4961.4  251.11  4973.4  251.49    4993  250.33  5000.9  247.88
  5003.7  247.38  5006.9  247.88  5014.1  250.53  5075.3  252.59  5105.9   254.6
  5136.5  255.54  5167.1   257.8  5202.5  258.78  5218.1  260.26  5289.5  263.28
  5340.4  266.74  5355.7  266.88  5360.8  267.74    5509  275.26  5547.8  276.02
#Mann= 6 ,-1 , 0
  4201.7     .05       0  4651.7      .1       0  4856.5     .05       0
  4961.4      .1       0  5000.9     .07       0  5006.9      .1       0
Bank Sta=4973.4,5014.1
XS Rating Curve= 0 ,0
Exp/Cntr=0.3,0.1

Type RM Length L Ch R = 1 ,67431   ,324,324,324
BEGIN DESCRIPTION:
UNT001 IN PECR 125.0
END DESCRIPTION:
XS GIS Cut Line= 3
      2260437.72     13254246.86      2260287.72     13253646.85
      2260037.71     13253146.84
#Sta/Elev= 30
  4360.3  272.59  4419.6  269.46  4442.8  268.83  4460.8  267.03  4473.7   266.8
  4535.5   262.9  4638.6  258.34  4809.1  253.44  4873.1  250.73  4919.5  249.69
  4960.7  249.27  4978.8  249.83  4981.6  249.83  4987.2  248.08  4998.1  246.35
  5000.9  245.85  5004.1  246.35  5009.5  248.58  5015.1  249.84  5023.5  250.57
  5037.5  249.56  5090.6  251.37  5143.7  254.69  5216.3   257.9  5336.5  264.78
  5395.2  267.13  5484.7  272.99  5515.4  274.11  5523.8  275.55  5537.8  275.94
#Mann= 4 ,-1 , 0
  4360.3     .05       0  4809.1      .1       0  4998.1     .07       0
  5004.1      .1       0
Bank Sta=4978.8,5023.5
XS Rating Curve= 0 ,0
Exp/Cntr=0.3,0.1

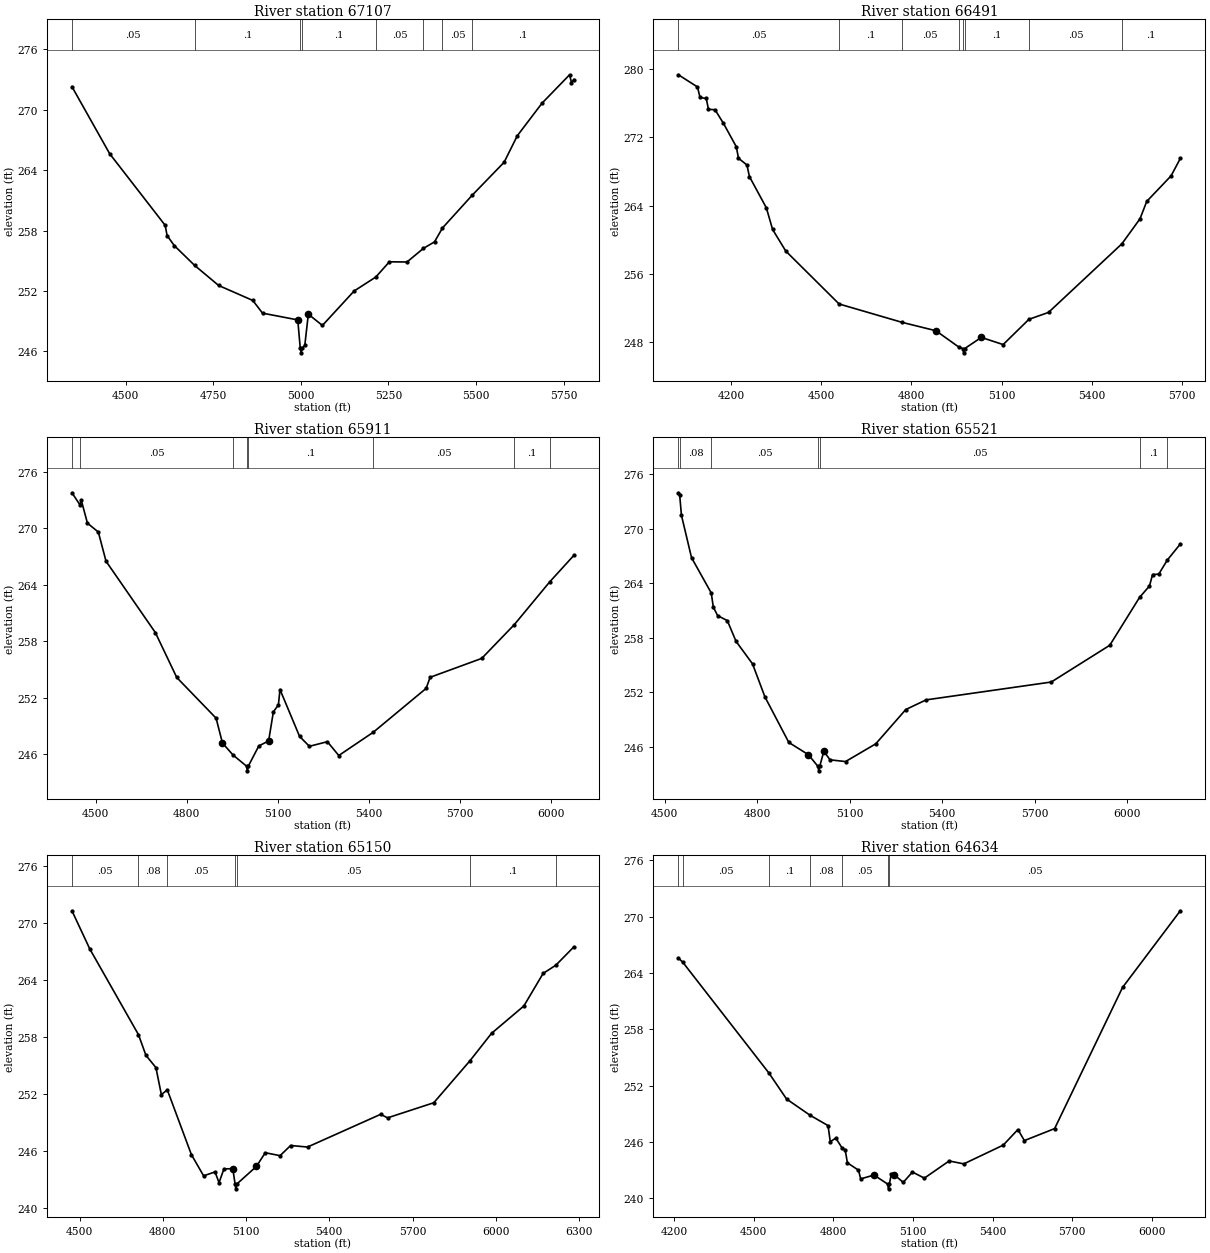
Type RM Length L Ch R = 1 ,67107   ,616,616,616
BEGIN DESCRIPTION:
UNT001 IN PECR 124.0
END DESCRIPTION:
XS GIS Cut Line= 4
       2260555.4       13254202.      2260623.58     13253893.38
      2260555.41     13253251.09      2260117.63     13253078.85
#Sta/Elev= 30
  4346.8  272.29  4454.5  265.63  4612.9  258.52  4618.3  257.51  4638.8  256.51
  4696.7  254.55  4765.4  252.55    4863  251.06  4890.7   249.8  4991.2  249.13
  4998.3  246.36    5001  245.86  5004.3  246.36  5011.3  246.59  5021.4   249.7
  5061.6  248.58  5152.1     252  5214.1  253.39  5252.7   254.9    5303  254.88
  5349.8  256.23  5381.5  256.88  5404.3  258.26  5489.3  261.52  5580.1  264.78
  5617.9  267.42  5688.4  270.65    5767  273.47  5772.4   272.7  5779.2  272.99
#Mann= 8 ,-1 , 0
  4346.8     .05       0  4696.7      .1       0  4998.3     .07       0
  5004.3      .1       0  5214.1     .05       0  5349.8      .1       0
  5404.3     .05       0  5489.3      .1       0
Bank Sta=4991.2,5021.4
XS Rating Curve= 0 ,0
Exp/Cntr=0.3,0.1

Type RM Length L Ch R = 1 ,66491   ,580,580,580
BEGIN DESCRIPTION:
UNT001 IN PECR 123.0
END DESCRIPTION:
XS GIS Cut Line= 3
      2260537.73     13254346.84      2261137.72     13253546.85
      2261437.72     13252946.86
#Sta/Elev= 30
  4024.2  279.34  4087.7  277.91  4096.1  276.68  4116.9  276.56  4124.2  275.29
  4146.1  275.24  4174.2  273.64  4216.9   270.9  4224.2  269.55  4252.3  268.76
  4260.6   267.4  4316.9  263.74  4337.7   261.2  4381.5  258.67  4559.1  252.46
  4768.2  250.31  4881.5  249.32  4957.1  247.42  4971.2  247.23  4973.9  246.73
  4977.2  247.23  5032.6  248.54  5105.2   247.7    5191  250.66  5256.2  251.47
  5500.3  259.51  5560.8  262.45  5583.2  264.49  5664.3  267.49    5695  269.53
#Mann= 8 ,-1 , 0
  4024.2     .05       0  4559.1      .1       0  4768.2     .05       0
  4957.1      .1       0  4971.2     .07       0  4977.2      .1       0
    5191     .05       0  5500.3      .1       0
Bank Sta=4881.5,5032.6
XS Rating Curve= 0 ,0
Exp/Cntr=0.3,0.1

Type RM Length L Ch R = 1 ,65911   ,390,390,390
BEGIN DESCRIPTION:
UNT001 IN PECR 122.0
END DESCRIPTION:
XS GIS Cut Line= 4
      2261193.74     13254585.35      2261311.78     13254258.99
      2261575.67     13253425.66      2261624.28     13252995.06
#Sta/Elev= 30
  4421.8  273.78  4447.9  272.51  4452.8  272.96  4472.8  270.55  4508.8   269.6
  4534.1   266.5  4696.7  258.91  4767.3  254.13    4897   249.8  4917.9  247.16
  4952.6  245.89  4997.2   244.7    5000   244.2  5003.2   244.7  5037.8  246.85
  5070.1  247.38  5085.8  250.48  5102.4  251.22  5107.6  252.85  5172.2  247.86
  5204.5  246.81  5263.8   247.3  5301.4  245.83  5415.3  248.31  5589.3  252.97
  5602.5  254.15  5772.6  256.16  5880.2  259.76  5996.4  264.29  6076.3  267.12
#Mann= 8 ,-1 , 0
  4421.8     .08       0  4447.9     .05       0  4952.6      .1       0
  4997.2     .07       0  5003.2      .1       0  5415.3     .05       0
  5880.2      .1       0  5996.4     .05       0
Bank Sta=4917.9,5070.1
XS Rating Curve= 0 ,0
Exp/Cntr=0.3,0.1

Type RM Length L Ch R = 1 ,65521   ,371,371,371
BEGIN DESCRIPTION:
UNT001 IN PECR 121.0
END DESCRIPTION:
XS GIS Cut Line= 3
      2261658.99     13254578.47      2261714.56     13254397.88
      2261867.33     13252967.36
#Sta/Elev= 30
  4544.7  273.95  4548.8  273.71  4554.5  271.48  4587.2  266.82  4651.2  262.94
  4657.8  261.39  4671.9  260.45  4703.3   259.9  4731.6  257.62    4785  255.15
  4825.2  251.52  4902.7  246.51    4966  245.17    4997  243.89  4999.8  243.39
    5003  243.89  5016.3  245.54  5036.4   244.6  5086.7  244.41  5184.7  246.36
  5282.1  250.13  5348.1  251.19  5753.8  253.15  5943.5  257.19  6040.3  262.46
  6072.2   263.7  6082.3  264.96  6102.4  265.01    6130  266.55  6172.3  268.32
#Mann= 7 ,-1 , 0
  4544.7     .05       0  4548.8     .08       0  4651.2     .05       0
    4997     .03       0    5003     .05       0  6040.3      .1       0
    6130     .05       0
Bank Sta=4966,5016.3
XS Rating Curve= 0 ,0
Exp/Cntr=0.3,0.1

Type RM Length L Ch R = 1 ,65150   ,516,516,516
BEGIN DESCRIPTION:
UNT001 IN PECR 120.0
END DESCRIPTION:
XS GIS Cut Line= 2
      2261920.14     13254710.93      2262545.14     13253013.01
#Sta/Elev= 30
  4472.3  271.25  4536.5  267.24    4712  258.22    4739  256.04    4775  254.75
  4794.6  251.91  4816.1   252.4  4902.9  245.59  4946.9  243.36  4988.1  243.77
  5002.5  242.64  5020.1  244.08  5052.1  244.12  5060.4  242.49  5063.1  241.99
  5066.4  242.49  5137.3  244.35  5169.2  245.79  5222.6  245.48  5260.6  246.55
  5321.5  246.39    5585  249.83  5610.1  249.46  5776.7  251.05  5907.7  255.49
  5984.8  258.35  6101.3  261.23  6170.9  264.66  6216.6  265.52  6281.6  267.45
#Mann= 7 ,-1 , 0
  4472.3     .05       0    4712     .08       0  4816.1     .05       0
  5060.4     .03       0  5066.4     .05       0  5907.7      .1       0
  6216.6     .05       0
Bank Sta=5052.1,5137.3
XS Rating Curve= 0 ,0
Exp/Cntr=0.3,0.1

Type RM Length L Ch R = 1 ,64634   ,493,493,493
BEGIN DESCRIPTION:
UNT001 IN PECR 119.0
END DESCRIPTION:
XS GIS Cut Line= 3
      2262137.74     13254796.82      2262587.72     13254196.85
      2262887.71     13253096.89
#Sta/Elev= 30
  4216.6  265.61  4233.2  265.15  4557.2  253.36  4623.9  250.58  4712.4  248.85
  4780.1  247.75  4788.4  246.03  4809.3  246.42  4833.2  245.35  4844.7  245.15
    4853  243.78  4894.7     243    4903  242.07    4953  242.48    5005  241.51
  5007.8  241.01    5011  241.51  5018.4   242.6  5028.8  242.52  5063.3   241.7
  5097.9   242.8  5142.8  242.15  5236.1  243.98  5291.3  243.67  5439.9  245.67
  5495.2  247.33  5519.4  246.15  5633.4  247.43  5889.1  262.47  6106.7  270.64
#Mann= 7 ,-1 , 0
  4216.6      .1       0  4233.2     .05       0  4557.2      .1       0
  4712.4     .08       0  4833.2     .05       0    5005     .03       0
    5011     .05       0
Bank Sta=4953,5028.8
XS Rating Curve= 0 ,0
Exp/Cntr=0.3,0.1

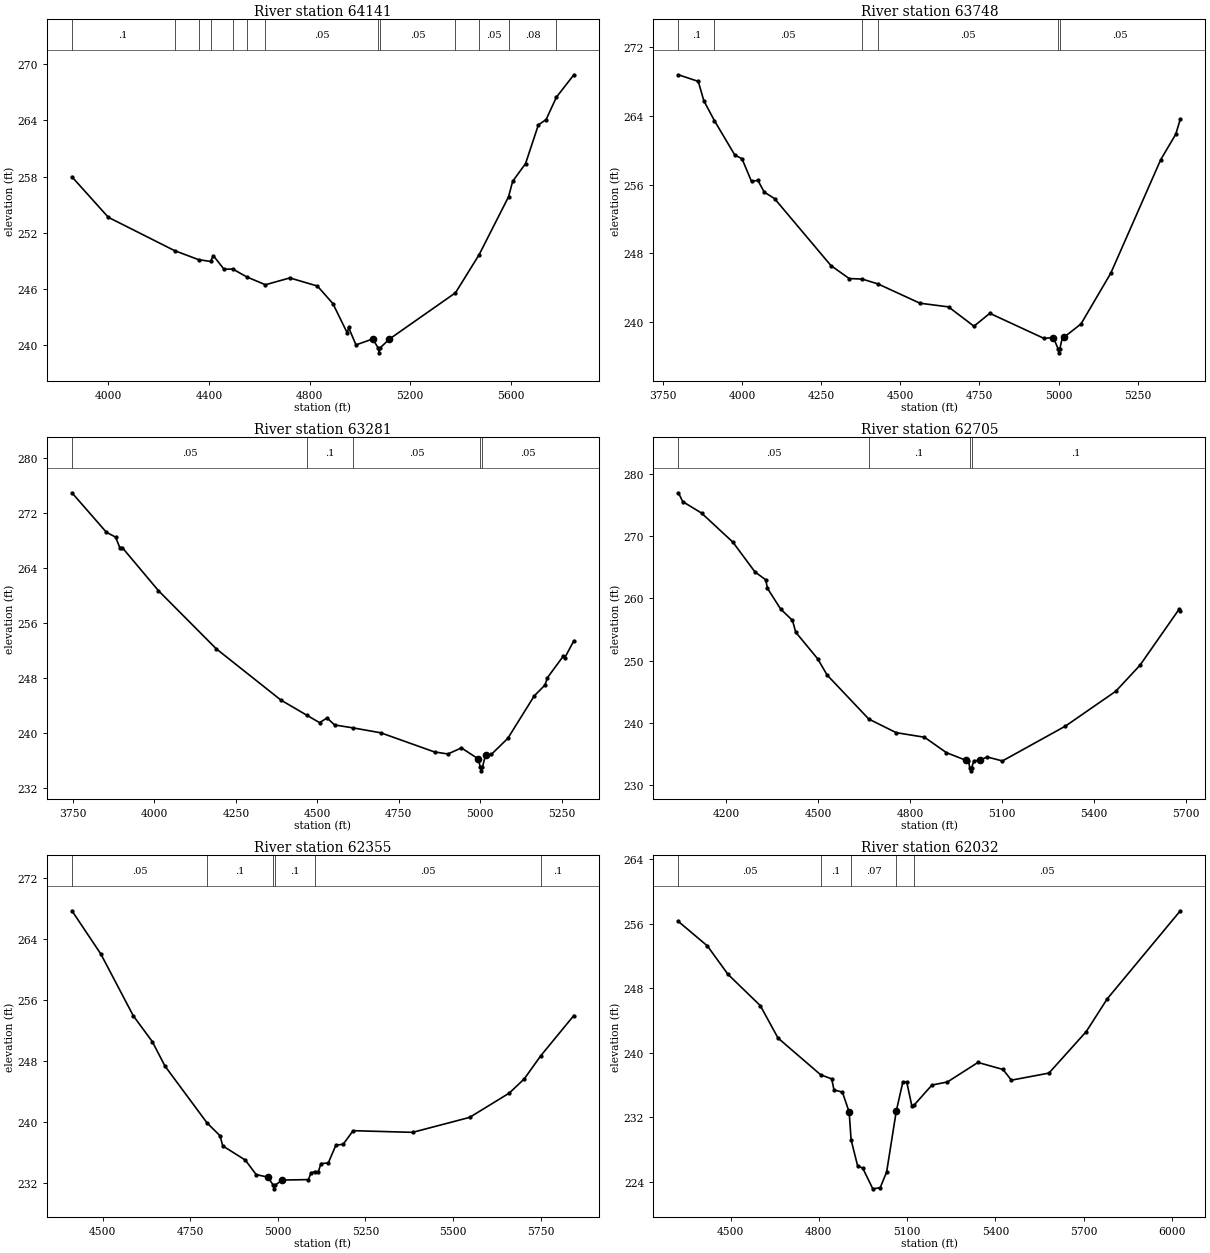
Type RM Length L Ch R = 1 ,64141   ,393,393,393
BEGIN DESCRIPTION:
UNT001 IN PECR 118.0
END DESCRIPTION:
XS GIS Cut Line= 3
      2262297.87     13254861.45      2262974.97     13254184.34
       2263183.3     13253168.76
#Sta/Elev= 30
    3856  257.97  4000.6  253.64  4263.6  250.08  4359.4  249.11  4406.7  248.92
  4417.8  249.54  4460.2  248.09  4495.1  248.11  4549.8  247.28  4624.7  246.43
  4721.8  247.16  4831.4  246.29  4892.7  244.42  4950.2  241.26  4955.3  241.86
  4984.5     240    5051  240.63  5073.4  239.65  5076.2  239.15  5079.4  239.65
  5117.3  240.62    5380  245.57  5473.8  249.64  5590.7  255.83  5607.2  257.49
  5658.3  259.38  5709.3  263.52    5740  264.09  5780.9  266.48  5850.3  268.88
#Mann= 13 ,-1 , 0
    3856      .1       0  4263.6     .05       0  4359.4      .1       0
  4406.7     .08       0  4495.1     .05       0  4549.8      .1       0
  4624.7     .05       0  5073.4     .03       0  5079.4     .05       0
    5380     .08       0  5473.8     .05       0  5590.7     .08       0
  5780.9     .05       0
Bank Sta=5051,5117.3
XS Rating Curve= 0 ,0
Exp/Cntr=0.3,0.1

Type RM Length L Ch R = 1 ,63748   ,467,467,467
BEGIN DESCRIPTION:
UNT001 IN PECR 117.0
END DESCRIPTION:
XS GIS Cut Line= 3
      2263237.72     13254996.88      2263337.72     13253796.85
      2263487.73     13253446.83
#Sta/Elev= 30
  3799.2  268.79  3861.9  268.02  3879.5  265.76    3913  263.44  3977.3  259.44
  3999.9  259.02    4030  256.37  4050.1   256.5  4070.2  255.13  4102.8  254.37
  4280.9  246.57  4338.6  245.06  4379.5     245  4429.1  244.44  4561.9  242.19
  4652.2  241.76  4732.5  239.51  4782.6  241.01  4953.2   238.1  4983.3  238.19
  4997.9  236.91  5000.6  236.41  5003.9  236.91  5012.5  238.32  5017.9  238.26
  5070.5  239.77  5164.8   245.7  5322.5  258.92  5369.7  261.86  5384.2  263.62
#Mann= 6 ,-1 , 0
  3799.2      .1       0    3913     .05       0  4379.5      .1       0
  4429.1     .05       0  4997.9     .03       0  5003.9     .05       0
#XS Ineff= 2 , 0
         4782.27     241
Permanent Ineff=
       F       F
Bank Sta=4983.3,5017.9
XS Rating Curve= 0 ,0
Exp/Cntr=0.3,0.1

Type RM Length L Ch R = 1 ,63281   ,576,576,576
BEGIN DESCRIPTION:
UNT001 IN PECR 116.0
END DESCRIPTION:
XS GIS Cut Line= 3
      2264087.71     13255096.81      2263787.72     13253896.85
      2263737.72     13253596.88
#Sta/Elev= 30
  3746.6  274.88  3852.2  269.16  3880.6  268.44  3893.4  266.93  3901.2  266.92
    4012  260.68  4189.8  252.23  4388.2  244.79  4468.9  242.56  4506.8  241.52
  4529.9  242.19  4553.1  241.18    4609  240.76  4694.9  240.04  4859.8  237.26
    4901  236.97  4942.3  237.85  4993.6  236.27  5000.8  235.02  5003.5  234.52
  5006.8  235.02  5016.4  236.81  5034.2   236.9  5084.9  239.24    5166   245.4
  5198.9  246.97  5206.5  248.04  5254.7  251.14  5259.7  250.93  5287.6   253.4
#Mann= 5 ,-1 , 0
  3746.6     .05       0  4468.9      .1       0    4609     .05       0
  5000.8     .03       0  5006.8     .05       0
Bank Sta=4993.6,5016.4
XS Rating Curve= 0 ,0
Exp/Cntr=0.3,0.1

Type RM Length L Ch R = 1 ,62705   ,350,350,350
BEGIN DESCRIPTION:
UNT001 IN PECR 115.0
END DESCRIPTION:
XS GIS Cut Line= 3
      2264513.88     13254950.48      2264308.05     13254017.21
      2263891.88     13253477.92
#Sta/Elev= 30
  4044.3  276.97  4058.3  275.55  4119.7  273.71  4222.1  269.03  4293.8  264.26
    4329  262.99  4334.7  261.62  4377.8  258.29  4416.3  256.47  4426.9  254.57
  4498.6  250.29  4529.3  247.69  4665.2  240.62  4754.6  238.43  4846.8   237.7
  4918.4  235.22  4981.7     234  4990.1   233.9  4994.6   232.8  4997.4   232.3
  5000.6   232.8  5007.7  233.89  5028.6  234.04    5051  234.53  5101.1  233.89
  5306.6  239.49  5470.6  245.08  5549.4  249.25    5678  258.32  5681.2  257.92
#Mann= 4 ,-1 , 0
  4044.3     .05       0  4665.2      .1       0  4994.6     .07       0
  5000.6      .1       0
Bank Sta=4981.7,5028.6
XS Rating Curve= 0 ,0
Exp/Cntr=0.3,0.1

Type RM Length L Ch R = 1 ,62355   ,323,323,323
BEGIN DESCRIPTION:
UNT001 IN PECR 114.0
END DESCRIPTION:
XS GIS Cut Line= 3
      2264787.71     13254646.82      2264637.72     13254046.85
       2264087.7     13253446.84
#Sta/Elev= 30
  4412.3  267.73  4494.7  262.07  4587.5  253.96  4641.6  250.59  4677.7  247.39
  4797.5  239.96  4834.9  238.25  4842.6  236.93    4907  235.07    4938  233.17
  4971.5  232.83  4986.5   231.8  4989.3   231.3  4992.5   231.8  5012.7  232.45
  5087.2  232.51  5094.6  233.39  5106.8  233.57  5115.5  233.55  5122.9  234.61
  5143.9  234.69  5165.5  237.02  5186.4  237.14  5214.8  238.92  5384.4   238.7
  5547.2  240.66  5660.6  243.85  5703.2  245.71  5750.7  248.76  5844.7  254.01
#Mann= 6 ,-1 , 0
  4412.3     .05       0  4797.5      .1       0  4986.5     .07       0
  4992.5      .1       0  5106.8     .05       0  5750.7      .1       0
Bank Sta=4971.5,5012.7
XS Rating Curve= 0 ,0
Exp/Cntr=0.3,0.1

Type RM Length L Ch R = 1 ,62032   ,638,638,638
BEGIN DESCRIPTION:
UNT001 IN PECR 113.0
END DESCRIPTION:
XS GIS Cut Line= 4
      2265075.67     13254705.22      2265084.35     13254323.23
      2264823.93     13253750.31      2264355.18     13253238.16
#Sta/Elev= 30
  4322.9   256.3  4421.3  253.27  4491.3  249.74  4601.3  245.85  4661.4  241.83
  4806.3  237.27  4843.8  236.76  4851.6  235.39  4880.2  235.12  4903.2  232.64
  4909.7  229.21  4931.8  225.98  4949.4  225.67  4983.6  223.11  5008.6  223.25
  5030.5   225.2  5063.5   232.8  5085.5  236.35  5098.8  236.38  5116.3  233.38
  5123.2  233.48  5184.3  235.99  5237.2  236.38  5340.9   238.8    5426  237.93
  5454.4   236.6  5582.1  237.48  5709.1  242.64    5780  246.69  6028.6  257.63
#Mann= 5 ,-1 , 0
  4322.9     .05       0  4806.3      .1       0  4909.7     .07       0
  5063.5      .1       0  5123.2     .05       0
Bank Sta=4903.2,5063.5
XS Rating Curve= 0 ,0
Exp/Cntr=0.3,0.1