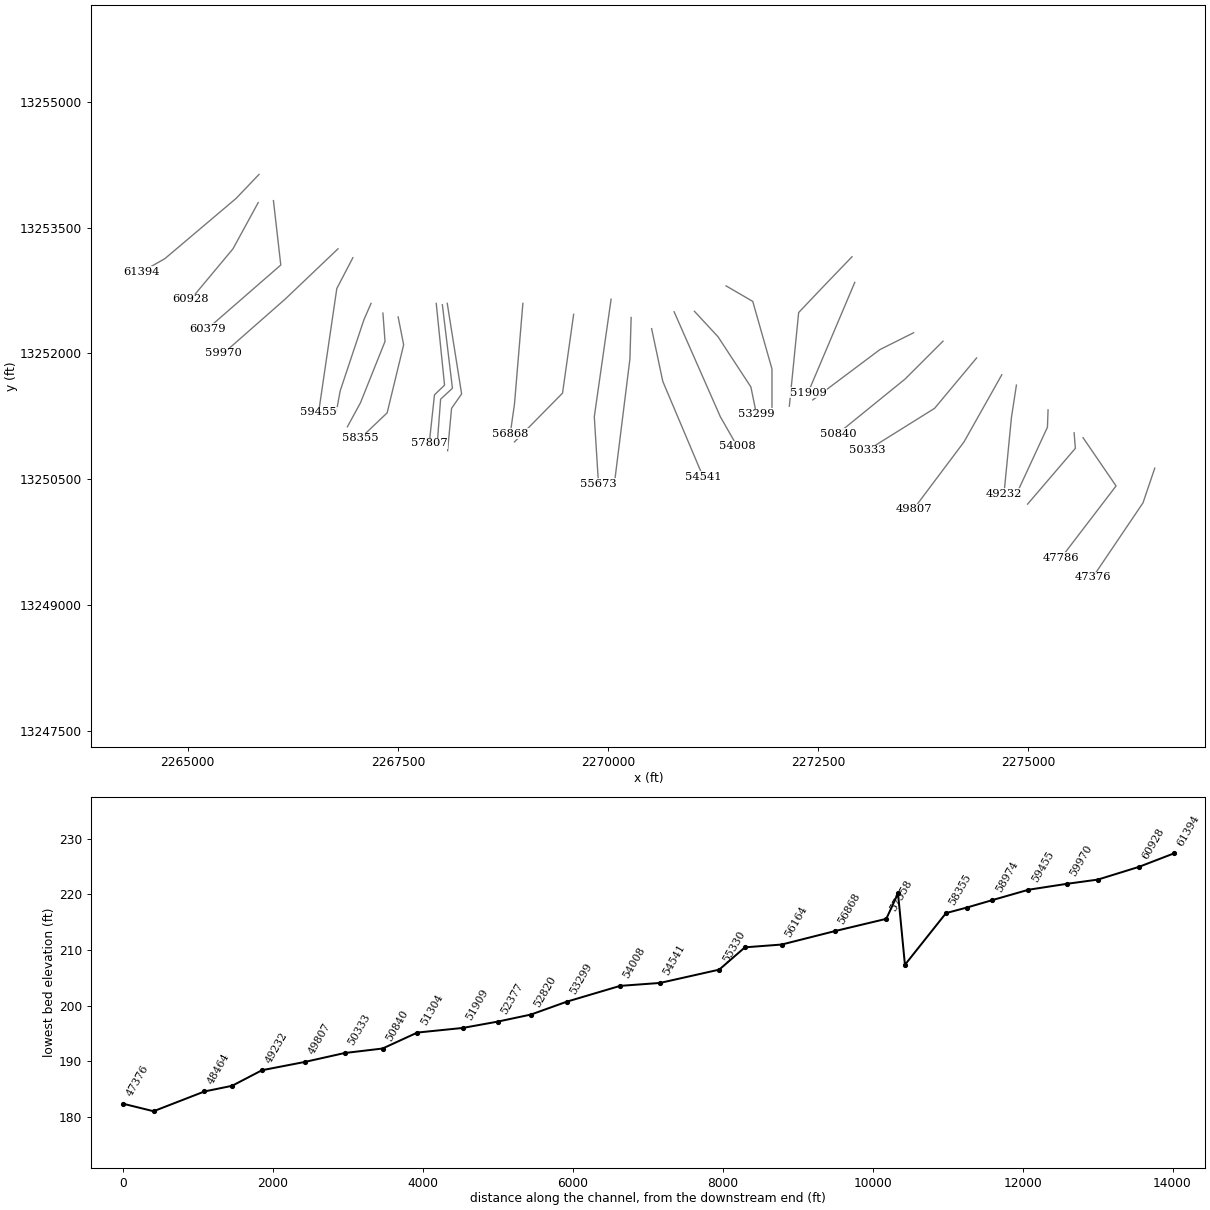
HEC-RAS study UNT001 IN PECR.prj: UNT001 IN PECR Base Level Engineering

--- UNT001 IN PECR.g01 (geometry) --- (continued)

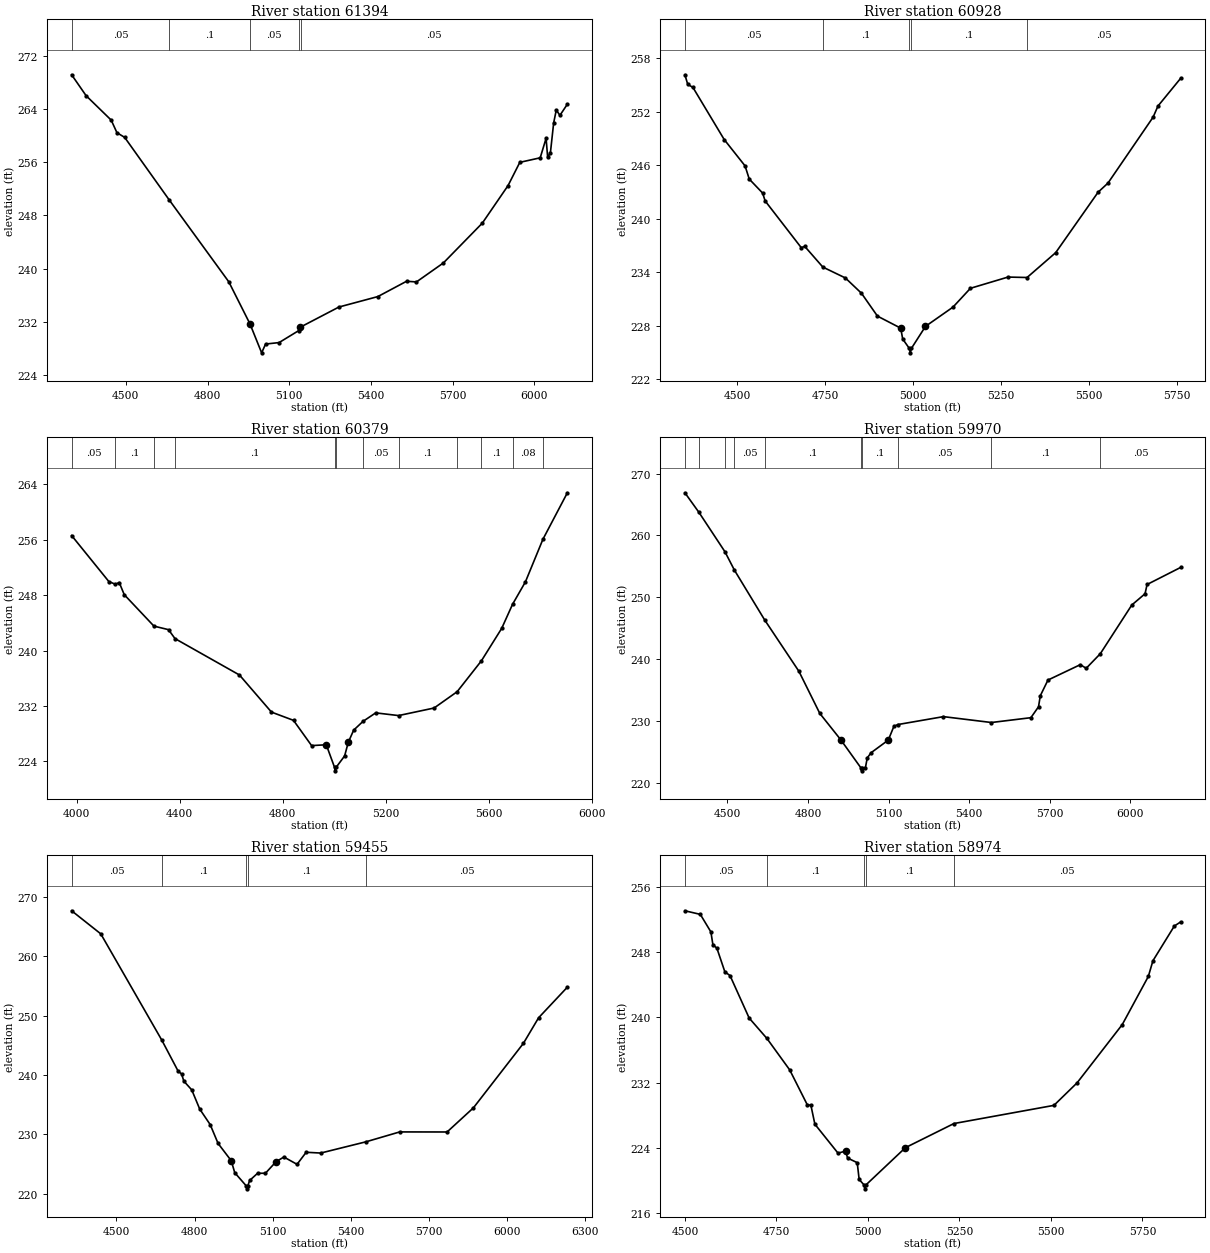
Type RM Length L Ch R = 1 ,61394   ,466,466,466
BEGIN DESCRIPTION:
UNT001 IN PECR 112.0
END DESCRIPTION:
XS GIS Cut Line= 4
      2265847.27     13254132.44      2265573.84     13253845.99
      2264727.48     13253129.85      2264454.06     13252973.61
#Sta/Elev= 30
  4301.3  269.12  4354.4  265.98  4446.5  262.31  4467.6  260.42  4495.9  259.72
  4659.2  250.34  4878.1  238.03  4956.1  231.69  4998.7  227.36  5013.2  228.68
  5062.7   228.9  5134.1  230.68  5140.7  231.25  5142.4  231.25  5282.4  234.24
  5425.3  235.81  5530.7  238.11    5567  238.01  5665.8  240.86  5808.7  246.84
  5903.2  252.48  5946.4  255.97  6021.2  256.65  6042.8  259.58  6048.6  256.72
  6058.7  257.42  6070.6  261.89  6080.2  263.82  6093.6  263.03  6120.9   264.7
#Mann= 5 ,-1 , 0
  4301.3     .05       0  4659.2      .1       0  4956.1     .05       0
  5134.1      .1       0  5142.4     .05       0
Bank Sta=4956.1,5140.7
XS Rating Curve= 0 ,0
Exp/Cntr=0.3,0.1

Type RM Length L Ch R = 1 ,60928   ,549,549,549
BEGIN DESCRIPTION:
UNT001 IN PECR 111.0
END DESCRIPTION:
XS GIS Cut Line= 3
      2265837.71     13253796.83      2265537.72     13253246.85
      2265037.72     13252646.85
#Sta/Elev= 30
  4352.4  256.13  4360.4  255.06  4375.2  254.71  4463.9  248.87  4523.2  245.91
  4535.1  244.43  4573.1  242.86  4580.2  241.98  4682.7  236.74  4692.7  236.88
    4744  234.56    4808  233.34  4853.6  231.63  4899.1  229.06  4965.1  227.71
  4970.8  226.49  4989.5  225.44  4992.3  224.94  4995.5  225.44  5035.5  227.91
  5113.6  230.07  5163.1  232.18  5269.8  233.44  5323.9  233.39  5405.2  236.18
  5525.6  242.96  5553.6  243.98  5681.8  251.38  5695.5  252.62  5759.9  255.73
#Mann= 5 ,-1 , 0
  4352.4     .05       0    4744      .1       0  4989.5     .07       0
  4995.5      .1       0  5323.9     .05       0
Bank Sta=4965.1,5035.5
XS Rating Curve= 0 ,0
Exp/Cntr=0.3,0.1

Type RM Length L Ch R = 1 ,60379   ,409,409,409
BEGIN DESCRIPTION:
UNT001 IN PECR 110.0
END DESCRIPTION:
XS GIS Cut Line= 3
       2266019.1     13253820.32      2266106.51     13253053.65
      2265237.74     13252296.87
#Sta/Elev= 30
  3980.6  256.58    4125  249.95  4150.4  249.56  4165.3  249.81  4184.7  248.06
    4300  243.52  4356.5  243.01  4381.7  241.72  4631.9  236.47  4756.1  231.12
  4841.6  229.93  4911.8  226.29  4968.8  226.41  5000.9  223.15  5003.7  222.65
  5006.9  223.15    5040   224.8  5054.2  226.77  5075.1  228.52  5111.2  229.78
  5160.6  231.01  5249.3  230.62  5387.2  231.71  5476.6  234.06  5570.9  238.52
  5649.5  243.19  5691.6  246.66  5741.6   249.9  5809.6  256.05  5904.4  262.75
#Mann= 12 ,-1 , 0
  3980.6     .05       0  4150.4      .1       0    4300     .05       0
  4381.7      .1       0  5000.9     .07       0  5006.9      .1       0
  5111.2     .05       0  5249.3      .1       0  5476.6     .05       0
  5570.9      .1       0  5691.6     .08       0  5809.6     .05       0
Bank Sta=4968.8,5054.2
XS Rating Curve= 0 ,0
Exp/Cntr=0.3,0.1

Type RM Length L Ch R = 1 ,59970   ,515,515,515
BEGIN DESCRIPTION:
UNT001 IN PECR 109.0
END DESCRIPTION:
XS GIS Cut Line= 3
      2266787.75     13253246.88      2266159.72     13252648.43
      2265425.32     13252002.58
#Sta/Elev= 30
  4341.5  266.89  4394.1   263.7  4490.4  257.36    4526  254.36  4638.2  246.33
    4766     238  4843.7  231.19  4921.7  226.93  4996.4   222.4  4999.1   221.9
  5002.4   222.4  5013.5  222.41  5020.4  223.99  5034.6  224.83  5098.5  226.87
  5119.5  229.09  5134.3  229.39    5304  230.67  5482.6  229.72  5629.5   230.5
  5657.9  232.26  5664.6  234.05  5693.1  236.59  5813.6  239.08  5835.4  238.49
    5888  240.85  6005.2  248.73  6054.5  250.55  6062.1  252.05    6187  254.81
#Mann= 10 ,-1 , 0
  4341.5      .1       0  4394.1     .05       0  4490.4      .1       0
    4526     .05       0  4638.2      .1       0  4996.4     .07       0
  5002.4      .1       0  5134.3     .05       0  5482.6      .1       0
    5888     .05       0
Bank Sta=4921.7,5098.5
XS Rating Curve= 0 ,0
Exp/Cntr=0.3,0.1

Type RM Length L Ch R = 1 ,59455   ,481,481,481
BEGIN DESCRIPTION:
UNT001 IN PECR 108.0
END DESCRIPTION:
XS GIS Cut Line= 3
      2266964.57     13253140.74      2266773.27     13252773.23
      2266557.05     13251299.93
#Sta/Elev= 30
    4328  267.68  4439.9  263.79  4674.5  245.86  4737.5  240.61  4749.9  240.21
  4758.9  238.97  4789.2   237.5  4819.8  234.27  4859.9  231.66  4890.3  228.48
  4940.8  225.57  4954.3  223.55  4998.4  221.33  5001.2  220.83  5004.4  221.33
  5011.5  222.24  5041.9  223.45  5072.2  223.46  5112.6  225.39  5142.9  226.19
  5193.5  224.96  5228.5  226.99  5284.4  226.86  5457.7  228.75  5587.7  230.42
  5769.6  230.41  5870.7  234.48  6062.7  245.35  6120.9  249.65  6231.4  254.81
#Mann= 5 ,-1 , 0
    4328     .05       0  4674.5      .1       0  4998.4     .07       0
  5004.4      .1       0  5457.7     .05       0
Bank Sta=4940.8,5112.6
XS Rating Curve= 0 ,0
Exp/Cntr=0.3,0.1

Type RM Length L Ch R = 1 ,58974   ,341,341,341
BEGIN DESCRIPTION:
UNT001 IN PECR 107.0
END DESCRIPTION:
XS GIS Cut Line= 4
      2267181.06     13252596.97      2267095.49     13252400.66
      2266813.54     13251554.83      2266768.57     13251309.96
#Sta/Elev= 30
  4499.7  253.08  4541.8  252.64  4570.7  250.49  4576.2  248.92  4587.1  248.49
  4608.9  245.59    4623  245.13  4675.3  239.92  4723.8  237.42  4786.1  233.56
  4833.8  229.31  4844.1   229.2  4854.9   226.9  4918.1  223.35    4939   223.6
  4944.2  222.75  4970.6  222.18  4975.9  220.12  4988.9  219.47  4991.7  218.97
  4994.9  219.47  5102.3  224.02  5234.9  226.98  5508.2  229.21  5571.4  231.97
  5694.9  239.12  5766.1  245.02  5778.7  246.95  5837.2  251.21  5854.4  251.71
#Mann= 5 ,-1 , 0
  4499.7     .05       0  4723.8      .1       0  4988.9     .07       0
  4994.9      .1       0  5234.9     .05       0
Bank Sta=4939,5102.3
XS Rating Curve= 0 ,0
Exp/Cntr=0.3,0.1

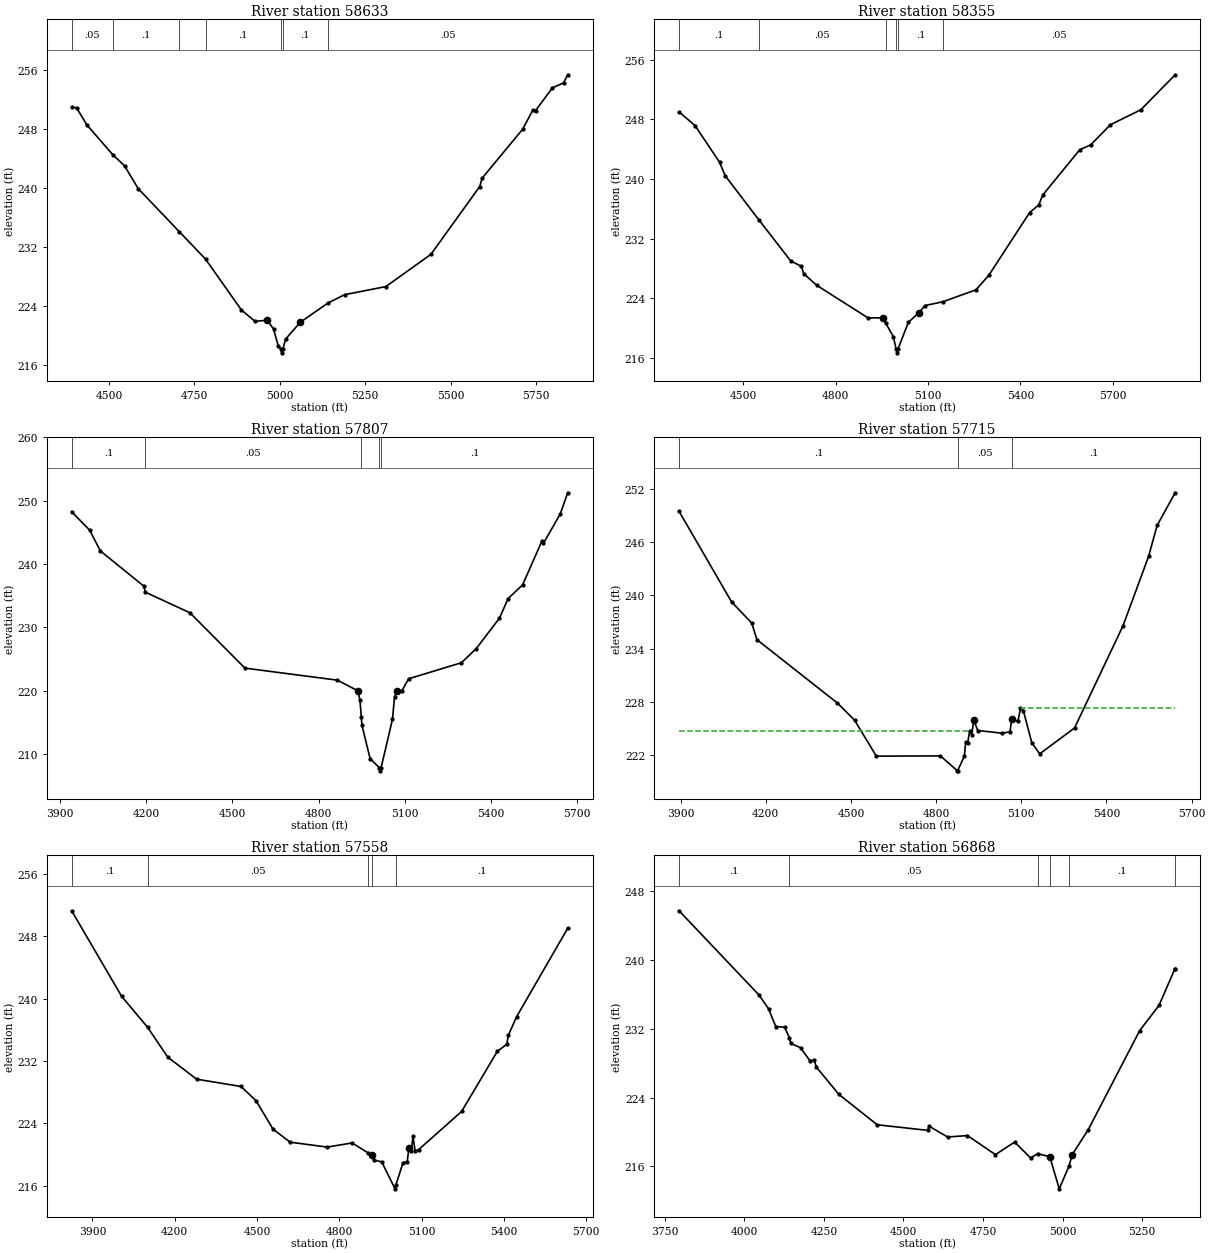
Type RM Length L Ch R = 1 ,58633   ,278,278,278
BEGIN DESCRIPTION:
UNT001 IN PECR 106.0
END DESCRIPTION:
XS GIS Cut Line= 4
      2267322.05     13252481.23      2267347.22     13252143.89
      2267055.21     13251413.86      2266899.15      13251126.9
#Sta/Elev= 30
    4391  251.01  4405.4  250.92  4435.5   248.6  4511.7  244.53  4545.8  243.04
  4585.9  239.93  4706.3  234.07  4782.6  230.37  4887.6  223.45  4927.6   221.9
    4963  222.07  4981.5  220.88  4995.3  218.58  5002.7  218.13  5005.4  217.63
  5008.7  218.13  5016.9   219.5  5059.5  221.77  5139.8  224.37  5189.2  225.53
    5310  226.63  5441.9  231.01  5584.8  240.23  5591.8  241.37  5710.2     248
  5739.8  250.59  5748.2  250.55  5797.6  253.64  5829.9  254.31  5842.2  255.41
#Mann= 7 ,-1 , 0
    4391     .05       0  4511.7      .1       0  4706.3     .05       0
  4782.6      .1       0  5002.7     .07       0  5008.7      .1       0
  5139.8     .05       0
Bank Sta=4963,5059.5
XS Rating Curve= 0 ,0
Exp/Cntr=0.3,0.1

Type RM Length L Ch R = 1 ,58355   ,548,548,548
BEGIN DESCRIPTION:
UNT001 IN PECR 105.0
END DESCRIPTION:
XS GIS Cut Line= 4
       2267503.3     13252435.92      2267568.75     13252103.61
       2267372.4     13251293.02      2267055.67     13250991.38
#Sta/Elev= 30
    4292  249.02  4343.9  247.17  4423.5  242.25  4441.5  240.45  4550.3  234.54
  4654.7  228.97  4689.1  228.26  4696.5  227.28  4738.3  225.72  4905.2  221.33
  4952.5  221.34  4962.3  220.65  4987.5  218.81  4996.5  217.13  4999.3  216.63
  5002.5  217.13  5036.2  220.73  5069.8  222.01  5090.4  222.99  5147.7  223.49
  5255.6   225.1  5297.4  227.06  5429.9  235.49  5459.5  236.52  5472.2  237.84
  5592.7  243.94    5628  244.59  5691.8  247.29  5790.6   249.3  5902.1  254.01
#Mann= 6 ,-1 , 0
    4292      .1       0  4550.3     .05       0  4962.3      .1       0
  4996.5     .07       0  5002.5      .1       0  5147.7     .05       0
Bank Sta=4952.5,5069.8
XS Rating Curve= 0 ,0
Exp/Cntr=0.3,0.1

Type RM Length L Ch R = 1 ,57807   ,92,92,92
BEGIN DESCRIPTION:
Mapping XS 5d56d4dd
END DESCRIPTION:
XS GIS Cut Line= 4
       2267956.6     13252596.37      2268055.56     13251622.39
      2267935.76     13251507.81      2267873.38     13250930.73
#Sta/Elev= 30
  3941.4  248.26  4004.1  245.34  4041.4  242.06  4192.2  236.52  4197.6  235.56
    4353  232.29    4544  223.56  4865.6  221.66  4936.9  219.97  4944.1  218.46
  4948.6   215.9    4951  214.54  4979.4  209.24  5011.6  207.84  5014.3  207.34
  5017.6  207.84    5057  215.46  5064.3  218.98  5071.2  219.92  5089.2  219.95
  5113.4  221.88  5296.9  224.41  5348.6  226.65  5429.1  231.45  5459.3  234.55
  5509.6   236.7  5577.3  243.68  5582.3  243.28  5640.3  247.88  5666.6  251.25
#Mann= 5 ,-1 , 0
  3941.4      .1       0  4197.6     .05       0  4948.6      .1       0
  5011.6     .07       0  5017.6      .1       0
Bank Sta=4936.9,5071.2
XS Rating Curve= 0 ,0
Exp/Cntr=0.3,0.1

Type RM Length L Ch R = 1 ,57715   ,157,157,157
BEGIN DESCRIPTION:
UNT001 IN PECR 104.0
END DESCRIPTION:
XS GIS Cut Line= 4
      2268029.52     13252580.71      2268149.31     13251585.93
      2268008.68     13251455.73      2267967.01     13250903.61
#Sta/Elev= 30
  3894.6  249.51  4079.8  239.26  4150.3  236.89  4168.9     235  4452.5  227.83
  4512.9  225.89  4589.5  221.83  4815.1  221.86  4875.2  220.17  4875.7  220.17
  4899.6  221.85  4904.1  223.44  4911.4  223.37  4918.2  224.71  4925.6  224.23
  4932.4  225.94  4946.6  224.73  5031.6  224.43    5060  224.58  5066.8  226.03
  5088.2  225.77  5097.1  227.24  5107.1  226.99  5137.2  223.33  5164.9  222.09
  5287.6  225.02  5458.1  236.56  5548.4  244.42  5578.5  247.93  5641.9  251.61
#Mann= 3 ,-1 , 0
  3894.6      .1       0  4875.7     .05       0  5066.8      .1       0
#XS Ineff= 2 , 0
       0 4918.33  224.72  5099.8       0  227.25
Permanent Ineff=
       T       T
Bank Sta=4932.4,5066.8
XS Rating Curve= 0 ,0
Exp/Cntr=0.3,0.1

Type RM Length L Ch R = 1 ,57558   ,690,690,690
BEGIN DESCRIPTION:
UNT001 IN PECR 103.0
END DESCRIPTION:
XS GIS Cut Line= 4
      2268087.72     13252596.88      2268258.68     13251518.23
      2268138.89     13251346.35      2268092.05     13250841.54
#Sta/Elev= 30
  3824.3   251.3  4006.6  240.31  4101.4  236.33  4174.6  232.51  4279.9  229.68
  4441.9  228.74  4496.3  226.92  4558.7  223.25    4621  221.59  4755.8  220.96
  4846.9  221.49  4904.2  220.23  4920.3     220  4925.5  219.29  4954.7  219.07
  5003.2   215.6  5006.4   216.1  5032.8  218.98  5047.7  219.08  5053.8  220.83
  5062.5   220.4  5068.6  222.35  5076.5  220.47  5089.5  220.64  5245.9  225.53
  5376.5  233.27  5410.4  234.15  5416.7  235.33  5446.8  237.72  5632.9  249.06
#Mann= 5 ,-1 , 0
  3824.3      .1       0  4101.4     .05       0  4904.2      .1       0
  4920.3     .05       0  5006.4      .1       0
Bank Sta=4920.3,5053.8
XS Rating Curve= 0 ,0
Exp/Cntr=0.3,0.1

Type RM Length L Ch R = 1 ,56868   ,704,704,704
BEGIN DESCRIPTION:
UNT001 IN PECR 102.0
END DESCRIPTION:
XS GIS Cut Line= 3
      2268987.72      13252596.9      2268887.72     13251396.85
      2268837.71     13251046.81
#Sta/Elev= 30
  3795.4  245.71  4046.3  235.92  4076.4  234.31    4099  232.25  4126.6  232.18
    4142  230.94  4146.7  230.28  4176.8  229.79  4206.9  228.24  4219.4  228.36
  4226.9  227.52  4297.2  224.36  4417.6  220.83  4575.6  220.18  4580.7  220.66
  4638.4  219.41  4701.1  219.57  4788.9  217.36  4849.1  218.82  4899.3  216.97
  4921.6  217.47  4959.5  217.12  4989.3  213.38  5019.8  216.02  5029.9  217.35
  5080.4  220.27    5242  231.79  5302.6  234.71  5352.2  238.95  5353.2  238.95
#Mann= 6 ,-1 , 0
  3795.4      .1       0    4142     .05       0  4921.6      .1       0
  4959.5     .05       0  5019.8      .1       0  5352.2     .05       0
Bank Sta=4959.5,5029.9
XS Rating Curve= 0 ,0
Exp/Cntr=0.3,0.1

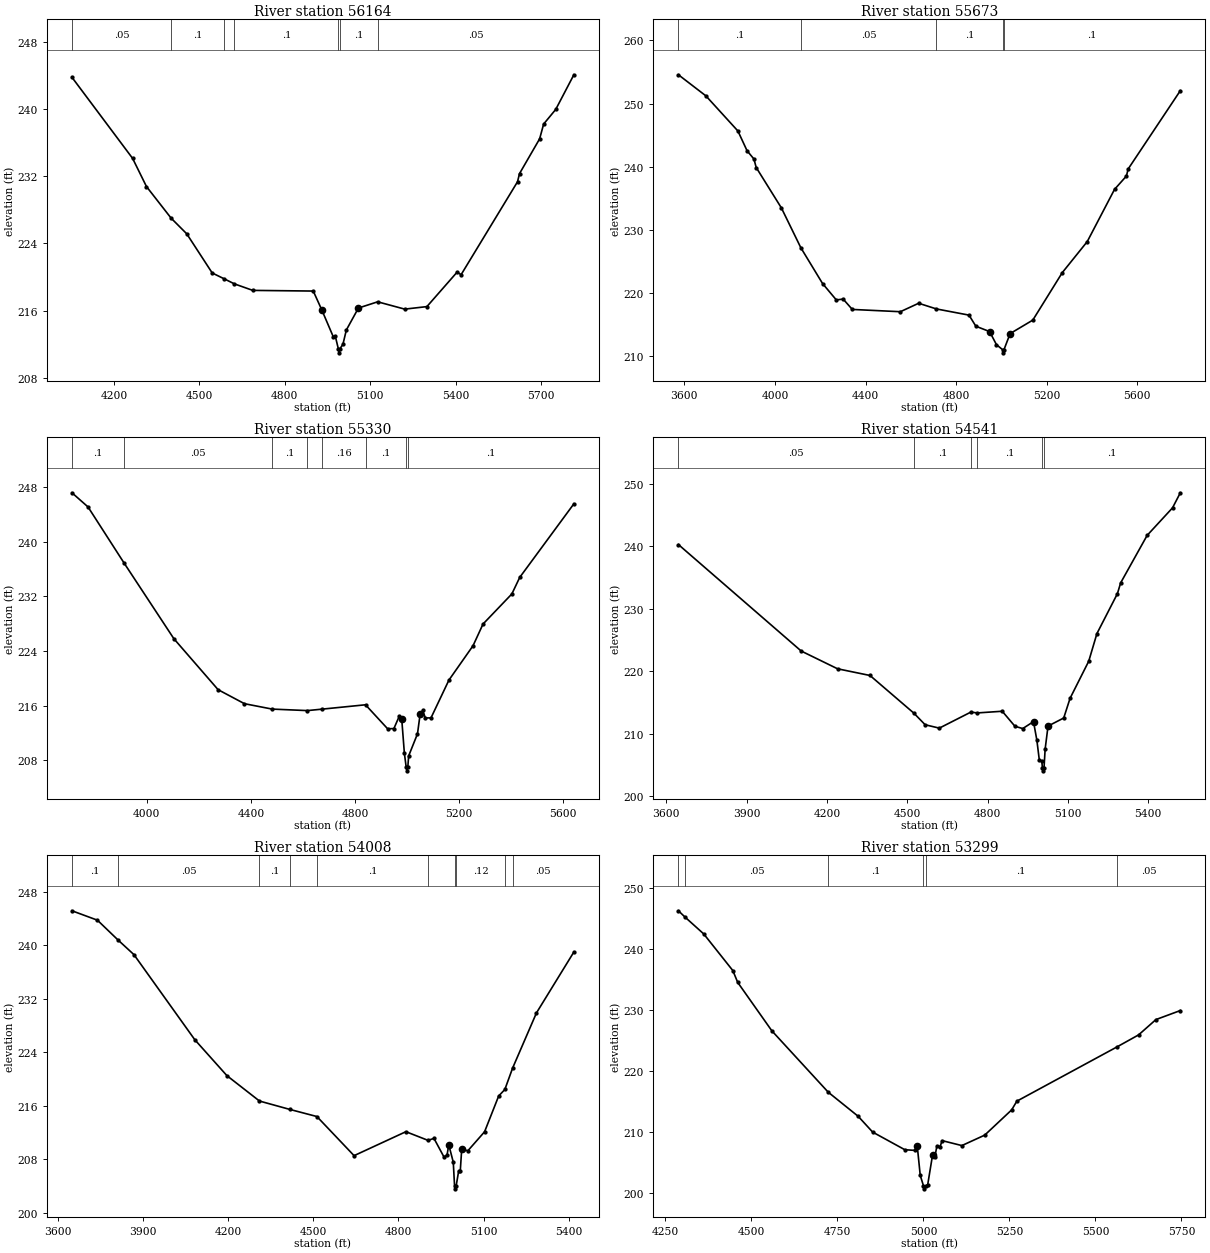
Type RM Length L Ch R = 1 ,56164   ,491,491,491
BEGIN DESCRIPTION:
UNT001 IN PECR 101.0
END DESCRIPTION:
XS GIS Cut Line= 3
      2269592.01     13252466.14      2269459.74     13251527.81
      2268887.72     13250946.86
#Sta/Elev= 30
  4052.4  243.76  4265.5  234.11  4314.2  230.76  4400.8     227  4455.6  225.14
  4545.1  220.48  4588.1  219.77  4623.3  219.18  4687.5  218.41    4900  218.33
  4930.3  216.06  4970.7  212.86  4977.2  212.99  4987.9  211.48  4990.6  210.98
  4993.9  211.48  5004.2  211.99  5016.2   213.7  5058.6  216.31  5126.2  217.05
  5221.3  216.18  5299.1  216.48  5405.2  220.58  5419.3  220.28  5617.4  231.33
  5624.4   232.3  5695.1  236.44  5709.2   238.2  5751.7  239.94  5815.3  244.06
#Mann= 7 ,-1 , 0
  4052.4     .05       0  4400.8      .1       0  4588.1     .05       0
  4623.3      .1       0  4987.9     .07       0  4993.9      .1       0
  5126.2     .05       0
Bank Sta=4930.3,5058.6
XS Rating Curve= 0 ,0
Exp/Cntr=0.3,0.1

Type RM Length L Ch R = 1 ,55673   ,343,343,343
BEGIN DESCRIPTION:
UNT001 IN PECR 100.0
END DESCRIPTION:
XS GIS Cut Line= 3
      2270037.71     13252646.81      2269837.72     13251246.85
      2269887.72     13250446.88
#Sta/Elev= 30
  3573.9  254.56  3695.1  251.22  3836.5  245.65  3876.9  242.52  3907.2  241.21
  3917.3  239.86  4028.4  233.46  4114.5  227.13  4210.2  221.47  4270.9  218.87
  4301.2     219  4341.6  217.36  4553.7     217  4634.5  218.34  4712.8  217.44
  4856.7  216.46    4887   214.7  4947.7  213.85    4978  211.77  5005.1  210.98
  5007.9  210.48  5011.1  210.98  5038.2  213.53  5138.4  215.67  5268.6   223.2
  5378.8  228.12  5499.1  236.39  5551.7  238.51  5559.2  239.62  5789.6  252.04
#Mann= 5 ,-1 , 0
  3573.9      .1       0  4114.5     .05       0  4712.8      .1       0
  5005.1     .07       0  5011.1      .1       0
Bank Sta=4947.7,5038.2
XS Rating Curve= 0 ,0
Exp/Cntr=0.3,0.1

Type RM Length L Ch R = 1 ,55330   ,789,789,789
BEGIN DESCRIPTION:
UNT001 IN PECR 99.0
END DESCRIPTION:
XS GIS Cut Line= 3
       2270276.3     13252428.56      2270261.54     13251933.86
      2270084.52     13250510.35
#Sta/Elev= 30
  3712.1  247.18  3773.8  245.11  3911.9  236.93    4104  225.81    4274  218.35
  4375.3   216.3  4481.8  215.51  4617.2  215.29    4673   215.5  4840.6  216.14
  4925.6  212.63  4949.7  212.66  4969.9  214.43  4979.9  214.02    4990  209.05
  4997.1  206.97  4999.8  206.47  5003.1  206.97  5006.5  208.66  5040.4  211.89
  5050.5  214.76  5060.6  215.32  5070.6  214.22  5092.3  214.22  5161.3  219.76
    5254  224.79  5292.3  227.96  5403.2  232.37  5433.4  234.79  5641.5  245.56
#Mann= 8 ,-1 , 0
  3712.1      .1       0  3911.9     .05       0  4481.8      .1       0
  4617.2     .05       0    4673     .16       0  4840.6      .1       0
  4997.1     .07       0  5003.1      .1       0
Bank Sta=4979.9,5050.5
XS Rating Curve= 0 ,0
Exp/Cntr=0.3,0.1

Type RM Length L Ch R = 1 ,54541   ,533,533,533
BEGIN DESCRIPTION:
UNT001 IN PECR 98.0
END DESCRIPTION:
XS GIS Cut Line= 3
      2270519.97     13252295.65      2270652.87     13251668.04
      2271132.56     13250531.55
#Sta/Elev= 30
    3645  240.27  4103.7  223.24  4239.6   220.4  4360.8  219.33  4524.8   213.3
  4566.8  211.45  4619.7  210.91  4737.8  213.48    4761  213.34  4854.8  213.61
  4902.2  211.21  4931.3  210.84  4971.6  211.95  4984.2  208.97  4993.3  205.81
  5002.5  205.66  5004.9  204.58  5007.7  204.08  5010.9  204.58  5015.1  207.56
  5025.9  211.24  5084.5  212.53  5108.2  215.68  5177.9  221.61  5208.5  226.03
    5285  232.41  5297.3  234.15  5396.2  241.74    5491  246.14  5520.1  248.55
#Mann= 6 ,-1 , 0
    3645     .05       0  4524.8      .1       0  4737.8     .16       0
    4761      .1       0  5004.9     .07       0  5010.9      .1       0
Bank Sta=4971.6,5025.9
XS Rating Curve= 0 ,0
Exp/Cntr=0.3,0.1

Type RM Length L Ch R = 1 ,54008   ,709,709,709
BEGIN DESCRIPTION:
UNT001 IN PECR 97.0
END DESCRIPTION:
XS GIS Cut Line= 3
      2270787.74     13252496.82      2271337.72     13251246.85
      2271537.71     13250896.87
#Sta/Elev= 30
  3649.5   245.2  3739.3  243.79  3811.7  240.83    3868  238.63  4082.5  225.88
  4195.7   220.5  4310.4   216.7  4416.9  215.45  4512.7  214.38  4643.7  208.52
  4826.4  212.11  4904.4  210.81  4925.2  211.11  4960.5  208.32  4971.4  208.62
  4977.4  210.15  4993.3  207.54  4997.7  204.05  5000.5  203.55  5003.7  204.05
  5012.4  206.25    5018  206.25    5023   209.5  5044.6  209.25  5103.6   212.1
  5153.3  217.46    5175  218.43  5202.3  221.63  5286.5  229.91  5418.2  239.02
#Mann= 10 ,-1 , 0
  3649.5      .1       0  3811.7     .05       0  4310.4      .1       0
  4416.9     .16       0  4512.7      .1       0  4904.4     .12       0
  4997.7     .07       0  5003.7     .12       0    5175      .1       0
  5202.3     .05       0
Bank Sta=4977.4,5023
XS Rating Curve= 0 ,0
Exp/Cntr=0.3,0.1

Type RM Length L Ch R = 1 ,53299   ,479,479,479
BEGIN DESCRIPTION:
UNT001 IN PECR 96.0
END DESCRIPTION:
XS GIS Cut Line= 4
      2271029.41     13252502.43      2271310.02     13252199.67
      2271701.35     13251601.59       2271767.8     13251276.74
#Sta/Elev= 30
  4287.8  246.29  4306.9  245.26  4361.5  242.49    4446  236.49  4460.2  234.55
  4559.4  226.62  4723.5  216.55  4810.3  212.61  4852.5  210.02    4946  207.13
  4976.2  207.02  4982.1  207.77  4990.8  202.93  5000.2  201.22    5003  200.72
  5006.2  201.22  5012.4  201.36  5026.6  206.26  5033.4  205.98  5039.4  207.78
  5048.5  207.64  5054.5  208.62  5111.8  207.81  5178.2  209.52  5256.6  213.66
  5271.7  215.09  5562.8  223.98  5625.6  225.95    5676  228.46  5746.9  229.94
#Mann= 6 ,-1 , 0
  4287.8      .1       0  4306.9     .05       0  4723.5      .1       0
  5000.2     .07       0  5006.2      .1       0  5562.8     .05       0
Bank Sta=4982.1,5026.6
XS Rating Curve= 0 ,0
Exp/Cntr=0.3,0.1

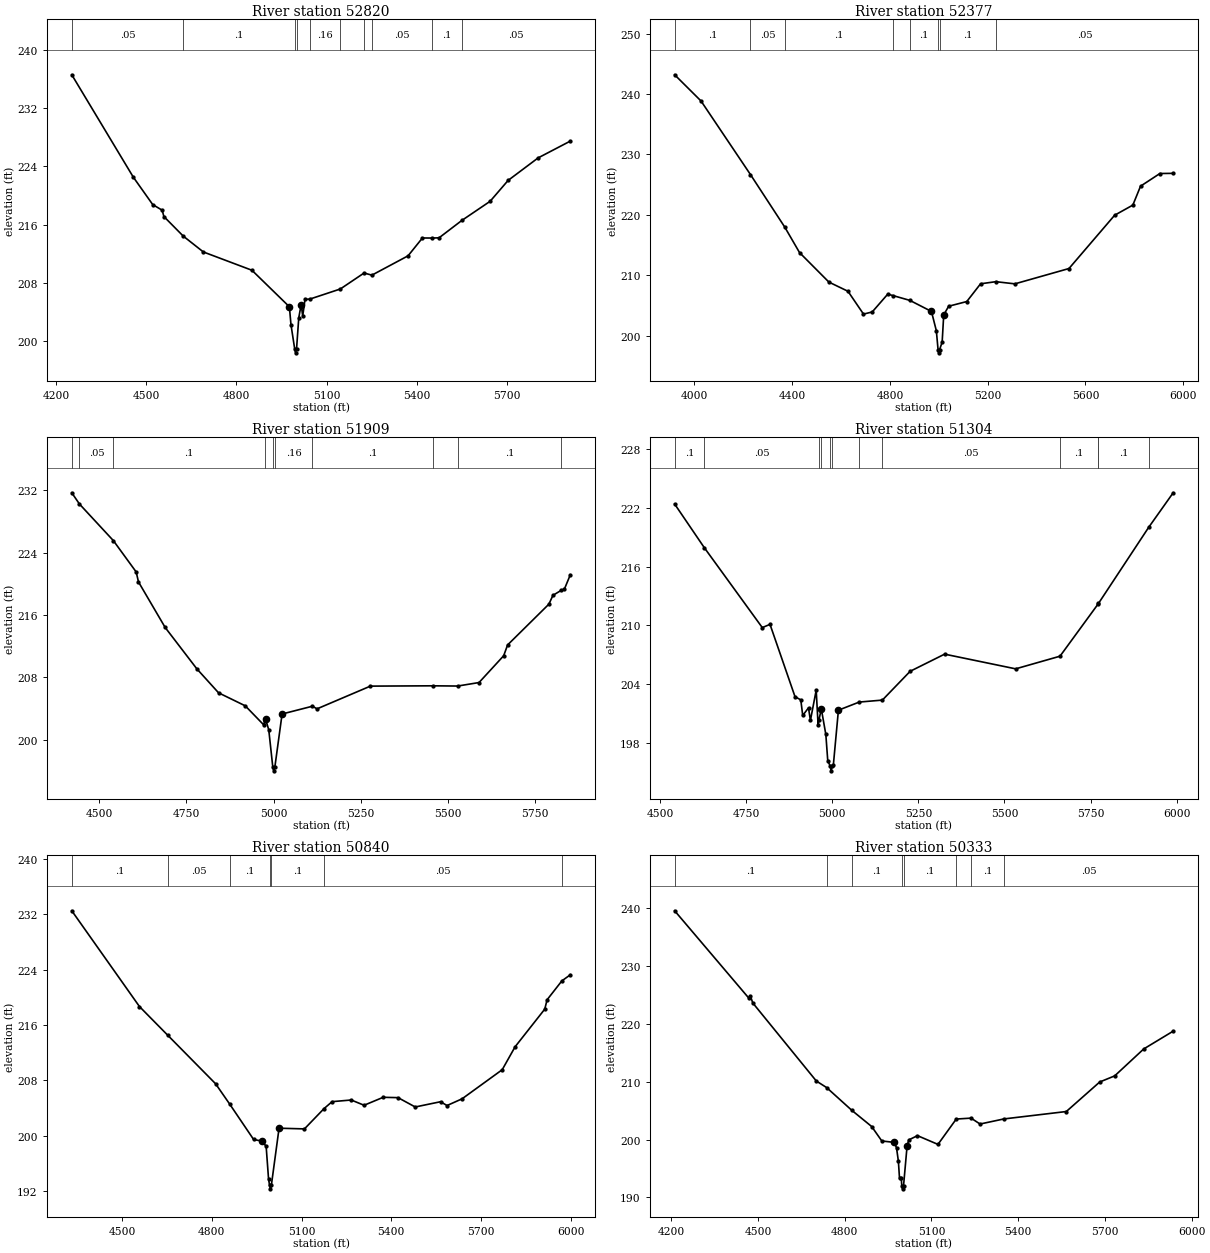
Type RM Length L Ch R = 1 ,52820   ,443,443,443
BEGIN DESCRIPTION:
UNT001 IN PECR 95.0
END DESCRIPTION:
XS GIS Cut Line= 4
      2271406.03     13252805.12       2271723.5     13252620.54
       2271952.4     13251815.72       2271952.4     13251359.89
#Sta/Elev= 30
  4251.8  236.55  4456.7   222.5  4521.3  218.74  4552.7  217.97  4558.5   217.1
  4622.8  214.42  4689.9  212.24  4851.6  209.73  4976.3  204.72  4981.6  202.26
  4994.1   198.9  4996.9   198.4  5000.1   198.9  5007.5   203.2  5015.5  205.03
  5020.7  203.45  5028.3  205.74  5044.1  205.77  5145.9  207.16  5224.9  209.35
    5251  209.06  5371.4  211.71  5419.3  214.16  5451.4  214.15  5474.6  214.18
  5550.3  216.56  5644.6  219.19  5704.6  222.06  5804.6  225.15  5911.6  227.45
#Mann= 10 ,-1 , 0
  4251.8     .05       0  4622.8      .1       0  4994.1     .07       0
  5000.1      .1       0  5044.1     .16       0  5145.9     .05       0
  5224.9      .1       0    5251     .05       0  5451.4      .1       0
  5550.3     .05       0
Bank Sta=4976.3,5015.5
XS Rating Curve= 0 ,0
Exp/Cntr=0.3,0.1

Type RM Length L Ch R = 1 ,52377   ,468,468,468
BEGIN DESCRIPTION:
UNT001 IN PECR 94.0
END DESCRIPTION:
XS GIS Cut Line= 4
       2272904.9     13253152.17      2272543.09     13252775.59
       2272269.9     13252487.63      2272159.14     13251372.68
#Sta/Elev= 30
  3919.2   243.2    4027  238.86  4229.3  226.67  4370.3  217.92  4430.1  213.74
  4550.3  208.85  4628.3  207.33  4691.8  203.55  4727.4   203.9  4790.9  206.85
    4814   206.6  4881.5  205.82  4969.8  203.99  4989.9  200.78  4996.9  197.63
  4999.7  197.13  5002.9  197.63  5013.6  198.91    5020  203.41  5040.1  204.85
  5114.4  205.63  5170.8  208.57  5233.3  208.92    5311  208.56  5532.5   211.1
  5719.3  219.93  5793.8  221.61  5825.2  224.74  5904.4  226.84  5958.8  226.87
#Mann= 8 ,-1 , 0
  3919.2      .1       0  4229.3     .05       0  4370.3      .1       0
    4814     .16       0  4881.5      .1       0  4996.9     .07       0
  5002.9      .1       0  5233.3     .05       0
Bank Sta=4969.8,5020
XS Rating Curve= 0 ,0
Exp/Cntr=0.3,0.1

Type RM Length L Ch R = 1 ,51909   ,605,605,605
BEGIN DESCRIPTION:
UNT001 IN PECR 93.0
END DESCRIPTION:
XS GIS Cut Line= 2
      2272937.72     13252846.84      2272380.74     13251530.96
#Sta/Elev= 30
  4421.7   231.7  4443.6  230.26    4541  225.55  4606.3  221.53  4612.9  220.25
  4689.4   214.4    4780   209.1  4842.4  206.01  4918.9  204.34  4971.7   201.9
  4975.5  202.41  4977.1  202.62  4986.3  201.26  4997.8  196.49  5000.5  195.99
  5003.8  196.49  5024.5  203.29  5111.6  204.29  5124.6  203.95  5277.6  206.87
  5456.3  206.91  5527.7  206.88    5589  207.33  5659.6  210.77  5670.9  212.16
  5789.3   217.4  5800.8  218.53  5825.3  219.19  5833.3  219.29  5850.6  221.17
#Mann= 10 ,-1 , 0
  4421.7      .1       0  4443.6     .05       0    4541      .1       0
  4975.5     .16       0  4997.8     .07       0  5003.8     .16       0
  5111.6      .1       0  5456.3     .05       0  5527.7      .1       0
  5825.3     .05       0
Bank Sta=4977.1,5024.5
XS Rating Curve= 0 ,0
Exp/Cntr=0.3,0.1

Type RM Length L Ch R = 1 ,51304   ,464,464,464
BEGIN DESCRIPTION:
UNT001 IN PECR 92.0
END DESCRIPTION:
XS GIS Cut Line= 3
      2273637.76     13252246.87      2273237.72     13252046.85
      2272437.68     13251446.83
#Sta/Elev= 30
  4542.5  222.39  4628.3  217.95  4796.9  209.78  4819.3  210.11  4891.9  202.73
  4908.7   202.4  4914.3  200.81  4931.1  201.59  4936.6   200.3  4953.4  203.39
    4959  199.81  4961.5  200.37  4968.3  201.48  4981.4  198.87    4987  196.18
    4994  195.66  4996.8  195.16    5000  195.66  5003.3  195.78  5017.9  201.35
  5078.4  202.18  5145.5  202.38  5226.2  205.32  5326.2  207.07  5532.5  205.57
  5661.2  206.86  5772.5  212.22  5772.8  212.24  5918.8  220.02  5989.8  223.54
#Mann= 12 ,-1 , 0
  4542.5      .1       0  4628.3     .05       0  4961.5     .16       0
  4968.3     .05       0    4994     .04       0    5000     .05       0
  5078.4      .1       0  5145.5     .05       0  5661.2      .1       0
  5772.5     .05       0  5772.8      .1       0  5918.8     .05       0
Bank Sta=4968.3,5017.9
XS Rating Curve= 0 ,0
Exp/Cntr=0.3,0.1

Type RM Length L Ch R = 1 ,50840   ,507,507,507
BEGIN DESCRIPTION:
UNT001 IN PECR 91.0
END DESCRIPTION:
XS GIS Cut Line= 3
      2273987.73     13252146.87      2273537.72     13251696.85
      2272737.71     13251046.85
#Sta/Elev= 30
  4331.7  232.51    4558  218.66  4652.3  214.52  4812.6  207.49  4859.9  204.54
  4939.8  199.43  4968.1  199.19  4981.7  198.44  4989.7  193.75  4993.1  192.79
  4995.9  192.29  4999.1  192.79  5024.9  201.06  5109.8  200.96  5175.4   203.9
  5202.3   204.9  5266.2  205.14  5309.3  204.38  5373.2  205.53  5422.8  205.48
  5480.3  204.13    5565  204.89  5586.6  204.34  5636.9  205.31  5771.2  209.52
  5814.3  212.84  5913.4  218.28  5921.3  219.64  5970.7  222.37  5998.9  223.25
#Mann= 7 ,-1 , 0
  4331.7      .1       0  4652.3     .05       0  4859.9      .1       0
  4993.1     .07       0  4999.1      .1       0  5175.4     .05       0
  5970.7      .1       0
Bank Sta=4968.1,5024.9
XS Rating Curve= 0 ,0
Exp/Cntr=0.3,0.1

Type RM Length L Ch R = 1 ,50333   ,526,526,526
BEGIN DESCRIPTION:
UNT001 IN PECR 90.0
END DESCRIPTION:
XS GIS Cut Line= 3
      2274387.75     13251946.88      2273887.72     13251346.85
      2273087.69     13250846.83
#Sta/Elev= 30
  4211.6  239.53  4467.4  224.48  4473.9  224.79  4481.7  223.61  4701.7  210.11
  4737.3  208.98  4824.8  205.03  4893.1  202.25  4928.2  199.75  4971.2  199.51
    4979  198.59  4985.5  196.27  4989.4  193.31  4995.6  193.31  4997.3  191.98
  5000.1  191.48  5003.3  191.98  5015.7  198.93  5021.6  199.94  5051.6  200.67
  5122.4  199.16  5185.7  203.54  5236.9   203.7    5268  202.68  5350.6  203.56
  5566.4  204.84  5681.9  209.94  5733.8     211  5834.1  215.65  5936.1  218.73
#Mann= 8 ,-1 , 0
  4211.6      .1       0  4737.3     .05       0  4824.8      .1       0
  4997.3     .07       0  5003.3      .1       0  5185.7     .05       0
  5236.9      .1       0  5350.6     .05       0
Bank Sta=4971.2,5015.7
XS Rating Curve= 0 ,0
Exp/Cntr=0.3,0.1

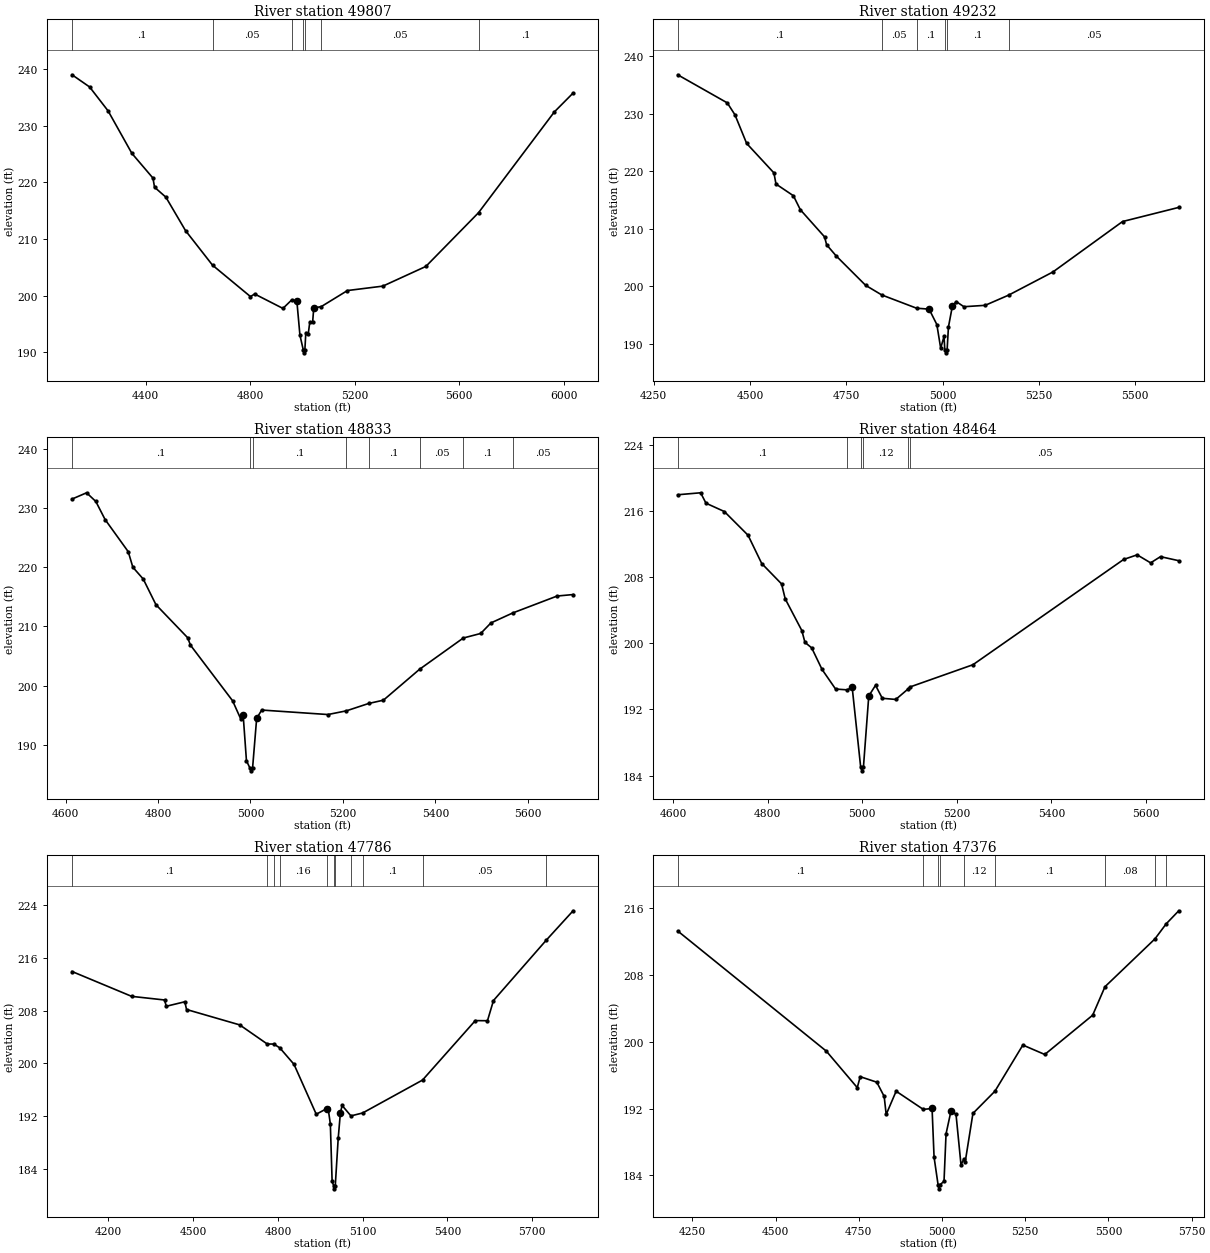
Type RM Length L Ch R = 1 ,49807   ,575,575,575
BEGIN DESCRIPTION:
UNT001 IN PECR 89.0
END DESCRIPTION:
XS GIS Cut Line= 3
      2274687.71     13251746.84      2274237.72     13250946.85
       2273637.7     13250146.83
#Sta/Elev= 30
  4117.6  239.03  4184.8  236.88  4255.6  232.65  4346.7  225.14  4427.4  220.77
  4433.4  219.16  4476.8   217.4    4552  211.49  4655.4  205.38  4800.6  199.83
  4816.5  200.29  4924.9  197.74  4958.2  199.23  4978.1  199.07  4989.9  193.02
  5002.8  190.39  5005.6  189.89  5008.8  190.39  5012.5  193.47  5021.8  193.26
  5027.5  195.26  5038.6  195.35  5042.8  197.81  5071.9  198.07  5171.9   200.9
  5307.3  201.68  5471.9  205.16  5673.6  214.66  5963.6  232.46  6035.5   235.8
#Mann= 7 ,-1 , 0
  4117.6      .1       0  4655.4     .05       0  4958.2      .1       0
  5002.8     .07       0  5008.8      .1       0  5071.9     .05       0
  5673.6      .1       0
Bank Sta=4978.1,5042.8
XS Rating Curve= 0 ,0
Exp/Cntr=0.3,0.1

Type RM Length L Ch R = 1 ,49232   ,399,399,399
BEGIN DESCRIPTION:
UNT001 IN PECR 88.0
END DESCRIPTION:
XS GIS Cut Line= 3
      2274861.57     13251623.76       2274802.5     13251239.79
       2274713.9     13250331.68
#Sta/Elev= 30
  4312.4   236.8  4441.1  231.91    4461  229.84  4491.4  224.85  4562.2  219.72
  4567.6  217.78  4612.8  215.74  4630.8  213.31  4693.7  208.58  4699.1   207.2
  4723.9  205.26  4800.4  200.14  4842.2  198.47  4932.6  196.16  4965.1     196
  4985.2  193.32  4995.2   189.2  5003.9  191.25  5005.9  188.89  5008.7  188.39
  5011.9  188.89  5015.3  192.88  5025.4  196.47  5035.4  197.32  5055.5  196.42
  5110.6  196.66  5171.4  198.43  5286.6  202.47  5467.4  211.25  5613.3  213.71
#Mann= 6 ,-1 , 0
  4312.4      .1       0  4842.2     .05       0  4932.6      .1       0
  5005.9     .07       0  5011.9      .1       0  5171.4     .05       0
Bank Sta=4965.1,5025.4
XS Rating Curve= 0 ,0
Exp/Cntr=0.3,0.1

Type RM Length L Ch R = 1 ,48833   ,369,369,369
BEGIN DESCRIPTION:
UNT001 IN PECR 87.0
END DESCRIPTION:
XS GIS Cut Line= 3
      2275238.13     13251328.35      2275230.75     13251121.65
      2274862.15     13250325.47
#Sta/Elev= 30
  4613.9  231.55  4645.4  232.61  4665.4  231.14  4685.4  228.09  4735.5  222.65
  4745.5  220.02    4768  218.02  4795.5  213.68  4864.1   208.1  4870.1  206.85
  4961.3  197.44  4978.7  194.41  4984.2  195.03  4991.3  187.31  4998.6  186.09
  5001.4  185.59  5004.6  186.09  5013.4  194.47  5024.4  195.87  5167.6  195.11
  5207.7  195.74  5255.7  196.98  5287.7  197.54    5366  202.77  5460.5  208.05
  5498.2  208.82  5520.3   210.6  5567.6  212.29  5663.5  215.15  5698.1   215.4
#Mann= 8 ,-1 , 0
  4613.9      .1       0  4998.6     .07       0  5004.6      .1       0
  5207.7     .05       0  5255.7      .1       0    5366     .05       0
  5460.5      .1       0  5567.6     .05       0
Bank Sta=4984.2,5013.4
XS Rating Curve= 0 ,0
Exp/Cntr=0.3,0.1

Type RM Length L Ch R = 1 ,48464   ,678,678,678
BEGIN DESCRIPTION:
UNT001 IN PECR 86.0
END DESCRIPTION:
XS GIS Cut Line= 3
      2275548.25     13251055.21      2275563.02     13250870.61
       2274994.5     13250206.11
#Sta/Elev= 30
  4609.7  217.98  4658.2  218.22  4669.5  216.96  4708.4  215.95  4758.5  213.08
  4787.4  209.66  4829.4  207.19  4837.1  205.38  4872.2  201.55  4878.8  200.12
  4893.1  199.45    4915  196.84  4943.6  194.47  4968.1  194.37  4978.7  194.68
  4996.6  185.07  4999.3  184.57  5002.6  185.07  5013.8  193.63  5028.1  194.92
  5042.4  193.35  5070.9  193.21  5097.2  194.49  5101.5  194.73  5234.1  197.41
  5552.8  210.15  5581.4  210.71  5609.9  209.74  5630.8  210.49  5669.4     210
#Mann= 6 ,-1 , 0
  4609.7      .1       0  4968.1     .12       0  4996.6     .07       0
  5002.6     .12       0  5097.2      .1       0  5101.5     .05       0
Bank Sta=4978.7,5013.8
XS Rating Curve= 0 ,0
Exp/Cntr=0.3,0.1

Type RM Length L Ch R = 1 ,47786   ,410,410,410
BEGIN DESCRIPTION:
UNT001 IN PECR 85.0
END DESCRIPTION:
XS GIS Cut Line= 3
       2275654.5     13250997.42      2276047.43     13250422.39
      2275393.01     13249565.96
#Sta/Elev= 30
  4070.9  213.91    4282  210.15  4398.5   209.6  4404.6  208.65  4470.3  209.33
  4476.4  208.16  4664.7  205.83  4762.1  202.94  4785.4  202.93  4806.7  202.35
  4856.8  199.87  4935.7  192.31  4972.8  193.16  4977.4  193.28  4985.6  190.86
  4991.9  182.15  4997.1  181.52  4999.9  181.02  5003.1  181.52  5013.4  188.64
    5021  192.43  5027.2  193.64  5058.5  192.06    5100   192.5    5312  197.48
  5498.9  206.48    5542  206.46  5563.3  209.52  5750.8  218.68  5845.2   223.1
#Mann= 11 ,-1 , 0
  4070.9      .1       0  4762.1     .16       0  4785.4      .1       0
  4806.7     .16       0  4972.8     .12       0  4997.1     .07       0
  5003.1     .12       0  5058.5     .16       0    5100      .1       0
    5312     .05       0  5750.8      .1       0
Bank Sta=4972.8,5021
XS Rating Curve= 0 ,0
Exp/Cntr=0.3,0.1

Type RM Length L Ch R = 1 ,47376   ,662,662,662
BEGIN DESCRIPTION:
UNT001 IN PECR 84.0
END DESCRIPTION:
XS GIS Cut Line= 3
      2276508.13     13250634.35      2276367.84     13250220.84
      2275769.74     13249334.77
#Sta/Elev= 30
  4205.6  213.28  4652.3  198.88  4745.2  194.51  4754.1  195.82  4803.9  195.16
  4826.1  193.45  4832.1  191.29    4862  194.08  4943.6   191.9    4970  192.01
    4976  186.18    4988  182.88  4990.7  182.38    4994  182.88  5005.9  183.28
    5012  188.97  5026.9  191.72  5041.9  191.33  5056.9  185.27  5065.2  185.91
  5069.3  185.54  5092.8  191.42  5158.9  194.08  5242.8  199.61  5308.7  198.48
  5452.6  203.19  5489.6   206.6  5639.7  212.33  5673.4  214.13  5711.3   215.7
#Mann= 9 ,-1 , 0
  4205.6      .1       0  4943.6     .12       0    4988     .07       0
    4994     .12       0  5065.2     .12       0  5158.9      .1       0
  5489.6     .08       0  5639.7      .1       0  5673.4     .08       0
Bank Sta=4970,5026.9
XS Rating Curve= 0 ,0
Exp/Cntr=0.3,0.1