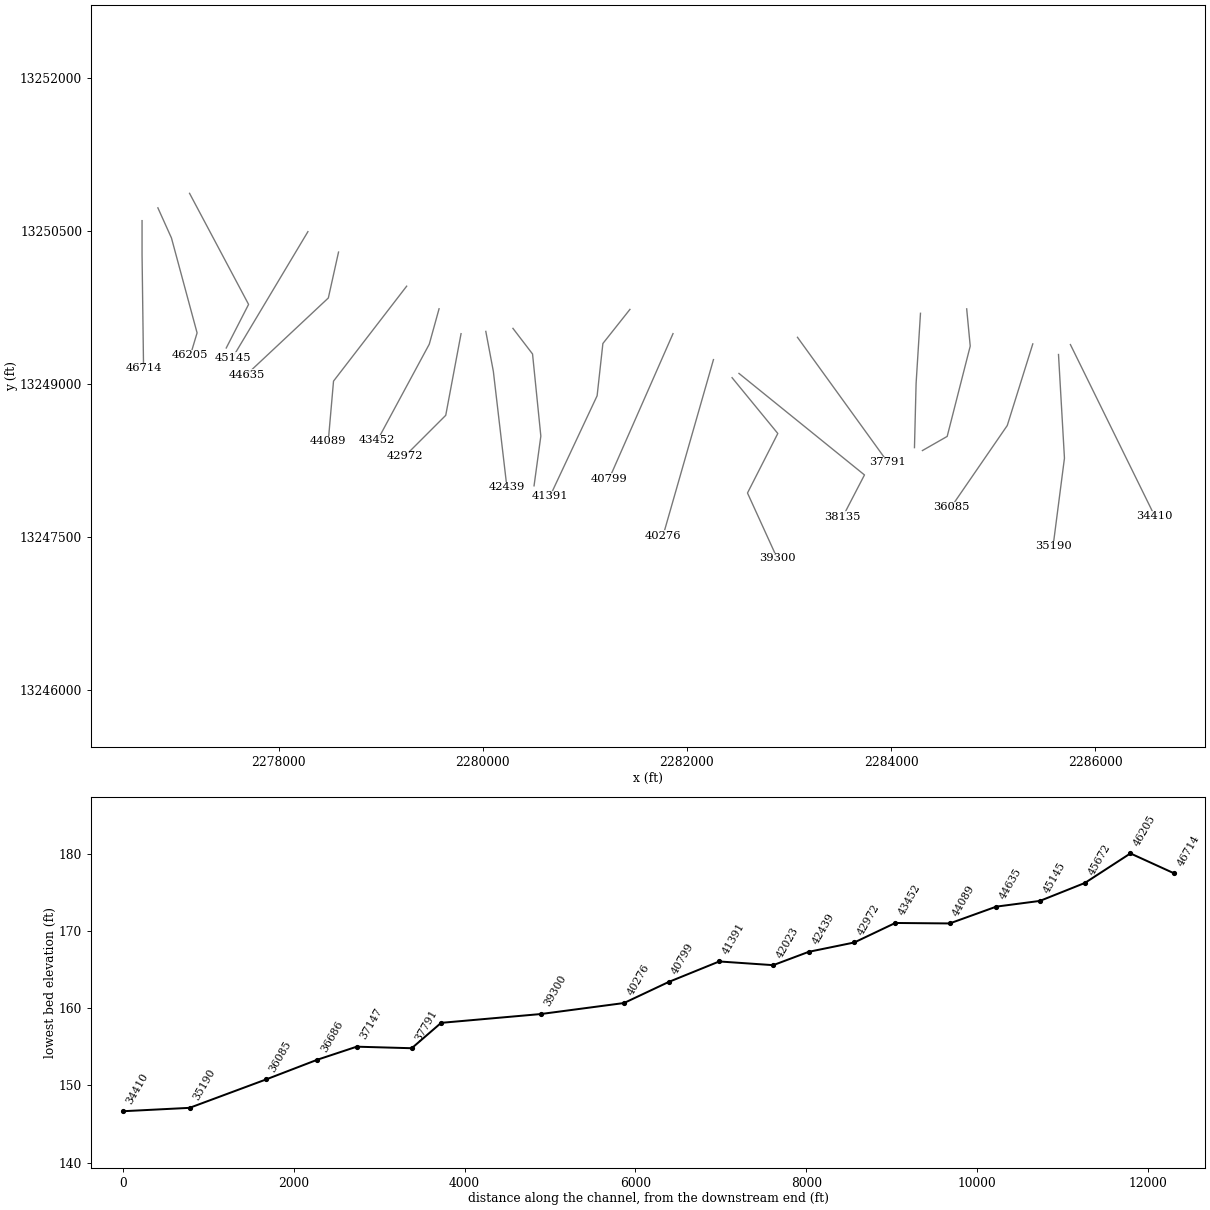
HEC-RAS study UNT001 IN PECR.prj: UNT001 IN PECR Base Level Engineering

--- UNT001 IN PECR.g01 (geometry) --- (continued)

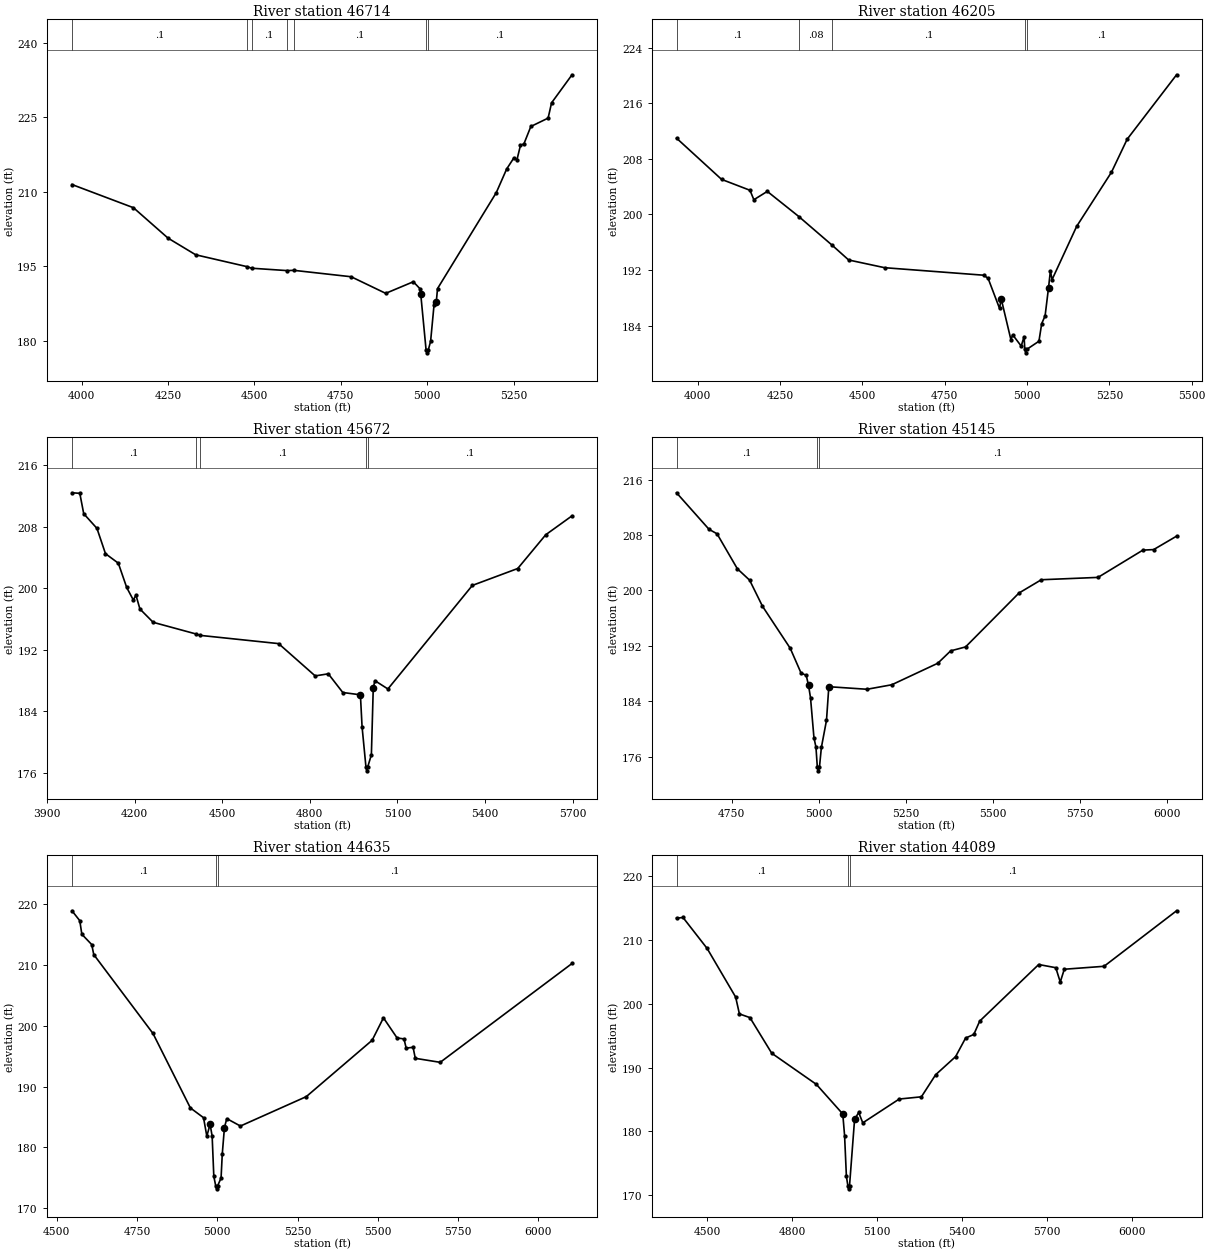
Type RM Length L Ch R = 1 ,46714   ,509,509,509
BEGIN DESCRIPTION:
UNT001 IN PECR 83.0
END DESCRIPTION:
XS GIS Cut Line= 3
      2276663.18     13250604.84      2276663.18     13250272.53
      2276677.95     13249157.63
#Sta/Elev= 30
  3971.8  211.47  4149.8  206.79  4249.8  200.66  4329.8   197.3  4479.5  194.89
  4491.6  194.59  4594.1  194.11  4614.2  194.16  4779.8  192.87  4879.8  189.52
  4959.8  191.86  4979.8  190.39 4981.25  189.36  4996.8  178.02  4999.6  177.52
  5002.8  178.02  5009.8  179.85  5019.6   187.1 5026.25  187.78  5029.8  190.48
  5199.9  209.84  5229.9   214.6  5249.9  216.75  5259.9  216.52  5269.9  219.38
  5279.9  219.68  5299.9  223.18  5349.9  224.87  5359.9  227.95  5419.1  233.61
#Mann= 7 ,-1 , 0
  3971.8      .1       0  4479.5     .08       0  4491.6      .1       0
  4594.1     .16       0  4614.2      .1       0  4996.8     .07       0
  5002.8      .1       0
Bank Sta=4981.25,5026.25
XS Rating Curve= 0 ,0
Exp/Cntr=0.3,0.1

Type RM Length L Ch R = 1 ,46205   ,533,533,533
BEGIN DESCRIPTION:
UNT001 IN PECR 82.0
END DESCRIPTION:
XS GIS Cut Line= 4
      2276818.25     13250730.29      2276951.15     13250434.97
      2277202.19     13249504.63      2277135.74     13249283.14
#Sta/Elev= 30
  3935.5  210.98  4072.3  205.05  4158.6  203.48  4170.4  202.12  4211.2  203.32
    4307   199.7  4408.5  195.56  4458.3  193.45  4567.7  192.34  4868.5  191.26
  4881.8  190.81  4916.5  186.49  4921.7  187.84  4951.2  181.96  4956.4  182.69
  4982.4  181.06  4991.1  182.43  4993.3  180.59  4996.1  180.09  4999.3  180.59
  5036.2  181.76  5044.6   184.3  5054.9  185.41  5065.3  189.44    5071  191.89
  5076.1  190.63  5150.8  198.29  5256.5  206.08  5304.2  210.83  5454.2   220.1
#Mann= 5 ,-1 , 0
  3935.5      .1       0    4307     .08       0  4408.5      .1       0
  4993.3     .07       0  4999.3      .1       0
Bank Sta=4921.7,5065.3
XS Rating Curve= 0 ,0
Exp/Cntr=0.3,0.1

Type RM Length L Ch R = 1 ,45672   ,527,527,527
BEGIN DESCRIPTION:
UNT001 IN PECR 81.0
END DESCRIPTION:
XS GIS Cut Line= 3
      2277128.48     13250872.38       2277706.6     13249783.85
      2277487.83     13249356.74
#Sta/Elev= 30
  3985.4  212.43  4012.2  212.36  4025.6  209.71  4070.9   207.8  4100.1  204.51
  4144.1  203.27  4172.8  200.11  4195.5  198.48  4204.4  199.12  4218.1  197.31
  4263.4  195.58  4408.6  194.08  4424.7  193.88    4693  192.81  4818.2  188.61
  4863.2  188.88  4912.8  186.45  4973.1  186.15  4978.8     182  4992.1  176.76
  4994.8  176.26  4998.1  176.76  5010.7  178.35  5017.1  187.03  5022.7  187.99
  5067.3  186.91  5356.5  200.38  5511.9  202.58  5607.8  206.97  5697.8  209.43
#Mann= 5 ,-1 , 0
  3985.4      .1       0  4408.6     .08       0  4424.7      .1       0
  4992.1     .07       0  4998.1      .1       0
Bank Sta=4973.1,5017.1
XS Rating Curve= 0 ,0
Exp/Cntr=0.3,0.1

Type RM Length L Ch R = 1 ,45145   ,510,510,510
BEGIN DESCRIPTION:
UNT001 IN PECR 80.0
END DESCRIPTION:
XS GIS Cut Line= 2
      2278287.74     13250496.89      2277550.36     13249263.04
#Sta/Elev= 30
    4591  214.12  4684.4  208.84  4707.5  208.19  4765.8  203.14  4801.1  201.49
  4838.1  197.72  4917.9  191.64    4949  188.06  4963.8  187.74  4970.4   186.3
  4976.2  184.48    4986  178.74  4991.8  177.35  4995.8  174.43  4998.5  173.93
  5001.8  174.43  5007.4  177.31  5022.1  181.23  5028.8  186.09  5138.6  185.72
  5209.7  186.37    5342  189.48    5379  191.27  5421.8  191.84  5575.4  199.63
  5639.6  201.55  5802.6  201.89  5931.5  205.83  5962.6  205.91  6028.4  207.85
#Mann= 3 ,-1 , 0
    4591      .1       0  4995.8     .07       0  5001.8      .1       0
Bank Sta=4970.4,5028.8
XS Rating Curve= 0 ,0
Exp/Cntr=0.3,0.1

Type RM Length L Ch R = 1 ,44635   ,546,546,546
BEGIN DESCRIPTION:
UNT001 IN PECR 79.0
END DESCRIPTION:
XS GIS Cut Line= 3
      2278587.72     13250296.86      2278487.72     13249846.85
       2277687.7     13249096.83
#Sta/Elev= 30
  4547.5  218.93  4571.8   217.3  4578.2  215.07    4609  213.37  4615.4  211.72
  4799.8  198.75  4916.3   186.5  4957.3  184.89  4967.5  181.86  4977.7  183.81
  4984.1  181.87  4989.3  175.25  4995.2  173.69    4998  173.19  5001.2  173.69
  5011.9  174.97  5015.6  178.89  5022.4  183.27  5029.7  184.74  5072.2  183.52
  5277.4  188.36  5482.5  197.63  5517.7  201.32  5560.2  198.01  5581.7  197.85
  5588.5  196.34    5610  196.47  5616.9  194.66  5694.5     194  6105.1  210.26
#Mann= 3 ,-1 , 0
  4547.5      .1       0  4995.2     .07       0  5001.2      .1       0
Bank Sta=4977.7,5022.4
XS Rating Curve= 0 ,0
Exp/Cntr=0.3,0.1

Type RM Length L Ch R = 1 ,44089   ,637,637,637
BEGIN DESCRIPTION:
UNT001 IN PECR 78.0
END DESCRIPTION:
XS GIS Cut Line= 3
      2279254.86     13249962.42      2278538.64     13249032.07
      2278486.97     13248441.63
#Sta/Elev= 30
  4391.3  213.42  4414.2  213.53  4499.4  208.68  4600.2  201.06  4613.5  198.42
  4650.7  197.84  4727.7  192.26  4885.4  187.38  4978.7  182.74  4985.1  179.36
  4991.5  172.99  4996.6  171.51  4999.3  171.01  5002.6  171.51  5020.4  181.88
  5034.9  182.98  5049.4  181.35  5178.1  185.08  5256.5  185.43  5306.7  188.88
  5377.4  191.73  5412.7  194.64  5441.7   195.2  5462.5  197.29    5671  206.16
  5731.3  205.66  5747.2  203.41  5761.4  205.42  5901.9  205.88  6158.1  214.58
#Mann= 3 ,-1 , 0
  4391.3      .1       0  4996.6     .07       0  5002.6      .1       0
Bank Sta=4978.7,5020.4
XS Rating Curve= 0 ,0
Exp/Cntr=0.3,0.1

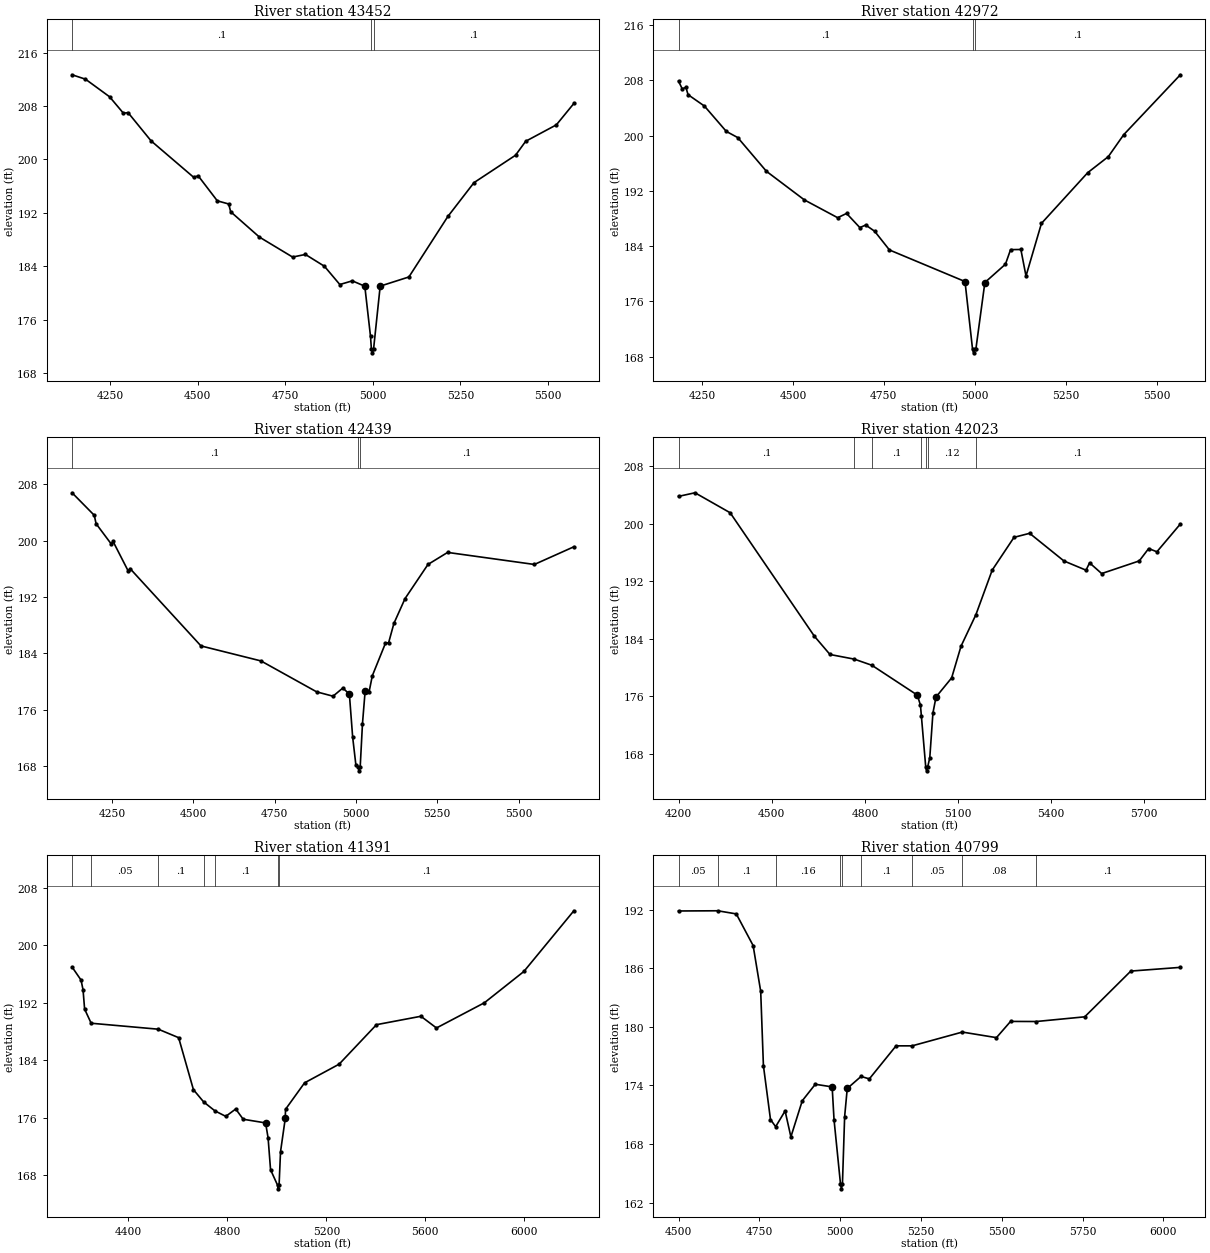
Type RM Length L Ch R = 1 ,43452   ,480,480,480
BEGIN DESCRIPTION:
UNT001 IN PECR 77.0
END DESCRIPTION:
XS GIS Cut Line= 3
      2279572.35     13249740.92      2279476.36     13249393.87
      2278967.72     13248450.31
#Sta/Elev= 30
  4141.9  212.67  4180.2  212.01  4248.9  209.38  4288.4  206.92  4301.7  207.01
  4367.4  202.78  4488.5  197.35    4502  197.54  4556.4  193.81  4588.9  193.34
  4594.5  192.18  4676.5  188.39  4771.2   185.4  4807.8  185.79  4862.1  184.02
    4906  181.29  4941.6  181.84  4977.3  181.04  4993.6  173.52  4996.2  171.57
    4999  171.07  5002.2  171.57  5021.2  181.05  5103.1  182.42  5214.3  191.47
  5288.8  196.53  5407.4  200.63  5436.4  202.72    5524  205.18  5573.9  208.38
#Mann= 3 ,-1 , 0
  4141.9      .1       0  4996.2     .07       0  5002.2      .1       0
Bank Sta=4977.3,5021.2
XS Rating Curve= 0 ,0
Exp/Cntr=0.3,0.1

Type RM Length L Ch R = 1 ,42972   ,533,533,533
BEGIN DESCRIPTION:
UNT001 IN PECR 76.0
END DESCRIPTION:
XS GIS Cut Line= 3
      2279787.71     13249496.82      2279637.72     13248696.85
      2279237.71     13248296.85
#Sta/Elev= 30
  4185.6  207.86  4195.7  206.76  4205.9  206.96  4211.8  205.91  4256.8  204.26
    4317  200.59  4348.4   199.7  4427.2  194.82  4531.5  190.68  4623.1   188.1
  4647.6  188.72  4684.1  186.67  4700.2  187.04  4724.8  186.14  4765.5  183.43
  4973.2  178.86    4994  169.04  4996.7  168.54    5000  169.04    5003  169.04
  5027.8  178.72  5084.4  181.37  5098.5  183.48  5126.8   183.5  5140.9  179.66
  5183.4  187.28  5310.6  194.62  5367.2  196.94  5409.6  200.12  5565.2  208.79
#Mann= 3 ,-1 , 0
  4185.6      .1       0    4994     .07       0    5000      .1       0
Bank Sta=4973.2,5027.8
XS Rating Curve= 0 ,0
Exp/Cntr=0.3,0.1

Type RM Length L Ch R = 1 ,42439   ,416,416,416
BEGIN DESCRIPTION:
UNT001 IN PECR 75.0
END DESCRIPTION:
XS GIS Cut Line= 3
      2280030.14     13249519.38      2280103.97     13249128.06
      2280236.83     13247991.42
#Sta/Elev= 30
  4127.5  206.82  4195.8  203.62  4201.3  202.43  4248.2  199.53  4253.3  199.93
  4300.6  195.66  4305.7  196.06  4523.8  185.07  4708.2  182.94  4879.3  178.55
  4929.7  177.93  4959.9  179.09    4980  178.23  4990.1  172.11  5000.1  168.12
  5007.2  167.83    5010  167.33  5013.2  167.83  5020.3  174.05  5028.5  178.69
  5040.4   178.5  5050.5  180.83  5090.7  185.43  5100.8  185.55  5116.9  188.27
  5151.2   191.8  5221.6  196.64    5282  198.35  5548.7  196.64  5670.1  199.15
#Mann= 3 ,-1 , 0
  4127.5      .1       0  5007.2     .07       0  5013.2      .1       0
Bank Sta=4980,5028.5
XS Rating Curve= 0 ,0
Exp/Cntr=0.3,0.1

Type RM Length L Ch R = 1 ,42023   ,632,632,632
BEGIN DESCRIPTION:
UNT001 IN PECR 74.0
END DESCRIPTION:
XS GIS Cut Line= 4
      2280295.96     13249548.92      2280487.93     13249297.88
      2280569.15     13248493.06       2280502.7     13248005.81
#Sta/Elev= 30
  4199.3  203.79  4252.3  204.29  4365.6  201.51    4637  184.33  4687.2  181.79
  4765.8  181.14  4822.2  180.29  4968.6  176.14  4978.7  174.74  4981.8  173.19
  4995.8   166.1  4998.5   165.6  5001.8   166.1  5008.8  167.43  5018.9  173.64
  5028.9  175.88  5079.2  178.53  5109.4  182.94  5157.4  187.33  5209.9  193.53
  5280.2  198.09  5330.5  198.65  5441.1   194.8  5512.2  193.52  5523.6  194.54
  5562.6  193.05  5683.7  194.81    5714  196.53  5740.5  196.08    5816  199.94
#Mann= 7 ,-1 , 0
  4199.3      .1       0  4765.8     .12       0  4822.2      .1       0
  4981.8     .12       0  4995.8     .07       0  5001.8     .12       0
  5157.4      .1       0
Bank Sta=4968.6,5028.9
XS Rating Curve= 0 ,0
Exp/Cntr=0.3,0.1

Type RM Length L Ch R = 1 ,41391   ,592,592,592
BEGIN DESCRIPTION:
UNT001 IN PECR 73.0
END DESCRIPTION:
XS GIS Cut Line= 4
      2281441.66     13249734.88      2281176.91     13249400.69
      2281120.49     13248888.54      2280659.13     13247904.42
#Sta/Elev= 30
  4172.2  196.97  4208.5  195.15  4216.6  193.79  4222.9  191.11  4249.4  189.14
  4520.7  188.31    4603  187.13  4662.8  179.89  4704.2  178.18  4749.6  176.94
  4793.6  176.17  4833.8   177.2    4864  175.77  4954.5  175.26  4964.6  173.18
  4974.6  168.74    5003  166.58  5005.7  166.08    5009  166.58  5014.9  171.25
 5034.09  175.89    5035  177.15  5112.1  180.84  5251.8  183.44  5402.8  188.94
  5582.4  190.11  5645.3  188.48    5839  191.99  5998.7  196.35  6200.7   204.8
#Mann= 7 ,-1 , 0
  4172.2      .1       0  4249.4     .05       0  4520.7      .1       0
  4704.2     .16       0  4749.6      .1       0    5003     .07       0
    5009      .1       0
Bank Sta=4954.5,5034.09
XS Rating Curve= 0 ,0
Exp/Cntr=0.3,0.1

Type RM Length L Ch R = 1 ,40799   ,523,523,523
BEGIN DESCRIPTION:
UNT001 IN PECR 72.0
END DESCRIPTION:
XS GIS Cut Line= 2
      2281863.79     13249497.29      2281239.11     13248076.01
#Sta/Elev= 30
    4500  191.85  4621.3  191.87  4678.7  191.55  4730.8  188.31  4754.2  183.63
  4762.6  176.03  4784.5  170.51  4800.5  169.78  4829.7  171.39  4847.6  168.74
  4882.8  172.43  4923.1  174.12  4975.3  173.85  4981.1  170.49  5001.1  163.92
  5003.8  163.42  5007.1  163.92  5013.9  170.81    5022  173.69  5064.7  174.92
  5090.3  174.67    5173  178.05  5222.7  178.05    5378  179.46  5483.6  178.89
  5527.3  180.55  5606.6  180.54  5756.7  181.02  5899.3   185.7  6052.5  186.08
#Mann= 9 ,-1 , 0
    4500     .05       0  4621.3      .1       0  4800.5     .16       0
  5001.1     .07       0  5007.1     .16       0  5064.7      .1       0
  5222.7     .05       0    5378     .08       0  5606.6      .1       0
Bank Sta=4975.3,5022
XS Rating Curve= 0 ,0
Exp/Cntr=0.3,0.1

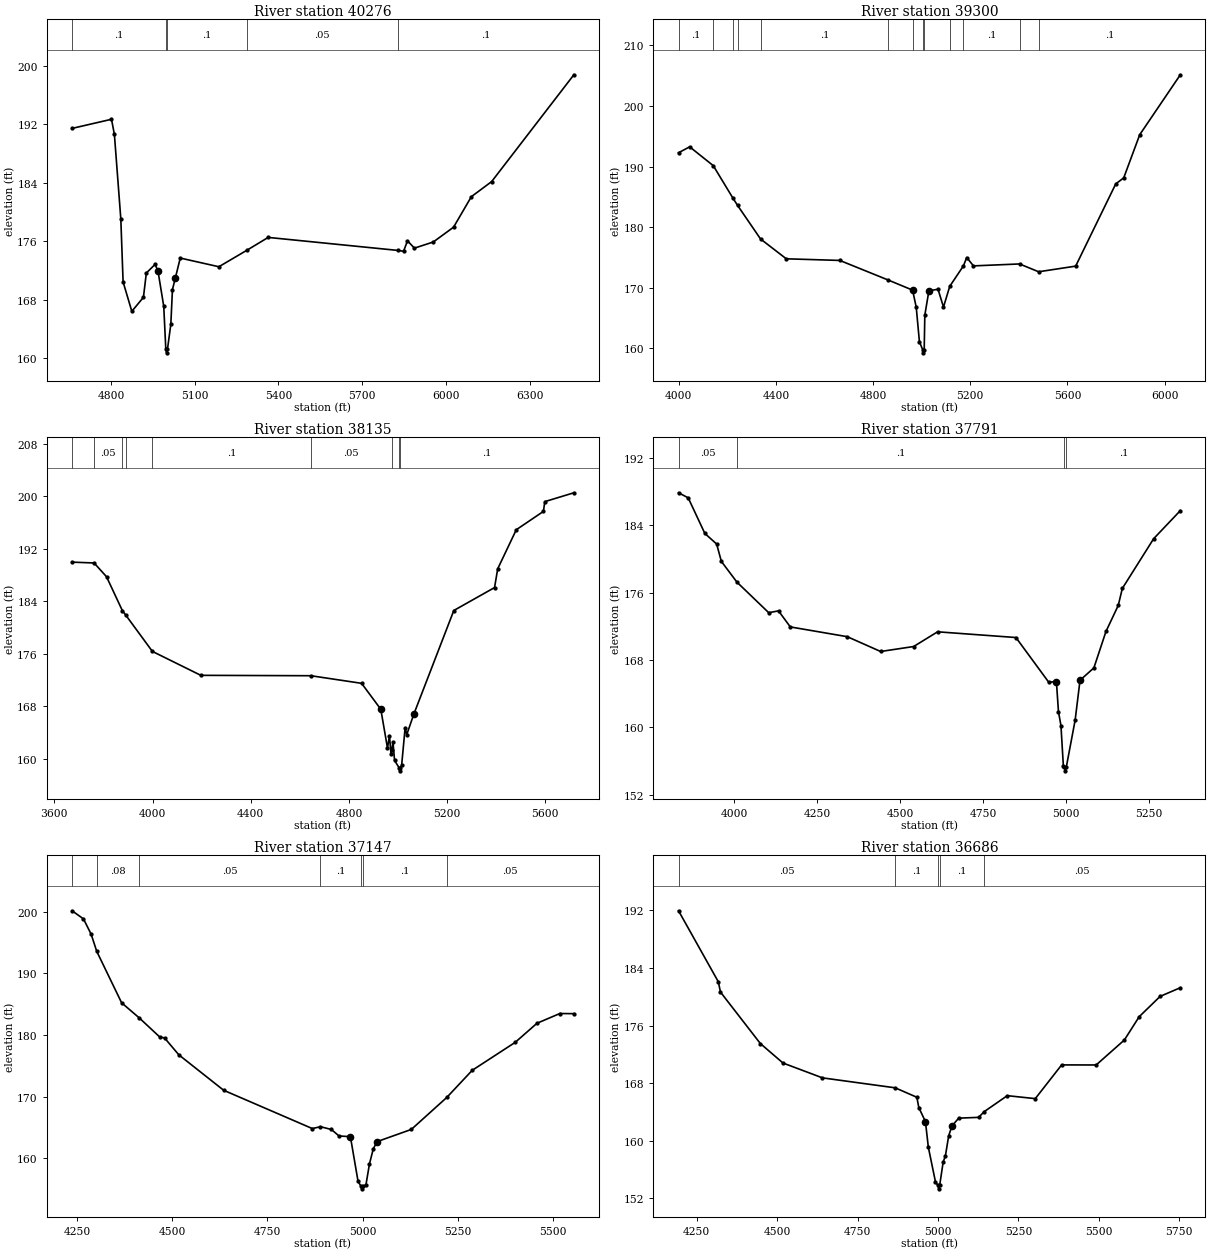
Type RM Length L Ch R = 1 ,40276   ,976,976,976
BEGIN DESCRIPTION:
UNT001 IN PECR 71.0
END DESCRIPTION:
XS GIS Cut Line= 2
      2282259.97     13249242.75      2281765.16     13247513.55
#Sta/Elev= 30
  4660.2  191.45  4801.5   192.7  4811.9  190.63  4834.9  179.06  4843.1  170.41
  4874.4  166.38    4916   168.3  4926.4  171.63  4957.6  172.81    4968  171.94
  4988.8  167.07  4996.2  161.19  4998.9  160.69  5002.2  161.19  5014.2  164.61
    5020  169.36  5030.4  170.95    5048  173.68  5186.4  172.49  5285.5  174.72
  5363.2  176.51  5827.4  174.73  5848.3  174.61  5862.5  176.04  5887.3  175.04
  5954.8  175.88  6027.6  177.91  6091.3  182.09  6164.1  184.16  6458.8   198.8
#Mann= 5 ,-1 , 0
  4660.2      .1       0  4996.2     .07       0  5002.2      .1       0
  5285.5     .05       0  5827.4      .1       0
Bank Sta=4968,5030.4
XS Rating Curve= 0 ,0
Exp/Cntr=0.3,0.1

Type RM Length L Ch R = 1 ,39300   ,1165,1165,1165
BEGIN DESCRIPTION:
Mapping XS cd1abceb
END DESCRIPTION:
XS GIS Cut Line= 4
      2282442.27     13249065.59      2282890.16     13248518.75
      2282593.29     13247935.41      2282884.96     13247294.78
#Sta/Elev= 30
  3999.2  192.28    4045  193.26  4142.2  190.15  4223.7  184.75  4242.2  183.59
  4336.8  178.05  4442.7  174.78    4663  174.51  4863.2  171.26  4962.5  169.61
  4977.5   166.8  4990.7  161.07  5004.3  159.76  5007.1  159.26  5010.3  159.76
  5012.9  165.48  5029.6  169.49  5067.2  169.76  5089.7  166.81  5115.5  170.24
  5171.9  173.62  5185.3  174.99  5213.1  173.61  5402.7  173.93  5481.3  172.64
  5633.7  173.57  5798.8  187.15  5831.5  188.13  5897.4  195.26  6064.5  205.15
#Mann= 13 ,-1 , 0
  3999.2      .1       0  4142.2     .05       0  4223.7      .1       0
  4242.2     .05       0  4336.8      .1       0  4863.2     .16       0
  4962.5     .12       0  5004.3     .07       0  5010.3     .12       0
  5115.5     .16       0  5171.9      .1       0  5402.7     .05       0
  5481.3      .1       0
Bank Sta=4962.5,5029.6
XS Rating Curve= 0 ,0
Exp/Cntr=0.3,0.1

Type RM Length L Ch R = 1 ,38135   ,344,344,344
BEGIN DESCRIPTION:
UNT001 IN PECR 70.0
END DESCRIPTION:
XS GIS Cut Line= 3
      2282509.96     13249107.28      2283739.12      13248112.5
      2283525.78     13247701.43
#Sta/Elev= 30
  3672.1  189.96    3762  189.83  3812.5  187.73  3876.8  182.58  3891.4  181.85
  3999.3  176.34  4196.7  172.69  4645.1  172.63  4851.7  171.47    4930  167.51
  4957.2  161.59  4965.2  163.49  4971.6  160.63  4974.7  161.35  4979.6  162.49
    4986   159.7  5004.1  158.62  5006.9  158.12  5010.1  158.62  5014.8  158.95
  5029.1  164.72  5035.6  163.64  5064.3  166.75  5227.4  182.58  5393.4  186.08
  5406.2  188.94  5481.9   194.9  5592.5   197.7  5598.1  199.19  5716.5  200.54
#Mann= 9 ,-1 , 0
  3672.1      .1       0    3762     .05       0  3876.8      .1       0
  3891.4     .05       0  3999.3      .1       0  4645.1     .05       0
  4974.7      .1       0  5004.1     .07       0  5010.1      .1       0
Bank Sta=4930,5064.3
XS Rating Curve= 0 ,0
Exp/Cntr=0.3,0.1

Type RM Length L Ch R = 1 ,37791   ,644,644,644
BEGIN DESCRIPTION:
UNT001 IN PECR 69.0
END DESCRIPTION:
XS GIS Cut Line= 2
      2283082.86     13249461.47       2283968.6     13248235.09
#Sta/Elev= 30
  3832.3  187.89  3861.4  187.29  3911.7  183.05  3947.2   181.8  3961.4  179.73
  4008.5  177.26  4104.3  173.63  4133.7  173.85  4169.3  171.94    4341  170.78
  4441.6  169.02  4541.1  169.61  4613.3  171.36  4849.5  170.68  4948.3  165.37
  4971.5  165.45  4977.7  161.87  4985.2  160.21  4992.4  155.46  4995.6  155.33
  4998.3  154.83  5001.6  155.33    5028  160.86  5042.7   165.6  5084.5  167.07
  5120.9   171.4  5157.9  174.49  5170.3  176.52  5264.7  182.43  5345.1  185.77
#Mann= 4 ,-1 , 0
  3832.3     .05       0  4008.5      .1       0  4995.6     .07       0
  5001.6      .1       0
Bank Sta=4971.5,5042.7
XS Rating Curve= 0 ,0
Exp/Cntr=0.3,0.1

Type RM Length L Ch R = 1 ,37147   ,461,461,461
BEGIN DESCRIPTION:
UNT001 IN PECR 68.0
END DESCRIPTION:
XS GIS Cut Line= 3
      2284287.72     13249696.84      2284244.69     13249008.31
      2284228.75     13248379.99
#Sta/Elev= 30
  4236.9  200.14  4266.9  198.82    4287  196.34  4301.7  193.56  4367.1  185.21
  4413.8  182.74  4467.3  179.66  4479.9  179.51  4517.4  176.77  4635.2  171.02
  4868.1  164.81  4889.6  165.11  4918.2  164.66  4938.2  163.61  4968.2  163.49
  4988.3  156.24  4995.3  155.53    4998  155.03  5001.3  155.53  5008.8  155.59
  5018.3  159.08  5028.3  161.52  5038.3  162.69  5128.3  164.67  5221.3  169.85
  5288.3  174.26  5401.1  178.79  5458.4  181.89  5518.4  183.47  5555.3  183.45
#Mann= 7 ,-1 , 0
  4236.9      .1       0  4301.7     .08       0  4413.8     .05       0
  4889.6      .1       0  4995.3     .07       0  5001.3      .1       0
  5221.3     .05       0
Bank Sta=4968.2,5038.3
XS Rating Curve= 0 ,0
Exp/Cntr=0.3,0.1

Type RM Length L Ch R = 1 ,36686   ,601,601,601
BEGIN DESCRIPTION:
UNT001 IN PECR 67.0
END DESCRIPTION:
XS GIS Cut Line= 4
      2284740.22     13249740.03      2284774.95     13249375.45
      2284549.25     13248490.04       2284306.8     13248351.49
#Sta/Elev= 30
  4193.9  191.93  4317.6  182.07  4324.2  180.65  4448.2   173.5  4518.5   170.8
  4641.2  168.74  4867.1  167.36  4934.4  166.05  4940.5  164.62  4961.1  162.67
  4970.1  159.12  4992.1  154.34  4999.4  153.84  5002.2  153.34  5005.4  153.84
  5016.2  157.07  5023.1   157.9  5033.4  160.72  5043.7  162.07  5064.3  163.15
  5126.3  163.26  5143.9  164.06  5215.4  166.27  5302.4  165.86  5384.3  170.54
  5491.6  170.53  5579.3     174  5625.3  177.23  5690.3  180.05  5753.1  181.25
#Mann= 5 ,-1 , 0
  4193.9     .05       0  4867.1      .1       0  4999.4     .07       0
  5005.4      .1       0  5143.9     .05       0
Bank Sta=4961.1,5043.7
XS Rating Curve= 0 ,0
Exp/Cntr=0.3,0.1

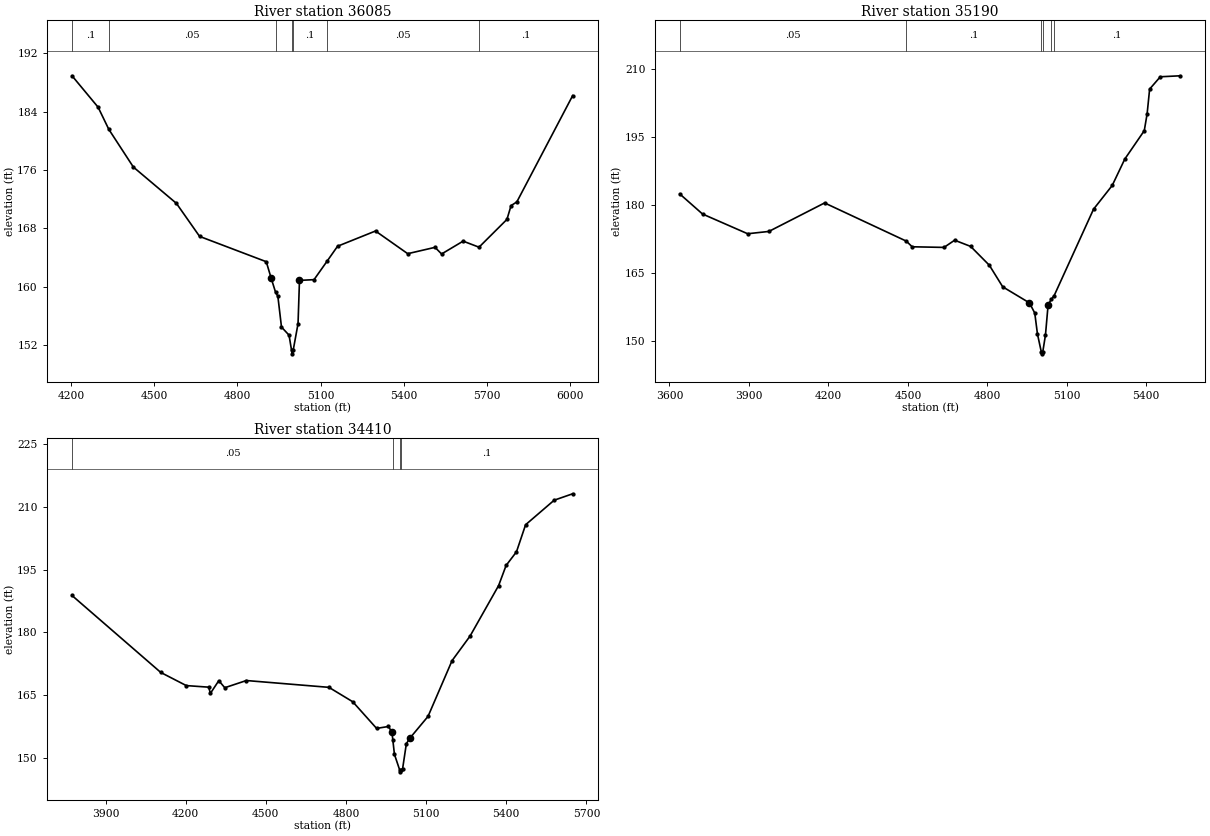
Type RM Length L Ch R = 1 ,36085   ,895,895,895
BEGIN DESCRIPTION:
UNT001 IN PECR 66.0
END DESCRIPTION:
XS GIS Cut Line= 3
      2285387.72     13249396.84      2285137.72     13248596.85
       2284587.7     13247796.82
#Sta/Elev= 30
  4202.1   188.9  4296.4  184.59    4335  181.56  4423.7  176.39  4579.3  171.41
  4663.1  166.88    4904  163.41  4921.3   161.2  4937.7  159.21  4945.9  158.67
    4959  154.45  4986.3  153.34  4995.3  151.28  4998.1  150.78  5001.3  151.28
  5018.8  154.92    5024  160.85  5076.6  160.95  5123.9  163.49  5161.6  165.53
  5298.7  167.62  5415.1  164.51  5513.8  165.38  5537.5  164.47  5615.3  166.23
  5672.7   165.4  5773.6  169.21  5788.5   171.1  5809.4  171.61  6011.1  186.18
#Mann= 7 ,-1 , 0
  4202.1      .1       0    4335     .05       0  4937.7      .1       0
  4995.3     .07       0  5001.3      .1       0  5123.9     .05       0
  5672.7      .1       0
Bank Sta=4921.3,5024
XS Rating Curve= 0 ,0
Exp/Cntr=0.3,0.1

Type RM Length L Ch R = 1 ,35190   ,780,780,780
BEGIN DESCRIPTION:
UNT001 IN PECR 65.0
END DESCRIPTION:
XS GIS Cut Line= 3
      2285639.53     13249292.85      2285697.86     13248276.84
      2285586.08     13247411.71
#Sta/Elev= 30
  3638.7  182.44  3724.8     178  3895.1  173.64  3975.2  174.15  4185.6  180.45
    4494  172.01  4516.1  170.76  4636.3  170.62  4676.5  172.21    4737  170.84
  4807.6  166.67    4858  161.91  4958.9  158.36    4979  156.11  4989.1  151.49
  5003.4   147.6  5006.2   147.1  5009.4   147.6  5019.4  151.26  5029.4  157.98
  5041.9  159.18    5052  159.94  5200.9  179.07  5271.4  184.31  5318.8  190.14
  5392.4  196.42  5403.2  200.17  5412.6  205.61  5452.9  208.33  5528.7  208.55
#Mann= 6 ,-1 , 0
  3638.7     .05       0    4494      .1       0  5003.4     .07       0
  5009.4      .1       0  5041.9     .12       0    5052      .1       0
Bank Sta=4958.9,5029.4
XS Rating Curve= 0 ,0
Exp/Cntr=0.3,0.1

Type RM Length L Ch R = 1 ,34410   ,350,350,350
BEGIN DESCRIPTION:
UNT001 IN PECR 64.0
END DESCRIPTION:
XS GIS Cut Line= 2
      2285756.18     13249390.07      2286582.57     13247708.12
#Sta/Elev= 30
  3774.5  188.84  4106.8  170.43  4202.3  167.29  4286.6  166.91  4292.2   165.4
    4324  168.47  4346.3  166.78  4427.1   168.5  4736.2  166.87  4825.4  163.42
  4914.6  157.05  4959.1  157.51  4972.2  156.09  4975.5  154.21  4981.4  150.84
  5000.7  147.16  5003.4  146.66  5006.7  147.16  5011.6  147.26    5026  153.39
  5039.6  154.75  5107.1  159.92    5197  173.25  5264.4  179.13  5371.3  191.21
  5399.3  196.02  5438.2  199.29  5472.3  205.76  5579.2  211.63  5648.5  213.17
#Mann= 4 ,-1 , 0
  3774.5     .05       0  4975.5      .1       0  5000.7     .07       0
  5006.7      .1       0
Bank Sta=4972.2,5039.6
XS Rating Curve= 0 ,0
Exp/Cntr=0.3,0.1