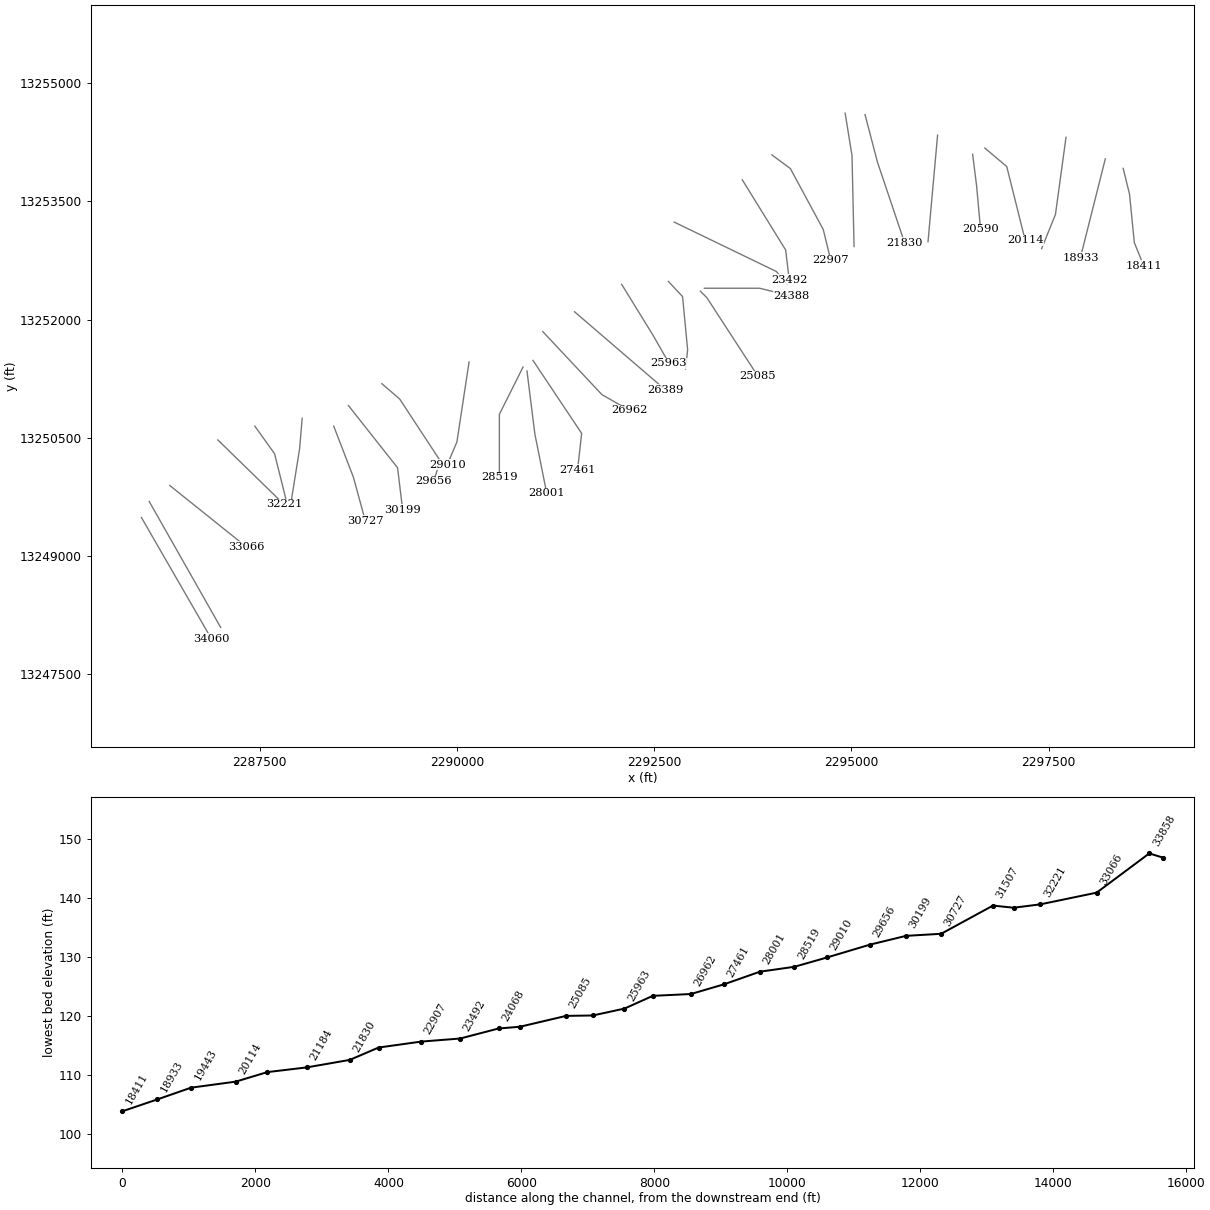
HEC-RAS study UNT001 IN PECR.prj: UNT001 IN PECR Base Level Engineering

--- UNT001 IN PECR.g01 (geometry) --- (continued)

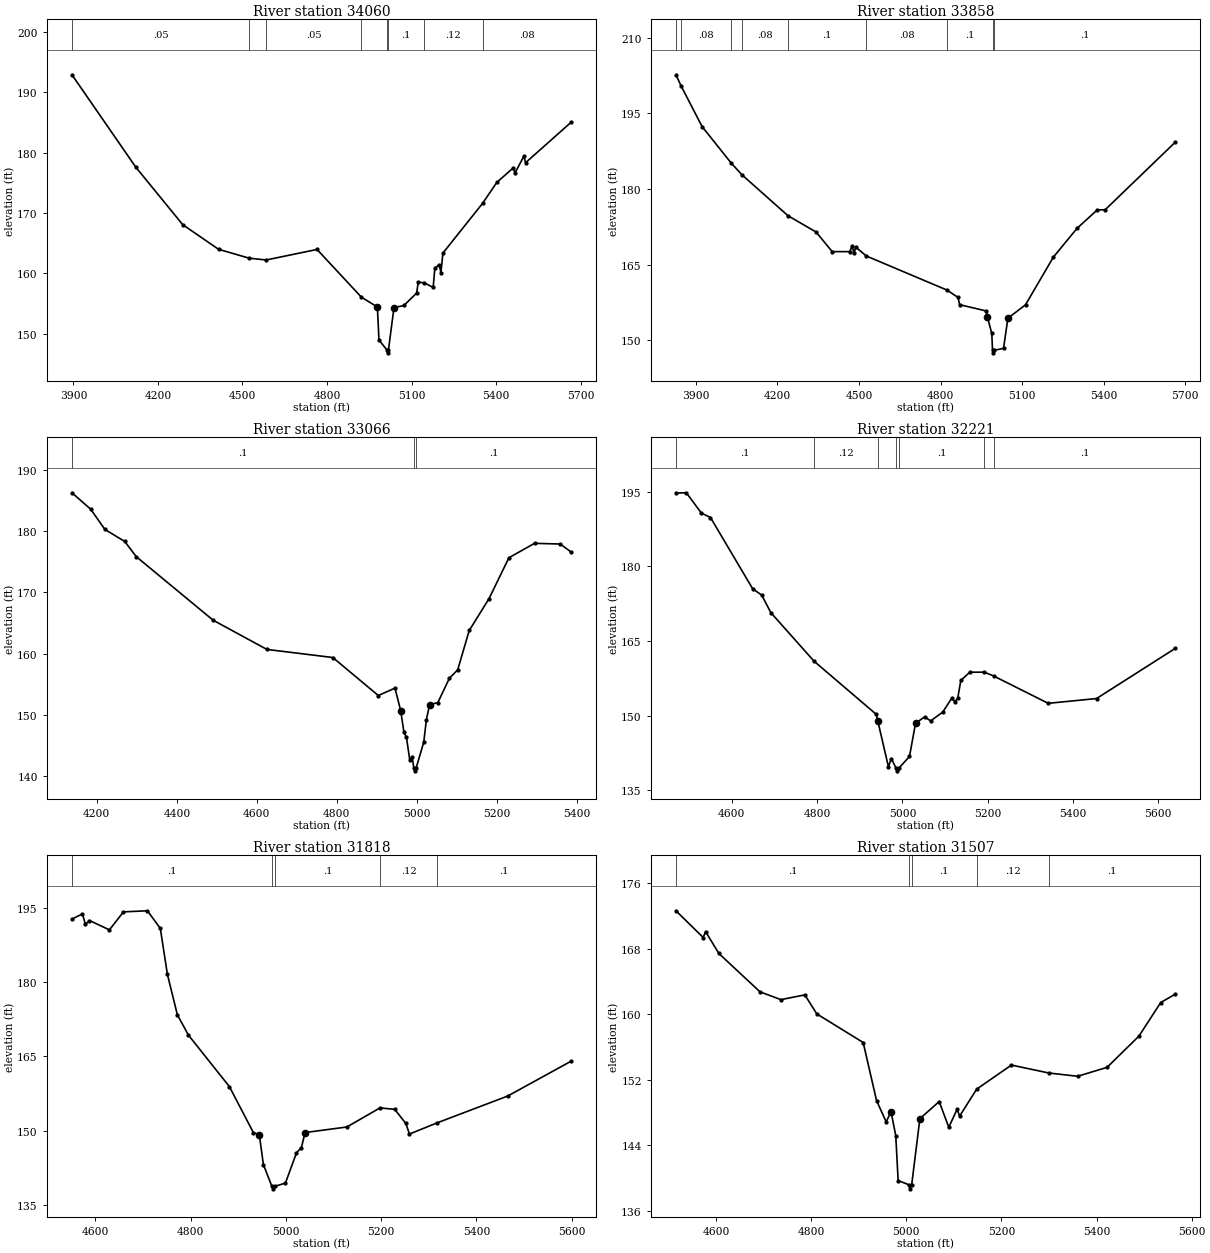
Type RM Length L Ch R = 1 ,34060   ,202,202,202
BEGIN DESCRIPTION:
UNT001 IN PECR 63.0
END DESCRIPTION:
XS GIS Cut Line= 2
      2285999.54     13249487.49       2286884.7     13247951.48
#Sta/Elev= 30
  3894.9   192.9  4121.1  177.62    4288  168.08    4415     164  4523.5  162.53
  4584.1  162.23  4764.7  163.97  4922.1  156.07  4978.8  154.45  4984.5  148.98
  5012.2  147.35  5014.9  146.85  5018.2  147.35  5037.7  154.33  5072.9  154.69
  5118.1  156.74  5123.9  158.55  5144.5  158.45  5176.8  157.69  5182.8  160.89
  5198.6  161.44  5204.3  160.11  5211.4  163.37  5352.4  171.62  5402.6  175.07
  5461.5   177.5  5467.3  176.64  5498.8  179.43  5504.6  178.33  5667.7  185.09
#Mann= 8 ,-1 , 0
  3894.9     .05       0  4523.5     .08       0  4584.1     .05       0
  4922.1      .1       0  5012.2     .07       0  5018.2      .1       0
  5144.5     .12       0  5352.4     .08       0
Bank Sta=4978.8,5037.7
XS Rating Curve= 0 ,0
Exp/Cntr=0.3,0.1

Type RM Length L Ch R = 1 ,33858   ,792,792,792
BEGIN DESCRIPTION:
UNT001 IN PECR 62.0
END DESCRIPTION:
XS GIS Cut Line= 2
      2286098.51      13249690.6       2287004.7     13248091.75
#Sta/Elev= 30
  3826.6  202.65  3846.1  200.38  3922.9  192.38  4029.1  185.21  4069.4  182.83
  4239.1  174.71  4342.3  171.49  4401.4  167.61  4466.3   167.6  4474.6  168.73
  4482.2  167.29    4488  168.51    4527  166.74    4825  159.96  4864.6  158.52
  4870.3   157.1    4967  155.86  4972.7   154.6  4988.6  151.39  4991.4  148.05
  4994.1  147.55  4997.4  148.05  5031.9  148.44  5047.8   154.4  5112.7  157.07
  5215.1  166.51  5302.2  172.22  5376.7  175.87  5405.7   175.9  5664.4  189.33
#Mann= 9 ,-1 , 0
  3826.6      .1       0  3846.1     .08       0  4029.1      .1       0
  4069.4     .08       0  4239.1      .1       0    4527     .08       0
    4825      .1       0  4991.4     .07       0  4997.4      .1       0
Bank Sta=4972.7,5047.8
XS Rating Curve= 0 ,0
Exp/Cntr=0.3,0.1

Type RM Length L Ch R = 1 ,33066   ,845,845,845
BEGIN DESCRIPTION:
UNT001 IN PECR 61.0
END DESCRIPTION:
XS GIS Cut Line= 2
      2286358.94     13249893.73      2287332.83     13249112.53
#Sta/Elev= 30
  4137.9  186.26    4185  183.56  4220.2  180.28  4269.8  178.32  4298.6  175.84
  4490.7  165.47  4625.1   160.7  4789.9  159.38  4903.6  153.18  4945.2  154.39
  4959.6  150.68  4967.6  147.19    4974  146.35    4982  142.73  4988.4  143.08
  4992.3  141.39    4995  140.89  4998.3  141.39  5017.2  145.58  5023.6  149.17
  5031.6  151.68  5052.4  152.03  5081.2  155.99    5102  157.37  5130.8  163.79
  5180.4     169    5230  175.66    5294  178.01  5358.1   177.9  5386.4  176.55
#Mann= 3 ,-1 , 0
  4137.9      .1       0  4992.3     .07       0  4998.3      .1       0
Bank Sta=4959.6,5031.6
XS Rating Curve= 0 ,0
Exp/Cntr=0.3,0.1

Type RM Length L Ch R = 1 ,32221   ,403,403,403
BEGIN DESCRIPTION:
UNT001 IN PECR 60.0
END DESCRIPTION:
XS GIS Cut Line= 2
      2286968.31     13250471.85      2287806.83     13249654.17
#Sta/Elev= 30
  4468.9  194.75  4493.3   194.8  4528.6  190.72  4549.9  189.83  4648.9  175.49
    4670  174.23  4691.3  170.72  4792.8  160.94  4938.8  150.25  4942.3  148.88
  4967.1  139.73    4974  141.37  4985.2  139.41  4987.9  138.91  4991.2  139.41
  5016.5   141.8  5030.6  148.46  5051.9  149.75  5066.1  148.95  5094.4  150.71
  5115.5   153.5  5122.7  152.81  5129.6   153.5  5136.8  157.07  5157.9  158.74
  5192.1  158.74  5213.7  157.98  5341.8  152.48    5455  153.44  5640.1  163.55
#Mann= 7 ,-1 , 0
  4468.9      .1       0  4792.8     .12       0  4942.3      .1       0
  4985.2     .07       0  4991.2      .1       0  5192.1     .12       0
  5213.7      .1       0
Bank Sta=4942.3,5030.6
XS Rating Curve= 0 ,0
Exp/Cntr=0.3,0.1

Type RM Length L Ch R = 1 ,31818   ,311,311,311
BEGIN DESCRIPTION:
UNT001 IN PECR 59.0
END DESCRIPTION:
XS GIS Cut Line= 3
      2287437.74     13250646.82      2287687.72     13250296.85
      2287837.71      13249696.9
#Sta/Elev= 30
  4550.9  192.68    4573  193.73  4579.1   191.6  4587.7  192.39  4629.5   190.5
    4659  194.13  4709.4  194.35  4736.4  190.78  4751.2  181.55  4772.1   173.4
  4795.4   169.3  4881.4  158.92  4931.8  149.64  4944.1  149.27  4952.7  143.22
  4970.6  138.83  4973.4  138.33  4976.6  138.83    4999  139.49  5022.2  145.59
  5032.5  146.64  5040.2  149.67  5127.9  150.79  5197.5  154.64  5228.4  154.34
  5251.6  151.52  5259.3  149.37  5317.3  151.62  5465.4  157.02  5599.4  164.09
#Mann= 5 ,-1 , 0
  4550.9      .1       0  4970.6     .07       0  4976.6      .1       0
  5197.5     .12       0  5317.3      .1       0
Bank Sta=4944.1,5040.2
XS Rating Curve= 0 ,0
Exp/Cntr=0.3,0.1

Type RM Length L Ch R = 1 ,31507   ,780,780,780
BEGIN DESCRIPTION:
UNT001 IN PECR 58.0
END DESCRIPTION:
XS GIS Cut Line= 3
      2288037.72     13250746.87      2288004.75     13250357.29
      2287900.58     13249706.25
#Sta/Elev= 30
  4515.7  172.62    4573  169.36    4578  170.08    4606  167.41  4692.5  162.73
  4736.5  161.78  4786.7  162.36  4811.9  160.04  4909.4  156.55  4937.5  149.47
  4957.8  146.86  4967.9  148.13  4977.9  145.19  4982.9  139.71  5005.4   139.2
  5008.1   138.7  5011.4   139.2  5028.6  147.26  5069.2  149.35  5089.4  146.21
    5107  148.42  5112.1  147.57    5148  150.86  5221.1   153.8  5299.8  152.83
  5360.2  152.43  5422.2  153.52  5489.3  157.34    5535  161.43    5566  162.46
#Mann= 5 ,-1 , 0
  4515.7      .1       0  5005.4     .07       0  5011.4      .1       0
    5148     .12       0  5299.8      .1       0
Bank Sta=4967.9,5028.6
XS Rating Curve= 0 ,0
Exp/Cntr=0.3,0.1

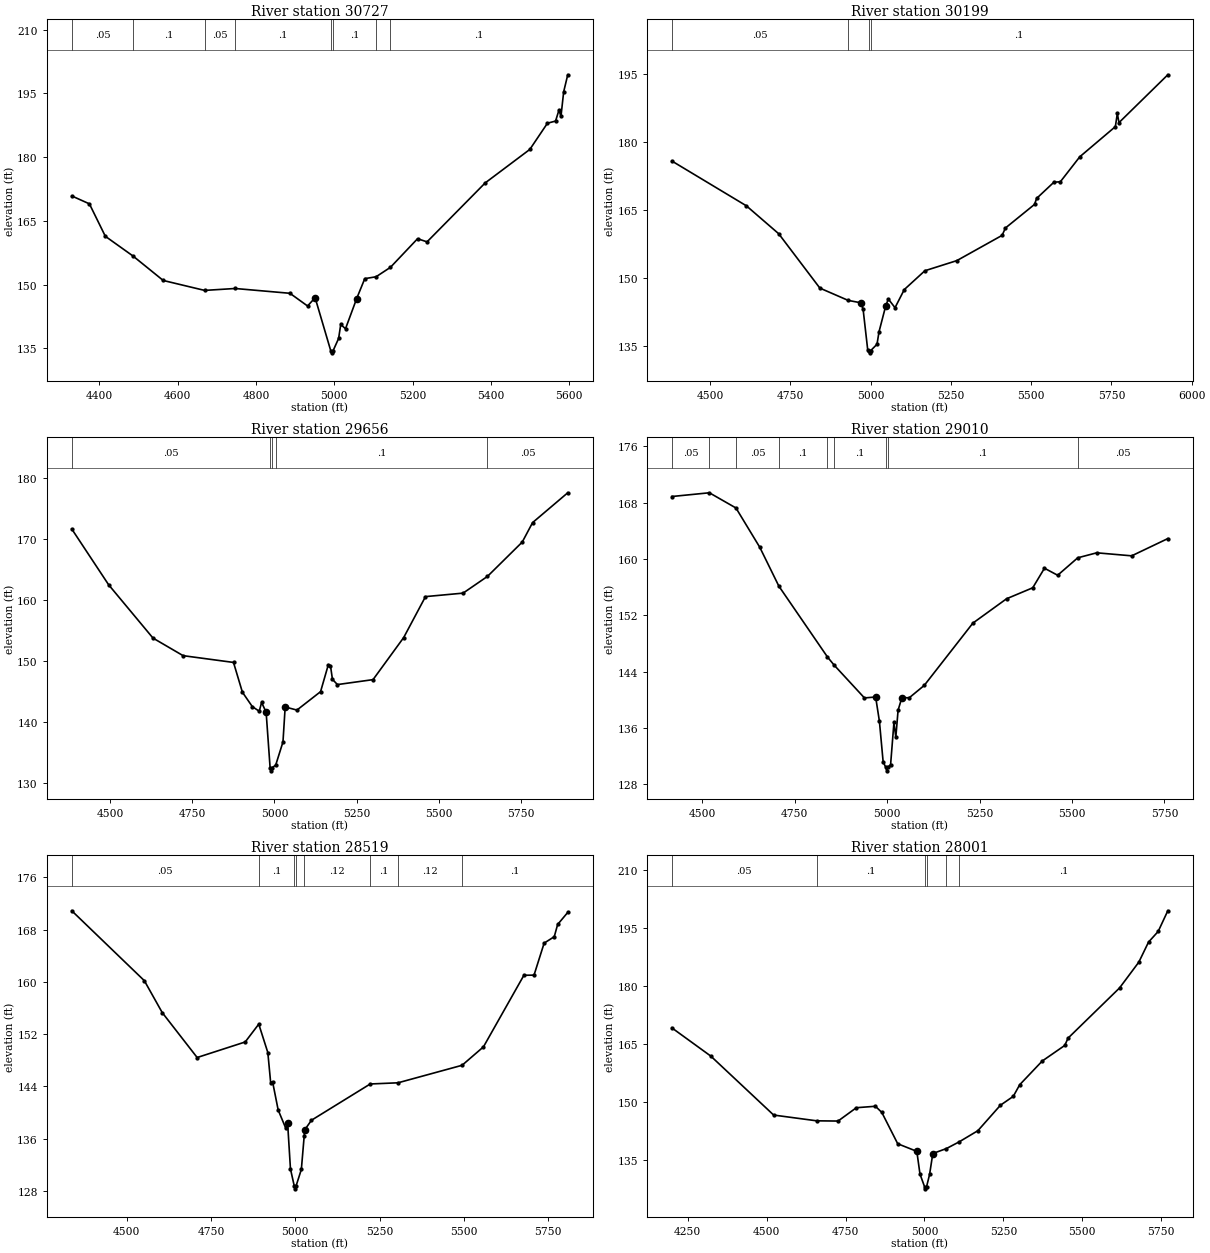
Type RM Length L Ch R = 1 ,30727   ,528,528,528
BEGIN DESCRIPTION:
UNT001 IN PECR 57.0
END DESCRIPTION:
XS GIS Cut Line= 3
      2288437.73     13250646.84      2288687.72     13249996.85
      2288837.72     13249446.84
#Sta/Elev= 30
  4329.7  170.85  4374.7  168.99  4415.4  161.35    4486  156.71  4563.2  150.95
  4668.9  148.61  4746.8  149.06  4886.8  147.93  4931.8  144.94  4951.1  146.89
    4991  134.41  4993.7  133.91    4997  134.41  5011.1   137.3  5016.5  140.59
  5028.7  139.58  5057.2  146.69  5077.9  151.38  5106.7  151.82  5143.4  154.04
  5212.7  160.78  5236.9  160.04  5385.4  173.92  5499.4  181.81  5544.4  187.98
  5565.1  188.48  5573.7  191.04  5578.9  189.59  5585.8  195.38  5596.2  199.38
#Mann= 8 ,-1 , 0
  4329.7     .05       0    4486      .1       0  4668.9     .05       0
  4746.8      .1       0    4991     .07       0    4997      .1       0
  5106.7     .16       0  5143.4      .1       0
Bank Sta=4951.1,5057.2
XS Rating Curve= 0 ,0
Exp/Cntr=0.3,0.1

Type RM Length L Ch R = 1 ,30199   ,543,543,543
BEGIN DESCRIPTION:
UNT001 IN PECR 56.0
END DESCRIPTION:
XS GIS Cut Line= 3
      2288623.51     13250909.04       2289247.1     13250118.31
      2289311.39      13249584.7
#Sta/Elev= 30
  4381.2  175.88  4613.2     166  4713.9  159.84  4842.2  147.84  4930.3  145.13
  4969.8   144.6  4976.8  143.18  4991.3  134.15  4994.6  134.06  4997.4  133.56
  5000.6  134.06  5020.1  135.45  5026.5  138.24  5047.3  143.93  5055.4  145.43
  5076.2  143.52  5105.1  147.52  5169.2  151.67  5268.6   153.9  5409.8  159.48
  5419.9  161.09  5510.6   166.3  5517.2  167.63    5571   171.2  5591.1   171.3
  5651.6  176.81  5762.4  183.46  5768.5  186.36  5773.6  184.34  5925.7   194.9
#Mann= 4 ,-1 , 0
  4381.2     .05       0  4930.3      .1       0  4994.6     .07       0
  5000.6      .1       0
Bank Sta=4969.8,5047.3
XS Rating Curve= 0 ,0
Exp/Cntr=0.3,0.1

Type RM Length L Ch R = 1 ,29656   ,646,646,646
BEGIN DESCRIPTION:
UNT001 IN PECR 55.0
END DESCRIPTION:
XS GIS Cut Line= 4
      2289047.83     13251185.43      2289272.81     13250992.59
       2289787.1     13250208.31      2289703.52     13249944.72
#Sta/Elev= 30
  4382.7  171.71  4495.1  162.56  4630.1  153.83  4721.8  150.95  4875.3  149.84
  4902.4  144.96  4932.6   142.6  4953.7  141.84  4960.9  143.28  4974.7  141.68
  4986.8  132.57  4989.6  132.07  4992.8  132.57  5003.9  133.02    5026  136.81
  5032.7  142.54  5068.5  142.03  5140.5  145.05  5164.2  149.48  5170.7  149.29
  5176.7  147.07  5191.8  146.21  5300.3  147.02  5393.7  153.92  5460.1  160.63
  5574.6   161.2  5648.8  163.94  5754.8  169.57  5786.3  172.76  5893.4  177.65
#Mann= 5 ,-1 , 0
  4382.7     .05       0  4986.8     .03       0  4992.8     .05       0
  5003.9      .1       0  5648.8     .05       0
Bank Sta=4974.7,5032.7
XS Rating Curve= 0 ,0
Exp/Cntr=0.3,0.1

Type RM Length L Ch R = 1 ,29010   ,491,491,491
BEGIN DESCRIPTION:
UNT001 IN PECR 54.0
END DESCRIPTION:
XS GIS Cut Line= 3
      2290153.52     13251461.85      2289999.24     13250446.16
      2289877.08     13250156.83
#Sta/Elev= 30
  4417.7  168.87  4519.2   169.4  4591.1  167.24  4655.4  161.67  4707.2  156.13
  4838.7  146.06  4856.7  144.91  4938.6  140.25  4968.9  140.38  4979.1  136.94
  4989.2  131.16  4996.3  130.39    4999  129.89  5002.3  130.39  5009.4  130.79
  5018.4  136.76  5023.5  134.67  5029.6   138.5  5039.7  140.27    5060  140.28
  5100.4  142.03  5231.9  150.88    5323  154.34  5393.8   155.9  5425.5  158.68
  5461.2  157.68  5515.5  160.16  5566.9  160.87  5661.4  160.44  5759.1  162.89
#Mann= 9 ,-1 , 0
  4417.7     .05       0  4519.2      .1       0  4591.1     .05       0
  4707.2      .1       0  4838.7     .05       0  4856.7      .1       0
  4996.3     .07       0  5002.3      .1       0  5515.5     .05       0
Bank Sta=4968.9,5039.7
XS Rating Curve= 0 ,0
Exp/Cntr=0.3,0.1

Type RM Length L Ch R = 1 ,28519   ,518,518,518
BEGIN DESCRIPTION:
UNT001 IN PECR 53.0
END DESCRIPTION:
XS GIS Cut Line= 3
      2290837.73     13251396.87      2290537.72     13250796.85
      2290537.72     13249996.89
#Sta/Elev= 30
  4337.1  170.87  4552.3  160.17  4605.4  155.28  4708.9  148.41  4851.4  150.79
  4891.6  153.52  4918.5  149.17  4926.9  144.56  4932.5  144.72  4949.2  140.37
  4971.6   137.6  4977.2  138.35  4985.6  131.36  4996.6  128.81  4999.3  128.31
  5002.6  128.81  5017.9  131.28  5026.3  136.37  5027.9  137.34  5047.9  138.81
  5222.2  144.36  5304.5  144.54  5494.5  147.22  5557.9  150.04  5677.9     161
  5707.9  161.02  5737.9  165.92  5767.9   166.9  5777.9  168.77  5807.9  170.62
#Mann= 8 ,-1 , 0
  4337.1     .05       0  4891.6      .1       0  4996.6     .07       0
  5002.6      .1       0  5026.3     .12       0  5222.2      .1       0
  5304.5     .12       0  5494.5      .1       0
Bank Sta=4977.2,5027.9
XS Rating Curve= 0 ,0
Exp/Cntr=0.3,0.1

Type RM Length L Ch R = 1 ,28001   ,540,540,540
BEGIN DESCRIPTION:
UNT001 IN PECR 52.0
END DESCRIPTION:
XS GIS Cut Line= 3
      2290887.72     13251346.82      2290987.72     13250546.85
      2291137.71      13249796.9
#Sta/Elev= 30
  4199.8  169.09  4323.2  161.79  4522.3  146.55  4658.7  145.06  4726.3     145
  4784.3  148.45  4844.7  148.82  4864.9  147.23  4915.3  139.13  4975.8  137.17
  4985.8   131.3  5000.5  127.98  5003.2  127.48  5006.5  127.98  5016.2  131.19
  5026.4  136.61  5069.5  137.89  5110.3  139.64  5169.2  142.51  5240.6  149.09
  5281.3  151.38  5301.7  154.39  5373.1  160.52  5444.5  164.55  5454.7  166.42
  5617.9   179.4  5679.1  186.09  5709.7  191.25  5740.3  194.01  5770.8  199.35
#Mann= 6 ,-1 , 0
  4199.8     .05       0  4658.7      .1       0  5000.5     .07       0
  5006.5      .1       0  5069.5     .12       0  5110.3      .1       0
Bank Sta=4975.8,5026.4
XS Rating Curve= 0 ,0
Exp/Cntr=0.3,0.1

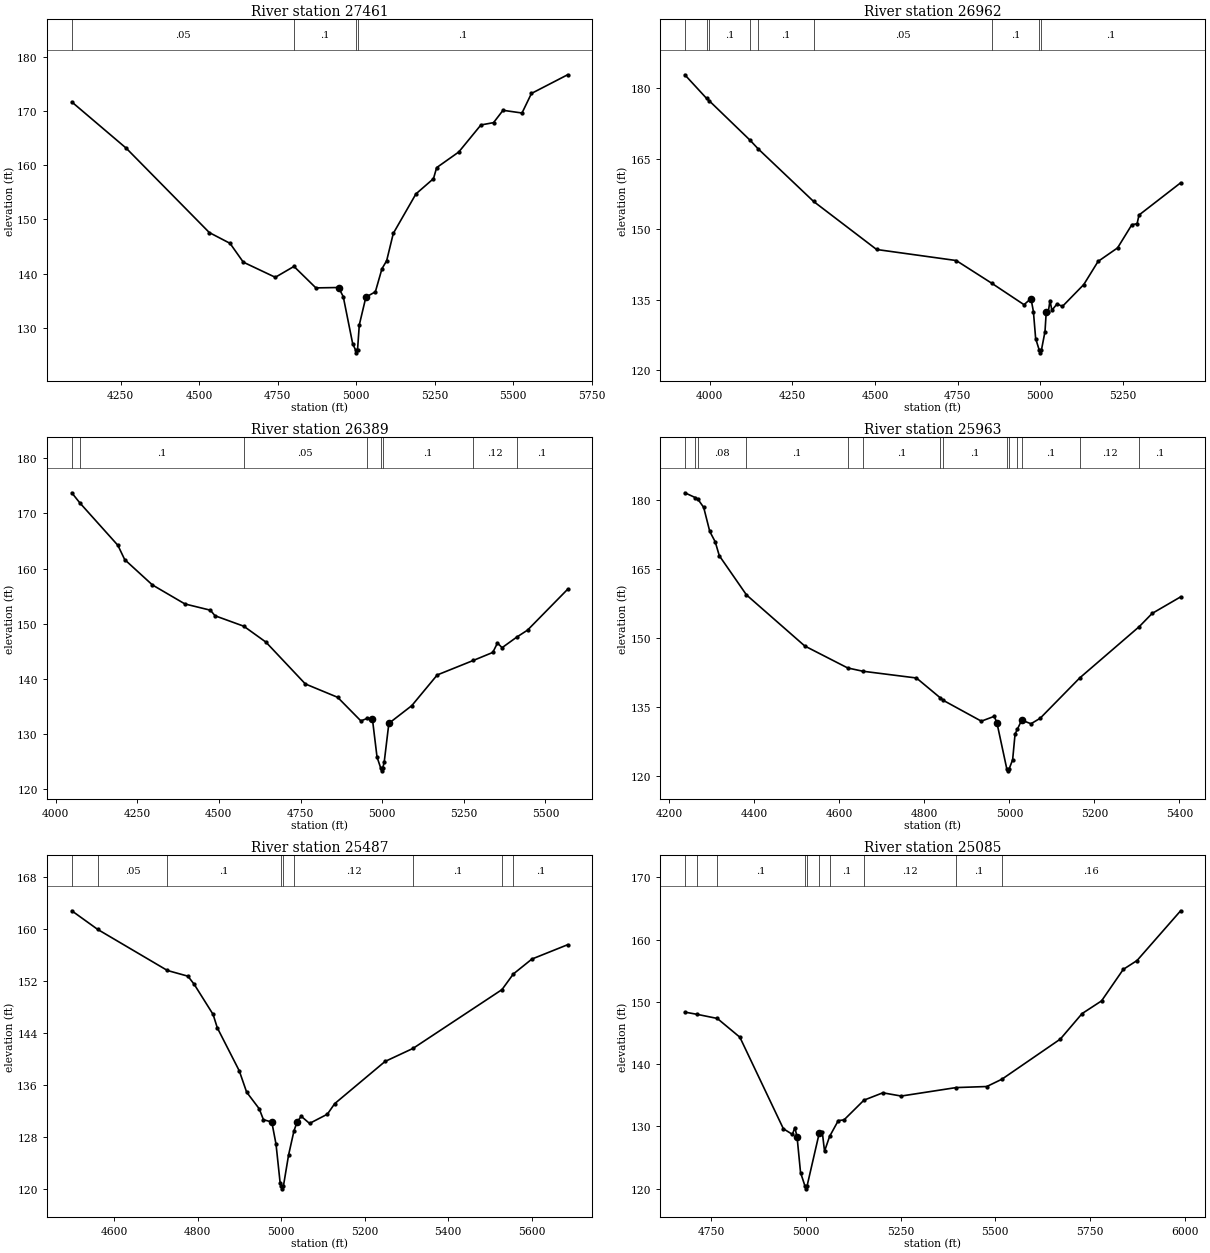
Type RM Length L Ch R = 1 ,27461   ,499,499,499
BEGIN DESCRIPTION:
UNT001 IN PECR 51.0
END DESCRIPTION:
XS GIS Cut Line= 3
      2290963.51     13251481.19      2291580.67     13250555.45
      2291529.24      13250092.6
#Sta/Elev= 30
  4094.7  171.74  4267.9  163.19  4532.6  147.58  4598.4  145.59  4640.7  142.11
  4742.6  139.31    4802  141.32  4871.8  137.35  4943.9  137.42  4958.9  135.73
    4989     127  4998.3  125.84    5001  125.34  5004.3  125.84    5010  130.52
    5031  135.65  5061.1  136.62  5082.1  140.89  5097.1  142.38  5118.2  147.43
  5190.3  154.73  5246.1  157.55  5256.2  159.59  5326.6  162.48  5397.1  167.48
  5437.3  167.91  5467.5  170.19  5527.9  169.69    5558  173.31    5673  176.76
#Mann= 4 ,-1 , 0
  4094.7     .05       0    4802      .1       0  4998.3     .07       0
  5004.3      .1       0
Bank Sta=4943.9,5031
XS Rating Curve= 0 ,0
Exp/Cntr=0.3,0.1

Type RM Length L Ch R = 1 ,26962   ,573,573,573
BEGIN DESCRIPTION:
UNT001 IN PECR 50.0
END DESCRIPTION:
XS GIS Cut Line= 3
      2291087.69     13251846.89      2291837.72     13251046.85
      2292187.68     13250846.88
#Sta/Elev= 30
  3924.7  182.88  3990.7  177.84    3998  177.38  4122.5  168.92  4146.2  167.14
    4314  155.93  4504.8  145.69  4745.6  143.34  4853.2   138.5  4950.7  133.94
  4971.8  135.25  4979.1  132.48  4985.9  126.73  4997.1  124.19  4999.8  123.69
  5003.1  124.19  5014.2  128.23  5017.9  132.42  5024.2  132.42  5029.2  134.82
    5035  132.75  5050.8  134.12  5066.7  133.56  5131.5  138.23  5174.7  143.15
  5233.7  146.03  5276.9  150.97  5292.7  151.17  5298.5  153.02  5424.4  159.88
#Mann= 9 ,-1 , 0
  3924.7      .1       0  3990.7     .08       0    3998      .1       0
  4122.5     .05       0  4146.2      .1       0    4314     .05       0
  4853.2      .1       0  4997.1     .07       0  5003.1      .1       0
Bank Sta=4971.8,5017.9
XS Rating Curve= 0 ,0
Exp/Cntr=0.3,0.1

Type RM Length L Ch R = 1 ,26389   ,426,426,426
BEGIN DESCRIPTION:
UNT001 IN PECR 49.0
END DESCRIPTION:
XS GIS Cut Line= 2
      2291490.66     13252098.31       2292641.4     13251108.29
#Sta/Elev= 30
  4049.7  173.75  4074.8  171.89  4190.9  164.23  4211.8  161.64  4296.5  157.06
  4396.2  153.61  4474.1  152.48  4488.3  151.47  4576.3  149.58  4644.1   146.7
  4764.8  139.12  4863.7   136.7  4934.9  132.42  4953.4  132.87    4970  132.86
  4984.3  125.87  4995.6  123.88  4998.3  123.38  5001.6  123.88  5006.2  124.91
  5020.5  131.98  5090.7  135.19  5168.6  140.75  5279.2  143.38  5338.7  144.83
    5353  146.53  5367.2  145.69  5412.7  147.63  5445.1  148.87  5567.7  156.26
#Mann= 8 ,-1 , 0
  4049.7     .08       0  4074.8      .1       0  4576.3     .05       0
  4953.4      .1       0  4995.6     .07       0  5001.6      .1       0
  5279.2     .12       0  5412.7      .1       0
Bank Sta=4970,5020.5
XS Rating Curve= 0 ,0
Exp/Cntr=0.3,0.1

Type RM Length L Ch R = 1 ,25963   ,476,476,476
BEGIN DESCRIPTION:
UNT001 IN PECR 48.0
END DESCRIPTION:
XS GIS Cut Line= 3
      2292087.71     13252446.88      2292487.72     13251796.85
      2292687.74     13251446.82
#Sta/Elev= 30
  4236.4  181.51  4261.5  180.45  4267.6  180.06  4280.8  178.34  4295.1  173.13
    4308  170.86  4317.5  167.87  4381.5  159.36  4518.6  148.29  4619.5  143.53
    4655  142.82  4781.3  141.35  4837.1  137.07  4844.9  136.48    4934  131.99
  4964.4  133.04  4970.7  131.61  4993.7  121.72  4996.5  121.22  4999.7  121.72
  5007.6  123.61  5013.3  129.17  5018.6  130.22    5029  132.21  5050.8  131.43
  5072.3  132.61  5165.6  141.38  5305.6   152.5  5335.8  155.35  5402.8  158.94
#Mann= 14 ,-1 , 0
  4236.4      .1       0  4261.5     .05       0  4267.6     .08       0
  4381.5      .1       0  4619.5     .05       0    4655      .1       0
  4837.1     .05       0  4844.9      .1       0  4993.7     .07       0
  4999.7      .1       0  5018.6     .12       0    5029      .1       0
  5165.6     .12       0  5305.6      .1       0
Bank Sta=4970.7,5029
XS Rating Curve= 0 ,0
Exp/Cntr=0.3,0.1

Type RM Length L Ch R = 1 ,25487   ,402,402,402
BEGIN DESCRIPTION:
UNT001 IN PECR 47.0
END DESCRIPTION:
XS GIS Cut Line= 4
      2292679.93     13252484.04      2292859.95     13252291.16
      2292924.24     13251616.16      2292898.53     13251371.91
#Sta/Elev= 30
  4498.3  162.86  4560.4  159.99  4727.3  153.67  4776.5  152.79  4791.5  151.54
  4836.8   146.9  4846.8  144.85  4899.4  138.23  4917.1  134.94  4947.3  132.37
  4957.3   130.7  4977.4  130.33  4987.5  126.93  4997.4  120.93  4999.4  120.55
  5002.1  120.05  5005.4  120.55  5017.6  125.27  5030.5  128.98  5037.7  130.29
  5047.7  131.23  5067.8  130.12  5110.4  131.54  5128.1  133.17  5248.6  139.66
  5315.6  141.67  5528.6  150.72  5555.9  153.13  5600.4  155.43  5685.8  157.63
#Mann= 9 ,-1 , 0
  4498.3      .1       0  4560.4     .05       0  4727.3      .1       0
  4999.4     .07       0  5005.4      .1       0  5030.5     .12       0
  5315.6      .1       0  5528.6     .12       0  5555.9      .1       0
Bank Sta=4977.4,5037.7
XS Rating Curve= 0 ,0
Exp/Cntr=0.3,0.1

Type RM Length L Ch R = 1 ,25085   ,697,697,697
BEGIN DESCRIPTION:
UNT001 IN PECR 46.0
END DESCRIPTION:
XS GIS Cut Line= 3
      2293085.64     13252359.68      2293167.42     13252277.89
      2293817.23     13251278.18
#Sta/Elev= 30
  4680.9  148.36  4714.3  147.99  4766.6  147.34  4826.1  144.33  4940.9  129.63
  4964.8  128.72  4971.1  129.82    4977  128.35  4986.2   122.6  4997.6  120.48
  5000.3  119.98  5003.6  120.48  5035.5  128.92  5043.6  129.08  5049.5  126.02
  5062.8  128.39  5085.8  130.94  5100.9  131.05  5153.5  134.22  5203.3   135.4
  5251.8  134.88  5396.6  136.24  5477.6  136.41  5517.6  137.59  5671.6  144.03
  5728.9  148.12  5780.3  150.16  5837.6  155.22  5873.9  156.64  5988.9  164.63
#Mann= 10 ,-1 , 0
  4680.9      .1       0  4714.3     .05       0  4766.6      .1       0
  4997.6     .07       0  5003.6      .1       0  5035.5     .12       0
  5062.8      .1       0  5153.5     .12       0  5396.6      .1       0
  5517.6     .16       0
Bank Sta=4977,5035.5
XS Rating Curve= 0 ,0
Exp/Cntr=0.3,0.1

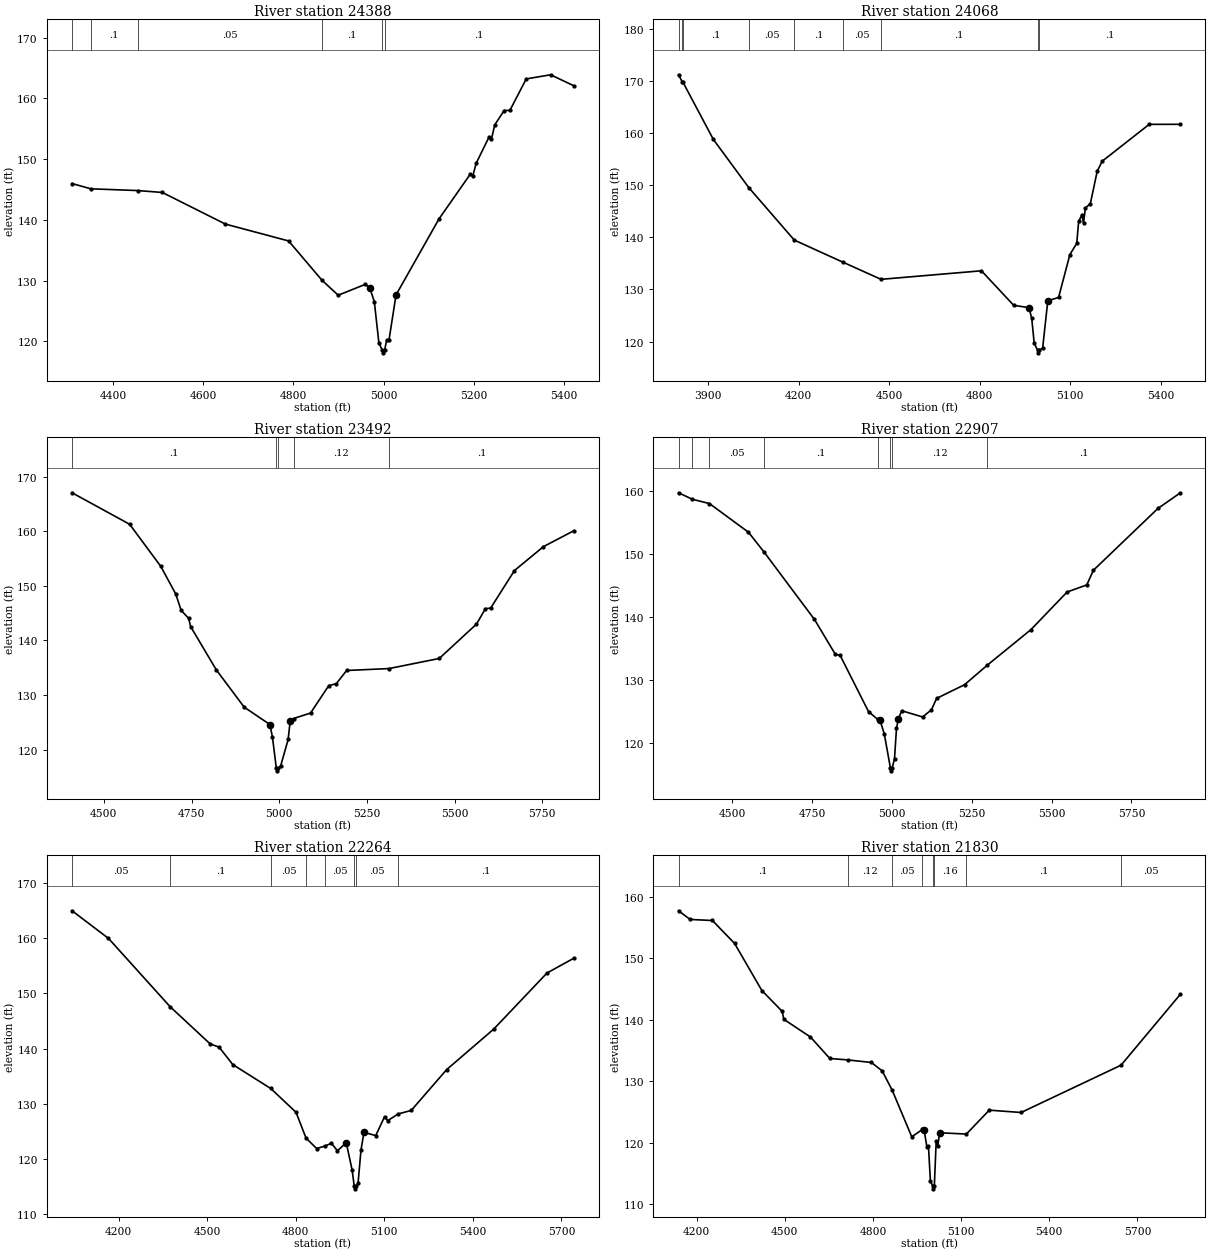
Type RM Length L Ch R = 1 ,24388   ,320,320,320
BEGIN DESCRIPTION:
UNT001 IN PECR 45.0
END DESCRIPTION:
XS GIS Cut Line= 3
      2293137.68     13252396.85      2293837.72     13252396.85
      2294237.67     13252296.87
#Sta/Elev= 30
  4309.4  145.98  4351.1  145.12  4454.8  144.83  4509.4  144.52  4649.4  139.31
  4789.4  136.54  4863.5  130.06  4899.4  127.61  4959.4   129.4  4969.4   128.8
  4979.4  126.55  4989.4  119.82  4996.4  118.63  4999.2  118.13  5002.4  118.63
  5006.9  120.27    5012  120.27  5027.5  127.66  5122.8  140.17  5192.4  147.56
  5197.6  147.22  5205.3  149.34  5233.6  153.63  5238.8  153.24  5246.5  155.66
  5267.1  157.99    5280  158.03  5316.1   163.2  5370.2  163.88  5421.7  162.07
#Mann= 6 ,-1 , 0
  4309.4     .05       0  4351.1      .1       0  4454.8     .05       0
  4863.5      .1       0  4996.4     .07       0  5002.4      .1       0
Bank Sta=4969.4,5027.5
XS Rating Curve= 0 ,0
Exp/Cntr=0.3,0.1

Type RM Length L Ch R = 1 ,24068   ,576,576,576
BEGIN DESCRIPTION:
UNT001 IN PECR 44.0
END DESCRIPTION:
XS GIS Cut Line= 3
      2292753.96     13253236.65      2294048.95      13252609.6
      2294193.55     13252437.89
#Sta/Elev= 30
  3801.7  171.18  3813.9  169.84  3816.5  169.74    3917  158.79  4034.5  149.54
  4185.4  139.47  4346.2  135.24    4473  131.94  4805.8  133.58  4912.7  126.95
  4963.5  126.51  4972.5  124.43  4980.5  119.75  4991.7  118.34  4994.5  117.84
  4997.7  118.34  5008.6  118.73  5025.7  127.83  5061.4  128.46    5099   136.7
  5121.6  138.84    5128  143.08  5138.6  144.26  5144.1  142.73  5150.3  145.63
  5166.7  146.45  5189.3  152.63  5205.8  154.59  5361.8  161.67    5465  161.68
#Mann= 9 ,-1 , 0
  3801.7     .08       0  3813.9     .05       0  3816.5      .1       0
  4034.5     .05       0  4185.4      .1       0  4346.2     .05       0
    4473      .1       0  4991.7     .07       0  4997.7      .1       0
Bank Sta=4963.5,5025.7
XS Rating Curve= 0 ,0
Exp/Cntr=0.3,0.1

Type RM Length L Ch R = 1 ,23492   ,585,585,585
BEGIN DESCRIPTION:
UNT001 IN PECR 43.0
END DESCRIPTION:
XS GIS Cut Line= 3
      2293617.26     13253772.89       2294167.1     13252882.24
      2294212.45     13252501.22
#Sta/Elev= 30
  4409.4  167.04  4573.6  161.27  4662.3  153.57  4704.9  148.52  4720.3  145.52
  4741.5  144.06  4747.4  142.54  4820.7  134.61    4900   127.8  4973.3  124.62
  4980.6  122.33  4991.6  116.64  4994.3  116.14  4997.6  116.64  5004.1  117.06
  5025.3  121.88  5031.2  125.25  5040.8  125.72  5089.2  126.72  5141.2  131.74
  5162.5  132.09  5192.1  134.51  5312.7  134.86  5456.1  136.71  5562.2     143
  5587.8  145.83  5602.5  145.92  5670.4   152.8    5753  157.18  5839.8  160.09
#Mann= 5 ,-1 , 0
  4409.4      .1       0  4991.6     .07       0  4997.6      .1       0
  5040.8     .12       0  5312.7      .1       0
Bank Sta=4973.3,5031.2
XS Rating Curve= 0 ,0
Exp/Cntr=0.3,0.1

Type RM Length L Ch R = 1 ,22907   ,643,643,643
BEGIN DESCRIPTION:
UNT001 IN PECR 42.0
END DESCRIPTION:
XS GIS Cut Line= 4
      2293992.57     13254089.11      2294226.91     13253915.53
      2294643.58     13253142.96      2294739.06     13252752.35
#Sta/Elev= 30
  4331.6  159.75  4374.9  158.72  4428.4  158.04  4550.6  153.49  4600.1   150.3
  4757.1  139.66  4822.8   134.1  4837.6  133.95  4926.6  125.02  4955.5  123.78
  4962.6  123.66  4976.1  121.45    4995  116.12  4997.7  115.62    5001  116.12
    5008  117.56  5014.2  122.36  5019.9   123.8  5030.4  125.16  5096.1  124.17
  5123.7  125.31  5139.9  127.12  5227.4  129.29  5299.2  132.42    5435  138.02
  5548.5     144  5610.2  145.13  5630.8  147.45  5832.9  157.26  5903.1  159.74
#Mann= 8 ,-1 , 0
  4331.6     .05       0  4374.9      .1       0  4428.4     .05       0
  4600.1      .1       0  4955.5     .12       0    4995     .07       0
    5001     .12       0  5299.2      .1       0
Bank Sta=4962.6,5019.9
XS Rating Curve= 0 ,0
Exp/Cntr=0.3,0.1

Type RM Length L Ch R = 1 ,22264   ,434,434,434
BEGIN DESCRIPTION:
UNT001 IN PECR 41.0
END DESCRIPTION:
XS GIS Cut Line= 3
      2294921.35     13254618.66      2295008.16     13254080.46
       2295034.2     13252925.91
#Sta/Elev= 30
    4042  164.93  4165.4  159.93  4374.2  147.57  4509.8  140.84  4540.2  140.25
  4586.5   137.1  4715.1  132.77  4800.8  128.46  4834.7  123.79  4870.8   121.9
  4898.1  122.35  4920.8  122.86  4940.9   121.5  4970.9  122.94  4990.9     118
  4997.9  115.11  5000.6  114.61  5003.9  115.11  5010.9  115.64  5020.9  121.67
  5030.9  124.83  5070.9  124.25  5100.9  127.69  5110.9  126.94  5147.4  128.18
  5190.9  128.79  5310.9  136.18    5471  143.54    5651  153.67    5742  156.35
#Mann= 8 ,-1 , 0
    4042     .05       0  4374.2      .1       0  4715.1     .05       0
  4834.7     .16       0  4898.1     .05       0  4997.9     .04       0
  5003.9     .05       0  5147.4      .1       0
Bank Sta=4970.9,5030.9
XS Rating Curve= 0 ,0
Exp/Cntr=0.3,0.1

Type RM Length L Ch R = 1 ,21830   ,646,646,646
BEGIN DESCRIPTION:
UNT001 IN PECR 40.0
END DESCRIPTION:
XS GIS Cut Line= 3
       2295173.1     13254601.27      2295329.34     13254002.33
      2295676.13     13252970.64
#Sta/Elev= 30
  4138.4  157.71  4177.8   156.3  4253.6  156.13    4329  152.41    4422  144.74
  4491.3  141.35  4496.5  140.07  4587.3  137.19  4653.2   133.7  4713.6  133.47
  4794.5  133.05  4831.2  131.69  4865.3  128.55    4932  120.97  4968.5  122.17
  4974.2  122.01  4983.6  119.28  4988.8  119.48  4995.3  113.82  5002.8  113.01
  5005.6  112.51  5008.8  113.01  5015.1  120.24  5020.4  119.43  5026.9  121.63
  5117.7  121.41  5195.7   125.3    5304  124.92  5644.1  132.61  5845.8  144.13
#Mann= 8 ,-1 , 0
  4138.4      .1       0  4713.6     .12       0  4865.3     .05       0
  4968.5     .16       0  5002.8     .07       0  5008.8     .16       0
  5117.7      .1       0  5644.1     .05       0
Bank Sta=4974.2,5026.9
XS Rating Curve= 0 ,0
Exp/Cntr=0.3,0.1

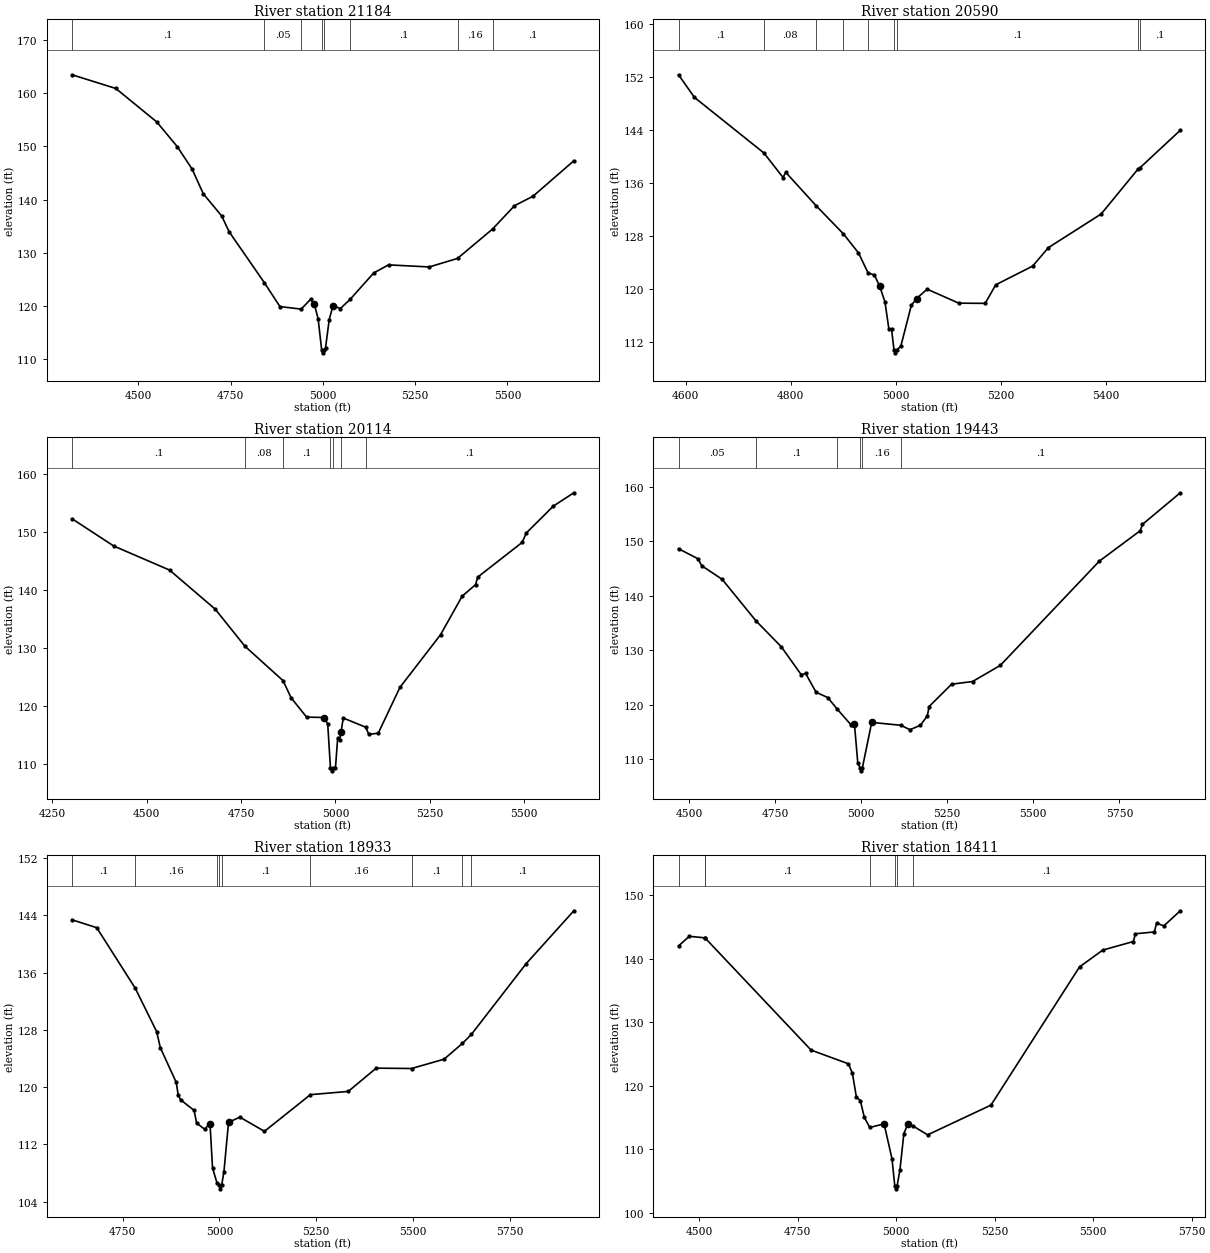
Type RM Length L Ch R = 1 ,21184   ,594,594,594
BEGIN DESCRIPTION:
UNT001 IN PECR 39.0
END DESCRIPTION:
XS GIS Cut Line= 2
      2296093.23     13254340.89       2295971.7     13252986.73
#Sta/Elev= 30
  4320.4  163.46  4438.9  160.89  4550.1  154.59  4605.6  149.95  4645.7  145.74
  4675.9  141.12  4726.1  136.92  4746.1  133.97  4841.8  124.38  4883.6  119.93
  4941.3  119.45    4967  121.32  4977.1  120.32  4987.1  117.63  4996.8  111.74
  4999.5  111.24  5002.8  111.74  5007.2  112.19  5017.2  117.49  5027.3   120.1
  5047.3  119.56  5073.8  121.28  5137.7  126.24  5177.9  127.76  5288.3  127.37
  5364.8  128.97  5459.9   134.5  5519.2  138.87  5569.4  140.65    5680  147.31
#Mann= 8 ,-1 , 0
  4320.4      .1       0  4841.8     .05       0  4941.3     .16       0
  4996.8     .07       0  5002.8     .16       0  5073.8      .1       0
  5364.8     .16       0  5459.9      .1       0
Bank Sta=4977.1,5027.3
XS Rating Curve= 0 ,0
Exp/Cntr=0.3,0.1

Type RM Length L Ch R = 1 ,20590   ,476,476,476
BEGIN DESCRIPTION:
UNT001 IN PECR 38.0
END DESCRIPTION:
XS GIS Cut Line= 3
      2296537.72     13254096.88      2296587.72     13253696.85
      2296637.72     13253146.86
#Sta/Elev= 30
  4586.2  152.37  4616.5  148.96  4748.8  140.58  4785.3  136.88  4790.3  137.67
    4848  132.64  4900.2  128.38  4928.9  125.51  4947.2  122.48  4959.1  122.19
  4969.2  120.49  4979.3  118.12  4986.8  114.01  4991.8  114.01  4996.4  110.94
  4999.1  110.44  5002.4  110.94  5009.4  111.42  5029.5   117.6  5039.5  118.63
  5059.6  120.04  5119.9  117.93  5170.1   117.9  5190.2   120.7  5260.5  123.52
  5290.6  126.31    5391  131.38  5460.8  138.12  5464.6  138.33  5541.6     144
#Mann= 9 ,-1 , 0
  4586.2      .1       0  4748.8     .08       0    4848      .1       0
  4900.2     .08       0  4947.2      .1       0  4996.4     .07       0
  5002.4      .1       0  5460.8     .16       0  5464.6      .1       0
Bank Sta=4969.2,5039.5
XS Rating Curve= 0 ,0
Exp/Cntr=0.3,0.1

Type RM Length L Ch R = 1 ,20114   ,671,671,671
BEGIN DESCRIPTION:
UNT001 IN PECR 37.0
END DESCRIPTION:
XS GIS Cut Line= 3
      2296692.19     13254175.94      2296969.96     13253941.57
      2297204.34     13253004.06
#Sta/Elev= 30
  4301.9  152.25    4412  147.57  4560.3  143.41  4681.2  136.68  4760.1  130.29
  4861.2  124.35  4882.2  121.42  4923.4  118.08  4969.8  118.01  4979.4   116.9
  4986.7  109.32  4989.5  108.82  4992.7  109.32    5000  109.37  5005.9  114.52
    5011  114.09  5014.7  115.55  5020.7  117.92  5080.3  116.33  5088.3   115.1
  5113.4  115.31  5170.8   123.2  5278.4  132.27  5335.7  138.91  5371.1  140.89
    5377   142.2  5494.8  148.18  5505.8  149.81  5577.3  154.43  5631.7  156.73
#Mann= 7 ,-1 , 0
  4301.9      .1       0  4760.1     .08       0  4861.2      .1       0
  4986.7     .07       0  4992.7      .1       0  5014.7     .16       0
  5080.3      .1       0
Bank Sta=4969.8,5014.7
XS Rating Curve= 0 ,0
Exp/Cntr=0.3,0.1

Type RM Length L Ch R = 1 ,19443   ,510,510,510
BEGIN DESCRIPTION:
UNT001 IN PECR 36.0
END DESCRIPTION:
XS GIS Cut Line= 3
      2297721.29     13254312.59      2297587.32     13253332.93
       2297412.1     13252899.05
#Sta/Elev= 30
  4469.8  148.66  4526.1  146.82  4537.1  145.54  4596.7  143.02  4694.5   135.4
  4768.3  130.62    4826  125.49  4838.9  125.71  4869.2  122.26  4903.3  121.27
  4930.2  119.18  4970.1   116.3  4980.6  116.36  4990.3  109.22  4997.4   108.3
  5000.2   107.8  5003.4   108.3  5030.7  116.71  5115.4  116.18  5141.7  115.36
    5172  116.18  5192.2   117.9  5197.3  119.63  5262.8  123.74  5323.4  124.23
  5404.1   127.2  5691.6  146.38  5810.2  151.97  5816.8  153.14  5926.5  158.95
#Mann= 6 ,-1 , 0
  4469.8     .05       0  4694.5      .1       0  4930.2     .16       0
  4997.4     .07       0  5003.4     .16       0  5115.4      .1       0
Bank Sta=4980.6,5030.7
XS Rating Curve= 0 ,0
Exp/Cntr=0.3,0.1

Type RM Length L Ch R = 1 ,18933   ,522,522,522
BEGIN DESCRIPTION:
UNT001 IN PECR 35.0
END DESCRIPTION:
XS GIS Cut Line= 2
      2298219.49     13254038.77      2297902.72     13252781.77
#Sta/Elev= 30
  4619.4  143.36  4683.1  142.26  4782.7   133.8  4837.9  127.75  4847.4  125.51
  4888.5  120.66  4893.7  118.87  4899.8  118.23  4934.7  116.75  4941.1  114.98
  4961.7  114.13  4975.8   114.9  4982.3  108.71  4993.7  106.64  4999.9   106.3
  5002.7   105.8  5005.9   106.3  5011.8  108.22  5023.6  115.08  5052.8  115.81
  5116.4  113.83  5235.2  118.95  5332.9   119.4  5405.1  122.65  5496.5   122.6
  5580.5   123.9  5627.8   126.1  5650.9  127.35  5792.4  137.23  5915.7  144.62
#Mann= 9 ,-1 , 0
  4619.4      .1       0  4782.7     .16       0  4993.7      .1       0
  4999.9     .07       0  5005.9      .1       0  5235.2     .16       0
  5496.5      .1       0  5627.8     .16       0  5650.9      .1       0
Bank Sta=4975.8,5023.6
XS Rating Curve= 0 ,0
Exp/Cntr=0.3,0.1

Type RM Length L Ch R = 1 ,18411   ,463,463,463
BEGIN DESCRIPTION:
UNT001 IN PECR 34.0
END DESCRIPTION:
XS GIS Cut Line= 4
      2298446.05       13253918.      2298526.61      13253590.7
      2298587.03     13252976.46      2298707.35     13252680.67
#Sta/Elev= 30
  4447.6  142.03    4475  143.55  4514.4  143.31    4515  143.29  4784.1  125.64
    4879  123.48    4889  121.98  4899.1  118.24  4909.1  117.69  4919.2  115.06
    4933  113.46  4969.4  114.03  4989.5  108.52  4996.5   104.3  4999.3   103.8
  5002.5   104.3  5009.6  106.75  5019.6  112.49  5029.7  114.03    5044  113.65
  5079.9   112.3  5240.7  116.98  5465.4  138.73  5524.4  141.38    5602  142.73
  5607.4  143.95  5655.5  144.24  5660.9  145.61  5679.6   145.2  5721.2  147.57
#Mann= 7 ,-1 , 0
  4447.6      .1       0  4514.4     .16       0    4515      .1       0
    4933     .16       0  4996.5     .07       0  5002.5     .16       0
    5044      .1       0
Bank Sta=4969.4,5029.7
XS Rating Curve= 0 ,0
Exp/Cntr=0.3,0.1