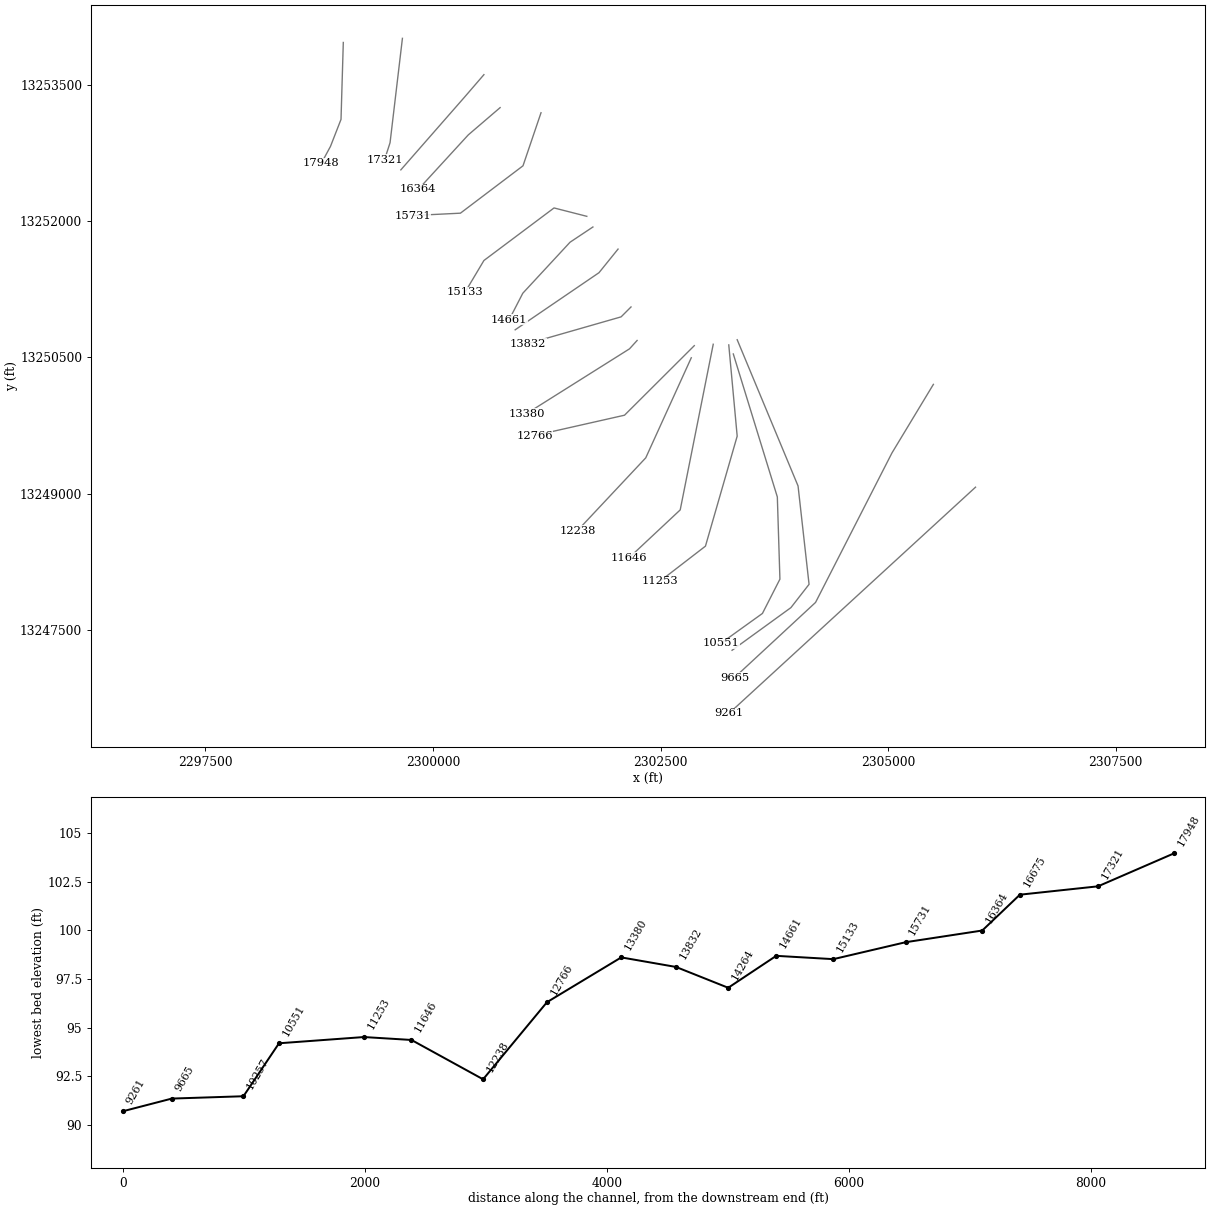
HEC-RAS study UNT001 IN PECR.prj: UNT001 IN PECR Base Level Engineering

--- UNT001 IN PECR.g01 (geometry) --- (continued)

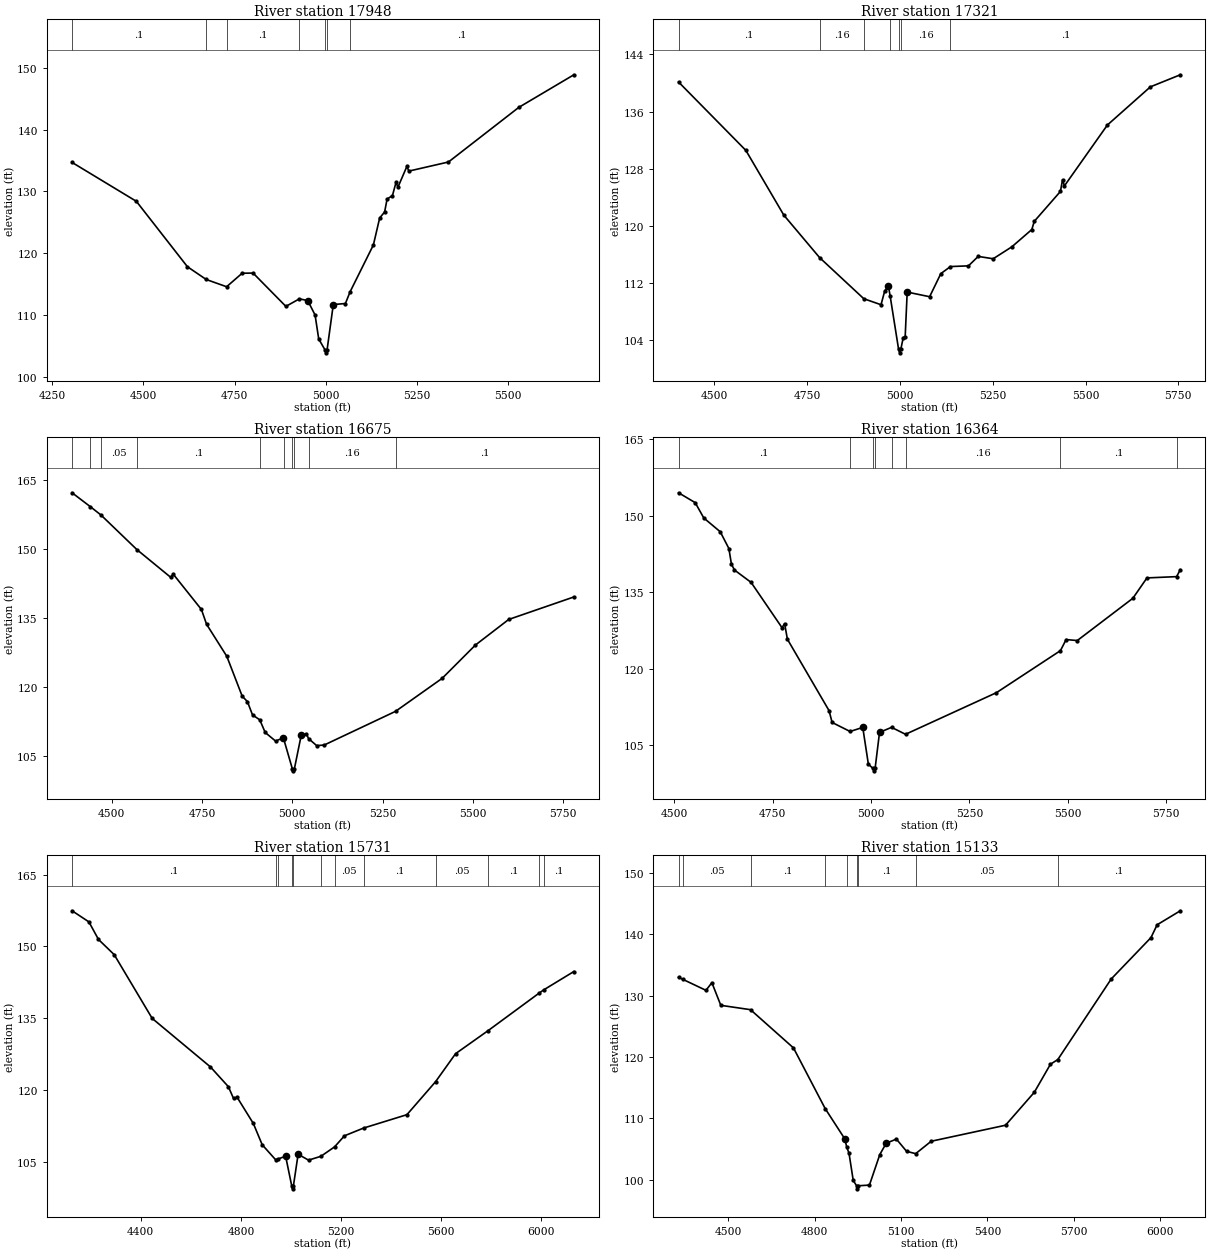
Type RM Length L Ch R = 1 ,17948   ,627,627,627
BEGIN DESCRIPTION:
UNT001 IN PECR 33.0
END DESCRIPTION:
XS GIS Cut Line= 4
      2299014.98     13253963.22      2298989.81     13253117.43
      2298874.01     13252820.38      2298773.33     13252634.13
#Sta/Elev= 30
  4304.2  134.69  4480.6  128.41  4620.7  117.85  4672.3  115.79  4728.2  114.62
  4770.8   116.8  4800.8  116.83  4890.8  111.45    4928  112.67  4950.8  112.38
  4970.9  110.06  4980.9  106.19  4997.9  104.45  5000.6  103.95  5003.9  104.45
  5020.9  111.75  5054.1  111.91  5067.2  113.83  5130.9  121.37  5148.1  125.72
  5161.7  126.69  5168.5  128.78  5183.2  129.34    5193  131.47  5198.3   130.7
  5222.8  134.05  5228.2  133.29  5336.9  134.76  5529.7  143.57  5680.9  148.84
#Mann= 7 ,-1 , 0
  4304.2      .1       0  4672.3     .16       0  4728.2      .1       0
    4928     .16       0  4997.9     .07       0  5003.9     .16       0
  5067.2      .1       0
Bank Sta=4950.8,5020.9
XS Rating Curve= 0 ,0
Exp/Cntr=0.3,0.1

Type RM Length L Ch R = 1 ,17321   ,646,646,646
BEGIN DESCRIPTION:
UNT001 IN PECR 32.0
END DESCRIPTION:
XS GIS Cut Line= 3
      2299664.46     13254008.56      2299528.52     13252860.66
      2299468.09     13252674.34
#Sta/Elev= 30
  4403.6  140.15    4585  130.58  4687.3  121.52  4783.5  115.59  4902.7  109.83
  4949.1  108.99  4959.2  110.95  4969.2  111.55  4973.8  110.17  4996.4  102.76
  4999.2  102.26  5002.4  102.76    5009   104.4  5014.1  104.43  5019.6  110.76
    5080  110.11  5110.2  113.34  5136.2  114.33  5184.7  114.43  5210.9  115.75
  5251.2  115.42  5301.5  117.09  5355.3  119.51    5362  120.66  5432.4  124.84
  5438.1  126.48  5443.2  125.62  5558.9  134.13  5674.7  139.47  5755.4  141.16
#Mann= 7 ,-1 , 0
  4403.6      .1       0  4783.5     .16       0  4902.7      .1       0
  4973.8     .16       0  4996.4     .07       0  5002.4     .16       0
  5136.2      .1       0
Bank Sta=4969.2,5019.6
XS Rating Curve= 0 ,0
Exp/Cntr=0.3,0.1

Type RM Length L Ch R = 1 ,16675   ,311,311,311
BEGIN DESCRIPTION:
UNT001 IN PECR 31.0
END DESCRIPTION:
XS GIS Cut Line= 3
      2300559.76     13253609.27      2300350.41     13253366.42
      2299647.08     13252562.61
#Sta/Elev= 30
  4390.6  162.15  4441.6  159.11  4470.4  157.34  4570.2  149.81  4663.1  143.84
  4670.8  144.48  4748.6  136.83  4762.8  133.63  4818.8  126.68  4861.5  118.01
  4875.8  116.86    4890  113.96    4910   112.9  4925.1  110.15  4953.6   108.3
  4975.4  108.97  4975.9  108.85    5000  102.33  5002.7  101.83    5006  102.33
  5024.8  109.56    5039  109.87  5045.1  108.83  5067.5   107.3  5088.4  107.43
  5285.7  114.73  5414.9   121.9  5506.9  129.12    5599  134.67  5779.3  139.55
#Mann= 10 ,-1 , 0
  4390.6     .05       0  4441.6      .1       0  4470.4     .05       0
  4570.2      .1       0    4910     .16       0  4975.9      .1       0
    5000     .07       0    5006      .1       0  5045.1     .16       0
  5285.7      .1       0
Bank Sta=4975.4,5024.8
XS Rating Curve= 0 ,0
Exp/Cntr=0.3,0.1

Type RM Length L Ch R = 1 ,16364   ,633,633,633
BEGIN DESCRIPTION:
UNT001 IN PECR 30.0
END DESCRIPTION:
XS GIS Cut Line= 3
      2300737.75     13253246.88      2300387.72     13252946.85
      2299837.69     13252346.82
#Sta/Elev= 30
  4510.9  154.47  4553.2  152.54  4575.1  149.53  4616.9  146.83  4638.8  143.55
  4645.4  140.46  4653.1  139.33  4695.3  136.91  4773.8  128.04  4780.4  128.84
  4787.5  125.78  4893.4  111.78  4901.1  109.47  4946.8   107.7    4979   108.5
  4993.2  101.31  5004.4  100.49  5007.1   99.99  5010.4  100.49  5021.6  107.52
  5052.1  108.51  5087.7  107.15  5318.8  115.31  5481.3  123.54  5495.7  125.71
  5524.1  125.52  5665.3   133.8  5701.1  137.79  5776.4  138.04  5785.9  139.41
#Mann= 8 ,-1 , 0
  4510.9      .1       0  4946.8     .16       0  5004.4     .07       0
  5010.4     .16       0  5052.1      .1       0  5087.7     .16       0
  5481.3      .1       0  5776.4     .08       0
Bank Sta=4979,5021.6
XS Rating Curve= 0 ,0
Exp/Cntr=0.3,0.1

Type RM Length L Ch R = 1 ,15731   ,598,598,598
BEGIN DESCRIPTION:
UNT001 IN PECR 29.0
END DESCRIPTION:
XS GIS Cut Line= 4
      2301187.04     13253190.63      2300989.12     13252607.29
      2300301.62     13252086.46      2299775.58     13252060.41
#Sta/Elev= 30
  4125.4  157.43  4192.7  155.11    4231  151.44  4293.8  148.27  4445.5  134.97
  4678.5  124.83  4749.9  120.72  4770.7  118.25  4785.3  118.47  4849.8  113.03
  4885.2  108.59  4938.7  105.47  4949.5  105.64  4978.8   106.2  5003.6   99.89
  5006.4   99.39  5009.6   99.89  5028.7  106.61  5070.3  105.38  5119.7  106.18
  5174.4  108.15  5213.9  110.46    5290  112.07  5463.5  114.87  5578.1  121.76
  5657.9   127.6  5788.1  132.42  5991.7  140.24  6009.5   140.9  6130.6  144.75
#Mann= 12 ,-1 , 0
  4125.4      .1       0  4938.7     .16       0  4949.5     .05       0
  5003.6     .04       0  5009.6     .05       0  5119.7      .1       0
  5174.4     .05       0    5290      .1       0  5578.1     .05       0
  5788.1      .1       0  5991.7     .05       0  6009.5      .1       0
Bank Sta=4978.8,5028.7
XS Rating Curve= 0 ,0
Exp/Cntr=0.3,0.1

Type RM Length L Ch R = 1 ,15133   ,472,472,472
BEGIN DESCRIPTION:
UNT001 IN PECR 28.0
END DESCRIPTION:
XS GIS Cut Line= 4
      2301690.08     13252051.86      2301330.05     13252143.96
      2300559.74     13251566.22      2300350.39     13251214.52
#Sta/Elev= 30
  4326.6  132.98  4341.2  132.65  4421.9  130.85  4442.5   132.1  4473.5  128.41
  4576.7   127.7  4726.1  121.47  4836.1   111.6  4904.6  106.64  4910.6  105.41
  4919.1   104.3  4933.7   99.89  4945.3   99.02  4948.1   98.52  4951.3   99.02
    4990   99.13  5026.1  104.11  5048.3  105.95  5083.7  106.62  5119.1  104.63
  5150.7  104.25  5204.6  106.27  5462.9  108.88  5562.9  114.24  5619.1  118.82
  5644.5  119.57  5830.2   132.7  5968.4  139.44  5989.8  141.53  6070.4  143.81
#Mann= 9 ,-1 , 0
  4326.6      .1       0  4341.2     .05       0  4576.7      .1       0
  4836.1     .05       0  4910.6      .1       0  4945.3     .07       0
  4951.3      .1       0  5150.7     .05       0  5644.5      .1       0
Bank Sta=4904.6,5048.3
XS Rating Curve= 0 ,0
Exp/Cntr=0.3,0.1

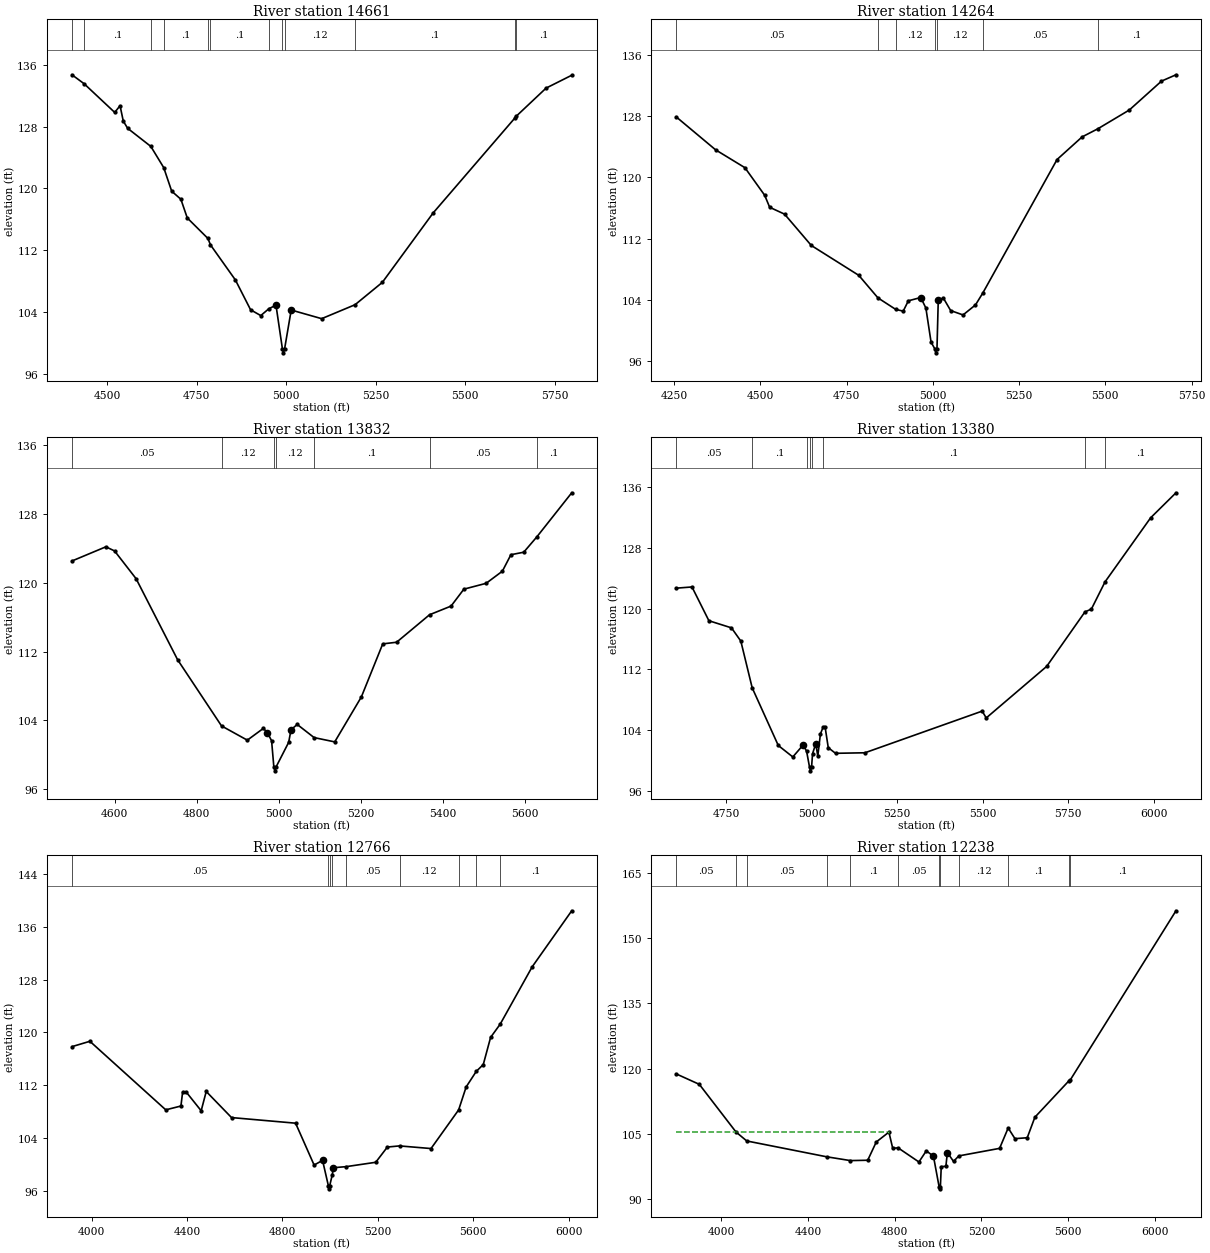
Type RM Length L Ch R = 1 ,14661   ,397,397,397
BEGIN DESCRIPTION:
UNT001 IN PECR 27.0
END DESCRIPTION:
XS GIS Cut Line= 4
      2301757.08     13251934.63      2301505.89     13251767.17
      2300986.76     13251206.18      2300836.03     13250913.09
#Sta/Elev= 30
  4401.8  134.74  4435.7  133.58  4521.2  129.86  4536.1  130.73  4545.1  128.74
  4557.3   127.8  4622.1  125.45  4658.1   122.7  4680.3  119.65    4706   118.6
  4723.8  116.18  4781.5  113.52  4788.6  112.69  4858.2  108.14  4900.7  104.27
  4929.1  103.52  4951.7  104.41  4971.6  104.87  4989.6   99.19  4992.3   98.69
  4995.6   99.19  5014.1  104.24  5099.2  103.12  5192.5  104.93  5268.7  107.83
  5410.4  116.82  5639.1  129.15  5642.7  129.37  5725.9  133.01  5797.6  134.68
#Mann= 12 ,-1 , 0
  4401.8     .05       0  4435.7      .1       0  4622.1     .05       0
  4658.1      .1       0  4781.5     .05       0  4788.6      .1       0
  4951.7     .12       0  4989.6     .07       0  4995.6     .12       0
  5192.5      .1       0  5639.1     .05       0  5642.7      .1       0
Bank Sta=4971.6,5014.1
XS Rating Curve= 0 ,0
Exp/Cntr=0.3,0.1

Type RM Length L Ch R = 1 ,14264   ,432,432,432
BEGIN DESCRIPTION:
UNT001 IN PECR 26.0
END DESCRIPTION:
XS GIS Cut Line= 3
      2302033.38     13251691.81      2301824.06     13251432.25
      2300903.02     13250804.27
#Sta/Elev= 30
  4256.4  127.93  4370.5  123.62  4455.5  121.28  4512.8  117.67  4527.2   116.1
  4570.4   115.2  4647.9   111.1  4785.5  107.19    4841  104.24  4892.6  102.73
  4914.2  102.51  4929.1  103.86    4965  104.29  4979.9  102.91  4994.9   98.45
    5006   97.55  5008.8   97.05    5012   97.55  5015.8  104.01  5030.8   104.2
  5051.7  102.58  5087.6  102.01  5123.6  103.32  5144.6  104.86    5360  122.35
  5432.6  125.31  5478.5  126.38  5569.4  128.83  5662.6  132.61  5704.6  133.44
#Mann= 7 ,-1 , 0
  4256.4     .05       0    4841      .1       0  4892.6     .12       0
    5006     .07       0    5012     .12       0  5144.6     .05       0
  5478.5      .1       0
Bank Sta=4965,5015.8
XS Rating Curve= 0 ,0
Exp/Cntr=0.3,0.1

Type RM Length L Ch R = 1 ,13832   ,452,452,452
BEGIN DESCRIPTION:
UNT001 IN PECR 25.0
END DESCRIPTION:
XS GIS Cut Line= 3
      2302175.74     13251055.48      2302066.88     13250946.62
      2301045.34     13250653.55
#Sta/Elev= 30
  4496.3  122.55  4578.8   124.2    4600  123.72  4652.4  120.49  4753.4  111.06
  4860.4  103.35  4923.2  101.69  4962.2  103.06  4971.9  102.58  4982.3  101.62
  4987.7   98.62  4990.4   98.12  4993.7   98.62  5023.9  101.44  5029.6  102.91
  5044.7  103.52  5085.8  101.99    5136  101.49  5200.8  106.72  5252.9   112.9
  5286.6  113.09  5366.8  116.29  5419.2   117.3  5450.4  119.27  5504.6  119.95
  5544.1  121.36  5564.9  123.28  5596.1  123.57  5628.1  125.36    5713  130.49
#Mann= 7 ,-1 , 0
  4496.3     .05       0  4860.4     .12       0  4987.7     .07       0
  4993.7     .12       0  5085.8      .1       0  5366.8     .05       0
  5628.1      .1       0
Bank Sta=4971.9,5029.6
XS Rating Curve= 0 ,0
Exp/Cntr=0.3,0.1

Type RM Length L Ch R = 1 ,13380   ,614,614,614
BEGIN DESCRIPTION:
UNT001 IN PECR 24.0
END DESCRIPTION:
XS GIS Cut Line= 3
      2302242.74     13250687.09      2302158.98     13250594.95
       2301028.6     13249883.23
#Sta/Elev= 30
  4604.3  122.68  4650.4  122.84  4699.8  118.39  4765.8  117.45  4793.1  115.71
  4826.3  109.55  4902.6  101.95    4945  100.44  4975.6  102.04  4985.4  101.17
  4993.8   99.11  4996.5   98.61  4999.8   99.11  5002.7  100.87  5012.1  102.19
    5018  100.55  5025.7  103.48  5033.6  104.37  5039.2  104.43  5048.6  101.66
  5069.8  100.92  5155.7  100.99  5498.3  106.48  5510.2  105.58  5686.7  112.37
  5798.7  119.56  5817.4  119.92  5857.3  123.51  5990.5  131.95  6064.6  135.25
#Mann= 8 ,-1 , 0
  4604.3     .05       0  4826.3      .1       0  4985.4     .12       0
  4993.8     .07       0  4999.8     .12       0  5033.6      .1       0
  5798.7     .05       0  5857.3      .1       0
Bank Sta=4975.6,5012.1
XS Rating Curve= 0 ,0
Exp/Cntr=0.3,0.1

Type RM Length L Ch R = 1 ,12766   ,528,528,528
BEGIN DESCRIPTION:
UNT001 IN PECR 23.0
END DESCRIPTION:
XS GIS Cut Line= 3
      2302870.89     13250630.02       2302104.3     13249865.44
      2301115.84     13249642.01
#Sta/Elev= 30
  3917.3  117.84  3992.5  118.65  4310.7  108.27  4374.3  108.85  4381.4  110.96
  4395.5  111.01  4459.2  108.13  4480.4  111.05  4586.5   107.1  4855.2  106.25
  4932.9   99.91  4968.3  100.62  4992.5   96.81  4995.2   96.31  4998.5   96.81
  5008.4   98.34  5014.1   99.51  5067.2   99.67  5191.3  100.33  5240.2  102.64
  5291.2  102.81  5423.2  102.41    5539  108.26  5570.6  111.74  5613.1   114.1
  5642.4  115.13  5673.1  119.24  5713.1  121.23  5847.4  129.92  6013.4  138.41
#Mann= 9 ,-1 , 0
  3917.3     .05       0  4992.5     .03       0  4998.5     .05       0
  5008.4      .1       0  5067.2     .05       0  5291.2     .12       0
    5539      .1       0  5613.1     .08       0  5713.1      .1       0
Bank Sta=4968.3,5014.1
XS Rating Curve= 0 ,0
Exp/Cntr=0.3,0.1

Type RM Length L Ch R = 1 ,12238   ,592,592,592
BEGIN DESCRIPTION:
UNT001 IN PECR 22.0
END DESCRIPTION:
XS GIS Cut Line= 3
      2302837.73     13250496.89      2302337.72     13249396.85
      2301587.74     13248596.87
#Sta/Elev= 30
  3792.3  118.76  3898.9  116.36  4068.2   105.4  4117.7  103.35  4485.5   99.72
  4595.5   98.84  4675.5   98.92    4715  103.12  4773.3  105.38  4790.8  101.66
  4815.5  101.77  4911.7   98.52  4945.7  101.08  4978.7   99.84  5004.7   92.85
  5007.5   92.35  5010.7   92.85  5014.6   97.45    5036   97.53  5042.9  100.69
  5071.2   98.65  5095.9   99.92  5283.7  101.65  5323.3  106.33  5354.5  103.88
  5411.2  104.09  5446.4   108.8  5601.8  117.08  5608.7  117.29  6097.2  156.24
#Mann= 12 ,-1 , 0
  3792.3     .05       0  4068.2      .1       0  4117.7     .05       0
  4485.5     .12       0  4595.5      .1       0  4815.5     .05       0
  5004.7    .035       0  5010.7     .05       0  5095.9     .12       0
  5323.3      .1       0  5601.8     .05       0  5608.7      .1       0
#XS Ineff= 2 , 0
            4775  105.51
Permanent Ineff=
       F       F
Bank Sta=4978.7,5042.9
XS Rating Curve= 0 ,0
Exp/Cntr=0.3,0.1

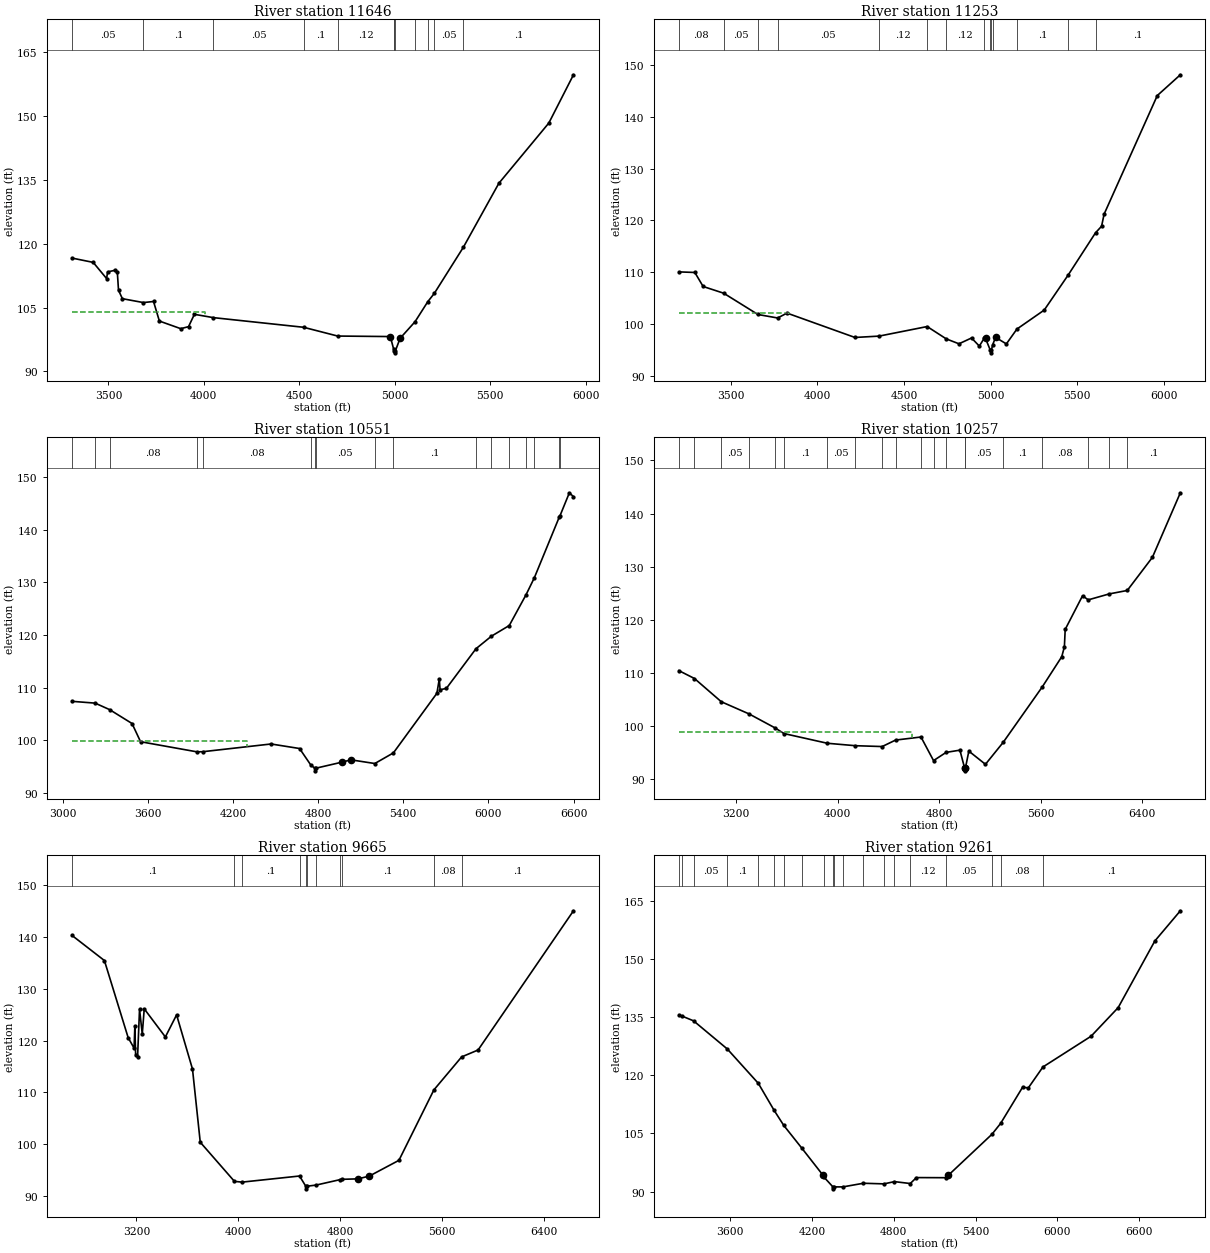
Type RM Length L Ch R = 1 ,11646   ,393,393,393
BEGIN DESCRIPTION:
UNT001 IN PECR 21.0
END DESCRIPTION:
XS GIS Cut Line= 3
      2303078.91     13250645.52       2302716.1     13248824.38
      2302154.09     13248297.93
#Sta/Elev= 30
  3309.6  116.61  3420.4   115.6  3490.7   111.8  3495.8  113.36  3532.6  113.73
  3546.9  113.26    3553  109.06  3573.3  107.08  3683.2  106.17  3736.5  106.42
  3767.1  101.83  3879.2  100.04    3920  100.52  3950.5  103.41  4050.4  102.63
  4522.6  100.37  4701.2   98.31  4977.2   98.19  4994.2   95.27  4997.9   94.87
  5000.6   94.37  5003.9   94.87  5028.3   97.78  5106.5  101.67  5173.4  106.38
  5207.8  108.34    5360  119.17  5545.8  134.17  5807.6  148.31  5936.6  159.63
#Mann= 12 ,-1 , 0
  3309.6     .05       0  3683.2      .1       0  4050.4     .05       0
  4522.6      .1       0  4701.2     .12       0  4994.2      .1       0
  4997.9     .07       0  5003.9      .1       0  5106.5     .12       0
  5173.4      .1       0  5207.8     .05       0    5360      .1       0
#XS Ineff= 2 , 0
         4005.68  104.02
Permanent Ineff=
       F       F
Bank Sta=4977.2,5028.3
XS Rating Curve= 0 ,0
Exp/Cntr=0.3,0.1

Type RM Length L Ch R = 1 ,11253   ,702,702,702
BEGIN DESCRIPTION:
UNT001 IN PECR 20.0
END DESCRIPTION:
XS GIS Cut Line= 4
      2303249.63     13250638.35       2303342.1     13249635.33
      2302993.53     13248426.01       2302495.6     13248041.89
#Sta/Elev= 30
  3200.5   110.1  3292.4  109.99  3340.3  107.29  3458.8     106  3656.6   101.9
  3770.3  101.23  3824.6  102.17  4216.6   97.48    4356   97.74  4633.5   99.58
  4744.2    97.2  4817.2   96.26  4889.7   97.38  4934.7   95.82  4962.2   97.29
 4970.74   97.28  4998.1   95.02  5000.9   94.52  5004.1   95.02  5012.4   96.12
  5028.4    97.5  5090.8   96.24  5151.9    99.1  5309.3  102.75  5446.9  109.46
  5605.4  117.62  5640.5  118.89    5655  121.21  5962.1  144.04  6095.2  148.04
#Mann= 14 ,-1 , 0
  3200.5     .08       0  3458.8     .05       0  3656.6      .1       0
  3770.3     .05       0    4356     .12       0  4633.5      .1       0
  4744.2     .12       0  4962.2     .05       0  4998.1    .035       0
  5004.1     .05       0  5012.4     .12       0  5151.9      .1       0
  5446.9     .05       0  5605.4      .1       0
#XS Ineff= 2 , 0
         3833.24  102.24
Permanent Ineff=
       F       F
Bank Sta=4970.74,5028.4
XS Rating Curve= 0 ,0
Exp/Cntr=0.3,0.1

Type RM Length L Ch R = 1 ,10551   ,294,294,294
BEGIN DESCRIPTION:
UNT001 IN PECR 19.0
END DESCRIPTION:
XS GIS Cut Line= 5
      2303299.42     13250538.78      2303783.15     13248966.65
      2303811.61     13248063.21      2303619.54     13247686.19
      2303164.23     13247358.93
#Sta/Elev= 30
  3066.5   107.4  3229.1  107.06  3331.5  105.82    3489  103.19  3549.2   99.73
    3946   97.81  3986.2   97.83  4468.6    99.3  4669.3   98.44  4750.2   95.24
  4778.2    94.7  4780.9    94.2  4784.2    94.7  4971.3   95.87  5031.3   96.29
  5199.6   95.59  5330.5   97.61    5637  108.93  5653.7  111.64  5659.3   109.6
  5703.7  109.86  5912.2  117.39  6020.9  119.77  6146.8   121.8  6265.1  127.65
  6323.3  130.86  6499.9  142.45  6502.9  142.56  6570.2  147.01  6599.1  146.27
#Mann= 17 ,-1 , 0
  3066.5     .08       0  3229.1     .05       0  3331.5     .08       0
    3946      .1       0  3986.2     .08       0  4750.2     .05       0
  4778.2     .03       0  4784.2     .05       0  5199.6     .12       0
  5330.5      .1       0  5912.2     .08       0  6020.9      .1       0
  6146.8     .08       0  6265.1      .1       0  6323.3     .08       0
  6499.9      .1       0  6502.9     .08       0
#XS Ineff= 2 , 0
            4300   99.91
Permanent Ineff=
       F       F
Bank Sta=4971.3,5031.3
XS Rating Curve= 0 ,0
Exp/Cntr=0.3,0.1

Type RM Length L Ch R = 1 ,10257   ,592,592,592
BEGIN DESCRIPTION:
UNT001 IN PECR 18.0
END DESCRIPTION:
XS GIS Cut Line= 5
      2303342.11     13250695.27      2304010.79     13249087.58
      2304131.72      13248006.3      2303932.54     13247750.21
      2303285.95     13247281.26
#Sta/Elev= 30
  2749.6  110.37  2872.1  108.89  3083.5  104.51  3302.6  102.21  3506.2   99.59
  3577.6   98.51    3919   96.68  4140.3   96.22  4351.7   96.06  4457.3   97.28
  4657.6   97.86  4756.6   93.41  4855.7   94.96  4964.5   95.38  5001.7   91.98
  5004.5   91.48  5007.7   91.98  5034.9    95.2  5165.7   92.71  5305.6   96.85
    5614  107.32  5767.2     113    5788  114.86  5794.4  118.15  5931.1  124.49
  5976.1  123.72  6141.5  124.84  6283.6  125.49  6481.6  131.73    6702  143.91
#Mann= 20 ,-1 , 0
  2749.6     .05       0  2872.1      .1       0  3083.5     .05       0
  3302.6      .1       0  3506.2     .08       0  3577.6      .1       0
    3919     .05       0  4140.3      .1       0  4351.7     .05       0
  4457.3      .1       0  4657.6     .05       0  4756.6      .1       0
  4855.7     .05       0  5001.7     .04       0  5007.7     .05       0
  5305.6      .1       0    5614     .08       0  5976.1     .08       0
  6141.5      .1       0  6283.6      .1       0
#XS Ineff= 2 , 0
         4588.07   98.71
Permanent Ineff=
       F       F
Bank Sta=5001.7,5007.7
XS Rating Curve= 0 ,0
Exp/Cntr=0.3,0.1

Type RM Length L Ch R = 1 ,9665    ,404,404,404
BEGIN DESCRIPTION:
Mapping XS 0bbca69d
END DESCRIPTION:
XS GIS Cut Line= 4
      2305497.56     13250204.45      2305042.27     13249450.38
      2304202.86     13247807.12      2303313.65     13246981.94
#Sta/Elev= 30
  2694.3  140.34  2948.5  135.49  3135.4  120.56  3181.8  118.55  3187.6  122.78
  3193.8  117.22    3209  116.86  3224.5  126.08  3245.9  121.28  3261.4  126.16
  3427.4  120.72  3515.6  124.99  3640.5  114.51  3701.5  100.37  3970.2    92.8
  4030.9   92.66  4481.4   93.84  4530.6   91.86  4533.3   91.36  4536.6   91.86
  4610.4   92.08    4802   93.15    4816    93.2  4940.3   93.29  5029.2   93.82
  5262.3   96.87  5536.8  110.48  5754.7  116.86  5884.2   118.2  6633.5  145.11
#Mann= 11 ,-1 , 0
  2694.3      .1       0  3970.2     .05       0  4030.9      .1       0
  4481.4     .05       0  4530.6     .07       0  4536.6     .05       0
  4610.4      .1       0    4802     .05       0    4816      .1       0
  5536.8     .08       0  5754.7      .1       0
Bank Sta=4940.3,5029.2
XS Rating Curve= 0 ,0
Exp/Cntr=0.3,0.1

Type RM Length L Ch R = 1 ,9261    ,762,762,762
BEGIN DESCRIPTION:
UNT001 IN PECR 16.0
END DESCRIPTION:
XS GIS Cut Line= 2
      2305960.46     13249074.29       2303252.4     13246587.56
#Sta/Elev= 30
  3225.2  135.55  3248.1  135.24  3332.4  134.02    3580  126.76  3807.5   117.9
  3923.3  110.94  3993.9  107.06  4125.4  101.24  4279.8    94.3  4286.3   93.82
  4354.5   91.21  4357.3   90.71  4360.5   91.21  4427.1   91.21    4578   92.15
  4728.9   91.99  4805.4   92.57  4921.3   92.08  4966.7   93.61  5181.7   93.58
  5199.7   94.18  5520.5  104.78  5584.1  107.58  5744.8  116.89  5787.3  116.74
  5894.1  122.12  6247.3  130.05  6445.8  137.42  6714.7   154.6  6901.8  162.39
#Mann= 20 ,-1 , 0
  3225.2     .05       0  3248.1      .1       0  3332.4     .05       0
    3580      .1       0  3807.5     .05       0  3923.3      .1       0
  3993.9     .05       0  4125.4      .1       0  4286.3     .05       0
  4354.5     .07       0  4360.5     .05       0  4427.1     .12       0
    4578     .05       0  4728.9      .1       0  4805.4     .05       0
  4921.3     .12       0  5181.7     .05       0  5520.5      .1       0
  5584.1     .08       0  5894.1      .1       0
Bank Sta=4279.8,5199.7
XS Rating Curve= 0 ,0
Exp/Cntr=0.3,0.1