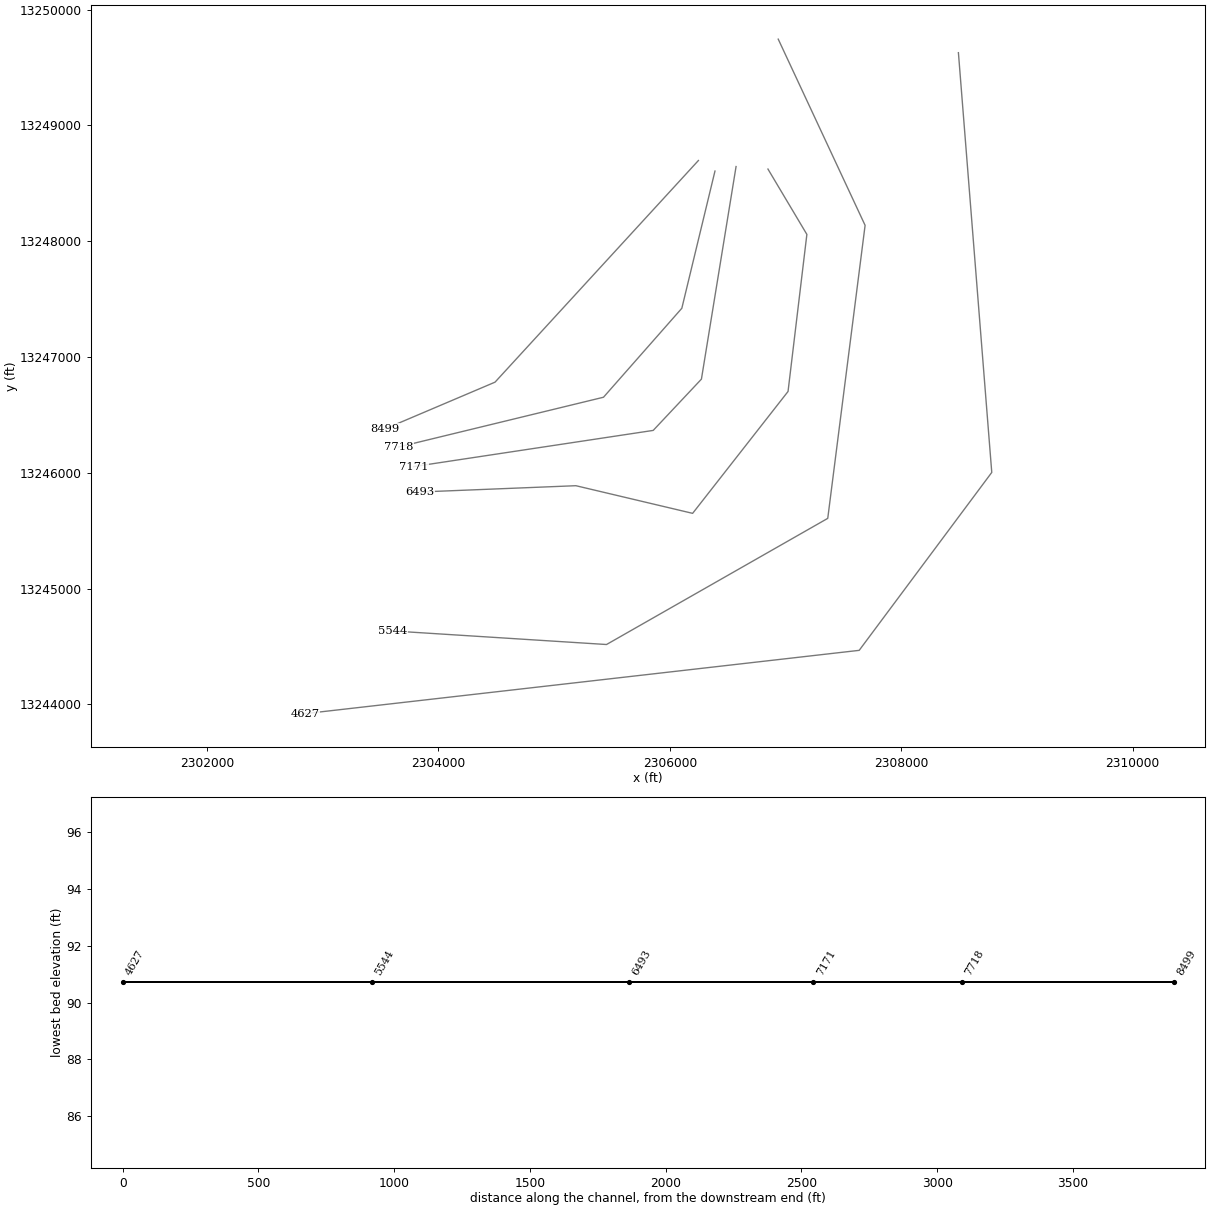
HEC-RAS study UNT001 IN PECR.prj: UNT001 IN PECR Base Level Engineering

--- UNT001 IN PECR.g01 (geometry) --- (continued)

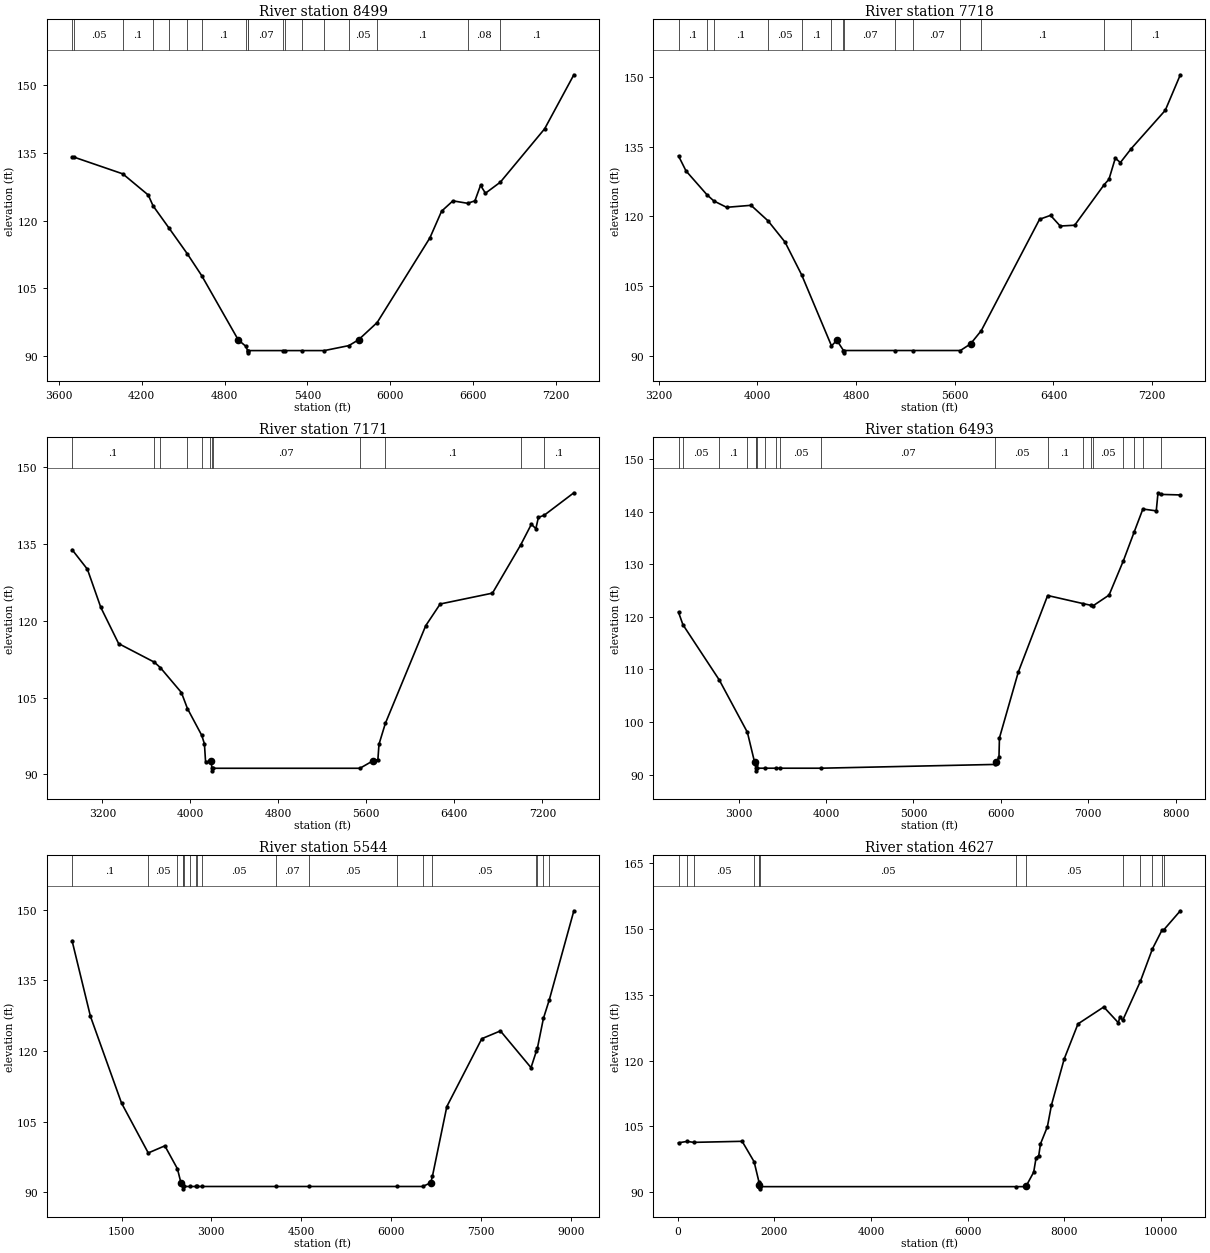
Type RM Length L Ch R = 1 ,8499    ,781,781,781
BEGIN DESCRIPTION:
UNT001 IN PECR 15.0
END DESCRIPTION:
XS GIS Cut Line= 3
      2306246.92     13248696.68      2304489.12     13246782.64
      2303538.61     13246378.99
#Sta/Elev= 30
  3696.5  134.14  3712.3  134.06  4063.7  130.37  4247.9  125.68  4282.8  123.28
  4397.1   118.4  4531.3  112.62  4634.4  107.83    4899   93.59  4953.5   92.17
  4966.9   91.21  4969.7   90.71  4972.9   91.21  5220.7   91.21  5240.8   91.21
  5358.6   91.21  5522.1   91.21  5699.6   92.31  5769.6    93.6  5904.6   97.43
  6286.3   116.2  6370.7   122.1  6452.5  124.39  6558.8  123.85  6611.8  124.39
  6652.6  127.84  6687.9  126.08  6795.8  128.53  7116.5  140.36  7327.9  152.33
#Mann= 18 ,-1 , 0
  3696.5      .1       0  3712.3     .05       0  4063.7      .1       0
  4282.8     .05       0  4397.1      .1       0  4531.3     .05       0
  4634.4      .1       0  4953.5     .07       0  4966.9     .07       0
  4972.9     .07       0  5220.7      .1       0  5240.8     .07       0
  5358.6     .12       0  5522.1     .07       0  5699.6     .05       0
  5904.6      .1       0  6558.8     .08       0  6795.8      .1       0
Bank Sta=4899,5769.6
XS Rating Curve= 0 ,0
Exp/Cntr=0.3,0.1

Type RM Length L Ch R = 1 ,7718    ,547,547,547
BEGIN DESCRIPTION:
UNT001 IN PECR 14.0
END DESCRIPTION:
XS GIS Cut Line= 4
      2306390.16     13248605.54       2306103.7     13247420.66
      2305426.62     13246652.43      2303655.74     13246222.73
#Sta/Elev= 30
  3362.2  132.99  3422.6  129.78  3593.1  124.64  3648.6  123.32  3751.8  121.96
  3949.7  122.39  4087.9  119.04    4225  114.49  4360.3  107.42  4601.4   92.21
  4644.7   93.39  4698.6   91.21  4701.4   90.71  4704.6   91.21  5117.1   91.21
  5262.4   91.21  5645.8   91.21  5727.6   92.62  5814.5   95.46  6287.3  119.39
    6376  120.23  6454.4  117.94  6571.4  118.11  6810.2  126.81  6849.2  127.97
  6900.7  132.51  6941.8  131.57  7030.3  134.58  7305.6  142.79  7427.5  150.42
#Mann= 14 ,-1 , 0
  3362.2      .1       0  3593.1     .05       0  3648.6      .1       0
  4087.9     .05       0  4360.3      .1       0  4601.4     .07       0
  4698.6     .07       0  4704.6     .07       0  5117.1     .12       0
  5262.4     .07       0  5645.8     .12       0  5814.5      .1       0
  6810.2     .08       0  7030.3      .1       0
Bank Sta=4644.7,5727.6
XS Rating Curve= 0 ,0
Exp/Cntr=0.3,0.1

Type RM Length L Ch R = 1 ,7171    ,678,678,678
BEGIN DESCRIPTION:
UNT001 IN PECR 13.0
END DESCRIPTION:
XS GIS Cut Line= 4
      2306572.45     13248644.58      2306272.98     13246808.68
      2305856.31     13246365.97      2303785.98     13246053.47
#Sta/Elev= 30
  2924.8  133.89  3064.3  130.06  3185.9  122.62    3348  115.55  3672.1  111.93
  3726.7  110.87  3918.7     106  3973.8  102.86  4103.9   97.63  4128.2   95.97
  4138.4   92.48  4174.9   92.56    4189    92.6  4196.2   91.21  4198.9   90.71
  4202.2   91.21  5541.6   91.21  5664.6   92.72    5705   92.89  5715.1    95.9
  5772.7   99.96  6139.9  119.04  6271.3  123.28  6746.7   125.4  7004.5  134.86
  7100.6  138.85  7141.1  137.98  7164.4  140.19  7216.9   140.6  7486.7  144.99
#Mann= 12 ,-1 , 0
  2924.8      .1       0  3672.1     .05       0  3726.7      .1       0
  3973.8     .05       0  4103.9      .1       0  4174.9     .07       0
  4196.2     .07       0  4202.2     .07       0  5541.6     .12       0
  5772.7      .1       0  7004.5     .08       0  7216.9      .1       0
Bank Sta=4189,5664.6
XS Rating Curve= 0 ,0
Exp/Cntr=0.3,0.1

Type RM Length L Ch R = 1 ,6493    ,949,949,949
BEGIN DESCRIPTION:
UNT001 IN PECR 11.0
END DESCRIPTION:
XS GIS Cut Line= 6
      2306848.06     13248622.84      2307184.45     13248058.58
      2307021.69     13246702.25      2306197.04     13245649.73
      2305187.92     13245888.45      2303842.57      13245834.2
#Sta/Elev= 30
    2311  120.87    2361  118.51  2777.4  107.99  3099.1   98.04  3181.2   92.37
  3193.6   91.79  3198.3   91.21  3201.1   90.71  3204.3   91.21  3298.8   91.21
  3424.1   91.21  3476.2   91.21  3941.7   91.21  5936.8   91.93  5947.8    92.4
  5978.7   93.33  5984.1   96.97  6200.6  109.53  6535.9  124.06    6939  122.53
  7037.1  122.17  7050.8  122.05  7238.7  124.14  7403.6  130.71  7527.8  136.21
  7625.9  140.51  7779.1  140.16  7799.1   143.6  7831.7  143.29  8054.5  143.19
#Mann= 20 ,-1 , 0
    2311      .1       0    2361     .05       0  2777.4      .1       0
  3099.1     .05       0  3193.6      .1       0  3198.3     .07       0
  3204.3      .1       0  3298.8     .05       0  3424.1     .07       0
  3476.2     .05       0  3941.7     .07       0  5936.8     .05       0
  6535.9      .1       0    6939     .05       0  7037.1      .1       0
  7050.8     .05       0  7403.6      .1       0  7527.8     .05       0
  7625.9     .08       0  7831.7      .1       0
Bank Sta=3181.2,5947.8
XS Rating Curve= 0 ,0
Exp/Cntr=0.3,0.1

Type RM Length L Ch R = 1 ,5544    ,917,917,917
BEGIN DESCRIPTION:
UNT001 IN PECR 9.0
END DESCRIPTION:
XS GIS Cut Line= 5
       2306936.9     13249744.82      2307687.72      13248136.8
      2307364.89     13245606.38      2305452.66     13244517.01
      2303603.73      13244634.2
#Sta/Elev= 30
   674.4  143.39   981.2  127.34  1499.9  108.93  1946.7   98.33  2223.6   99.84
  2433.7   94.97  2491.5   92.03  2526.7   91.21  2529.4   90.71  2532.7   91.21
  2544.5   91.21  2644.5   91.21  2744.5   91.21  2758.6   91.21  2844.4   91.21
  4075.3   91.21  4623.9   91.21  6106.2   91.21  6528.1   91.21  6662.7   91.99
  6692.4   93.42  6932.2  108.18  7516.3  122.59    7827  124.24    8338  116.44
  8428.9     120  8445.5  120.63  8544.9  126.89  8643.4  130.85  9053.4  149.75
#Mann= 19 ,-1 , 0
   674.4      .1       0  1946.7     .05       0  2433.7     .07       0
  2526.7    .033       0  2532.7     .07       0  2544.5     .05       0
  2644.5     .07       0  2744.5     .05       0  2758.6     .07       0
  2844.4     .05       0  4075.3     .07       0  4623.9     .05       0
  6106.2     .07       0  6528.1     .12       0  6692.4     .05       0
  8428.9      .1       0  8445.5     .08       0  8544.9     .05       0
  8643.4      .1       0
Bank Sta=2491.5,6662.7
XS Rating Curve= 0 ,0
Exp/Cntr=0.3,0.1

Type RM Length L Ch R = 1 ,4627    ,0,0,0
BEGIN DESCRIPTION:
UNT001 IN PECR 1.0
END DESCRIPTION:
XS GIS Cut Line= 4
      2308494.25     13249627.98      2308782.52     13246003.12
      2307636.69     13244466.66      2302845.07     13243919.79
#Sta/Elev= 30
    20.6  101.22   199.4  101.54   332.1  101.32  1335.9  101.56  1583.5   96.89
  1682.3   92.34 1692.64   91.53    1694   91.21  1696.7   90.71    1700   91.21
  6997.6   91.21  7198.3   91.21  7213.1   91.44  7364.1   94.52  7414.4   97.83
  7468.9   98.31    7505  100.98  7647.6  104.89    7732  109.85  7995.1  120.36
    8280  128.36  8813.4  132.22  9115.4  128.62  9147.1  130.03  9204.5  129.17
  9569.5  138.06  9820.1   145.5 10018.9   149.8   10049  149.76 10396.3  154.18
#Mann= 14 ,-1 , 0
    20.6     .05       0   199.4      .1       0   332.1     .05       0
  1583.5     .07       0  1682.3     .05       0    1694    .033       0
    1700     .05       0  6997.6     .07       0  7198.3     .05       0
  9204.5      .1       0  9569.5     .05       0  9820.1      .1       0
 10018.9     .05       0   10049      .1       0
Bank Sta=1692.64,7213.1
XS Rating Curve= 0 ,0
Exp/Cntr=0.3,0.1

Chan Stop Cuts=-1
Use User Specified Reach Order=0
Composite Channel Slope=5