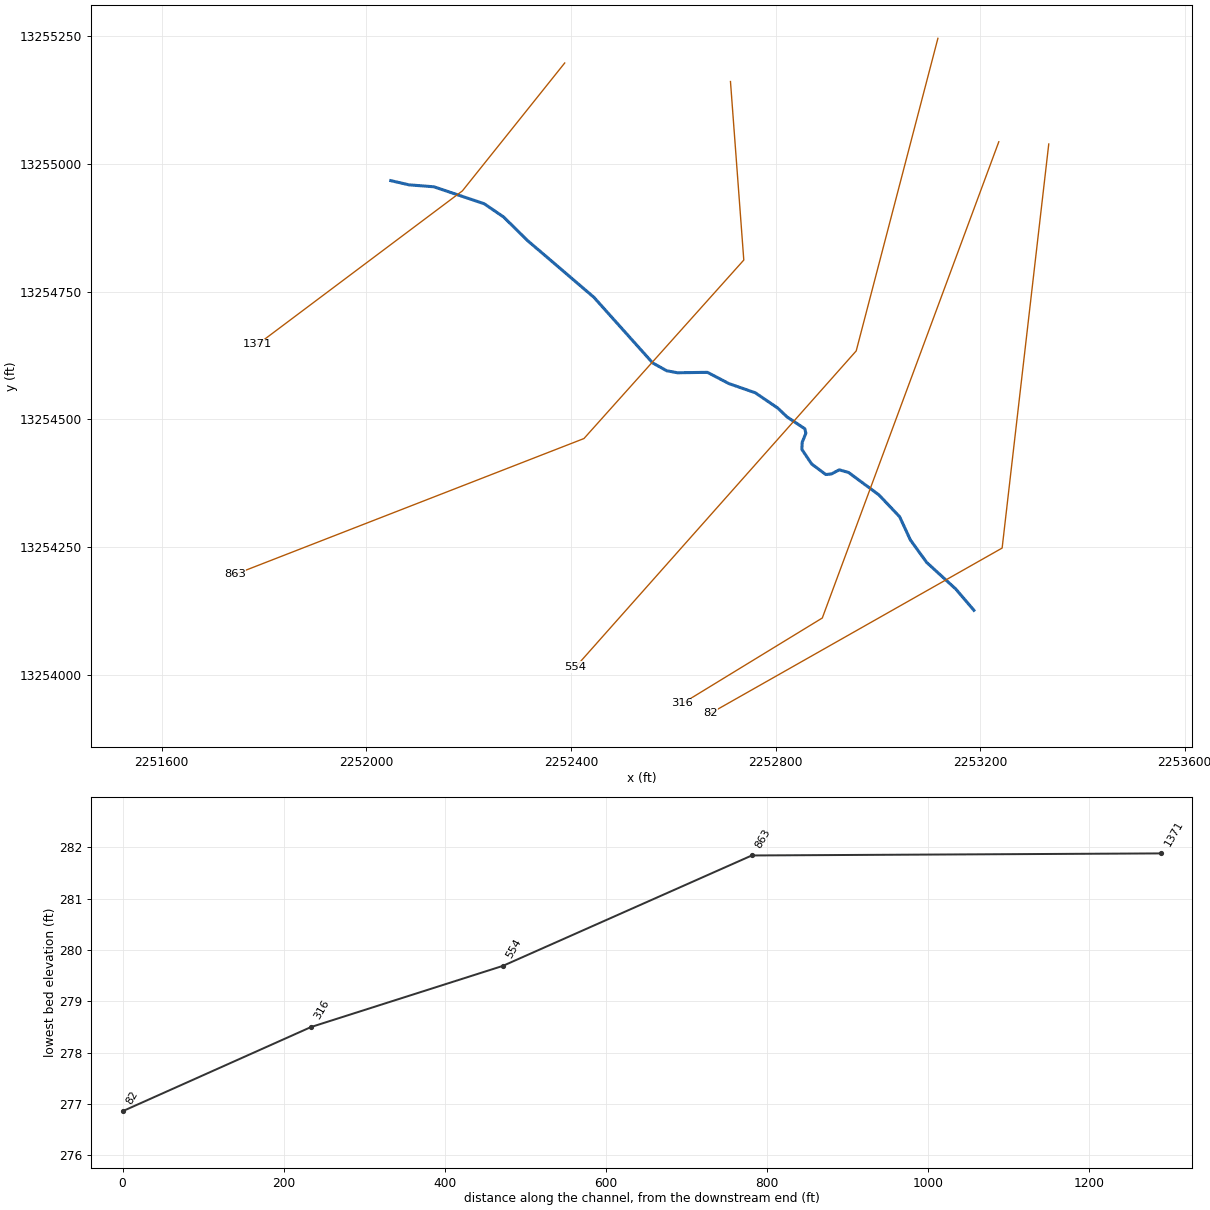
--- UNT002 IN PECR.prj (project) ---

Proj Title=UNT002 IN PECR Base Level Engineering
Current Plan=p01
Default Exp/Contr=0.3,0.1
English Units
Geom File=g01
Flow File=f01
Plan File=p01
Y Axis Title=Elevation
X Axis Title(PF)=Main Channel Distance
X Axis Title(XS)=Station
BEGIN DESCRIPTION:
UNT002 IN PECR
END DESCRIPTION:
DSS Export Rating Curves= 0
DSS Export Rating Curve Sorted= 0
DSS Export Volume Flow Curves= 0
DXF OffsetX= 0
DXF OffsetY= 0
DXF ScaleX= 1
DXF ScaleY= 10

--- UNT002 IN PECR.p01 (plan) ---

Plan Title=Multiple Run
Short Identifier=Multiple
Geom File=g01
Flow File=f01
Subcritical Flow
K Sum by GR= 0
Std Step Tol= 0.01
Critical Tol= 0.01
Num of Std Step Trials= 20
Max Error Tol= 0.3
Flow Tol Ratio= 0.001
Split Flow NTrial= 30
Split Flow Tol= 0.02
Split Flow Ratio= 0.02
Log Output Level= 0
Friction Slope Method= 1
Unsteady Friction Slope Method= 2
Unsteady Bridges Friction Slope Method= 1
Parabolic Critical Depth
Global Vel Dist=  1 , 1 , 1
Global Log Level= 0
CheckData=True
Encroach Param= -1, 0, 0, 0
BEGIN DESCRIPTION:
Multiple Run
END DESCRIPTION:

--- UNT002 IN PECR.f01 (steady flow) ---

Flow Title=Multiple
Program Version=4.10
Number of Profiles= 7
Profile Names=10-year,25-year,50-year,1pct_min,100-year,1pct_plu,500-year
River Rch & RM=UNT002 IN PECR,Reach-1         ,1371
     258     362     450     412     557     753     866
Boundary for River Rch & Prof#=UNT002 IN PECR,Reach-1         , 1
Up Type= 0
Dn Type= 3
Dn Slope=0.007
Boundary for River Rch & Prof#=UNT002 IN PECR,Reach-1         , 2
Up Type= 0
Dn Type= 3
Dn Slope=0.007
Boundary for River Rch & Prof#=UNT002 IN PECR,Reach-1         , 3
Up Type= 0
Dn Type= 3
Dn Slope=0.007
Boundary for River Rch & Prof#=UNT002 IN PECR,Reach-1         , 4
Up Type= 0
Dn Type= 3
Dn Slope=0.007
Boundary for River Rch & Prof#=UNT002 IN PECR,Reach-1         , 5
Up Type= 0
Dn Type= 3
Dn Slope=0.007
Boundary for River Rch & Prof#=UNT002 IN PECR,Reach-1         , 6
Up Type= 0
Dn Type= 3
Dn Slope=0.007
Boundary for River Rch & Prof#=UNT002 IN PECR,Reach-1         , 7
Up Type= 0
Dn Type= 3
Dn Slope=0.007
DSS Import GetInterval= 0
DSS Import GetPeak= 0
DSS Import FillOption= 0

--- UNT002 IN PECR.g01 (geometry) ---

Geom Title=Existing Conditions
Program Version=4.10

River Reach=UNT002 IN PECR  ,Reach-1
Reach XY= 30
      2252047.72     13254966.86      2252083.58     13254958.61
      2252131.84     13254954.88       2252230.3      13254921.7
       2252268.1     13254895.93      2252314.75       13254850.
      2252444.64       13254739.      2252559.66     13254610.53
      2252587.18     13254595.15      2252608.34     13254591.27
      2252666.72     13254592.12      2252708.95       13254570.
      2252760.22     13254552.18      2252804.02     13254522.39
      2252822.46     13254504.95       2252857.1     13254481.82
      2252859.22     13254473.04      2252852.05     13254455.39
      2252851.32     13254441.56      2252870.55     13254412.91
      2252898.19     13254392.34      2252909.15     13254393.49
      2252924.45     13254401.48      2252942.62      13254396.4
      2253001.86     13254352.61      2253042.55     13254309.76
      2253063.46     13254264.51      2253095.34      13254220.5
       2253152.4     13254168.38      2253187.72     13254126.86

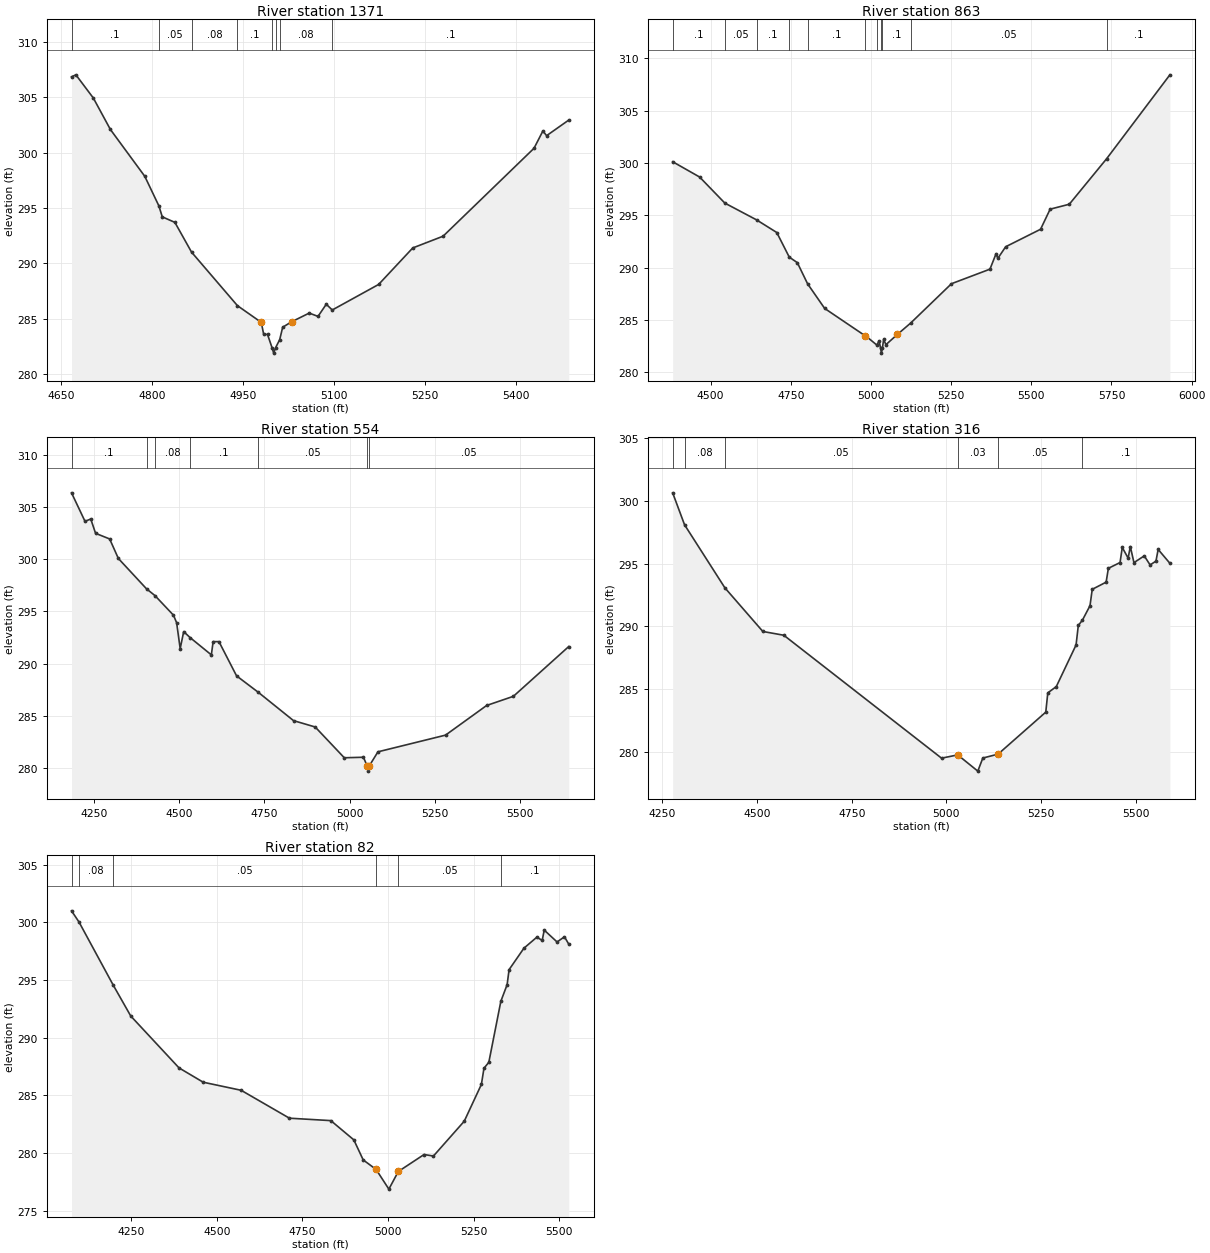
Type RM Length L Ch R = 1 ,1371    ,508,508,508
BEGIN DESCRIPTION:
UNT002 IN PECR 3.0
END DESCRIPTION:
XS GIS Cut Line= 3
      2252387.73     13255196.87      2252187.72     13254946.85
       2251787.7     13254646.84
#Sta/Elev= 30
  4667.4  306.86  4674.6  307.04  4703.4  304.94  4731.5   302.1  4788.3  297.86
  4811.5  295.19  4817.1   294.2  4837.9   293.7  4865.4  291.01  4941.1  286.17
  4980.4  284.66  4984.4  283.57  4990.7  283.57  4998.1  282.38  5000.9  281.88
  5004.1  282.38  5010.8   283.1  5015.7  284.22  5030.3  284.71  5059.5   285.5
    5074   285.2  5087.6   286.3  5097.5  285.78    5174  288.09  5230.3  291.39
  5280.3  292.45  5430.3   300.4  5444.9  301.96  5451.1  301.54  5487.6  302.95
#Mann= 8 ,-1 , 0
  4667.4      .1       0  4811.5     .05       0  4865.4     .08       0
  4941.1      .1       0  4998.1     .07       0  5004.1      .1       0
  5010.8     .08       0  5097.5      .1       0
Bank Sta=4980.4,5030.3
XS Rating Curve= 0 ,0
Exp/Cntr=0.3,0.1

Type RM Length L Ch R = 1 ,863     ,309,309,309
BEGIN DESCRIPTION:
UNT002 IN PECR 2.0
END DESCRIPTION:
XS GIS Cut Line= 4
       2252711.8     13255160.63      2252737.85     13254811.63
      2252425.35     13254462.67      2251743.04     13254197.04
#Sta/Elev= 30
  4381.5  300.12  4465.5  298.66  4544.2  296.17    4643  294.57  4706.2  293.36
  4745.1  291.01  4770.3  290.48  4802.3  288.46  4855.5  286.11  4981.6   283.5
  4982.6  283.51  5018.3  282.61  5025.2  283.02  5029.7  282.34  5032.5  281.84
  5035.7  282.34  5039.4  283.15  5046.6  282.65  5082.1  283.62    5124  284.72
    5251  288.47    5371  289.86  5390.1  291.34  5395.5  290.89    5420     292
  5528.8  293.67  5558.7  295.59  5618.4  296.06  5734.9  300.41  5932.1  308.42
#Mann= 11 ,-1 , 0
  4381.5      .1       0  4544.2     .05       0    4643      .1       0
  4745.1     .05       0  4802.3      .1       0  4981.6     .05       0
  5018.3      .1       0  5029.7     .04       0  5035.7      .1       0
    5124     .05       0  5734.9      .1       0
Bank Sta=4982.6,5082.1
XS Rating Curve= 0 ,0
Exp/Cntr=0.3,0.1

Type RM Length L Ch R = 1 ,554     ,238,238,238
BEGIN DESCRIPTION:
Mapping XS abb9ed
END DESCRIPTION:
XS GIS Cut Line= 3
      2253117.32     13255245.07      2252957.61     13254633.99
      2252409.01     13254015.95
#Sta/Elev= 30
  4184.3  306.36  4223.8  303.63  4240.7  303.85  4254.8  302.48  4296.1  301.94
  4321.6  300.07  4404.2  297.16    4429  296.51  4483.3  294.63  4492.5  293.91
  4502.9  291.43  4513.2  293.06  4531.9  292.49  4594.3  290.83  4599.5   292.1
  4616.6   292.1  4668.2  288.82  4732.1  287.24  4835.2  284.53  4898.8  283.92
  4984.1  280.97  5040.1  281.02  5051.3  280.19  5054.1  279.69  5057.3  280.19
  5082.8  281.54    5281  283.14  5401.4  285.98    5480  286.86  5642.3  291.63
#Mann= 7 ,-1 , 0
  4184.3      .1       0  4404.2     .05       0    4429     .08       0
  4531.9      .1       0  4732.1     .05       0  5051.3     .03       0
  5057.3     .05       0
Bank Sta=5051.3,5057.3
XS Rating Curve= 0 ,0
Exp/Cntr=0.3,0.1

Type RM Length L Ch R = 1 ,316     ,234,234,234
BEGIN DESCRIPTION:
Mapping XS abb9ed7e
END DESCRIPTION:
XS GIS Cut Line= 3
      2253236.37     13255042.81      2252891.33     13254111.85
      2252617.89     13253944.75
#Sta/Elev= 30
  4277.1  300.62  4308.5  298.08    4415  293.07  4515.3   289.6  4570.7   289.3
  4987.3  279.53    5030  279.79  5083.1   278.5  5096.3  279.54  5136.6  279.85
  5262.6  283.19  5267.9  284.72  5290.4  285.22  5342.6  288.53  5348.5  290.08
  5359.4   290.5  5379.4  291.65  5385.3  292.95    5422  293.52  5427.9  294.62
  5458.8  295.08  5464.6  296.28  5480.1  295.43  5485.9  296.35  5495.5  295.07
  5522.7  295.61  5538.1  294.89  5553.6  295.19  5559.4  296.12  5590.4  295.02
#Mann= 6 ,-1 , 0
  4277.1     .05       0  4308.5     .08       0    4415     .05       0
    5030     .03       0  5136.6     .05       0  5359.4      .1       0
Bank Sta=5030,5136.6
XS Rating Curve= 0 ,0
Exp/Cntr=0.3,0.1

Type RM Length L Ch R = 1 ,82      ,0,0,0
BEGIN DESCRIPTION:
UNT002 IN PECR 1.0
END DESCRIPTION:
XS GIS Cut Line= 3
      2253334.04     13255038.49       2253242.9     13254248.57
      2252672.44     13253925.38
#Sta/Elev= 30
  4076.4  300.99  4098.4  300.01  4198.2  294.54  4249.2  291.87  4390.1  287.37
  4460.6  286.13  4571.3  285.43  4712.2  283.01    4833   282.8  4900.1  281.13
  4927.5  279.39    4965  278.57  5002.3  276.86  5029.9  278.39    5105  279.86
  5132.4  279.73  5222.3  282.75  5272.3  285.94  5279.8  287.34    5294  287.86
  5329.1  293.15  5347.4  294.59  5353.1  295.89  5396.4  297.75  5433.9   298.7
  5449.8  298.43  5455.6  299.32  5493.1  298.29  5514.7  298.74  5527.2   298.1
#Mann= 6 ,-1 , 0
  4076.4     .05       0  4098.4     .08       0  4198.2     .05       0
    4965     .03       0  5029.9     .05       0  5329.1      .1       0
Bank Sta=4965,5029.9
XS Rating Curve= 0 ,0
Exp/Cntr=0.3,0.1

Chan Stop Cuts=-1
Use User Specified Reach Order=0
Composite Channel Slope=5