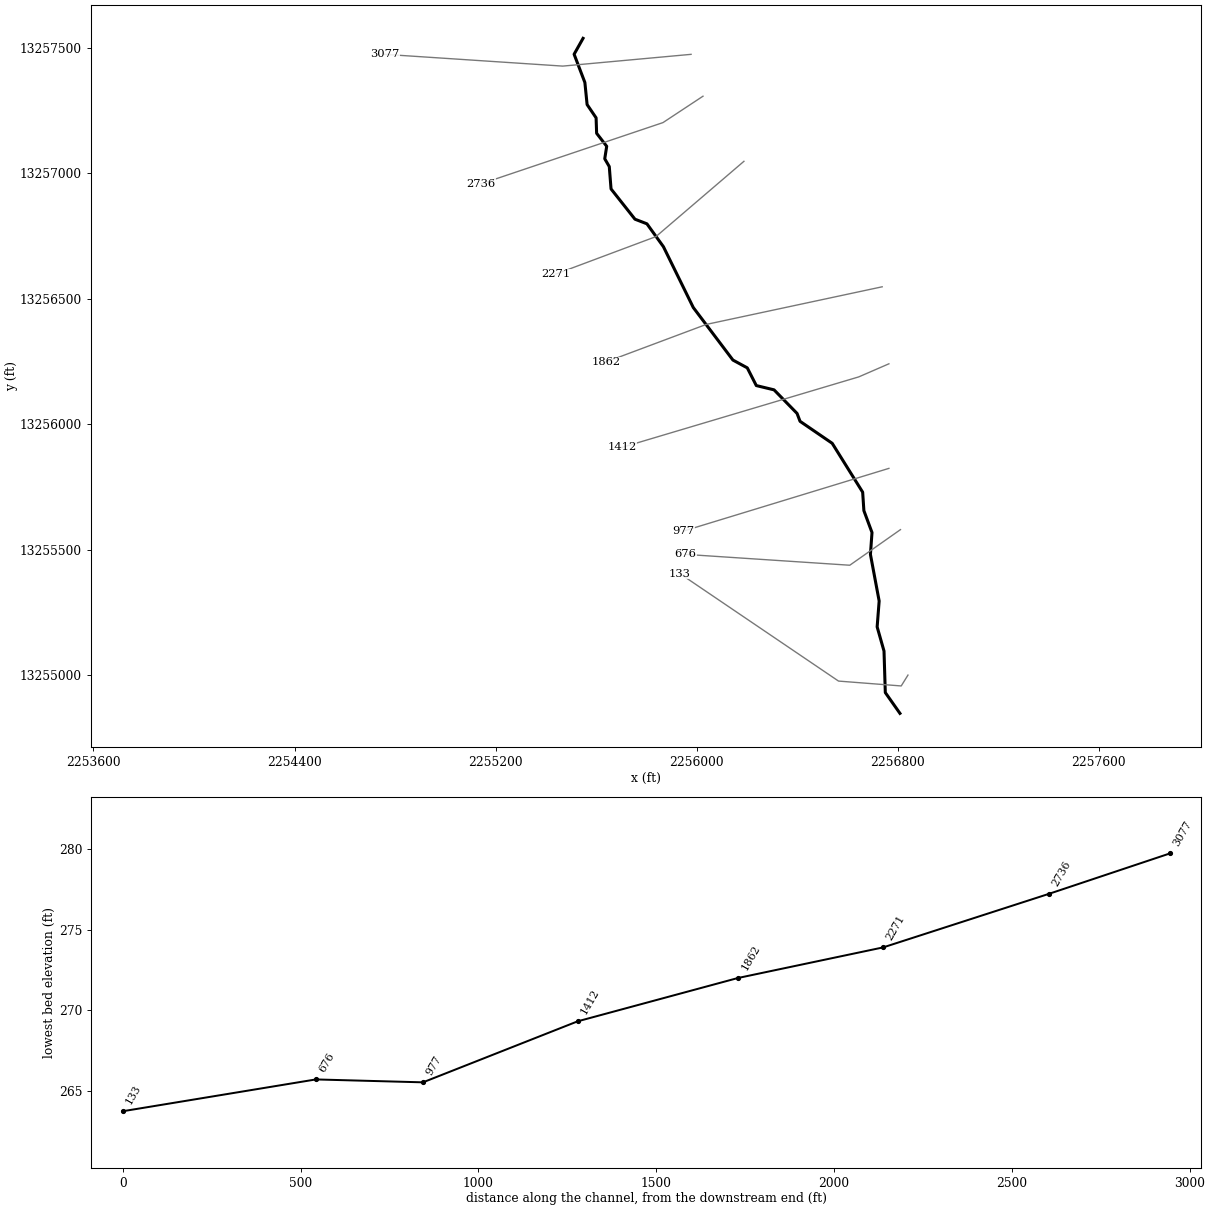
--- UNT003 IN PECR.prj (project) ---

Proj Title=UNT003 IN PECR Base Level Engineering
Current Plan=p01
Default Exp/Contr=0.3,0.1
English Units
Geom File=g01
Flow File=f01
Plan File=p01
Y Axis Title=Elevation
X Axis Title(PF)=Main Channel Distance
X Axis Title(XS)=Station
BEGIN DESCRIPTION:
UNT003 IN PECR
END DESCRIPTION:
DSS Export Rating Curves= 0
DSS Export Rating Curve Sorted= 0
DSS Export Volume Flow Curves= 0
DXF OffsetX= 0
DXF OffsetY= 0
DXF ScaleX= 1
DXF ScaleY= 10

--- UNT003 IN PECR.p01 (plan) ---

Plan Title=Multiple Run
Short Identifier=Multiple
Geom File=g01
Flow File=f01
Subcritical Flow
K Sum by GR= 0
Std Step Tol= 0.01
Critical Tol= 0.01
Num of Std Step Trials= 20
Max Error Tol= 0.3
Flow Tol Ratio= 0.001
Split Flow NTrial= 30
Split Flow Tol= 0.02
Split Flow Ratio= 0.02
Log Output Level= 0
Friction Slope Method= 1
Unsteady Friction Slope Method= 2
Unsteady Bridges Friction Slope Method= 1
Parabolic Critical Depth
Global Vel Dist=  1 , 1 , 1
Global Log Level= 0
CheckData=True
Encroach Param= -1, 0, 0, 0
BEGIN DESCRIPTION:
Multiple Run
END DESCRIPTION:

--- UNT003 IN PECR.f01 (steady flow) ---

Flow Title=Multiple
Program Version=4.10
Number of Profiles= 7
Profile Names=10-year,25-year,50-year,1pct_min,100-year,1pct_plu,500-year
River Rch & RM=UNT003 IN PECR,Reach-1         ,3077
     230     319     394     358     484     654     742
Boundary for River Rch & Prof#=UNT003 IN PECR,Reach-1         , 1
Up Type= 0
Dn Type= 3
Dn Slope=0.005
Boundary for River Rch & Prof#=UNT003 IN PECR,Reach-1         , 2
Up Type= 0
Dn Type= 3
Dn Slope=0.005
Boundary for River Rch & Prof#=UNT003 IN PECR,Reach-1         , 3
Up Type= 0
Dn Type= 3
Dn Slope=0.005
Boundary for River Rch & Prof#=UNT003 IN PECR,Reach-1         , 4
Up Type= 0
Dn Type= 3
Dn Slope=0.005
Boundary for River Rch & Prof#=UNT003 IN PECR,Reach-1         , 5
Up Type= 0
Dn Type= 3
Dn Slope=0.005
Boundary for River Rch & Prof#=UNT003 IN PECR,Reach-1         , 6
Up Type= 0
Dn Type= 3
Dn Slope=0.005
Boundary for River Rch & Prof#=UNT003 IN PECR,Reach-1         , 7
Up Type= 0
Dn Type= 3
Dn Slope=0.005
DSS Import GetInterval= 0
DSS Import GetPeak= 0
DSS Import FillOption= 0

--- UNT003 IN PECR.g01 (geometry) ---

Geom Title=Existing Conditions
Program Version=4.10

River Reach=UNT003 IN PECR  ,Reach-1
Reach XY= 30
      2255547.72     13257536.85      2255512.15     13257473.52
      2255554.98     13257360.89      2255563.83     13257272.96
      2255599.62     13257220.01      2255601.71      13257158.5
      2255641.79     13257106.67      2255634.02      13257056.9
      2255652.04     13257025.85      2255659.08     13256936.76
      2255754.27     13256816.17      2255801.84     13256797.78
      2255867.47     13256706.58       2255986.3     13256464.14
      2256143.94     13256254.89      2256201.05     13256223.86
      2256236.95     13256153.26      2256307.51     13256136.26
       2256399.1     13256042.28      2256411.02     13256010.81
      2256538.88     13255923.26      2256660.07     13255728.47
      2256664.93     13255654.86      2256697.22     13255567.71
      2256690.97     13255480.56      2256725.69     13255294.79
       2256717.7     13255191.67      2256744.99     13255095.44
      2256750.16     13254929.98      2256808.41     13254847.11

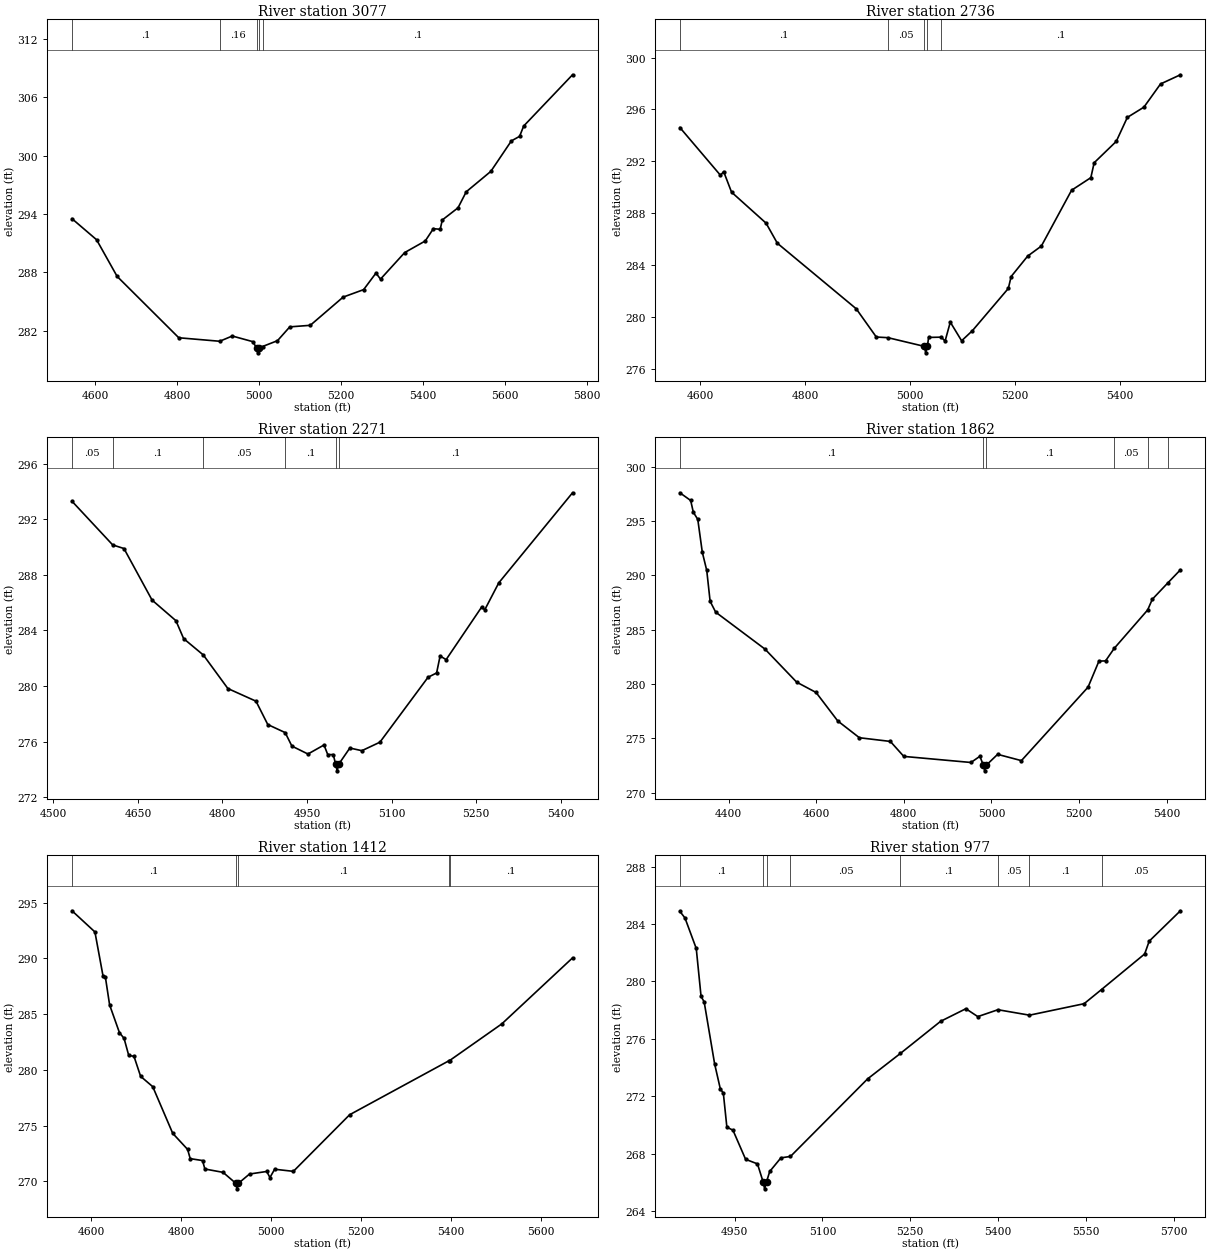
Type RM Length L Ch R = 1 ,3077    ,341,341,341
BEGIN DESCRIPTION:
UNT003 IN PECR 7.0
END DESCRIPTION:
XS GIS Cut Line= 3
      2255977.47     13257473.09      2255467.01     13257426.21
      2254758.67     13257473.09
#Sta/Elev= 30
  4543.2  293.51  4603.2  291.35  4653.4  287.58    4804  281.27    4904  280.91
  4934.6  281.45  4984.8  280.87    4994  280.22  4996.7  279.72    5000  280.22
  5008.5  280.37  5045.1  280.97  5075.1  282.39  5125.2  282.55  5205.4  285.45
  5255.5  286.22  5285.6  287.92  5296.7   287.3  5355.8  290.03  5405.9  291.22
  5425.9  292.49  5442.5  292.42  5447.6  293.38    5486  294.63  5506.1  296.28
  5566.2  298.38  5616.3  301.51  5636.4  301.98  5646.4  303.04  5765.7  308.31
#Mann= 5 ,-1 , 0
  4543.2      .1       0    4904     .16       0    4994     .07       0
    5000     .16       0  5008.5      .1       0
Bank Sta=4994,5000
XS Rating Curve= 0 ,0
Exp/Cntr=0.3,0.1

Type RM Length L Ch R = 1 ,2736    ,465,465,465
BEGIN DESCRIPTION:
UNT003 IN PECR 6.0
END DESCRIPTION:
XS GIS Cut Line= 3
      2256024.85     13257306.27      2255865.65     13257201.09
      2255141.82     13256956.97
#Sta/Elev= 30
  4560.7   294.6  4638.2  290.91  4644.2   291.2  4659.3  289.61  4725.1  287.22
  4746.6  285.67  4897.1  280.61  4935.4  278.43  4957.6  278.38  5026.9  277.71
  5029.6  277.21  5032.9  277.71  5035.1   278.4  5059.2  278.42  5066.6  278.12
  5076.5  279.58  5098.1  278.14  5118.7  278.92  5187.2  282.18  5192.6   283.1
  5224.2  284.68  5250.2  285.45  5307.9  289.76  5344.6  290.73  5350.9  291.88
  5393.1  293.53  5414.2  295.38  5445.8  296.17  5477.5  297.96  5515.4  298.67
#Mann= 5 ,-1 , 0
  4560.7      .1       0  4957.6     .05       0  5026.9    .035       0
  5032.9     .05       0  5059.2      .1       0
Bank Sta=5026.9,5032.9
XS Rating Curve= 0 ,0
Exp/Cntr=0.3,0.1

Type RM Length L Ch R = 1 ,2271    ,409,409,409
BEGIN DESCRIPTION:
UNT003 IN PECR 5.0
END DESCRIPTION:
XS GIS Cut Line= 3
       2256187.7     13257046.84      2255837.72     13256746.85
      2255437.67     13256596.84
#Sta/Elev= 30
    4533  293.29  4605.2  290.15  4625.2  289.89  4675.1  286.18  4717.4   284.7
  4731.1  283.41  4766.1  282.23  4809.6  279.82  4859.5  278.91  4880.4  277.23
  4911.3  276.65  4923.2  275.68  4951.7  275.11  4980.2  275.76  4986.8  275.07
  4996.6  275.07  5000.7   274.4  5003.5   273.9  5006.7   274.4    5026  275.54
  5047.4  275.35  5079.4  275.96  5164.8  280.63    5180  280.94  5186.2  282.16
  5196.9   281.9  5260.1  285.69  5265.4  285.48  5290.3  287.42  5421.2   293.9
#Mann= 6 ,-1 , 0
    4533     .05       0  4605.2      .1       0  4766.1     .05       0
  4911.3      .1       0  5000.7     .07       0  5006.7      .1       0
Bank Sta=5000.7,5006.7
XS Rating Curve= 0 ,0
Exp/Cntr=0.3,0.1

Type RM Length L Ch R = 1 ,1862    ,450,450,450
BEGIN DESCRIPTION:
UNT003 IN PECR 4.0
END DESCRIPTION:
XS GIS Cut Line= 3
      2256737.74     13256546.86      2256037.72     13256396.85
      2255637.73     13256246.86
#Sta/Elev= 30
  4288.5  297.62  4313.2  296.91  4319.2  295.83  4329.4  295.17  4339.7  292.15
  4349.9  290.46  4357.6  287.62  4370.3  286.62  4482.8  283.22  4555.3  280.17
  4599.6  279.22    4649   276.6  4698.5  275.05  4769.2  274.71  4799.9  273.33
  4953.3  272.77  4973.7  273.34  4981.8   272.5  4984.6     272  4987.8   272.5
  5014.2  273.52  5068.5  272.94  5220.7  279.71  5245.6  282.11  5260.7  282.13
  5280.4  283.28  5356.8  286.82  5367.5  287.81  5403.5  289.34  5431.6  290.52
#Mann= 6 ,-1 , 0
  4288.5      .1       0  4981.8     .07       0  4987.8      .1       0
  5280.4     .05       0  5356.8      .1       0  5403.5     .05       0
Bank Sta=4981.8,4987.8
XS Rating Curve= 0 ,0
Exp/Cntr=0.3,0.1

Type RM Length L Ch R = 1 ,1412    ,435,435,435
BEGIN DESCRIPTION:
UNT003 IN PECR 3.0
END DESCRIPTION:
XS GIS Cut Line= 3
       2256764.5       13256240.      2256644.72     13256187.92
      2255702.37     13255906.78
#Sta/Elev= 30
  4556.8  294.28  4607.8  292.38  4625.8  288.44  4631.2   288.3  4640.5  285.83
  4662.3  283.35  4672.7  282.82  4683.1  281.29  4694.7  281.22  4709.5  279.42
  4736.5  278.49    4781   274.3  4814.1  272.86  4819.9  272.03  4847.3  271.86
  4852.5   271.1    4893   270.8  4921.3  269.82    4924  269.32  4927.3  269.82
  4951.9  270.65  4990.3  270.88  4997.3  270.33  5007.8  271.08  5049.5  270.89
  5174.7  275.97    5395   280.8  5397.4  280.84  5513.5  284.13  5670.8  290.05
#Mann= 5 ,-1 , 0
  4556.8      .1       0  4921.3     .07       0  4927.3      .1       0
    5395     .05       0  5397.4      .1       0
Bank Sta=4921.3,4927.3
XS Rating Curve= 0 ,0
Exp/Cntr=0.3,0.1

Type RM Length L Ch R = 1 ,977     ,301,301,301
BEGIN DESCRIPTION:
UNT003 IN PECR 2.0
END DESCRIPTION:
XS GIS Cut Line= 2
       2256764.5     13255823.33      2255946.76     13255573.32
#Sta/Elev= 30
  4856.4  284.89  4865.1  284.43  4884.4   282.3  4892.6  278.96  4897.9  278.58
  4915.8  274.25  4925.4  272.53  4930.7   272.2  4936.7  269.84  4947.1  269.63
  4968.7   267.6    4989  267.28  4998.5  266.04  5001.2  265.54  5004.5  266.04
  5009.9  266.75    5029   267.7  5045.4   267.8  5177.2  273.21  5233.1  274.98
  5301.8  277.22    5345   278.1  5365.4  277.55  5399.8  278.03  5453.7  277.65
    5547  278.45  5576.8  279.44  5650.5  281.92  5658.2  282.81  5711.5  284.93
#Mann= 8 ,-1 , 0
  4856.4      .1       0  4998.5     .07       0  5004.5      .1       0
  5045.4     .05       0  5233.1      .1       0  5399.8     .05       0
  5453.7      .1       0  5576.8     .05       0
Bank Sta=4998.5,5004.5
XS Rating Curve= 0 ,0
Exp/Cntr=0.3,0.1

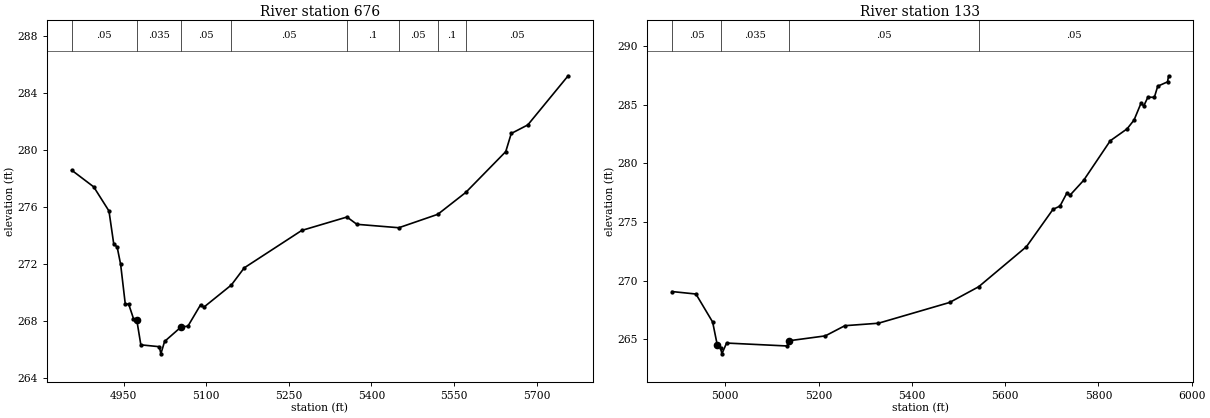
Type RM Length L Ch R = 1 ,676     ,543,543,543
BEGIN DESCRIPTION:
Mapping XS 3f656b7b
END DESCRIPTION:
XS GIS Cut Line= 3
      2256810.49     13255579.29      2256608.82     13255437.38
      2255954.55      13255480.7
#Sta/Elev= 30
  4855.2  278.58  4895.3  277.41    4923  275.72  4931.7   273.4  4937.8  273.21
  4944.2  271.98  4952.6  269.21  4958.8   269.2  4967.5  268.19  4973.6  268.07
  4980.9  266.35  5014.5  266.22  5017.3  265.72  5024.1  266.59  5053.7  267.59
  5066.5  267.66  5089.4  269.15  5095.5  268.99  5145.4  270.54  5168.8  271.74
  5273.3  274.36  5355.5   275.3  5373.5  274.79  5449.8  274.55  5520.6  275.49
  5571.4  277.02  5644.1  279.88  5654.1  281.15  5684.2  281.75  5757.5  285.19
#Mann= 8 ,-1 , 0
  4855.2     .05       0  4973.6    .035       0  5053.7     .05       0
  5145.4     .05       0  5355.5      .1       0  5449.8     .05       0
  5520.6      .1       0  5571.4     .05       0
Bank Sta=4973.6,5053.7
XS Rating Curve= 0 ,0
Exp/Cntr=0.3,0.1

Type RM Length L Ch R = 1 ,133     ,0,0,0
BEGIN DESCRIPTION:
UNT003 IN PECR 1.0
END DESCRIPTION:
XS GIS Cut Line= 4
      2256840.34     13254999.68      2256813.47     13254956.38
      2256564.01      13254975.8      2255932.43     13255404.32
#Sta/Elev= 30
  4886.2  269.06  4937.2  268.85    4973  266.46    4983  264.49  4990.1  264.25
  4992.8  263.75  5002.9  264.67  5132.5  264.42  5137.5  264.87  5214.5  265.28
  5256.5  266.15  5328.4  266.36    5481  268.13  5543.3  269.47  5645.8  272.89
  5702.7  276.07  5717.7  276.35  5732.6  277.47  5738.8  277.26  5768.5  278.55
  5825.5  281.92  5861.4  282.93  5876.4  283.68  5891.3  285.11  5897.3  284.89
  5906.2  285.64    5920  285.62  5927.2  286.57  5948.2  286.94  5950.6  287.46
#Mann= 4 ,-1 , 0
  4886.2     .05       0  4990.1    .035       0  5137.5     .05       0
  5543.3     .05       0
Bank Sta=4983,5137.5
XS Rating Curve= 0 ,0
Exp/Cntr=0.3,0.1

Chan Stop Cuts=-1
Use User Specified Reach Order=0
Composite Channel Slope=5