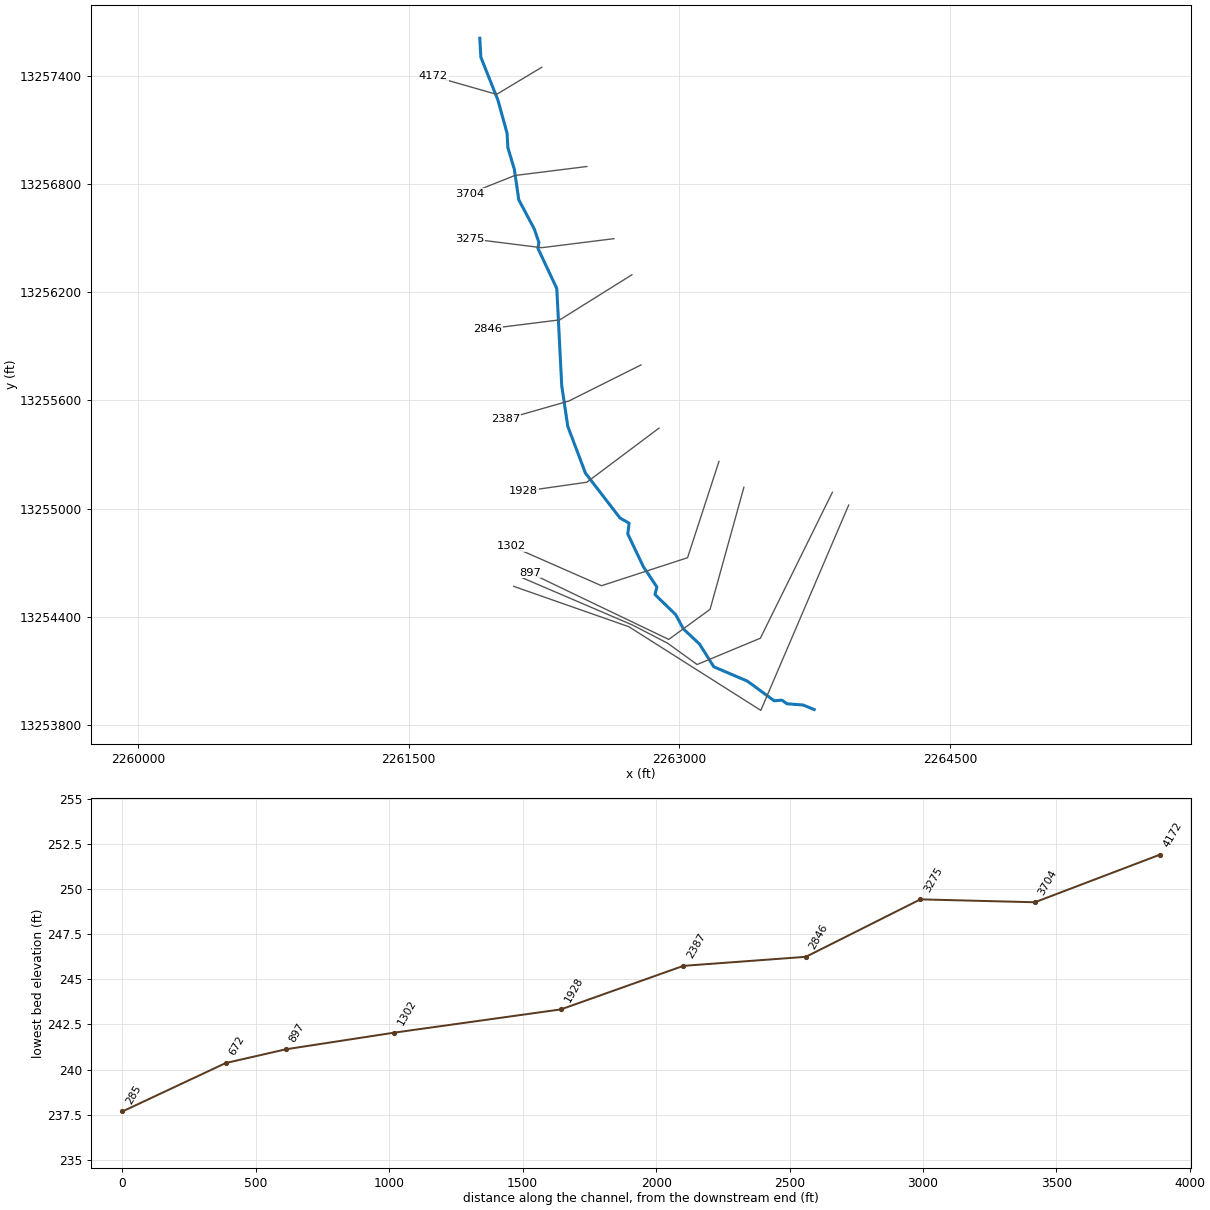
--- UNT004 IN PECR.prj (project) ---

Proj Title=UNT004 IN PECR Base Level Engineering
Current Plan=p01
Default Exp/Contr=0.3,0.1
English Units
Geom File=g01
Flow File=f01
Plan File=p01
Y Axis Title=Elevation
X Axis Title(PF)=Main Channel Distance
X Axis Title(XS)=Station
BEGIN DESCRIPTION:
UNT004 IN PECR
END DESCRIPTION:
DSS Export Rating Curves= 0
DSS Export Rating Curve Sorted= 0
DSS Export Volume Flow Curves= 0
DXF OffsetX= 0
DXF OffsetY= 0
DXF ScaleX= 1
DXF ScaleY= 10

--- UNT004 IN PECR.p01 (plan) ---

Plan Title=Multiple Run
Short Identifier=Multiple
Geom File=g01
Flow File=f01
Subcritical Flow
K Sum by GR= 0
Std Step Tol= 0.01
Critical Tol= 0.01
Num of Std Step Trials= 20
Max Error Tol= 0.3
Flow Tol Ratio= 0.001
Split Flow NTrial= 30
Split Flow Tol= 0.02
Split Flow Ratio= 0.02
Log Output Level= 0
Friction Slope Method= 1
Unsteady Friction Slope Method= 2
Unsteady Bridges Friction Slope Method= 1
Parabolic Critical Depth
Global Vel Dist=  1 , 1 , 1
Global Log Level= 0
CheckData=True
Encroach Param= -1, 0, 0, 0
BEGIN DESCRIPTION:
Multiple Run
END DESCRIPTION:

--- UNT004 IN PECR.f01 (steady flow) ---

Flow Title=Multiple
Program Version=4.10
Number of Profiles= 7
Profile Names=10-year,25-year,50-year,1pct_min,100-year,1pct_plu,500-year
River Rch & RM=UNT004 IN PECR,Reach-1         ,4172
     302     426     530     486     657     889    1025
Boundary for River Rch & Prof#=UNT004 IN PECR,Reach-1         , 1
Up Type= 0
Dn Type= 3
Dn Slope=0.0068
Boundary for River Rch & Prof#=UNT004 IN PECR,Reach-1         , 2
Up Type= 0
Dn Type= 3
Dn Slope=0.0068
Boundary for River Rch & Prof#=UNT004 IN PECR,Reach-1         , 3
Up Type= 0
Dn Type= 3
Dn Slope=0.0068
Boundary for River Rch & Prof#=UNT004 IN PECR,Reach-1         , 4
Up Type= 0
Dn Type= 3
Dn Slope=0.0068
Boundary for River Rch & Prof#=UNT004 IN PECR,Reach-1         , 5
Up Type= 0
Dn Type= 3
Dn Slope=0.0068
Boundary for River Rch & Prof#=UNT004 IN PECR,Reach-1         , 6
Up Type= 0
Dn Type= 3
Dn Slope=0.0068
Boundary for River Rch & Prof#=UNT004 IN PECR,Reach-1         , 7
Up Type= 0
Dn Type= 3
Dn Slope=0.0068
DSS Import GetInterval= 0
DSS Import GetPeak= 0
DSS Import FillOption= 0

--- UNT004 IN PECR.g01 (geometry) ---

Geom Title=Existing Conditions
Program Version=4.10

River Reach=UNT004 IN PECR  ,Reach-1
Reach XY= 30
      2261894.37     13257608.11      2261900.13     13257502.89
      2261994.59     13257265.56       2262045.6     13257081.24
      2262049.72     13257002.42      2262085.82     13256881.07
      2262110.44     13256712.43      2262196.09     13256551.13
      2262222.12     13256475.81      2262216.44     13256443.55
      2262321.09     13256220.55      2262348.46     13255682.16
      2262381.75     13255457.34      2262479.66     13255197.66
      2262670.87     13254949.22      2262721.85     13254919.48
      2262714.56     13254859.94      2262801.13     13254678.26
      2262875.78     13254565.92       2262865.3     13254524.45
      2262979.94     13254413.11      2263022.59     13254334.07
      2263112.52     13254249.29      2263191.35      13254123.7
       2263376.7     13254044.84      2263526.29     13253935.23
      2263568.56     13253938.78      2263597.41     13253918.72
      2263686.71     13253911.88      2263747.72     13253886.85

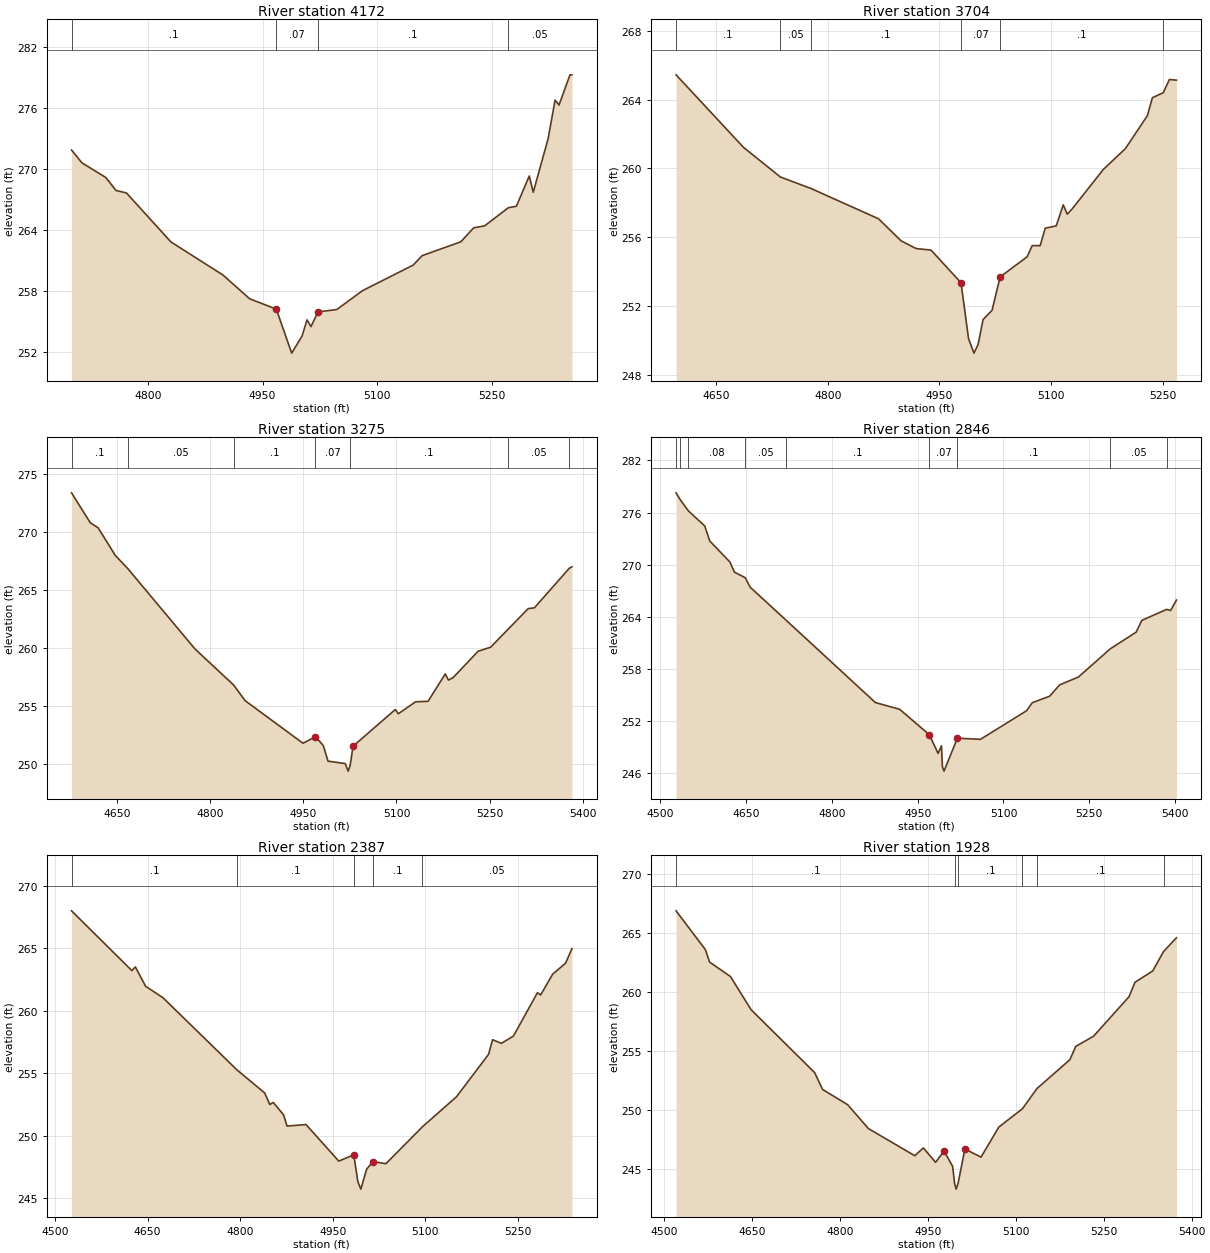
Type RM Length L Ch R = 1 ,4172    ,468,468,468
BEGIN DESCRIPTION:
UNT004 IN PECR 7.0
END DESCRIPTION:
XS GIS Cut Line= 3
      2262237.73     13257446.86      2261987.72     13257296.85
      2261637.69     13257396.86
#Sta/Elev= 30
  4699.7  271.87  4713.3  270.61  4744.4  269.18    4758  267.89  4771.6  267.65
  4829.9  262.83    4898  259.58    4933  257.24  4967.9  256.22  4988.1  251.89
  5001.7  253.57  5008.2  255.16  5013.4   254.5  5022.5  255.94  5047.2  256.18
    5081  258.04  5147.3  260.55    5159  261.48  5209.7  262.84  5226.6  264.22
  5240.9  264.41  5272.1   266.2  5282.5  266.34  5299.4  269.32  5304.6  267.72
  5324.1  272.99  5333.2  276.78  5338.4   276.3  5352.7  279.27  5355.3  279.27
#Mann= 4 ,-1 , 0
  4699.7      .1       0  4967.9     .07       0  5022.5      .1       0
  5272.1     .05       0
Bank Sta=4967.9,5022.5
XS Rating Curve= 0 ,0
Exp/Cntr=0.3,0.1

Type RM Length L Ch R = 1 ,3704    ,429,429,429
BEGIN DESCRIPTION:
UNT004 IN PECR 6.0
END DESCRIPTION:
XS GIS Cut Line= 3
      2262487.69     13256896.85      2262087.72     13256846.85
      2261837.76     13256746.87
#Sta/Elev= 30
  4596.1  265.44  4686.8  261.22  4736.3   259.5  4777.5  258.83  4868.2  257.07
  4898.4  255.79  4918.6  255.34  4938.7  255.25    4979  253.35  4989.1   250.1
  4996.4  249.26  5001.9  249.76  5008.6  251.21  5020.7  251.75  5031.5  253.69
  5067.8  254.86  5074.6  255.51  5085.3  255.51  5092.1  256.52  5106.9  256.66
  5116.3  257.88  5121.7  257.34  5128.4  257.65  5170.2  259.94  5199.8  261.15
  5229.4  263.07  5236.1  264.11  5250.7   264.4    5259  265.17  5268.4  265.13
#Mann= 6 ,-1 , 0
  4596.1      .1       0  4736.3     .05       0  4777.5      .1       0
    4979     .07       0  5031.5      .1       0  5250.7     .05       0
Bank Sta=4979,5031.5
XS Rating Curve= 0 ,0
Exp/Cntr=0.3,0.1

Type RM Length L Ch R = 1 ,3275    ,429,429,429
BEGIN DESCRIPTION:
UNT004 IN PECR 5.0
END DESCRIPTION:
XS GIS Cut Line= 3
       2262637.7     13256496.85      2262237.72     13256446.85
      2261837.72     13256496.85
#Sta/Elev= 30
  4576.5  273.38  4606.7   270.8  4619.3  270.37    4647  267.99  4667.2  266.85
  4775.5  259.93  4837.5  256.84  4856.1  255.49  4949.4  251.82  4969.5  252.38
  4982.1  251.62  4989.7  250.28  5017.4  250.07  5022.2  249.42  5025.4  249.92
    5030  251.56    5098  254.72    5103  254.36  5130.8  255.39  5150.9  255.43
  5178.6  257.79  5183.7  257.26  5191.2  257.47  5231.5  259.74  5251.7  260.09
  5279.2   261.6  5312.2  263.41  5322.2  263.48  5378.5  266.89  5382.7  267.01
#Mann= 7 ,-1 , 0
  4576.5      .1       0  4667.2     .05       0  4837.5      .1       0
  4969.5     .07       0  5025.4      .1       0  5279.2     .05       0
  5378.5      .1       0
Bank Sta=4969.5,5030
XS Rating Curve= 0 ,0
Exp/Cntr=0.3,0.1

Type RM Length L Ch R = 1 ,2846    ,459,459,459
BEGIN DESCRIPTION:
UNT004 IN PECR 4.0
END DESCRIPTION:
XS GIS Cut Line= 3
      2262737.71     13256296.85      2262337.72     13256046.85
      2261937.72     13255996.86
#Sta/Elev= 30
  4527.6  278.27    4535  277.47  4549.1   276.2  4577.7  274.46  4586.6  272.72
  4621.9   270.3  4629.6  269.14  4648.6   268.5  4657.3   267.4    4720  263.61
  4876.1  254.13  4918.5  253.36  4970.4  250.43  4985.7  248.28  4991.6  249.16
  4993.3  246.74  4996.1  246.24  5019.4  250.03  5059.8   249.9  5140.4  253.19
  5150.5  254.12  5180.7  254.86  5198.3  256.17  5231.1  257.07  5286.6  260.31
  5331.9  262.23  5341.9  263.59  5385.2  264.85  5392.3  264.73  5402.4  265.93
#Mann= 9 ,-1 , 0
  4527.6     .08       0    4535      .1       0  4549.1     .08       0
  4648.6     .05       0    4720      .1       0  4970.4     .07       0
  5019.4      .1       0  5286.6     .05       0  5385.2      .1       0
Bank Sta=4970.4,5019.4
XS Rating Curve= 0 ,0
Exp/Cntr=0.3,0.1

Type RM Length L Ch R = 1 ,2387    ,459,459,459
BEGIN DESCRIPTION:
UNT004 IN PECR 3.0
END DESCRIPTION:
XS GIS Cut Line= 3
      2262787.69     13255796.84      2262387.72     13255596.85
       2262037.7     13255496.85
#Sta/Elev= 30
  4526.7  267.98  4624.5   263.2  4630.1   263.5  4646.8  261.95  4674.8  261.04
  4794.8  255.27  4839.7  253.43  4848.1   252.5  4853.7  252.67  4870.5  251.67
    4876  250.78  4906.8   250.9  4959.9  247.98  4984.3  248.48  4990.8  246.34
  4995.7  245.74  5005.1  247.34  5015.5  247.94  5036.3  247.77  5095.5  250.72
  5150.7  253.12  5202.7  256.51  5209.2  257.68  5223.5  257.39    5243  257.97
    5282  261.44  5287.2  261.26  5306.7  262.92  5327.5  263.79  5337.9  264.96
#Mann= 5 ,-1 , 0
  4526.7      .1       0  4794.8      .1       0  4984.3     .07       0
  5015.5      .1       0  5095.5     .05       0
Bank Sta=4984.3,5015.5
XS Rating Curve= 0 ,0
Exp/Cntr=0.3,0.1

Type RM Length L Ch R = 1 ,1928    ,626,626,626
BEGIN DESCRIPTION:
UNT004 IN PECR 2.0
END DESCRIPTION:
XS GIS Cut Line= 3
      2262887.69     13255446.83      2262487.72     13255146.85
      2262137.73     13255096.86
#Sta/Elev= 30
  4520.6   266.9  4570.6  263.62  4577.8  262.56  4613.3  261.34  4648.7  258.52
    4757   253.2  4770.6  251.77  4813.3  250.48  4848.7  248.46  4927.8  246.16
  4942.4  246.82  4963.3   245.6  4977.8  246.56  4992.4  245.25  4995.7  243.83
  4998.4  243.33  5001.7  243.83  5013.3  246.73  5040.8  246.04  5071.1  248.58
  5111.5  250.14  5136.2  251.85  5192.3  254.29  5202.4  255.42  5232.7  256.28
  5293.3  259.63  5303.4  260.85  5333.7  261.81  5352.1  263.45  5374.1  264.62
#Mann= 6 ,-1 , 0
  4520.6      .1       0  4995.7     .07       0  5001.7      .1       0
  5111.5     .05       0  5136.2      .1       0  5352.1     .05       0
Bank Sta=4977.8,5013.3
XS Rating Curve= 0 ,0
Exp/Cntr=0.3,0.1

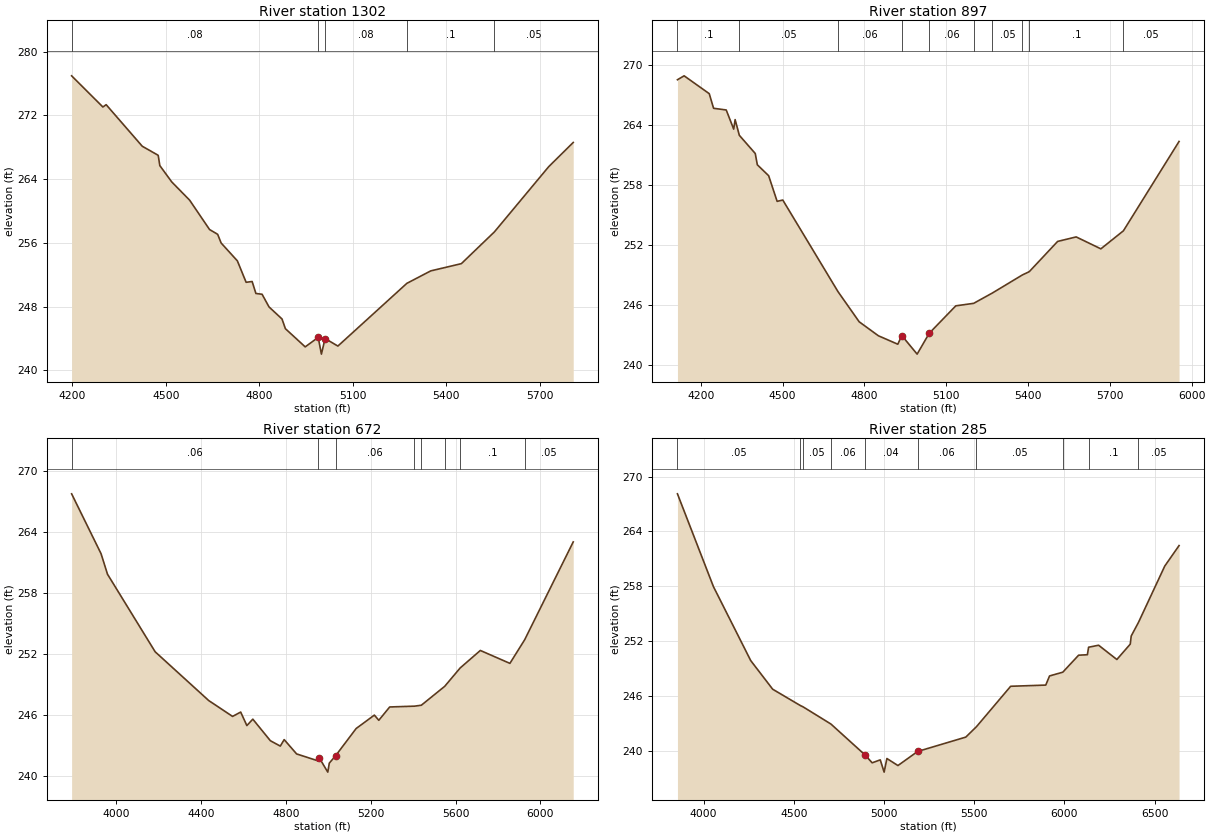
Type RM Length L Ch R = 1 ,1302    ,405,405,405
BEGIN DESCRIPTION:
Mapping XS ab89fd58
END DESCRIPTION:
XS GIS Cut Line= 4
      2263220.02      13255262.2      2263045.87     13254728.39
      2262568.89     13254573.18       2262069.2     13254792.74
#Sta/Elev= 30
  4197.9  276.95  4298.2  273.04  4308.7  273.33  4424.4  268.12  4475.6  266.98
  4480.8  265.69  4519.1  263.64  4576.5  261.35  4640.3  257.67  4666.3  257.07
  4677.5  255.98  4729.5  253.74  4757.6  251.05  4776.9  251.15    4789  249.65
  4808.8  249.55  4831.1  247.96  4872.7  246.45  4883.6  245.23  4947.1  242.95
  4988.8  244.14  4999.1  242.04  5010.9     244  5051.9  243.05  5273.2  250.92
  5349.7  252.48    5448  253.39  5553.9  257.37  5728.3  265.56  5806.8  268.59
#Mann= 5 ,-1 , 0
  4197.9     .08       0  4988.8     .05       0  5010.9     .08       0
  5273.2      .1       0  5553.9     .05       0
Bank Sta=4988.8,5010.9
XS Rating Curve= 0 ,0
Exp/Cntr=0.3,0.1

Type RM Length L Ch R = 1 ,897     ,225,225,225
BEGIN DESCRIPTION:
Mapping XS ab89fd
END DESCRIPTION:
XS GIS Cut Line= 4
       2263358.2     13255119.22      2263170.69      13254442.1
      2262941.52     13254275.43      2262171.69     13254644.74
#Sta/Elev= 30
  4114.1  268.51  4138.6   268.9  4230.7  267.12  4246.6  265.66    4293  265.49
  4320.4  263.58  4325.6  264.53  4341.1  262.96  4399.4  261.15  4407.1  260.02
  4448.6  258.93  4479.7  256.37  4500.5   256.5  4702.9  247.36  4780.6  244.35
  4851.2  242.95  4922.3  242.11    4937  242.97  4993.2  241.12  5037.5   243.2
    5135  245.94  5200.6  246.19  5269.1  247.22  5379.6  249.03  5404.5  249.35
  5508.5  252.37  5576.5  252.82  5667.1  251.63  5749.8  253.43  5953.9  262.35
#Mann= 10 ,-1 , 0
  4114.1      .1       0  4341.1     .05       0  4702.9     .06       0
    4937     .04       0  5037.5     .06       0  5200.6      .1       0
  5269.1     .05       0  5379.6     .08       0  5404.5      .1       0
  5749.8     .05       0
Bank Sta=4937,5037.5
XS Rating Curve= 0 ,0
Exp/Cntr=0.3,0.1

Type RM Length L Ch R = 1 ,672     ,387,387,387
BEGIN DESCRIPTION:
Mapping XS 4c55c3b0
END DESCRIPTION:
XS GIS Cut Line= 6
      2263848.72     13255091.22      2263449.43     13254282.22
      2263098.74     13254136.39      2262935.55     13254254.45
       2262741.1     13254355.14      2262133.42     13254615.57
#Sta/Elev= 30
    3791  267.74  3929.7  261.85  3960.1  259.83  4184.6   252.2  4437.1   247.4
  4549.4  245.84  4587.6  246.27  4616.7  244.94  4644.8  245.57  4727.5  243.45
  4774.3  242.92  4792.5  243.56  4851.2  242.15    4952  241.47  4957.5  241.78
    4998  240.36  5005.2  241.25  5034.4  241.96  5131.6  244.65  5217.5  245.97
  5238.4  245.46  5289.7  246.77  5406.5  246.85  5438.7  246.94  5548.9   248.8
  5621.9  250.61  5716.8  252.33  5856.1  251.06  5925.6  253.38  6154.5  263.01
#Mann= 8 ,-1 , 0
    3791     .06       0    4952     .04       0  5034.4     .06       0
  5406.5      .1       0  5438.7     .05       0  5548.9     .08       0
  5621.9      .1       0  5925.6     .05       0
Bank Sta=4957.5,5034.4
XS Rating Curve= 0 ,0
Exp/Cntr=0.3,0.1

Type RM Length L Ch R = 1 ,285     ,0,0,0
BEGIN DESCRIPTION:
UNT004 IN PECR 1.0
END DESCRIPTION:
XS GIS Cut Line= 4
      2263938.91     13255020.21      2263451.94      13253882.2
      2262720.31     13254346.04      2262082.45     13254569.59
#Sta/Elev= 30
  3855.1  268.12  4054.5  257.97  4261.2  249.88  4382.8  246.75  4536.5  244.96
  4552.2  244.81  4705.7  242.94  4892.5   239.6  4934.3   238.7  4979.1  239.02
  5000.6  237.68  5015.9  239.17    5077   238.4  5186.2  239.94  5453.1  241.51
  5512.3  242.65  5701.8  247.07  5896.2   247.2  5917.4   248.2  5990.6  248.61
  6078.5  250.47  6127.1  250.52  6133.7  251.34  6189.1  251.56  6290.4     250
  6364.6  251.68  6369.9  252.57  6410.2  254.06  6555.9  260.22  6635.1  262.46
#Mann= 10 ,-1 , 0
  3855.1     .05       0  4536.5      .1       0  4552.2     .05       0
  4705.7     .06       0  4892.5     .04       0  5186.2     .06       0
  5512.3     .05       0  5990.6     .08       0  6133.7      .1       0
  6410.2     .05       0
Bank Sta=4892.5,5186.2
XS Rating Curve= 0 ,0
Exp/Cntr=0.3,0.1

Chan Stop Cuts=-1
Use User Specified Reach Order=0
Composite Channel Slope=5