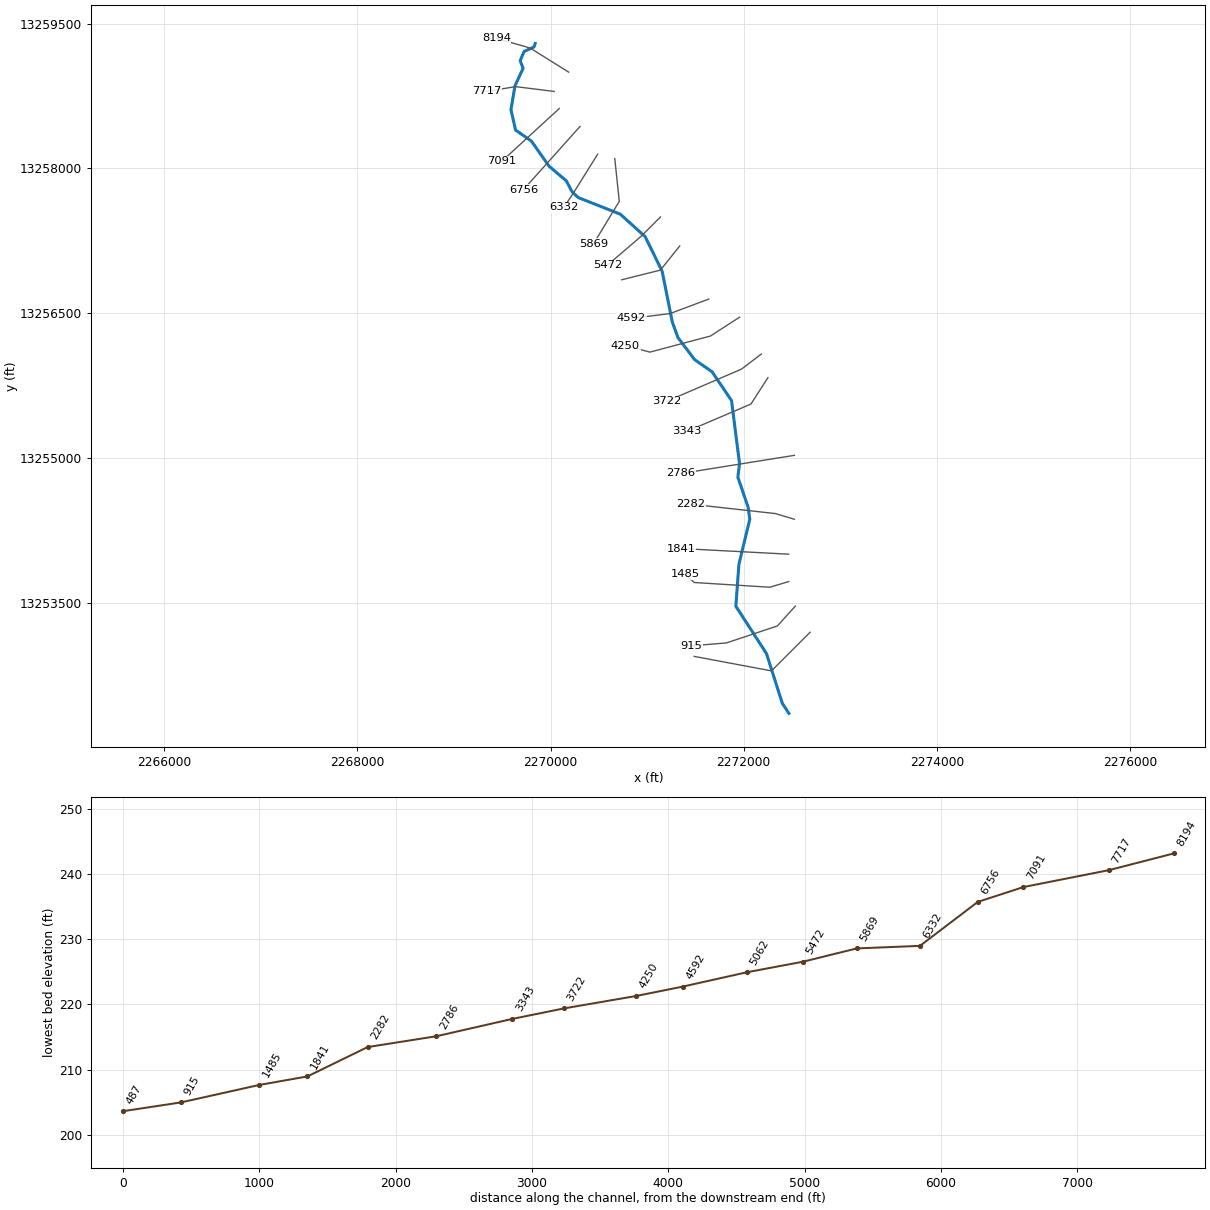
--- UNT005 IN PECR.prj (project) ---

Proj Title=UNT005 IN PECR Base Level Engineering
Current Plan=p01
Default Exp/Contr=0.3,0.1
English Units
Geom File=g01
Flow File=f01
Plan File=p01
Y Axis Title=Elevation
X Axis Title(PF)=Main Channel Distance
X Axis Title(XS)=Station
BEGIN DESCRIPTION:
UNT005 IN PECR
END DESCRIPTION:
DSS Export Rating Curves= 0
DSS Export Rating Curve Sorted= 0
DSS Export Volume Flow Curves= 0
DXF OffsetX= 0
DXF OffsetY= 0
DXF ScaleX= 1
DXF ScaleY= 10

--- UNT005 IN PECR.p01 (plan) ---

Plan Title=Multiple Run
Short Identifier=Multiple
Geom File=g01
Flow File=f01
Subcritical Flow
K Sum by GR= 0
Std Step Tol= 0.01
Critical Tol= 0.01
Num of Std Step Trials= 20
Max Error Tol= 0.3
Flow Tol Ratio= 0.001
Split Flow NTrial= 30
Split Flow Tol= 0.02
Split Flow Ratio= 0.02
Log Output Level= 0
Friction Slope Method= 1
Unsteady Friction Slope Method= 2
Unsteady Bridges Friction Slope Method= 1
Parabolic Critical Depth
Global Vel Dist=  1 , 1 , 1
Global Log Level= 0
CheckData=True
Encroach Param= -1, 0, 0, 0
BEGIN DESCRIPTION:
Multiple Run
END DESCRIPTION:

--- UNT005 IN PECR.f01 (steady flow) ---

Flow Title=Multiple
Program Version=4.10
Number of Profiles= 7
Profile Names=10-year,25-year,50-year,1pct_min,100-year,1pct_plu,500-year
River Rch & RM=UNT005 IN PECR,Reach-1         ,8194
     220     303     372     336     454     614     687
River Rch & RM=UNT005 IN PECR,Reach-1         ,7717
     377     533     665     609     824    1114    1285
Boundary for River Rch & Prof#=UNT005 IN PECR,Reach-1         , 1
Up Type= 0
Dn Type= 3
Dn Slope=0.005
Boundary for River Rch & Prof#=UNT005 IN PECR,Reach-1         , 2
Up Type= 0
Dn Type= 3
Dn Slope=0.005
Boundary for River Rch & Prof#=UNT005 IN PECR,Reach-1         , 3
Up Type= 0
Dn Type= 3
Dn Slope=0.005
Boundary for River Rch & Prof#=UNT005 IN PECR,Reach-1         , 4
Up Type= 0
Dn Type= 3
Dn Slope=0.005
Boundary for River Rch & Prof#=UNT005 IN PECR,Reach-1         , 5
Up Type= 0
Dn Type= 3
Dn Slope=0.005
Boundary for River Rch & Prof#=UNT005 IN PECR,Reach-1         , 6
Up Type= 0
Dn Type= 3
Dn Slope=0.005
Boundary for River Rch & Prof#=UNT005 IN PECR,Reach-1         , 7
Up Type= 0
Dn Type= 3
Dn Slope=0.005
DSS Import GetInterval= 0
DSS Import GetPeak= 0
DSS Import FillOption= 0

--- UNT005 IN PECR.g01 (geometry) ---

Geom Title=Existing Conditions

River Reach=UNT005 IN PECR,Reach-1
Reach XY= 30
      2269840.77     13259293.39      2269827.72     13259256.86
      2269726.22     13259211.48      2269685.38     13259114.28
      2269715.99     13259036.07      2269631.95     13258856.18
      2269590.16     13258606.91      2269637.72     13258396.86
      2269800.90     13258283.59      2269986.10     13258021.34
      2270164.17     13257870.21      2270223.92     13257755.63
      2270287.23     13257697.85      2270722.18     13257526.03
      2270979.93     13257293.13      2271155.21     13256935.82
      2271259.85     13256412.18      2271319.36     13256247.54
      2271491.29     13256020.27      2271673.33     13255893.07
      2271874.02     13255595.32      2271957.07     13254942.26
      2271939.37     13254802.75      2272044.65     13254495.53
      2272063.09     13254367.27      2271950.56     13253901.34
      2271918.68     13253466.65      2272235.85     13252976.08
      2272399.74     13252461.71      2272467.72     13252356.86

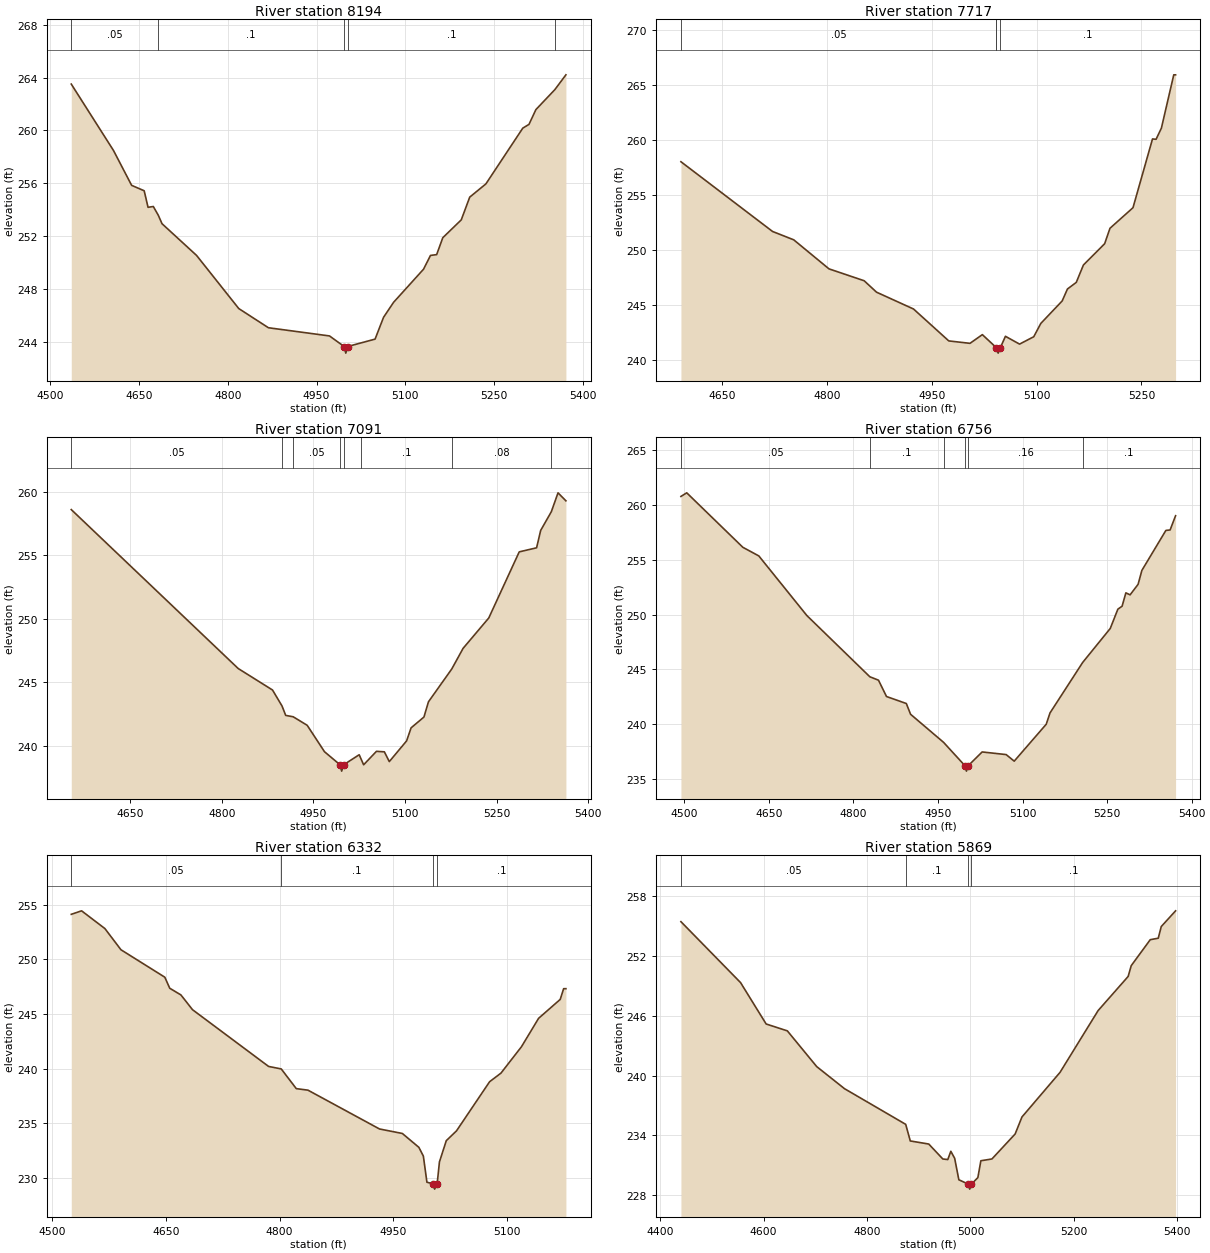
Type RM Length L Ch R = 1,8194,477,477,477
BEGIN DESCRIPTION:
UNT005 IN PECR 18.0
END DESCRIPTION:
XS GIS Cut Line= 3
      2270187.72     13258996.85      2269787.72     13259246.85
      2269437.73     13259346.85
#Sta/Elev= 30
  4535.5  263.51  4606.8  258.49  4637.5  255.85  4658.7  255.44  4665.2  254.19
  4674.1  254.25  4682.4  253.60  4688.8  252.95  4747.2  250.55  4818.5  246.53
  4868.6  245.08  4971.8  244.46  4996.5  243.66  4999.3  243.16  5002.5  243.66
  5048.8  244.22  5063.1  245.87  5080.0  247.00  5130.7  249.51  5142.4  250.55
  5152.8  250.61  5163.2  251.89  5194.4  253.24  5208.7  254.96  5236.0  255.96
  5298.4  260.18  5308.8  260.46  5320.5  261.58  5352.5  263.09  5371.2  264.21
#Mann=5,-1,0
  4535.5    0.05       0  4682.4     0.1       0  4996.5    0.07       0
  5002.5     0.1       0  5352.5    0.05       0
Bank Sta=4996.5,5002.5
Exp/Cntr=0.3,0.1

Type RM Length L Ch R = 1,7717,626,626,626
BEGIN DESCRIPTION:
UNT005 IN PECR 17.0
END DESCRIPTION:
XS GIS Cut Line= 3
      2270037.74     13258796.85      2269637.72     13258846.85
      2269337.69     13258796.85
#Sta/Elev= 30
  4591.5  257.99  4722.5  251.65  4752.8  250.89  4803.2  248.25  4853.5  247.17
  4871.2  246.13  4924.1  244.60  4974.5  241.70  5004.8  241.48  5022.5  242.27
  5041.6  241.14  5042.3  241.09  5045.1  240.59  5048.3  241.09  5055.5  242.12
  5075.7  241.41  5096.0  242.08  5106.1  243.29  5136.6  245.33  5144.2  246.42
  5156.8  247.02  5167.0  248.60  5197.4  250.54  5205.0  251.94  5237.9  253.81
  5265.8  260.06  5270.9  260.03  5278.5  261.04  5296.2  265.89  5298.8  265.89
#Mann=4,-1,0
  4591.5    0.05       0  5041.6     0.1       0  5042.3    0.04       0
  5048.3     0.1       0
Bank Sta=5042.3,5048.3
Exp/Cntr=0.3,0.1

Type RM Length L Ch R = 1,7091,335,335,335
BEGIN DESCRIPTION:
UNT005 IN PECR 16.0
END DESCRIPTION:
XS GIS Cut Line= 2
      2270090.26     13258620.19      2269493.80     13258072.61
#Sta/Elev= 30
  4553.5  258.60  4826.8  246.08  4882.9  244.39  4898.5  243.13  4904.5  242.39
  4916.8  242.28  4939.7  241.61  4968.0  239.53  4993.4  238.50  4996.1  238.00
  4999.4  238.50  5024.8  239.29  5028.3  238.91  5032.1  238.50  5053.1  239.56
  5066.0  239.52  5074.1  238.75  5102.4  240.38  5109.8  241.41  5130.8  242.26
  5138.2  243.46  5176.4  246.05  5194.9  247.67  5236.9  250.06  5286.8  255.27
  5315.2  255.59  5321.9  256.96  5339.3  258.43  5350.3  259.92  5363.2  259.29
#Mann=8,-1,0
  4553.5    0.05       0  4898.5     0.1       0  4916.8    0.05       0
  4993.4    0.03       0  4999.4    0.05       0  5028.3     0.1       0
  5176.4    0.08       0  5339.3     0.1       0
Bank Sta=4993.4,4999.4
Exp/Cntr=0.3,0.1

Type RM Length L Ch R = 1,6756,424,424,424
BEGIN DESCRIPTION:
UNT005 IN PECR 15.0
END DESCRIPTION:
XS GIS Cut Line= 2
      2270305.32     13258434.37      2269719.85     13257780.60
#Sta/Elev= 30
  4493.9  260.79  4504.2  261.12  4603.7  256.15  4632.1  255.36  4717.3  249.92
  4829.1  244.33  4844.4  244.02  4858.6  242.53  4893.8  241.89  4901.3  240.91
  4959.8  238.35  4997.7  236.22  5000.4  235.72  5003.7  236.22  5028.3  237.47
  5070.9  237.23  5085.2  236.63  5142.0  240.00  5148.7  241.03  5206.7  245.64
  5255.6  248.74  5269.1  250.50  5276.6  250.77  5283.3  251.99  5290.8  251.81
  5305.0  252.77  5311.7  254.04  5354.3  257.69  5361.8  257.73  5371.5  259.03
#Mann=6,-1,0
  4493.9    0.05       0  4829.1     0.1       0  4959.8    0.16       0
  4997.7    0.07       0  5003.7    0.16       0  5206.7     0.1       0
Bank Sta=4997.7,5003.7
Exp/Cntr=0.3,0.1

Type RM Length L Ch R = 1,6332,463,463,463
BEGIN DESCRIPTION:
UNT005 IN PECR 14.0
END DESCRIPTION:
XS GIS Cut Line= 3
      2270487.75     13258146.90      2270237.72     13257746.85
      2270137.73     13257596.88
#Sta/Elev= 30
  4525.4  254.11  4539.0  254.43  4569.7  252.81  4590.9  250.87  4648.7  248.36
  4655.2  247.35  4669.9  246.74  4685.2  245.39  4785.5  240.20  4802.2  239.97
  4822.0  238.17  4837.4  238.03  4931.7  234.48  4961.8  234.07  4983.6  232.80
  4989.5  232.00  4994.2  229.61  5001.7  229.48  5004.4  228.98  5007.7  229.48
  5010.7  231.47  5019.7  233.41  5033.2  234.31  5076.8  238.80  5091.8  239.59
  5118.8  242.00  5141.4  244.60  5169.9  246.33  5174.4  247.31  5177.4  247.31
#Mann=4,-1,0
  4525.4    0.05       0  4802.2     0.1       0  5001.7    0.07       0
  5007.7     0.1       0
Bank Sta=5001.7,5007.7
Exp/Cntr=0.3,0.1

Type RM Length L Ch R = 1,5869,397,397,397
BEGIN DESCRIPTION:
UNT005 IN PECR 13.0
END DESCRIPTION:
XS GIS Cut Line= 3
      2270664.93     13258101.54      2270711.79     13257658.89
      2270446.32     13257221.58
#Sta/Elev= 30
  4440.0  255.46  4555.3  249.34  4604.8  245.18  4645.8  244.49  4702.6  240.90
  4756.4  238.68  4874.7  235.10  4883.6  233.43  4919.3  233.12  4946.5  231.62
  4956.1  231.56  4962.0  232.39  4969.4  231.69  4977.5  229.53  4995.8  229.09
  4998.5  228.59  5001.8  229.09  5014.3  229.75  5020.1  231.44  5041.5  231.62
  5086.4  234.13  5099.6  235.84  5173.2  240.32  5246.9  246.53  5305.0  249.96
  5310.9  251.04  5347.7  253.65  5363.2  253.80  5369.0  254.97  5396.7  256.55
#Mann=4,-1,0
  4440.0    0.05       0  4874.7     0.1       0  4995.8    0.07       0
  5001.8     0.1       0
Bank Sta=4995.8,5001.8
Exp/Cntr=0.3,0.1

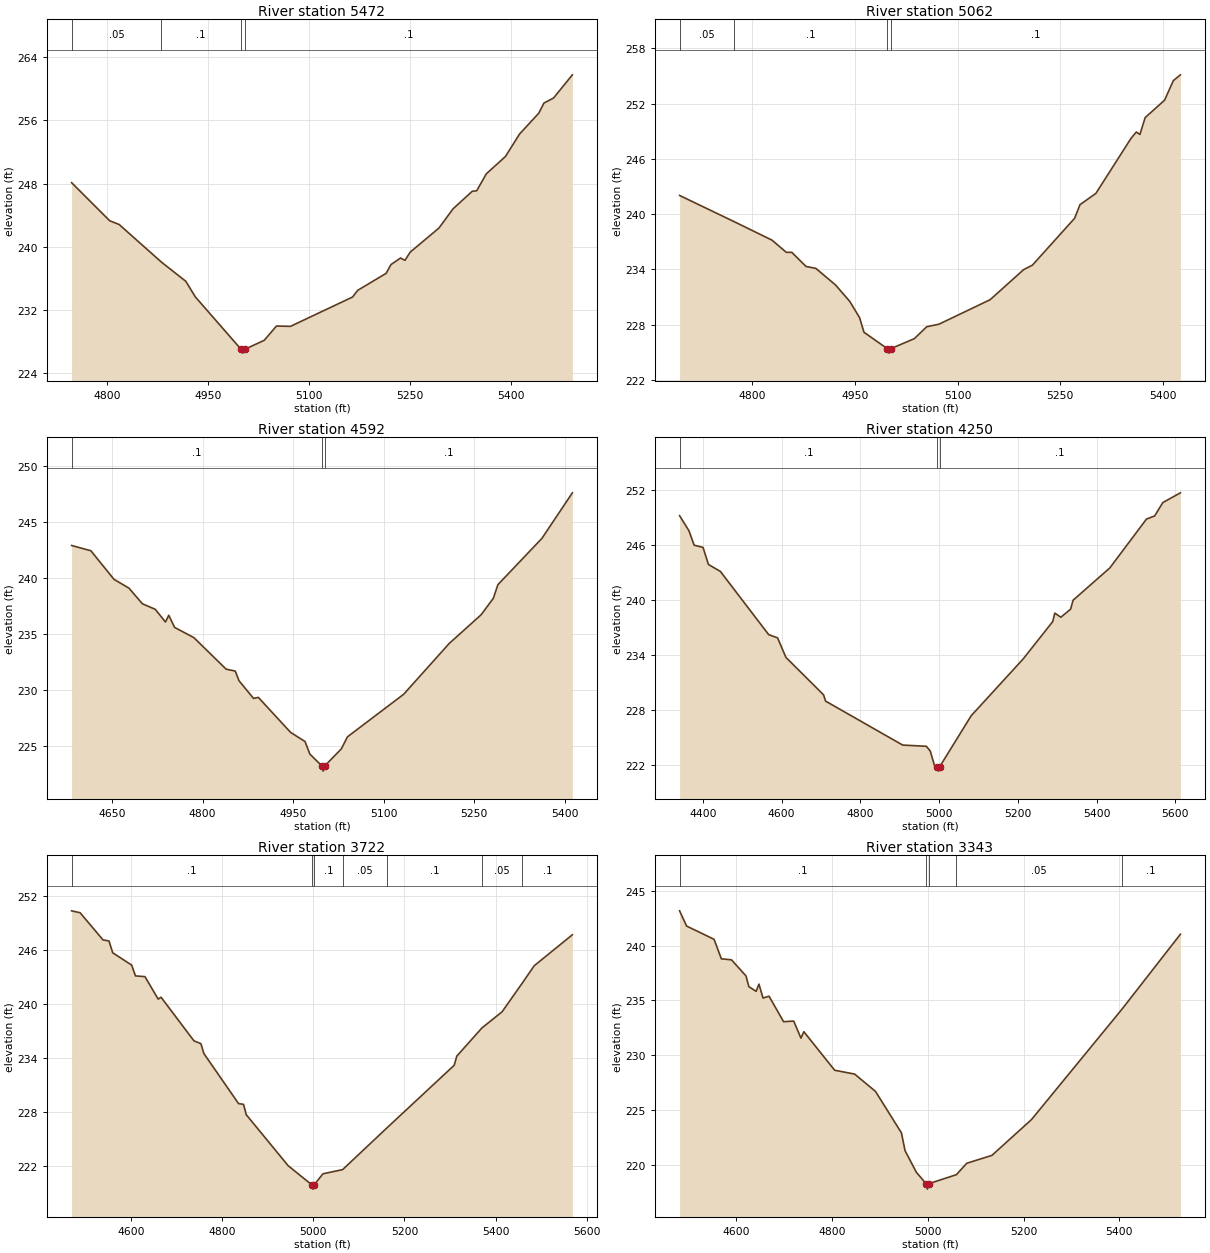
Type RM Length L Ch R = 1,5472,410,410,410
BEGIN DESCRIPTION:
UNT005 IN PECR 12.0
END DESCRIPTION:
XS GIS Cut Line= 3
      2271137.73     13257496.86      2270937.72     13257296.85
      2270587.75     13256996.88
#Sta/Elev= 30
  4747.4  248.12  4804.0  243.30  4818.1  242.82  4880.9  238.06  4917.1  235.63
  4931.3  233.65  4999.0  227.04  5001.7  226.54  5005.0  227.04  5033.5  228.16
  5051.7  229.97  5072.5  229.93  5164.7  233.64  5172.4  234.49  5214.6  236.64
  5221.8  237.75  5236.0  238.58  5242.6  238.29  5250.3  239.32  5293.1  242.38
  5314.0  244.81  5342.5  247.03  5349.1  247.09  5363.4  249.24  5391.9  251.44
  5412.8  254.28  5441.3  256.91  5449.0  258.20  5463.2  258.83  5491.2  261.77
#Mann=4,-1,0
  4747.4    0.05       0  4880.9     0.1       0  4999.0    0.07       0
  5005.0     0.1       0
Bank Sta=4999,5005
Exp/Cntr=0.3,0.1

Type RM Length L Ch R = 1,5062,470,470,470
BEGIN DESCRIPTION:
UNT005 IN PECR 11.0
END DESCRIPTION:
XS GIS Cut Line= 3
      2271337.71     13257196.84      2271137.72     13256946.85
      2270737.76     13256846.87
#Sta/Elev= 30
  4693.5  242.03  4773.8  239.17  4828.7  237.18  4849.6  235.86  4857.6  235.86
  4878.4  234.33  4892.8  234.12  4921.6  232.32  4942.4  230.54  4956.8  228.77
  4963.2  227.19  4997.0  225.43  4999.8  224.93  5003.0  225.43  5036.8  226.50
  5054.9  227.79  5072.9  228.07  5147.6  230.72  5196.6  233.98  5209.5  234.47
  5271.3  239.56  5279.1  241.03  5302.3  242.25  5353.8  248.23  5361.5  248.91
  5366.7  248.64  5374.4  250.47  5402.8  252.36  5415.6  254.48  5425.9  255.11
#Mann=4,-1,0
  4693.5    0.05       0  4773.8     0.1       0  4997.0    0.07       0
  5003.0     0.1       0
Bank Sta=4997,5003
Exp/Cntr=0.3,0.1

Type RM Length L Ch R = 1,4592,342,342,342
BEGIN DESCRIPTION:
UNT005 IN PECR 10.0
END DESCRIPTION:
XS GIS Cut Line= 3
      2271637.68     13256646.84      2271237.72     13256496.85
      2270837.70     13256446.85
#Sta/Elev= 30
  4582.7  242.87  4614.7  242.40  4653.0  239.85  4677.9  239.06  4700.1  237.67
  4721.5  237.17  4738.4  236.04  4743.8  236.64  4753.5  235.56  4785.6  234.64
  4839.0  231.83  4854.1  231.66  4860.3  230.80  4884.4  229.22  4892.4  229.31
  4945.8  226.19  4969.8  225.37  4977.8  224.25  4997.1  223.23  4999.8  222.73
  5003.1  223.23  5030.0  224.72  5040.1  225.79  5133.3  229.59  5208.9  234.13
  5261.8  236.69  5282.0  238.16  5289.5  239.37  5362.6  243.51  5413.0  247.57
#Mann=3,-1,0
  4582.7     0.1       0  4997.1    0.07       0  5003.1     0.1       0
Bank Sta=4997.1,5003.1
Exp/Cntr=0.3,0.1

Type RM Length L Ch R = 1,4250,528,528,528
BEGIN DESCRIPTION:
UNT005 IN PECR 9.0
END DESCRIPTION:
XS GIS Cut Line= 4
      2271957.73     13256459.38      2271654.63     13256263.83
      2271028.88     13256097.61      2270774.69     13256166.05
#Sta/Elev= 30
  4341.2  249.24  4365.0  247.59  4378.2  246.01  4400.7  245.77  4414.5  243.90
  4444.8  243.14  4567.3  236.23  4590.0  235.87  4611.1  233.74  4706.7  229.64
  4711.9  228.95  4907.6  224.14  4967.7  224.01  4977.6  223.49  4988.4  221.90
  4995.8  221.79  4998.5  221.29  5001.8  221.79  5081.5  227.35  5213.4  233.56
  5288.5  237.65  5293.8  238.58  5309.2  238.13  5333.9  239.01  5340.2  239.99
  5433.4  243.52  5526.6  248.87  5547.3  249.21  5568.0  250.67  5612.6  251.74
#Mann=3,-1,0
  4341.2     0.1       0  4995.8    0.07       0  5001.8     0.1       0
Bank Sta=4995.8,5001.8
Exp/Cntr=0.3,0.1

Type RM Length L Ch R = 1,3722,379,379,379
BEGIN DESCRIPTION:
UNT005 IN PECR 8.0
END DESCRIPTION:
XS GIS Cut Line= 3
      2272182.61     13256078.06      2271977.28     13255921.62
      2271204.82     13255589.17
#Sta/Elev= 30
  4469.4  250.31  4488.1  250.10  4538.4  247.08  4551.5  246.96  4559.7  245.65
  4601.3  244.28  4609.6  243.08  4630.4  243.00  4659.5  240.50  4665.8  240.71
  4737.9  235.87  4753.3  235.55  4759.7  234.46  4835.9  228.89  4846.8  228.81
  4852.8  227.66  4944.8  221.99  4996.2  219.89  4999.0  219.39  5002.2  219.89
  5021.0  221.09  5064.3  221.56  5162.3  226.23  5309.1  233.15  5314.9  234.17
  5369.9  237.29  5414.2  239.09  5458.7  242.29  5484.8  244.21  5568.5  247.65
#Mann=7,-1,0
  4469.4     0.1       0  4996.2    0.07       0  5002.2     0.1       0
  5064.3    0.05       0  5162.3     0.1       0  5369.9    0.05       0
  5458.7     0.1       0
Bank Sta=4996.2,5002.2
Exp/Cntr=0.3,0.1

Type RM Length L Ch R = 1,3343,557,557,557
BEGIN DESCRIPTION:
UNT005 IN PECR 7.0
END DESCRIPTION:
XS GIS Cut Line= 3
      2272251.03     13255833.59      2272075.06     13255559.86
      2271411.49     13255276.87
#Sta/Elev= 30
  4481.1  243.18  4495.8  241.79  4553.2  240.58  4568.4  238.80  4589.5  238.71
  4619.9  237.24  4625.9  236.26  4641.1  235.83  4647.0  236.49  4655.5  235.22
  4668.1  235.39  4698.5  233.06  4719.6  233.12  4734.8  231.56  4740.8  232.15
  4805.3  228.63  4847.0  228.28  4890.6  226.70  4944.9  222.91  4952.4  221.29
  4976.0  219.32  4996.3  218.28  4999.1  217.78  5002.3  218.28  5059.7  219.10
  5081.3  220.14  5134.0  220.86  5216.7  224.13  5405.4  234.18  5527.9  241.04
#Mann=5,-1,0
  4481.1     0.1       0  4996.3    0.07       0  5002.3     0.1       0
  5059.7    0.05       0  5405.4     0.1       0
Bank Sta=4996.3,5002.3
Exp/Cntr=0.3,0.1

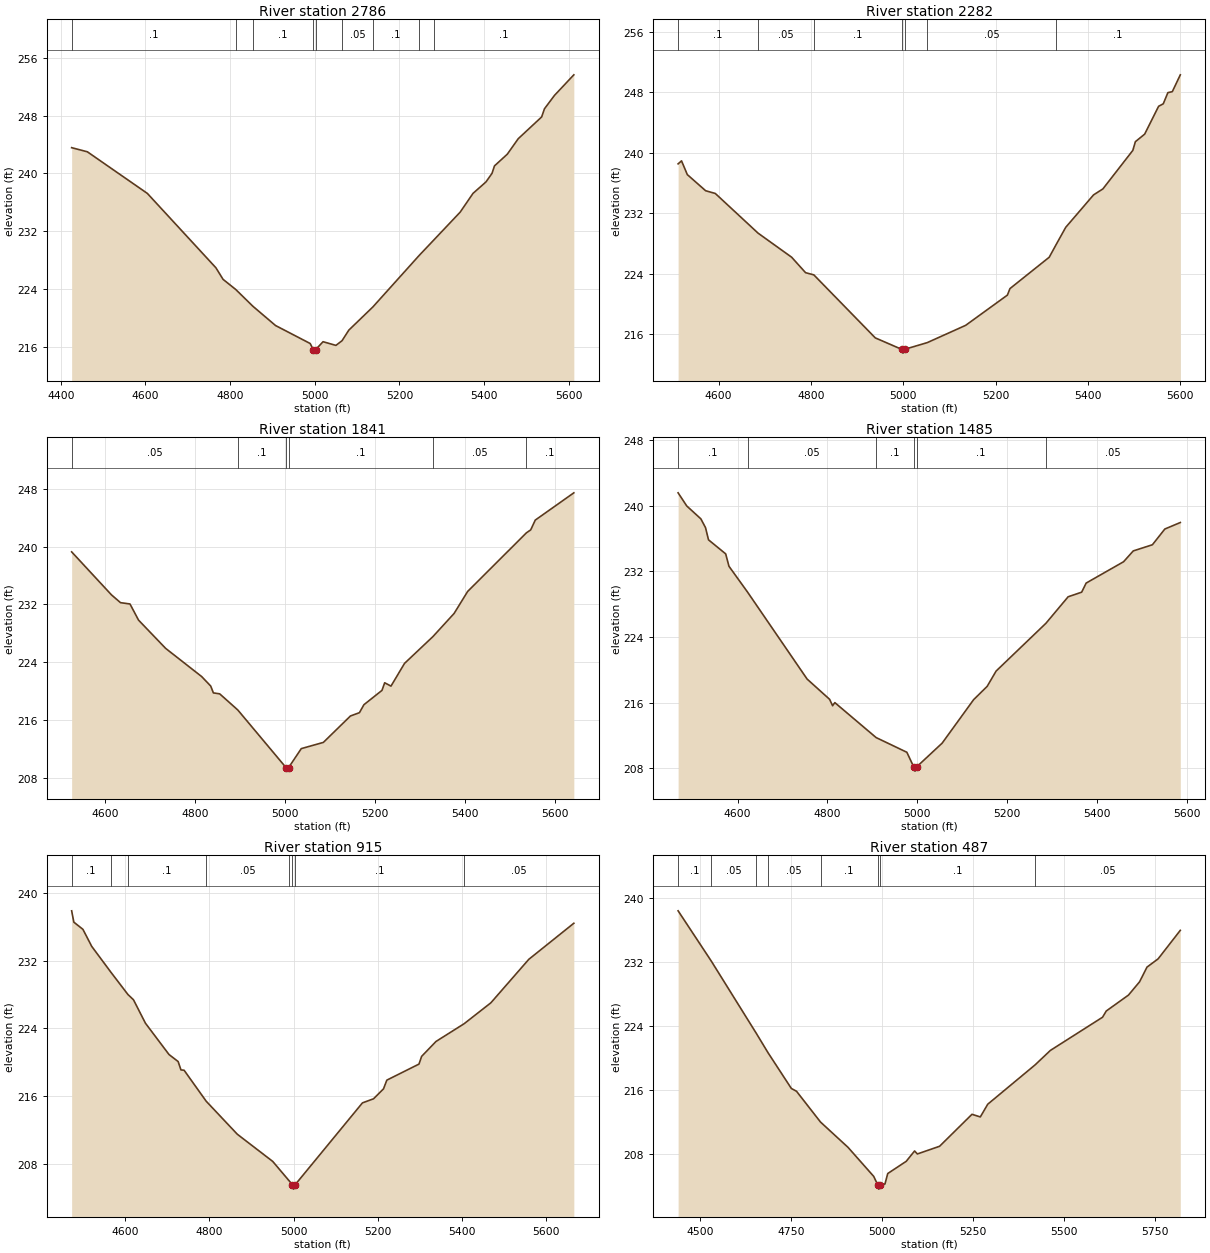
Type RM Length L Ch R = 1,2786,504,504,504
BEGIN DESCRIPTION:
UNT005 IN PECR 6.0
END DESCRIPTION:
XS GIS Cut Line= 2
      2272524.33     13255028.65      2271352.54     13254841.16
#Sta/Elev= 30
  4425.5  243.55  4462.6  242.98  4604.4  237.22  4766.4  226.93  4783.3  225.33
  4813.2  223.93  4853.7  221.61  4907.3  218.94  4989.2  216.45  4996.3  215.62
  4999.1  215.12  5002.3  215.62  5019.6  216.70  5050.0  216.19  5064.5  216.84
  5080.3  218.29  5137.3  221.51  5247.1  228.66  5281.9  230.81  5343.6  234.63
  5374.0  237.23  5404.4  238.80  5418.8  239.99  5424.7  241.03  5455.0  242.65
  5480.8  244.79  5536.1  247.80  5542.8  248.93  5566.4  250.78  5612.2  253.63
#Mann=9,-1,0
  4425.5     0.1       0  4813.2    0.05       0  4853.7     0.1       0
  4996.3    0.07       0  5002.3     0.1       0  5064.5    0.05       0
  5137.3     0.1       0  5247.1    0.05       0  5281.9     0.1       0
Bank Sta=4996.3,5002.3
Exp/Cntr=0.3,0.1

Type RM Length L Ch R = 1,2282,441,441,441
BEGIN DESCRIPTION:
UNT005 IN PECR 5.0
END DESCRIPTION:
XS GIS Cut Line= 3
      2272524.80     13254367.02      2272329.27     13254425.68
      2271451.01     13254523.26
#Sta/Elev= 30
  4512.5  238.54  4519.9  238.94  4532.4  237.12  4572.1  234.98  4593.0  234.62
  4685.7  229.36  4758.4  226.17  4788.6  224.12  4806.5  223.83  4939.6  215.48
  4996.9  213.96  4999.7  213.46  5002.9  213.96  5052.1  214.85  5135.3  217.14
  5225.8  221.15  5231.3  222.01  5316.4  226.17  5331.2  227.83  5352.1  230.13
  5412.4  234.43  5432.6  235.22  5497.5  240.33  5503.0  241.48  5523.1  242.48
  5553.3  246.17  5563.4  246.50  5573.4  247.98  5583.0  248.11  5600.3  250.34
#Mann=7,-1,0
  4512.5     0.1       0  4685.7    0.05       0  4806.5     0.1       0
  4996.9    0.07       0  5002.9     0.1       0  5052.1    0.05       0
  5331.2     0.1       0
Bank Sta=4996.9,5002.9
Exp/Cntr=0.3,0.1

Type RM Length L Ch R = 1,1841,356,356,356
BEGIN DESCRIPTION:
UNT005 IN PECR 4.0
END DESCRIPTION:
XS GIS Cut Line= 2
      2272466.16     13254005.25      2271352.10     13254063.89
#Sta/Elev= 30
  4525.4  239.26  4614.0  233.31  4634.0  232.24  4655.0  232.06  4674.0  229.83
  4734.1  225.93  4814.2  222.03  4834.3  220.72  4840.3  219.77  4854.3  219.64
  4894.5  217.41  5001.5  209.46  5004.2  208.96  5007.5  209.46  5035.5  212.07
  5084.6  212.93  5144.7  216.58  5164.7  217.04  5174.7  218.14  5214.8  220.12
  5220.8  221.17  5234.8  220.71  5264.9  223.85  5328.1  227.56  5375.0  230.75
  5405.1  233.79  5535.8  241.90  5545.2  242.30  5555.3  243.65  5641.0  247.42
#Mann=6,-1,0
  4525.4    0.05       0  4894.5     0.1       0  5001.5    0.07       0
  5007.5     0.1       0  5328.1    0.05       0  5535.8     0.1       0
Bank Sta=5001.5,5007.5
Exp/Cntr=0.3,0.1

Type RM Length L Ch R = 1,1485,570,570,570
BEGIN DESCRIPTION:
UNT005 IN PECR 3.0
END DESCRIPTION:
XS GIS Cut Line= 4
      2272466.14     13253721.71      2272270.60     13253663.04
      2271488.41     13253711.93      2271391.69     13253798.99
#Sta/Elev= 30
  4467.8  241.56  4487.0  239.96  4518.4  238.39  4528.8  237.32  4535.5  235.83
  4573.7  234.12  4581.0  232.61  4622.4  229.46  4755.0  218.86  4805.1  216.39
  4811.7  215.61  4816.7  215.99  4908.6  211.73  4977.0  209.94  4992.5  208.14
  4995.2  207.64  4998.5  208.14  5055.6  211.05  5125.7  216.35  5155.8  217.97
  5175.8  219.84  5286.5  225.65  5336.1  228.89  5366.2  229.45  5376.2  230.56
  5459.5  233.16  5481.1  234.48  5523.7  235.23  5551.4  237.15  5585.8  237.94
#Mann=6,-1,0
  4467.8     0.1       0  4622.4    0.05       0  4908.6     0.1       0
  4992.5    0.07       0  4998.5     0.1       0  5286.5    0.05       0
Bank Sta=4992.5,4998.5
Exp/Cntr=0.3,0.1

Type RM Length L Ch R = 1,915,428,428,428
BEGIN DESCRIPTION:
UNT005 IN PECR 2.0
END DESCRIPTION:
XS GIS Cut Line= 4
      2272534.59     13253467.49      2272348.82     13253262.17
      2271820.84     13253086.18      2271460.95     13253057.00
#Sta/Elev= 30
  4472.2  237.92  4477.4  236.58  4499.0  235.73  4520.0  233.71  4565.2  230.68
  4606.0  228.02  4619.3  227.39  4647.7  224.62  4703.8  220.91  4725.5  220.08
  4732.2  219.09  4739.7  219.05  4792.3  215.38  4866.2  211.48  4950.5  208.26
  4990.1  205.93  4997.5  205.48  5000.3  204.98  5003.5  205.48  5163.9  215.19
  5190.2  215.67  5214.0  216.85  5221.9  217.88  5298.4  219.78  5304.6  220.69
  5338.9  222.46  5405.8  224.56  5469.3  227.03  5559.6  232.18  5666.7  236.45
#Mann=8,-1,0
  4472.2     0.1       0  4565.2    0.05       0  4606.0     0.1       0
  4792.3    0.05       0  4990.1     0.1       0  4997.5    0.07       0
  5003.5     0.1       0  5405.8    0.05       0
Bank Sta=4997.5,5003.5
Exp/Cntr=0.3,0.1

Type RM Length L Ch R = 1,487,0,0,0
BEGIN DESCRIPTION:
UNT005 IN PECR 1.0
END DESCRIPTION:
XS GIS Cut Line= 3
      2272687.73     13253196.87      2272287.72     13252796.85
      2271487.76     13252946.85
#Sta/Elev= 30
  4439.4  238.43  4530.3  232.16  4654.4  223.09  4686.6  220.67  4750.5  216.21
  4764.7  215.86  4830.6  212.01  4906.1  208.85  4976.8  205.21  4988.0  204.12
  4990.7  203.62  4994.0  204.12  5007.6  204.26  5015.3  205.57  5066.1  207.10
  5089.0  208.39  5096.7  208.02  5157.7  208.98  5246.7  212.98  5269.6  212.65
  5290.0  214.24  5420.1  219.16  5462.1  220.97  5605.4  225.12  5615.6  225.90
  5676.6  227.89  5707.1  229.55  5727.5  231.39  5758.0  232.42  5819.0  235.99
#Mann=8,-1,0
  4439.4     0.1       0  4530.3    0.05       0  4654.4     0.1       0
  4686.6    0.05       0  4830.6     0.1       0  4988.0    0.07       0
  4994.0     0.1       0  5420.1    0.05       0
Bank Sta=4988,4994
Exp/Cntr=0.3,0.1

Chan Stop Cuts=-1