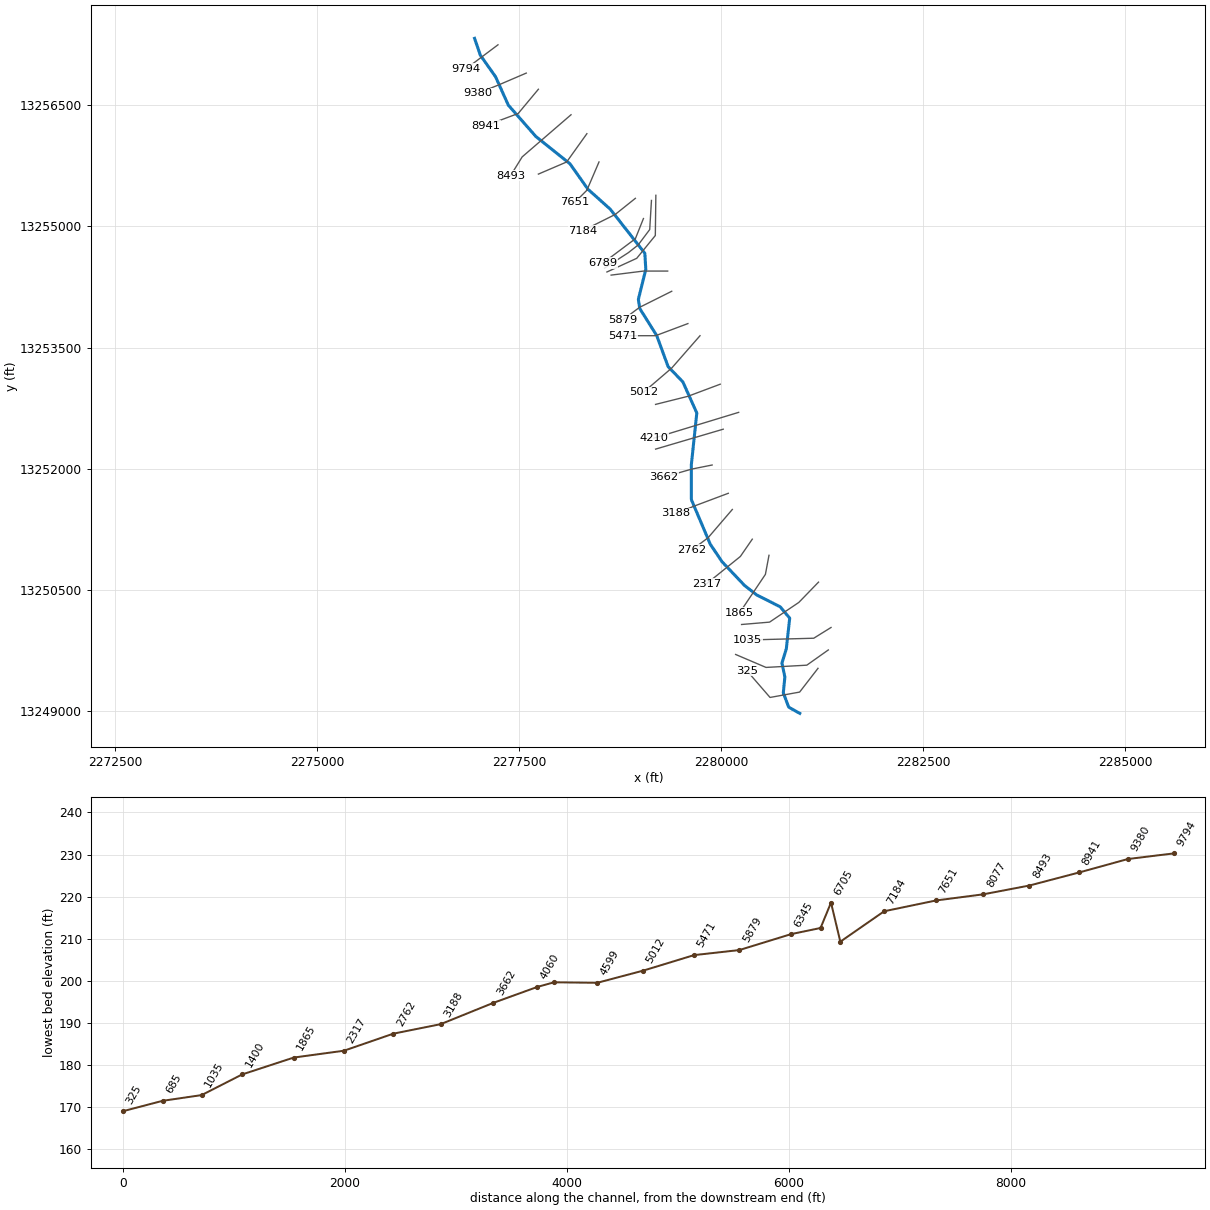
--- UNT006 IN PECR.prj (project) ---

Proj Title=UNT006 IN PECR Base Level Engineering
Current Plan=p01
Default Exp/Contr=0.3,0.1
English Units
Geom File=g01
Flow File=f01
Plan File=p01
Y Axis Title=Elevation
X Axis Title(PF)=Main Channel Distance
X Axis Title(XS)=Station
BEGIN DESCRIPTION:
UNT006 IN PECR
END DESCRIPTION:
DSS Export Rating Curves= 0
DSS Export Rating Curve Sorted= 0
DSS Export Volume Flow Curves= 0
DXF OffsetX= 0
DXF OffsetY= 0
DXF ScaleX= 1
DXF ScaleY= 10

--- UNT006 IN PECR.p01 (plan) ---

Plan Title=Multiple Run
Short Identifier=Multiple
Geom File=g01
Flow File=f01
Subcritical Flow
K Sum by GR= 0
Std Step Tol= 0.01
Critical Tol= 0.01
Num of Std Step Trials= 20
Max Error Tol= 0.3
Flow Tol Ratio= 0.001
Split Flow NTrial= 30
Split Flow Tol= 0.02
Split Flow Ratio= 0.02
Log Output Level= 0
Friction Slope Method= 1
Unsteady Friction Slope Method= 2
Unsteady Bridges Friction Slope Method= 1
Parabolic Critical Depth
Global Vel Dist=  1 , 1 , 1
Global Log Level= 0
CheckData=True
Encroach Param= -1, 0, 0, 0
BEGIN DESCRIPTION:
Multiple Run
END DESCRIPTION:

--- UNT006 IN PECR.f01 (steady flow) ---

Flow Title=Multiple
Program Version=4.10
Number of Profiles= 7
Profile Names=10-year,25-year,50-year,1pct_min,100-year,1pct_plu,500-year
River Rch & RM=UNT006 IN PECR,Reach-1         ,9794
     200     274     334     300     406     549     609
River Rch & RM=UNT006 IN PECR,Reach-1         ,9380
     362     510     635     582     787    1064    1225
Boundary for River Rch & Prof#=UNT006 IN PECR,Reach-1         , 1
Up Type= 0
Dn Type= 3
Dn Slope=0.005
Boundary for River Rch & Prof#=UNT006 IN PECR,Reach-1         , 2
Up Type= 0
Dn Type= 3
Dn Slope=0.005
Boundary for River Rch & Prof#=UNT006 IN PECR,Reach-1         , 3
Up Type= 0
Dn Type= 3
Dn Slope=0.005
Boundary for River Rch & Prof#=UNT006 IN PECR,Reach-1         , 4
Up Type= 0
Dn Type= 3
Dn Slope=0.005
Boundary for River Rch & Prof#=UNT006 IN PECR,Reach-1         , 5
Up Type= 0
Dn Type= 3
Dn Slope=0.005
Boundary for River Rch & Prof#=UNT006 IN PECR,Reach-1         , 6
Up Type= 0
Dn Type= 3
Dn Slope=0.005
Boundary for River Rch & Prof#=UNT006 IN PECR,Reach-1         , 7
Up Type= 0
Dn Type= 3
Dn Slope=0.005
DSS Import GetInterval= 0
DSS Import GetPeak= 0
DSS Import FillOption= 0

--- UNT006 IN PECR.g01 (geometry) ---

Geom Title=Existing Conditions

River Reach=UNT006 IN PECR,Reach-1
Reach XY= 30
      2276947.72     13257326.85      2277019.61     13257117.62
      2277207.48     13256851.75      2277365.46     13256500.58
      2277706.15     13256112.33      2278129.74     13255772.62
      2278351.01     13255459.50      2278627.05     13255212.63
      2279054.91     13254667.34      2279066.86     13254467.29
      2278974.92     13254096.59      2278991.89     13253983.89
      2279201.83     13253649.13      2279343.06     13253264.35
      2279525.24     13253075.78      2279698.05     13252691.10
      2279630.58     13252051.33      2279630.89     13251618.19
      2279864.37     13251067.49      2280009.86     13250850.48
      2280287.33     13250558.07      2280438.66     13250439.33
      2280730.66     13250291.78      2280847.76     13250151.72
      2280805.80     13249772.41      2280751.80     13249596.17
      2280787.66     13249422.67      2280768.59     13249227.40
      2280835.19     13249050.27      2280972.53     13248973.40

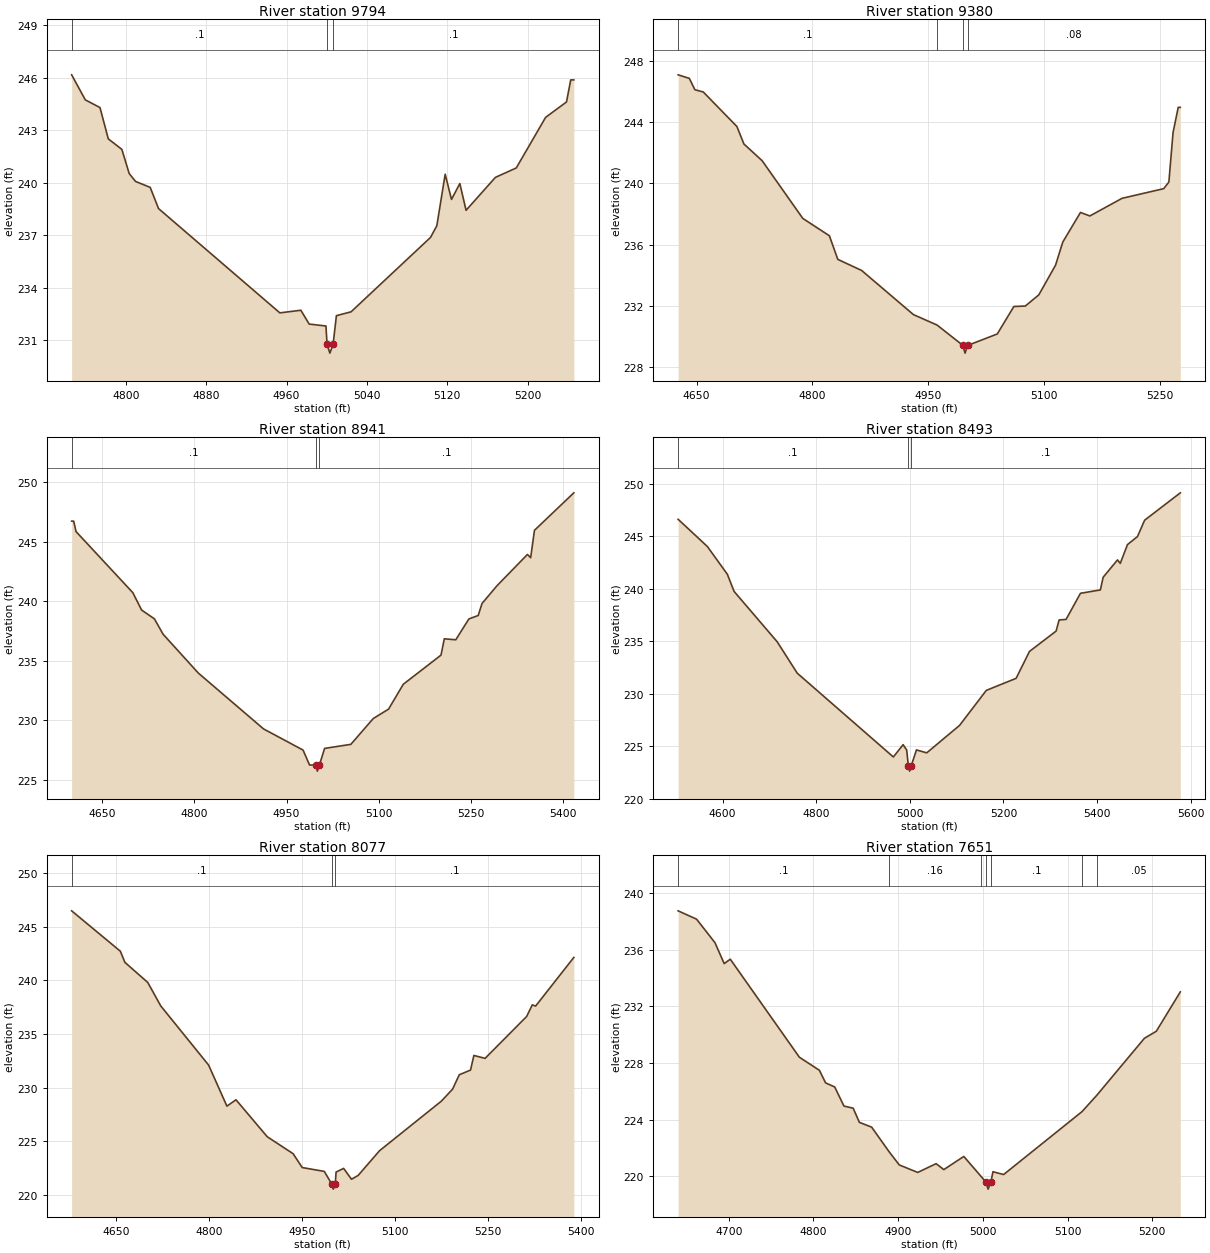
Type RM Length L Ch R = 1,9794,414,414,414
BEGIN DESCRIPTION:
UNT006 IN PECR 22.0
END DESCRIPTION:
XS GIS Cut Line= 3
      2277237.75     13257246.88      2277037.72     13257096.85
      2276837.75     13256946.88
#Sta/Elev= 30
  4746.0  246.16  4759.6  244.73  4774.2  244.29  4782.5  242.50  4796.0  241.90
  4803.3  240.52  4809.6  240.07  4824.2  239.73  4832.5  238.52  4953.3  232.56
  4974.2  232.71  4982.5  231.92  4999.2  231.81  5000.3  230.76  5003.1  230.26
  5006.3  230.76  5009.6  232.40  5024.2  232.62  5103.3  236.87  5109.6  237.54
  5117.9  240.48  5124.2  239.04  5132.5  239.95  5138.7  238.42  5167.9  240.30
  5188.7  240.84  5217.9  243.73  5238.7  244.61  5242.9  245.87  5246.0  245.87
#Mann=3,-1,0
  4746.0     0.1       0  5000.3    0.07       0  5006.3     0.1       0
Bank Sta=5000.3,5006.3
Exp/Cntr=0.3,0.1

Type RM Length L Ch R = 1,9380,439,439,439
BEGIN DESCRIPTION:
UNT006 IN PECR 21.0
END DESCRIPTION:
XS GIS Cut Line= 3
      2277587.70     13256896.84      2277237.72     13256746.85
      2276987.74     13256646.86
#Sta/Elev= 30
  4626.1  247.07  4640.6  246.84  4647.8  246.10  4658.7  245.95  4702.2  243.70
  4711.3  242.56  4734.9  241.47  4787.5  237.71  4821.9  236.58  4832.8  235.04
  4863.6  234.32  4930.7  231.44  4961.3  230.76  4994.8  229.43  4997.5  228.93
  5000.8  229.43  5039.2  230.18  5060.7  231.97  5075.5  232.00  5093.0  232.73
  5114.6  234.66  5124.0  236.17  5146.9  238.10  5159.0  237.87  5200.7  239.02
  5254.6  239.65  5261.3  240.08  5266.7  243.30  5273.4  244.95  5276.1  244.95
#Mann=4,-1,0
  4626.1     0.1       0  4961.3    0.08       0  4994.8    0.07       0
  5000.8    0.08       0
Bank Sta=4994.8,5000.8
Exp/Cntr=0.3,0.1

Type RM Length L Ch R = 1,8941,448,448,448
BEGIN DESCRIPTION:
UNT006 IN PECR 20.0
END DESCRIPTION:
XS GIS Cut Line= 3
      2277737.72     13256696.86      2277487.72     13256396.85
      2277087.73     13256246.86
#Sta/Elev= 30
  4600.1  246.75  4603.4  246.75  4607.3  245.87  4699.7  240.74  4714.0  239.28
  4734.8  238.54  4749.1  237.24  4806.4  233.98  4912.5  229.29  4976.9  227.51
  4987.4  226.26  4997.4  226.24  5000.2  225.74  5003.4  226.24  5012.0  227.65
  5054.7  227.99  5091.2  230.16  5116.1  230.95  5140.1  233.04  5201.5  235.49
  5206.9  236.86  5225.6  236.78  5246.9  238.53  5262.1  238.82  5268.3  239.83
  5292.3  241.30  5342.2  243.95  5347.5  243.68  5353.7  245.98  5417.8  249.13
#Mann=3,-1,0
  4600.1     0.1       0  4997.4    0.07       0  5003.4     0.1       0
Bank Sta=4997.4,5003.4
Exp/Cntr=0.3,0.1

Type RM Length L Ch R = 1,8493,416,416,416
BEGIN DESCRIPTION:
UNT006 IN PECR 19.0
END DESCRIPTION:
XS GIS Cut Line= 3
      2278141.63     13256381.24      2277537.04     13255859.85
      2277392.79     13255626.84
#Sta/Elev= 30
  4505.2  246.63  4567.6  244.04  4610.4  241.39  4624.7  239.76  4716.8  234.96
  4759.6  231.97  4964.8  223.99  4985.7  225.16  4993.3  224.65  4996.9  223.14
  4999.6  222.64  5002.9  223.14  5014.2  224.66  5036.1  224.38  5106.3  227.00
  5163.3  230.33  5227.0  231.48  5255.5  234.04  5312.4  235.98  5318.8  237.04
  5333.6  237.09  5364.4  239.58  5406.9  239.90  5412.9  241.11  5443.5  242.76
  5449.4  242.43  5464.8  244.22  5486.1  244.98  5501.4  246.54  5577.6  249.15
#Mann=3,-1,0
  4505.2     0.1       0  4996.9    0.07       0  5002.9     0.1       0
Bank Sta=4996.9,5002.9
Exp/Cntr=0.3,0.1

Type RM Length L Ch R = 1,8077,426,426,426
BEGIN DESCRIPTION:
UNT006 IN PECR 18.0
END DESCRIPTION:
XS GIS Cut Line= 3
      2278337.71     13256146.84      2278087.72     13255796.85
      2277737.71     13255646.85
#Sta/Elev= 30
  4577.7  246.47  4656.3  242.71  4663.7  241.67  4700.6  239.80  4721.5  237.62
  4798.9  232.10  4828.4  228.28  4843.1  228.87  4893.5  225.43  4935.3  223.85
  4950.0  222.56  4985.7  222.20  4997.4  221.05  5000.2  220.55  5003.4  221.05
  5004.7  222.14  5016.9  222.48  5029.6  221.47  5040.4  221.83  5074.9  224.13
  5174.6  228.74  5192.8  229.86  5203.6  231.20  5221.8  231.64  5227.2  233.00
  5245.3  232.73  5312.4  236.63  5321.5  237.71  5326.9  237.60  5388.6  242.13
#Mann=3,-1,0
  4577.7     0.1       0  4997.4    0.07       0  5003.4     0.1       0
Bank Sta=4997.4,5003.4
Exp/Cntr=0.3,0.1

Type RM Length L Ch R = 1,7651,467,467,467
BEGIN DESCRIPTION:
UNT006 IN PECR 17.0
END DESCRIPTION:
XS GIS Cut Line= 3
      2278487.72     13255796.85      2278337.72     13255446.85
      2278187.73     13255296.87
#Sta/Elev= 30
  4640.2  238.76  4662.0  238.17  4683.7  236.51  4694.6  235.03  4701.8  235.34
  4783.4  228.41  4807.0  227.49  4814.3  226.60  4825.1  226.31  4836.0  224.96
  4846.9  224.81  4854.2  223.81  4868.7  223.47  4889.1  221.75  4901.3  220.80
  4923.1  220.27  4944.8  220.89  4953.9  220.47  4977.5  221.40  4998.0  219.98
  5003.5  219.59  5006.2  219.09  5009.5  219.59  5011.9  220.32  5024.5  220.12
  5117.1  224.57  5134.6  225.73  5190.7  229.75  5204.8  230.25  5233.1  233.03
#Mann=7,-1,0
  4640.2     0.1       0  4889.1    0.16       0  4998.0     0.1       0
  5003.5    0.07       0  5009.5     0.1       0  5117.1    0.16       0
  5134.6    0.05       0
Bank Sta=5003.5,5009.5
Exp/Cntr=0.3,0.1

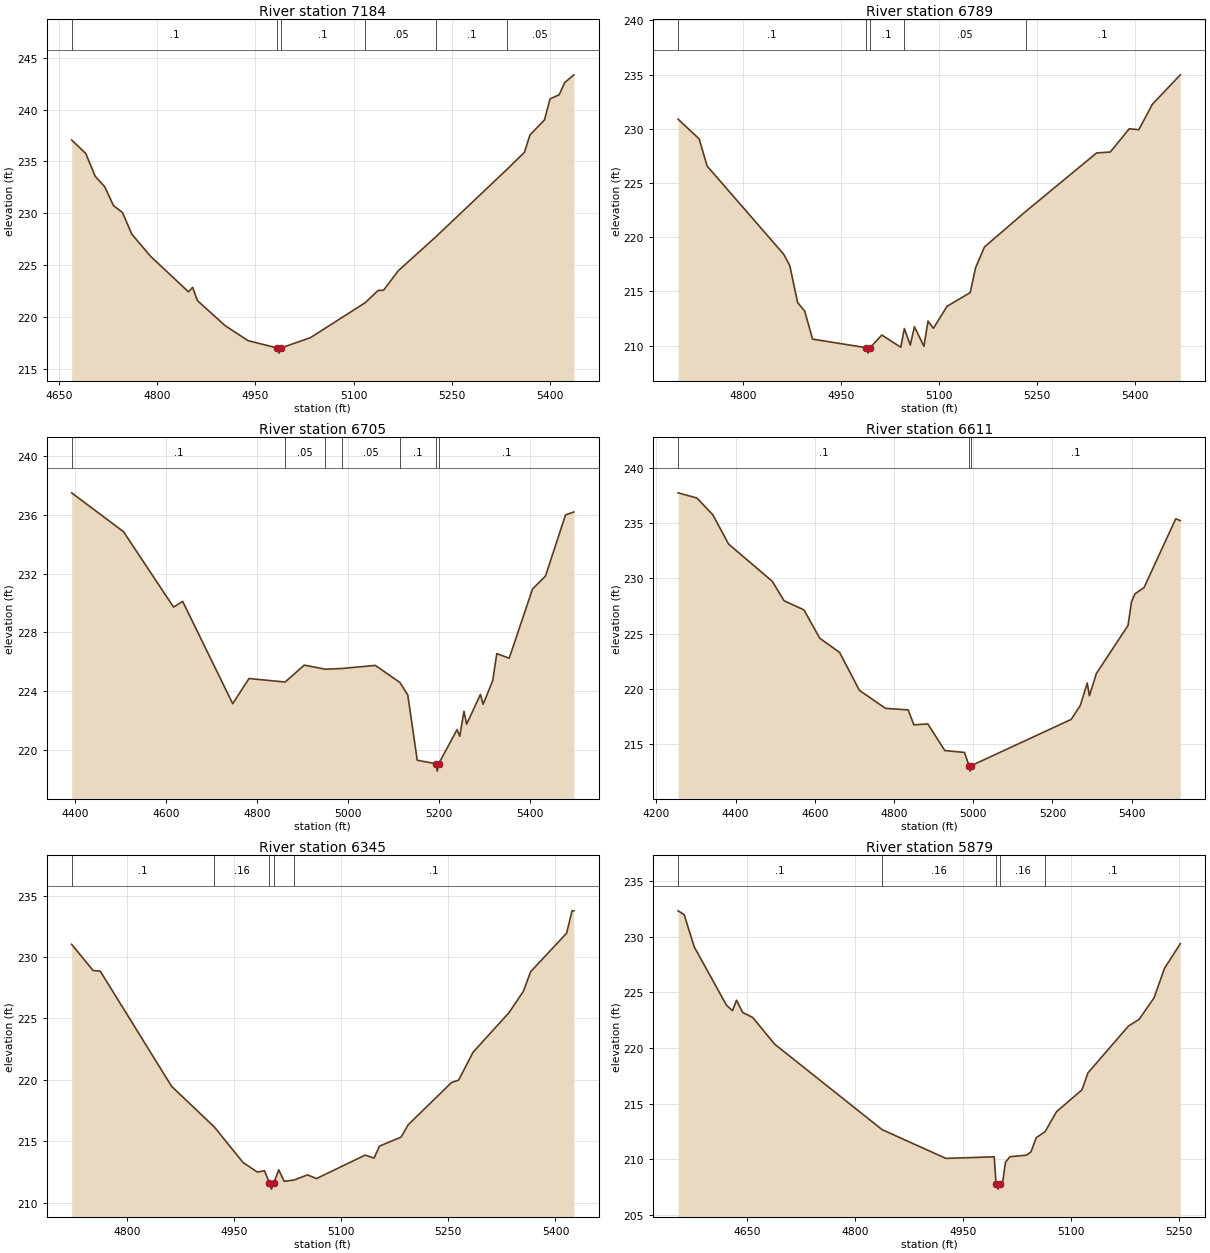
Type RM Length L Ch R = 1,7184,395,395,395
BEGIN DESCRIPTION:
UNT006 IN PECR 16.0
END DESCRIPTION:
XS GIS Cut Line= 3
      2278937.71     13255346.84      2278687.72     13255146.85
      2278287.68     13254946.83
#Sta/Elev= 30
  4669.3  237.07  4690.9  235.77  4705.3  233.57  4719.7  232.58  4733.3  230.74
  4746.9  230.09  4761.3  227.99  4790.1  225.85  4847.8  222.44  4854.2  222.87
  4861.4  221.60  4903.8  219.18  4939.0  217.73  4983.2  217.03  4986.0  216.53
  4989.2  217.03  5034.2  218.02  5117.9  221.39  5137.6  222.57  5146.0  222.59
  5168.3  224.46  5226.0  227.75  5334.2  234.22  5361.2  235.88  5369.6  237.55
  5391.9  239.01  5400.3  241.03  5414.3  241.43  5422.7  242.60  5436.7  243.35
#Mann=6,-1,0
  4669.3     0.1       0  4983.2    0.07       0  4989.2     0.1       0
  5117.9    0.05       0  5226.0     0.1       0  5334.2    0.05       0
Bank Sta=4983.2,4989.2
Exp/Cntr=0.3,0.1

Type RM Length L Ch R = 1,6789,84,84,84
BEGIN DESCRIPTION:
UNT006 IN PECR 15.0
END DESCRIPTION:
XS GIS Cut Line= 3
      2279037.72     13255096.86      2278937.72     13254846.85
      2278537.69     13254546.83
#Sta/Elev= 30
  4700.5  230.88  4732.8  229.06  4744.9  226.56  4862.1  218.44  4871.5  217.39
  4883.6  213.97  4894.4  213.19  4906.5  210.60  4988.6  209.81  4991.4  209.31
  4994.6  209.81  5012.5  210.98  5041.6  209.85  5047.1  211.58  5056.2  210.05
  5062.5  211.75  5077.1  209.94  5083.3  212.27  5091.6  211.60  5112.5  213.63
  5147.9  214.89  5156.2  217.19  5169.8  219.10  5232.7  222.36  5341.6  227.77
  5362.5  227.85  5391.6  230.00  5406.2  229.91  5427.1  232.26  5469.8  234.97
#Mann=5,-1,0
  4700.5     0.1       0  4988.6    0.07       0  4994.6     0.1       0
  5047.1    0.05       0  5232.7     0.1       0
Bank Sta=4988.6,4994.6
Exp/Cntr=0.3,0.1

Type RM Length L Ch R = 1,6705,94,94,94
BEGIN DESCRIPTION:
Mapping XS fae17a77
END DESCRIPTION:
XS GIS Cut Line= 5
      2279136.98     13255320.81      2279115.28     13254960.59
      2278972.05     13254769.62      2278850.52     13254674.13
      2278555.37     13254483.15
#Sta/Elev= 30
  4391.7  237.48  4505.9  234.84  4616.1  229.72  4636.1  230.11  4746.3  223.16
  4782.2  224.87  4861.6  224.63  4903.9  225.78  4950.5  225.50  4986.6  225.55
  5060.4  225.76  5114.5  224.60  5131.8  223.75  5152.6  219.32  5193.8  219.08
  5196.6  218.58  5199.8  219.08  5240.3  221.40  5246.2  220.95  5255.5  222.64
  5261.4  221.77  5291.7  223.79  5297.7  223.12  5318.8  224.73  5327.8  226.56
  5355.1  226.25  5406.5  230.95  5435.0  231.83  5479.1  235.98  5497.4  236.18
#Mann=7,-1,0
  4391.7     0.1       0  4861.6    0.05       0  4950.5     0.1       0
  4986.6    0.05       0  5114.5     0.1       0  5193.8    0.04       0
  5199.8     0.1       0
Bank Sta=5193.8,5199.8
Exp/Cntr=0.3,0.1

Type RM Length L Ch R = 1,6611,266,266,266
BEGIN DESCRIPTION:
Mapping XS a267fbbd
END DESCRIPTION:
XS GIS Cut Line= 4
      2279191.24     13255384.39      2279184.72     13254886.80
      2278954.69     13254604.68      2278585.81     13254435.43
#Sta/Elev= 30
  4255.1  237.74  4302.6  237.27  4342.6  235.76  4382.6  233.10  4492.7  229.74
  4522.7  227.97  4572.7  227.15  4612.7  224.58  4662.7  223.30  4712.7  219.87
  4778.5  218.24  4835.8  218.10  4850.1  216.75  4885.3  216.83  4928.4  214.42
  4977.9  214.25  4989.3  213.06  4992.1  212.56  4995.3  213.06  5247.2  217.24
  5270.2  218.50  5287.7  220.53  5293.2  219.38  5310.7  221.39  5390.6  225.74
  5399.5  227.89  5408.1  228.60  5431.1  229.17  5511.1  235.39  5522.6  235.23
#Mann=3,-1,0
  4255.1     0.1       0  4989.3    0.07       0  4995.3     0.1       0
Bank Sta=4989.3,4995.3
Exp/Cntr=0.3,0.1

Type RM Length L Ch R = 1,6345,466,466,466
BEGIN DESCRIPTION:
UNT006 IN PECR 14.0
END DESCRIPTION:
XS GIS Cut Line= 3
      2279337.69     13254446.85      2279037.72     13254446.85
      2278637.71     13254396.85
#Sta/Elev= 30
  4722.6  231.04  4752.6  228.91  4762.6  228.86  4862.6  219.47  4922.4  216.16
  4962.6  213.27  4982.6  212.49  4992.6  212.60  4999.6  211.60  5002.3  211.10
  5005.6  211.60  5012.6  212.67  5020.1  211.74  5033.9  211.84  5052.8  212.26
  5065.4  211.96  5133.4  213.87  5146.0  213.63  5153.6  214.60  5183.8  215.34
  5193.9  216.35  5254.4  219.78  5264.4  219.98  5284.6  222.25  5335.0  225.48
  5355.1  227.22  5365.2  228.81  5415.6  231.95  5423.2  233.77  5425.7  233.77
#Mann=5,-1,0
  4722.6     0.1       0  4922.4    0.16       0  4999.6    0.07       0
  5005.6    0.16       0  5033.9     0.1       0
Bank Sta=4999.6,5005.6
Exp/Cntr=0.3,0.1

Type RM Length L Ch R = 1,5879,408,408,408
BEGIN DESCRIPTION:
UNT006 IN PECR 13.0
END DESCRIPTION:
XS GIS Cut Line= 3
      2279387.75     13254196.87      2278987.72     13253996.85
      2278787.68     13253846.83
#Sta/Elev= 30
  4554.4  232.31  4562.8  231.97  4576.8  229.07  4621.5  223.84  4629.9  223.34
  4635.5  224.28  4643.9  223.19  4657.9  222.74  4688.6  220.33  4837.7  212.66
  4926.2  210.08  4993.3  210.22  4995.9  207.82  4998.6  207.32  5001.9  207.82
  5004.8  207.82  5008.9  209.73  5015.2  210.23  5038.1  210.37  5044.4  210.67
  5051.7  211.94  5064.1  212.49  5079.8  214.27  5115.2  216.24  5123.5  217.76
  5179.8  221.97  5194.4  222.56  5215.2  224.49  5229.8  227.15  5251.7  229.36
#Mann=5,-1,0
  4554.4     0.1       0  4837.7    0.16       0  4995.9    0.07       0
  5001.9    0.16       0  5064.1     0.1       0
Bank Sta=4995.9,5001.9
Exp/Cntr=0.3,0.1

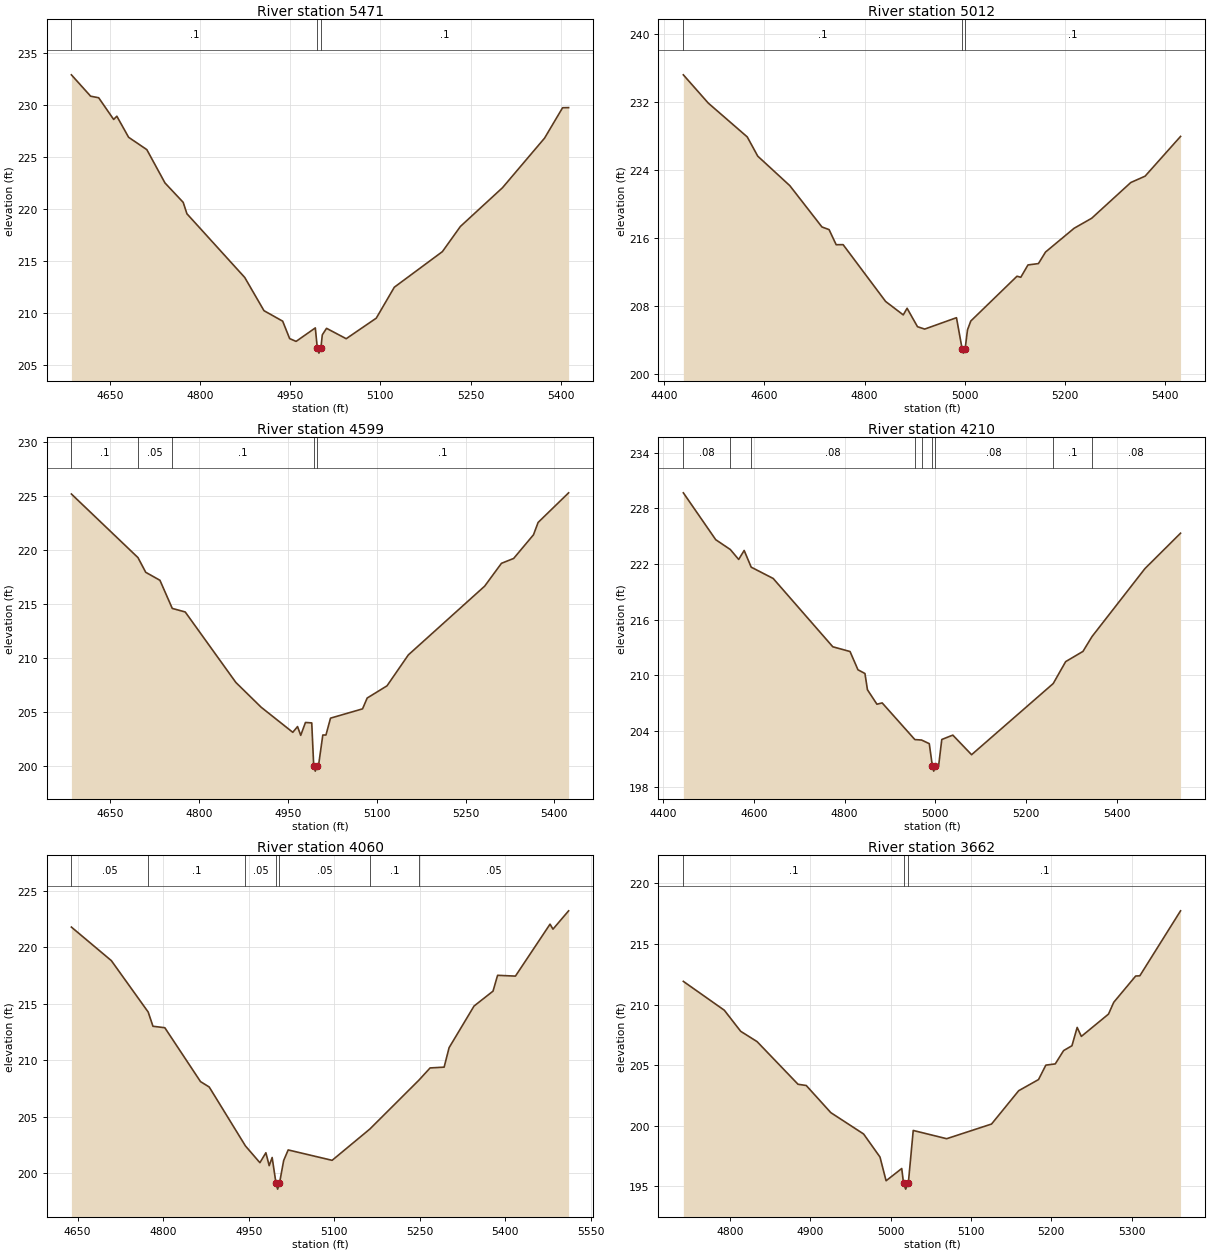
Type RM Length L Ch R = 1,5471,459,459,459
BEGIN DESCRIPTION:
UNT006 IN PECR 12.0
END DESCRIPTION:
XS GIS Cut Line= 3
      2279587.72     13253796.85      2279187.72     13253646.85
      2278787.72     13253646.85
#Sta/Elev= 30
  4585.9  232.94  4617.9  230.88  4631.3  230.73  4656.2  228.64  4661.5  228.95
  4681.1  226.92  4711.4  225.73  4741.6  222.52  4771.9  220.65  4778.1  219.55
  4874.3  213.41  4906.3  210.21  4937.4  209.20  4949.0  207.52  4959.7  207.25
  4991.7  208.55  4995.0  206.62  4997.7  206.12  5001.0  206.62  5003.3  207.88
  5010.4  208.51  5043.1  207.51  5093.1  209.49  5123.1  212.47  5203.1  215.90
  5233.1  218.33  5303.1  222.06  5373.1  226.84  5403.1  229.77  5413.1  229.78
#Mann=3,-1,0
  4585.9     0.1       0  4995.0    0.07       0  5001.0     0.1       0
Bank Sta=4995,5001
Exp/Cntr=0.3,0.1

Type RM Length L Ch R = 1,5012,413,413,413
BEGIN DESCRIPTION:
UNT006 IN PECR 11.0
END DESCRIPTION:
XS GIS Cut Line= 3
      2279737.72     13253646.85      2279387.72     13253246.85
      2279037.70     13252946.84
#Sta/Elev= 30
  4438.3  235.19  4488.1  231.86  4565.9  227.88  4586.8  225.62  4650.9  222.14
  4715.0  217.28  4729.2  216.97  4743.4  215.19  4757.2  215.20  4842.1  208.51
  4877.3  206.93  4884.9  207.71  4905.7  205.54  4920.0  205.26  4983.5  206.60
  4994.8  202.93  4997.5  202.43  5000.8  202.93  5005.5  205.17  5012.1  206.21
  5104.3  211.48  5111.9  211.36  5126.2  212.81  5147.1  212.97  5161.3  214.33
  5218.4  217.13  5253.5  218.31  5331.4  222.51  5360.0  223.26  5430.8  227.94
#Mann=3,-1,0
  4438.3     0.1       0  4994.8    0.07       0  5000.8     0.1       0
Bank Sta=4994.8,5000.8
Exp/Cntr=0.3,0.1

Type RM Length L Ch R = 1,4599,389,389,389
BEGIN DESCRIPTION:
UNT006 IN PECR 10.0
END DESCRIPTION:
XS GIS Cut Line= 3
      2279987.73     13253046.86      2279587.72     13252896.85
      2279187.74     13252796.86
#Sta/Elev= 30
  4584.5  225.18  4696.9  219.30  4710.0  217.94  4734.0  217.20  4754.8  214.60
  4776.7  214.27  4862.2  207.75  4904.9  205.46  4958.3  203.14  4966.3  203.67
  4971.7  202.86  4979.7  204.05  4990.3  204.01  4993.6  200.05  4996.3  199.55
  4999.6  200.05  5001.9  200.13  5009.0  202.89  5014.3  202.89  5022.0  204.45
  5076.1  205.31  5083.9  206.31  5117.4  207.44  5153.4  210.30  5282.3  216.66
  5310.6  218.77  5331.2  219.22  5364.7  221.41  5372.5  222.55  5424.0  225.29
#Mann=5,-1,0
  4584.5     0.1       0  4696.9    0.05       0  4754.8     0.1       0
  4993.6    0.07       0  4999.6     0.1       0
Bank Sta=4993.6,4999.6
Exp/Cntr=0.3,0.1

Type RM Length L Ch R = 1,4210,150,150,150
BEGIN DESCRIPTION:
Mapping XS 1ca72474
END DESCRIPTION:
XS GIS Cut Line= 2
      2280216.00     13252698.44      2279167.37     13252378.99
#Sta/Elev= 30
  4444.3  229.66  4515.7  224.61  4547.9  223.55  4566.3  222.48  4578.4  223.45
  4593.9  221.65  4642.4  220.43  4773.8  213.07  4811.8  212.56  4829.3  210.59
  4844.7  210.19  4850.2  208.44  4871.1  206.88  4882.7  207.02  4954.7  203.07
  4969.6  203.02  4986.5  202.63  4993.5  200.17  4996.3  199.67  4999.5  200.17
  5007.0  200.20  5014.1  203.08  5038.4  203.55  5079.8  201.44  5259.8  209.11
  5287.2  211.47  5325.3  212.57  5345.3  214.17  5461.9  221.49  5540.5  225.31
#Mann=9,-1,0
  4444.3    0.08       0  4547.9    0.05       0  4593.9    0.08       0
  4954.7     0.1       0  4969.6    0.08       0  4993.5    0.07       0
  4999.5    0.08       0  5259.8     0.1       0  5345.3    0.08       0
Bank Sta=4993.5,4999.5
Exp/Cntr=0.3,0.1

Type RM Length L Ch R = 1,4060,398,398,398
BEGIN DESCRIPTION:
UNT006 IN PECR 9.0
END DESCRIPTION:
XS GIS Cut Line= 2
      2280024.98     13252490.10      2279188.24     13252243.59
#Sta/Elev= 30
  4639.0  221.78  4709.1  218.81  4773.7  214.26  4782.1  213.00  4802.9  212.87
  4865.5  208.10  4880.8  207.62  4944.4  202.40  4969.7  200.92  4980.2  201.80
  4986.0  200.66  4991.2  201.38  4998.0  199.08  5000.8  198.58  5004.0  199.08
  5011.4  201.11  5019.3  202.05  5096.4  201.13  5162.6  203.90  5248.7  208.23
  5268.3  209.31  5292.9  209.38  5301.6  211.10  5345.4  214.79  5378.7  216.11
  5386.7  217.51  5418.0  217.44  5478.7  222.04  5483.9  221.60  5511.3  223.22
#Mann=7,-1,0
  4639.0    0.05       0  4773.7     0.1       0  4944.4    0.05       0
  4998.0   0.035       0  5004.0    0.05       0  5162.6     0.1       0
  5248.7    0.05       0
Bank Sta=4998,5004
Exp/Cntr=0.3,0.1

Type RM Length L Ch R = 1,3662,474,474,474
BEGIN DESCRIPTION:
UNT006 IN PECR 8.0
END DESCRIPTION:
XS GIS Cut Line= 3
      2279887.76     13252046.86      2279637.72     13251996.85
      2279287.72     13251896.85
#Sta/Elev= 30
  4741.9  211.92  4792.9  209.54  4813.3  207.80  4833.7  206.95  4884.7  203.43
  4894.9  203.33  4925.5  201.09  4966.3  199.33  4986.7  197.43  4994.3  195.47
  5013.8  196.48  5016.0  195.28  5018.7  194.78  5022.0  195.28  5028.1  199.62
  5069.7  198.94  5125.6  200.15  5159.4  202.90  5184.1  203.82  5193.2  205.01
  5204.9  205.11  5215.3  206.21  5225.7  206.61  5232.2  208.12  5237.4  207.38
  5271.2  209.22  5277.7  210.19  5305.0  212.36  5310.2  212.38  5360.9  217.74
#Mann=3,-1,0
  4741.9     0.1       0  5016.0    0.07       0  5022.0     0.1       0
Bank Sta=5016,5022
Exp/Cntr=0.3,0.1

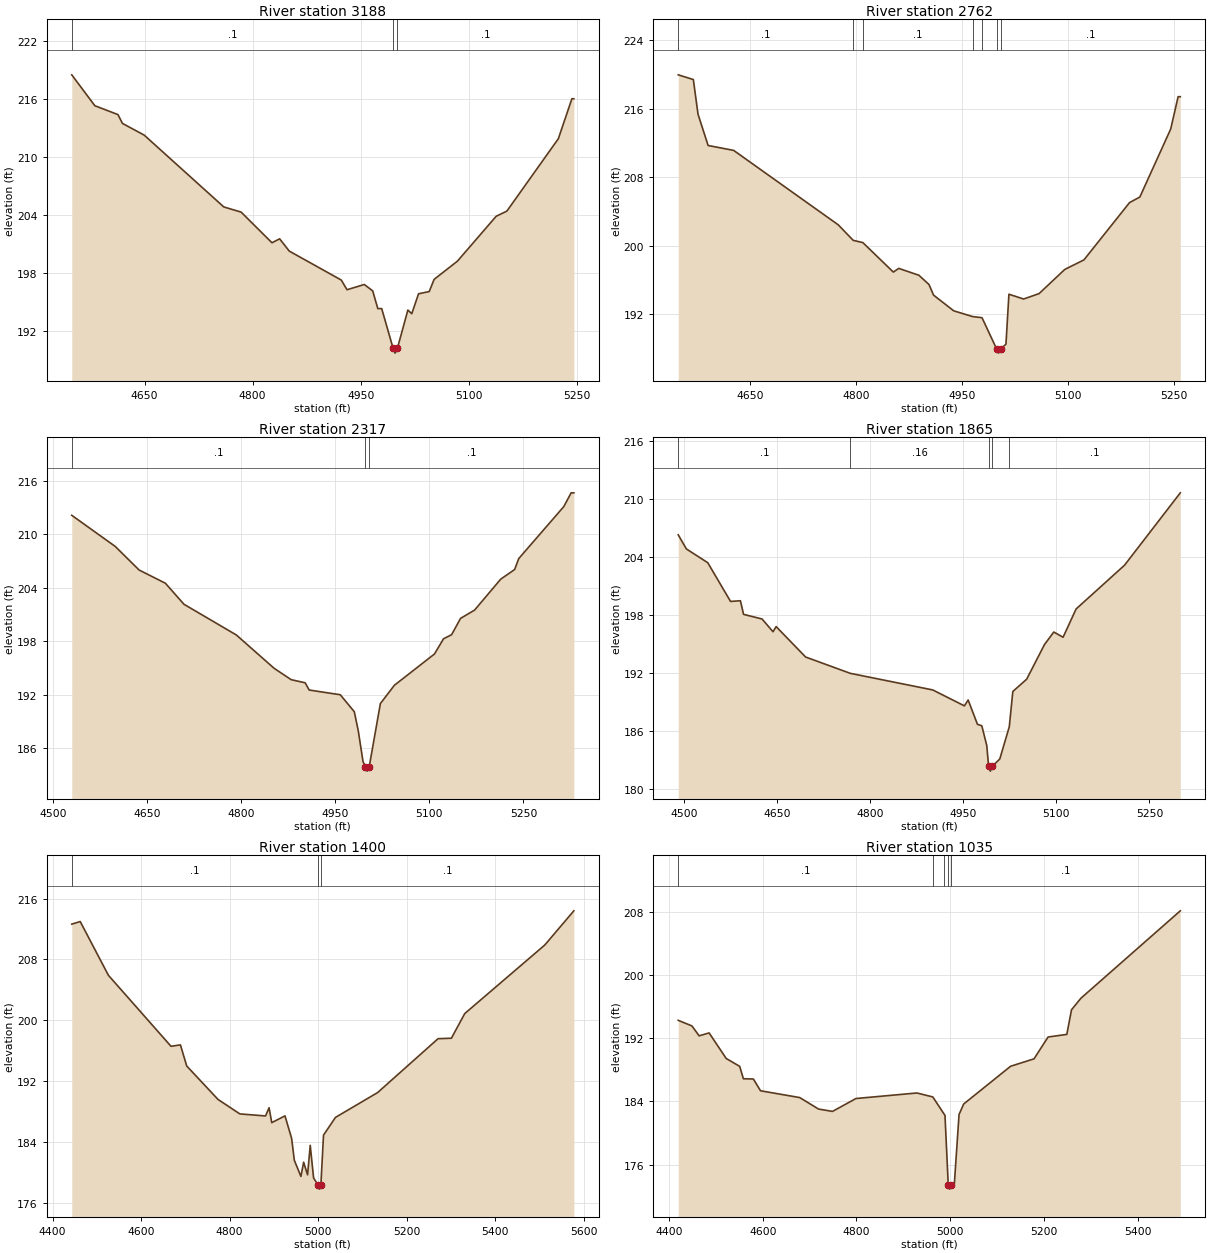
Type RM Length L Ch R = 1,3188,426,426,426
BEGIN DESCRIPTION:
UNT006 IN PECR 7.0
END DESCRIPTION:
XS GIS Cut Line= 3
      2280087.70     13251696.85      2279687.72     13251546.85
      2279437.76     13251446.87
#Sta/Elev= 30
  4549.1  218.48  4581.1  215.29  4613.2  214.37  4619.4  213.46  4649.6  212.25
  4760.0  204.83  4784.0  204.30  4826.8  201.13  4837.4  201.54  4850.8  200.27
  4922.9  197.28  4930.9  196.28  4954.9  196.82  4966.5  196.16  4973.6  194.33
  4979.0  194.33  4994.8  190.23  4997.6  189.73  5000.8  190.23  5015.3  194.18
  5020.7  193.80  5030.1  195.86  5044.9  196.09  5051.7  197.35  5084.0  199.23
  5137.8  203.87  5152.6  204.40  5224.0  211.88  5242.8  216.01  5245.5  216.01
#Mann=3,-1,0
  4549.1     0.1       0  4994.8    0.07       0  5000.8     0.1       0
Bank Sta=4994.8,5000.8
Exp/Cntr=0.3,0.1

Type RM Length L Ch R = 1,2762,445,445,445
BEGIN DESCRIPTION:
UNT006 IN PECR 6.0
END DESCRIPTION:
XS GIS Cut Line= 3
      2280137.72     13251496.86      2279837.72     13251146.85
      2279637.70     13250996.84
#Sta/Elev= 30
  4547.9  219.93  4569.3  219.38  4575.9  215.35  4590.2  211.69  4626.4  211.12
  4774.5  202.44  4795.7  200.63  4809.3  200.37  4852.5  196.93  4860.2  197.36
  4888.7  196.56  4903.0  195.48  4909.5  194.24  4938.1  192.41  4964.9  191.74
  4978.1  191.61  4998.7  187.98  5001.5  187.48  5004.7  187.98  5012.0  188.52
  5016.2  194.35  5037.0  193.79  5058.9  194.42  5095.3  197.24  5122.4  198.35
  5187.0  205.03  5201.6  205.68  5245.3  213.61  5255.8  217.38  5258.9  217.38
#Mann=7,-1,0
  4547.9     0.1       0  4795.7    0.16       0  4809.3     0.1       0
  4964.9    0.16       0  4978.1     0.1       0  4998.7    0.07       0
  5004.7     0.1       0
Bank Sta=4998.7,5004.7
Exp/Cntr=0.3,0.1

Type RM Length L Ch R = 1,2317,452,452,452
BEGIN DESCRIPTION:
UNT006 IN PECR 5.0
END DESCRIPTION:
XS GIS Cut Line= 3
      2280384.53     13251129.00      2280236.88     13250914.91
      2279816.00     13250575.25
#Sta/Elev= 30
  4529.5  212.10  4598.9  208.61  4636.9  205.97  4678.8  204.49  4708.5  202.13
  4792.0  198.69  4852.2  194.96  4879.5  193.68  4901.8  193.33  4908.2  192.52
  4957.8  191.99  4980.2  190.09  4986.6  187.92  4994.1  184.50  4998.0  183.93
  5000.7  183.43  5004.0  183.93  5021.8  191.00  5044.1  193.05  5108.1  196.56
  5122.5  198.26  5135.4  198.72  5149.7  200.55  5172.1  201.48  5213.7  204.94
  5236.0  206.03  5242.5  207.25  5314.4  213.08  5326.1  214.62  5330.4  214.62
#Mann=3,-1,0
  4529.5     0.1       0  4998.0    0.07       0  5004.0     0.1       0
Bank Sta=4998,5004
Exp/Cntr=0.3,0.1

Type RM Length L Ch R = 1,1865,465,465,465
BEGIN DESCRIPTION:
UNT006 IN PECR 4.0
END DESCRIPTION:
XS GIS Cut Line= 3
      2280591.30     13250929.69      2280546.99     13250693.40
      2280229.84     13250221.35
#Sta/Elev= 30
  4490.6  206.29  4503.7  204.83  4538.2  203.40  4574.9  199.39  4590.8  199.46
  4595.9  198.05  4625.7  197.57  4643.3  196.25  4648.4  196.78  4695.9  193.63
  4767.9  191.94  4900.8  190.22  4951.8  188.57  4957.8  189.18  4972.8  186.66
  4979.8  186.51  4987.8  184.46  4990.8  182.31  4993.6  181.81  4996.8  182.31
  5008.8  183.07  5024.1  186.41  5029.8  190.06  5052.1  191.33  5080.8  194.92
  5095.8  196.22  5110.8  195.68  5131.8  198.61  5209.8  203.14  5299.7  210.64
#Mann=5,-1,0
  4490.6     0.1       0  4767.9    0.16       0  4990.8    0.07       0
  4996.8    0.16       0  5024.1     0.1       0
Bank Sta=4990.8,4996.8
Exp/Cntr=0.3,0.1

Type RM Length L Ch R = 1,1400,365,365,365
BEGIN DESCRIPTION:
UNT006 IN PECR 3.0
END DESCRIPTION:
XS GIS Cut Line= 4
      2281204.17     13250597.44      2280960.48     13250346.37
      2280598.68     13250102.70      2280252.22     13250073.22
#Sta/Elev= 30
  4443.5  212.64  4462.6  212.98  4526.3  205.91  4667.6  196.58  4688.9  196.76
  4703.1  193.99  4773.8  189.59  4823.1  187.69  4881.1  187.42  4889.1  188.50
  4895.1  186.54  4925.0  187.43  4940.0  184.47  4946.1  181.59  4961.0  179.47
  4967.1  181.34  4976.0  179.68  4982.0  183.56  4989.6  179.27  5000.0  178.30
  5002.8  177.80  5006.0  178.30  5012.0  184.90  5039.0  187.23  5134.3  190.50
  5270.7  197.58  5300.8  197.64  5330.9  200.88  5511.6  209.89  5577.3  214.39
#Mann=3,-1,0
  4443.5     0.1       0  5000.0    0.07       0  5006.0     0.1       0
Bank Sta=5000,5006
Exp/Cntr=0.3,0.1

Type RM Length L Ch R = 1,1035,350,350,350
BEGIN DESCRIPTION:
UNT006 IN PECR 2.0
END DESCRIPTION:
XS GIS Cut Line= 3
      2281359.22     13250036.27      2281145.07     13249903.35
      2280325.52     13249881.20
#Sta/Elev= 30
  4419.5  194.25  4448.8  193.54  4464.1  192.29  4485.4  192.66  4522.0  189.42
  4550.7  188.43  4558.6  186.86  4579.9  186.83  4595.2  185.34  4678.9  184.48
  4718.9  183.03  4748.9  182.73  4798.9  184.36  4929.0  185.06  4963.0  184.56
  4987.7  182.34  4989.0  182.22  4996.0  173.40  4998.8  172.90  5002.0  173.40
  5009.0  173.57  5019.0  182.34  5029.0  183.67  5129.1  188.44  5179.1  189.38
  5209.1  192.14  5249.1  192.47  5259.1  195.58  5279.1  197.04  5491.4  208.10
#Mann=5,-1,0
  4419.5     0.1       0  4963.0    0.16       0  4987.7     0.1       0
  4996.0    0.07       0  5002.0     0.1       0
Bank Sta=4996,5002
Exp/Cntr=0.3,0.1

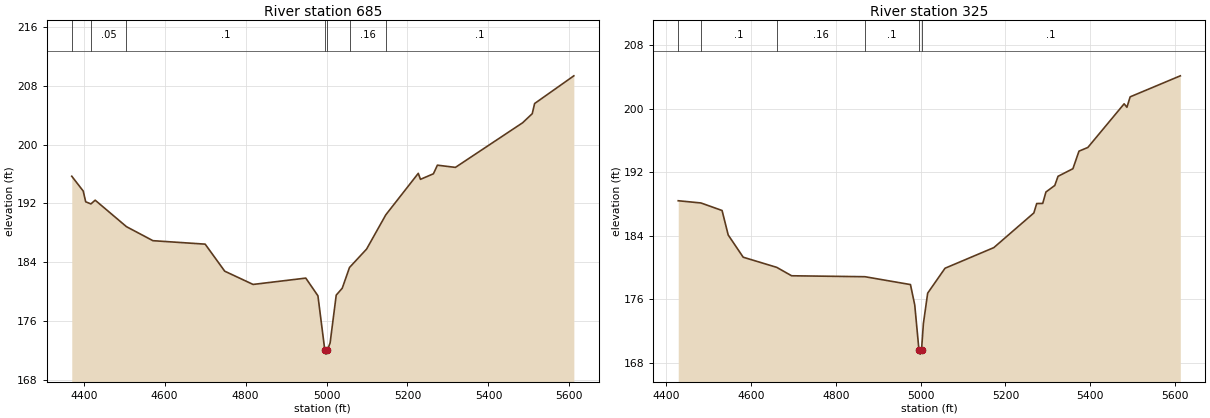
Type RM Length L Ch R = 1,685,360,360,360
BEGIN DESCRIPTION:
Mapping XS 5c5ae9fe
END DESCRIPTION:
XS GIS Cut Line= 4
      2281325.51     13249758.41      2281059.24     13249569.80
      2280554.49     13249542.07      2280178.56     13249702.39
#Sta/Elev= 30
  4370.5  195.70  4398.8  193.69  4404.9  192.23  4417.8  191.94  4428.3  192.45
  4505.7  188.85  4571.1  186.95  4700.1  186.48  4748.4  182.81  4818.5  181.01
  4948.7  181.87  4978.7  179.47  4995.8  172.05  4998.5  171.55  5001.8  172.05
  5008.8  173.07  5023.9  179.56  5038.8  180.50  5056.7  183.31  5098.9  185.81
  5146.4  190.46  5226.6  196.09  5232.1  195.28  5264.0  196.03  5273.9  197.20
  5318.4  196.90  5484.5  202.96  5508.2  204.19  5514.1  205.57  5611.0  209.33
#Mann=7,-1,0
  4370.5     0.1       0  4417.8    0.05       0  4505.7     0.1       0
  4995.8    0.07       0  5001.8     0.1       0  5056.7    0.16       0
  5146.4     0.1       0
Bank Sta=4995.8,5001.8
Exp/Cntr=0.3,0.1

Type RM Length L Ch R = 1,325,0,0,0
BEGIN DESCRIPTION:
UNT006 IN PECR 1.0
END DESCRIPTION:
XS GIS Cut Line= 4
      2281197.91     13249530.98      2280970.49     13249237.00
      2280604.41     13249170.43      2280316.54     13249502.58
#Sta/Elev= 30
  4428.9  188.41  4482.4  188.13  4532.2  187.18  4546.7  184.09  4582.0  181.29
  4661.1  180.01  4696.1  178.95  4869.0  178.83  4976.2  177.84  4986.3  175.27
  4996.3  169.57  4999.1  169.07  5002.3  169.57  5006.7  172.93  5016.8  176.76
  5057.7  179.90  5172.7  182.50  5267.0  186.87  5273.8  188.06  5287.9  188.07
  5295.5  189.51  5316.4  190.34  5324.0  191.49  5359.1  192.45  5373.4  194.66
  5394.3  195.13  5479.8  200.63  5486.4  200.20  5494.0  201.51  5612.2  204.16
#Mann=6,-1,0
  4428.9    0.05       0  4482.4     0.1       0  4661.1    0.16       0
  4869.0     0.1       0  4996.3    0.07       0  5002.3     0.1       0
Bank Sta=4996.3,5002.3
Exp/Cntr=0.3,0.1

Chan Stop Cuts=-1