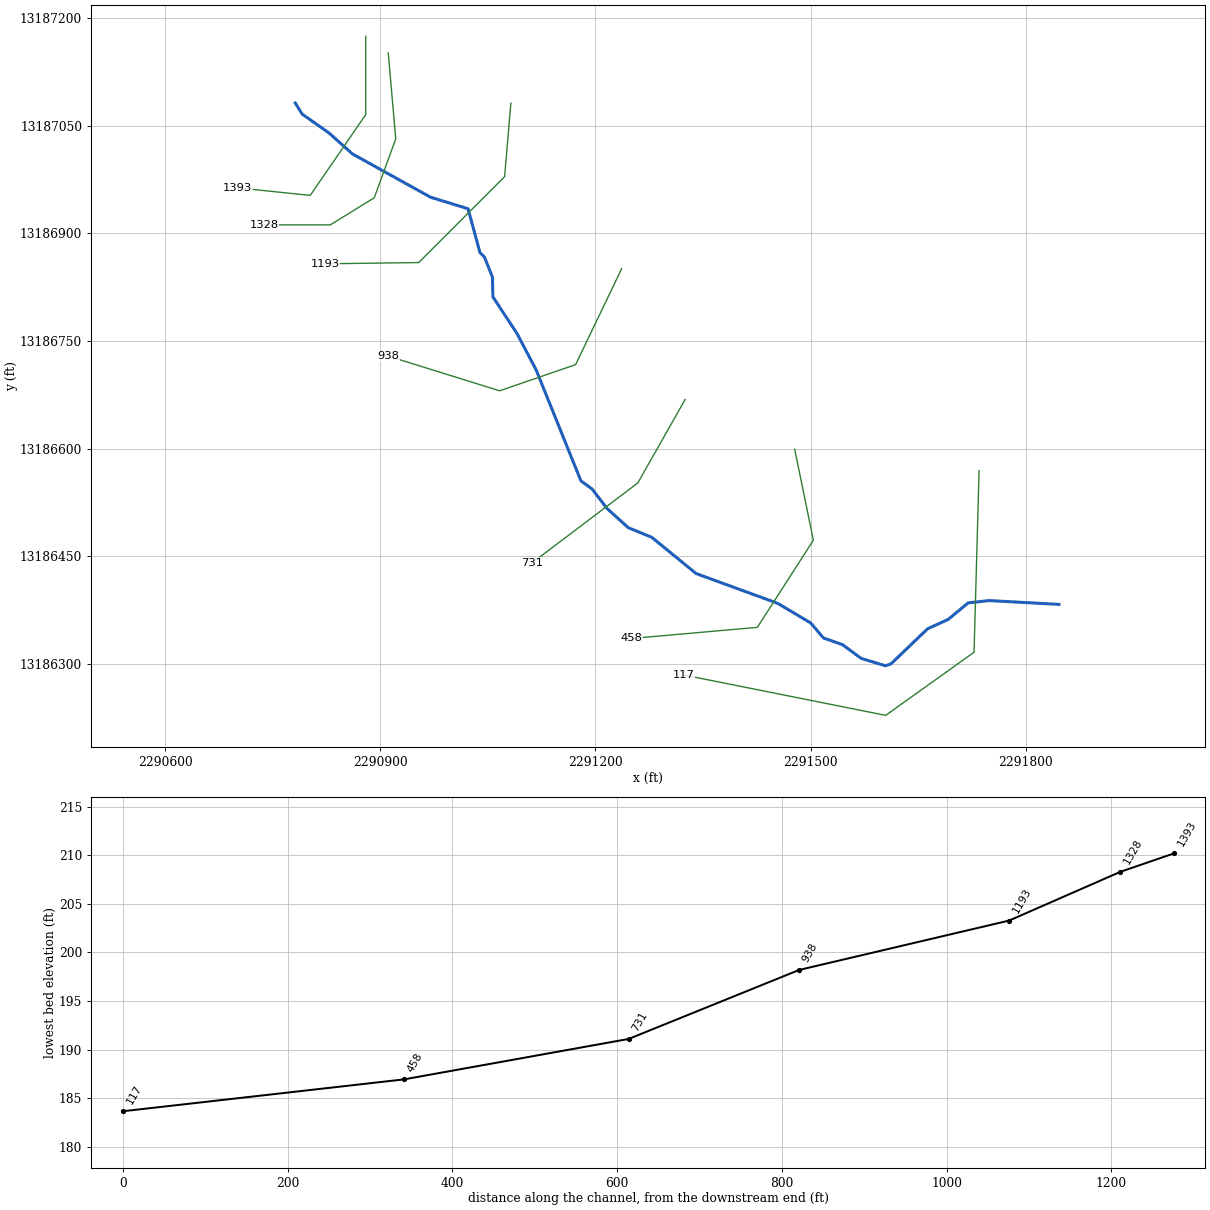
--- UNT305 IN PECR.prj (project) ---

Proj Title=UNT305 IN PECR Base Level Engineering
Current Plan=p01
Default Exp/Contr=0.3,0.1
English Units
Geom File=g01
Flow File=f01
Plan File=p01
Y Axis Title=Elevation
X Axis Title(PF)=Main Channel Distance
X Axis Title(XS)=Station
BEGIN DESCRIPTION:
UNT305 IN PECR
END DESCRIPTION:
DSS Export Rating Curves= 0
DSS Export Rating Curve Sorted= 0
DSS Export Volume Flow Curves= 0
DXF OffsetX= 0
DXF OffsetY= 0
DXF ScaleX= 1
DXF ScaleY= 10

--- UNT305 IN PECR.p01 (plan) ---

Plan Title=Multiple Run
Short Identifier=Multiple
Geom File=g01
Flow File=f01
Subcritical Flow
K Sum by GR= 0
Std Step Tol= 0.01
Critical Tol= 0.01
Num of Std Step Trials= 20
Max Error Tol= 0.3
Flow Tol Ratio= 0.001
Split Flow NTrial= 30
Split Flow Tol= 0.02
Split Flow Ratio= 0.02
Log Output Level= 0
Friction Slope Method= 1
Unsteady Friction Slope Method= 2
Unsteady Bridges Friction Slope Method= 1
Parabolic Critical Depth
Global Vel Dist=  1 , 1 , 1
Global Log Level= 0
CheckData=True
Encroach Param= -1, 0, 0, 0
BEGIN DESCRIPTION:
Multiple Run
END DESCRIPTION:

--- UNT305 IN PECR.f01 (steady flow) ---

Flow Title=Multiple
Number of Profiles=7
Profile Names=10-year,25-year,50-year,1pct_min,100-year,1pct_plu,500-year
River Rch & RM= UNT305 IN PECR,Reach-1,1393
      63      79      92      78     106     144     144
Boundary for River Rch & Prof#=UNT305 IN PECR,Reach-1,1
Up Type=0
Dn Type=3
Dn Slope=0.005
Boundary for River Rch & Prof#=UNT305 IN PECR,Reach-1,2
Up Type=0
Dn Type=3
Dn Slope=0.005
Boundary for River Rch & Prof#=UNT305 IN PECR,Reach-1,3
Up Type=0
Dn Type=3
Dn Slope=0.005
Boundary for River Rch & Prof#=UNT305 IN PECR,Reach-1,4
Up Type=0
Dn Type=3
Dn Slope=0.005
Boundary for River Rch & Prof#=UNT305 IN PECR,Reach-1,5
Up Type=0
Dn Type=3
Dn Slope=0.005
Boundary for River Rch & Prof#=UNT305 IN PECR,Reach-1,6
Up Type=0
Dn Type=3
Dn Slope=0.005
Boundary for River Rch & Prof#=UNT305 IN PECR,Reach-1,7
Up Type=0
Dn Type=3
Dn Slope=0.005

--- UNT305 IN PECR.g01 (geometry) ---

Geom Title=Existing Conditions
Program Version=4.10

River Reach=UNT305 IN PECR  ,Reach-1
Reach XY= 30
      2290781.61     13187081.66      2290791.16     13187066.26
      2290828.66     13187039.87       2290861.3      13187010.7
      2290970.33     13186950.28      2291022.41     13186934.31
      2291039.08      13186873.2      2291045.33     13186866.95
      2291056.44     13186839.17      2291057.13     13186811.39
      2291090.46      13186760.7      2291117.35      13186709.7
      2291179.79     13186554.94      2291195.41     13186543.49
      2291216.25      13186516.4      2291245.73     13186489.69
      2291278.55     13186476.24      2291340.42     13186425.67
      2291453.93     13186384.25       2291500.2     13186356.81
      2291517.95     13186335.83      2291544.31     13186326.68
      2291570.68     13186307.31      2291604.57     13186297.09
       2291612.1     13186299.78      2291663.21     13186348.74
      2291691.72     13186361.65       2291719.7     13186384.78
      2291748.75     13186388.01      2291846.31      13186382.7

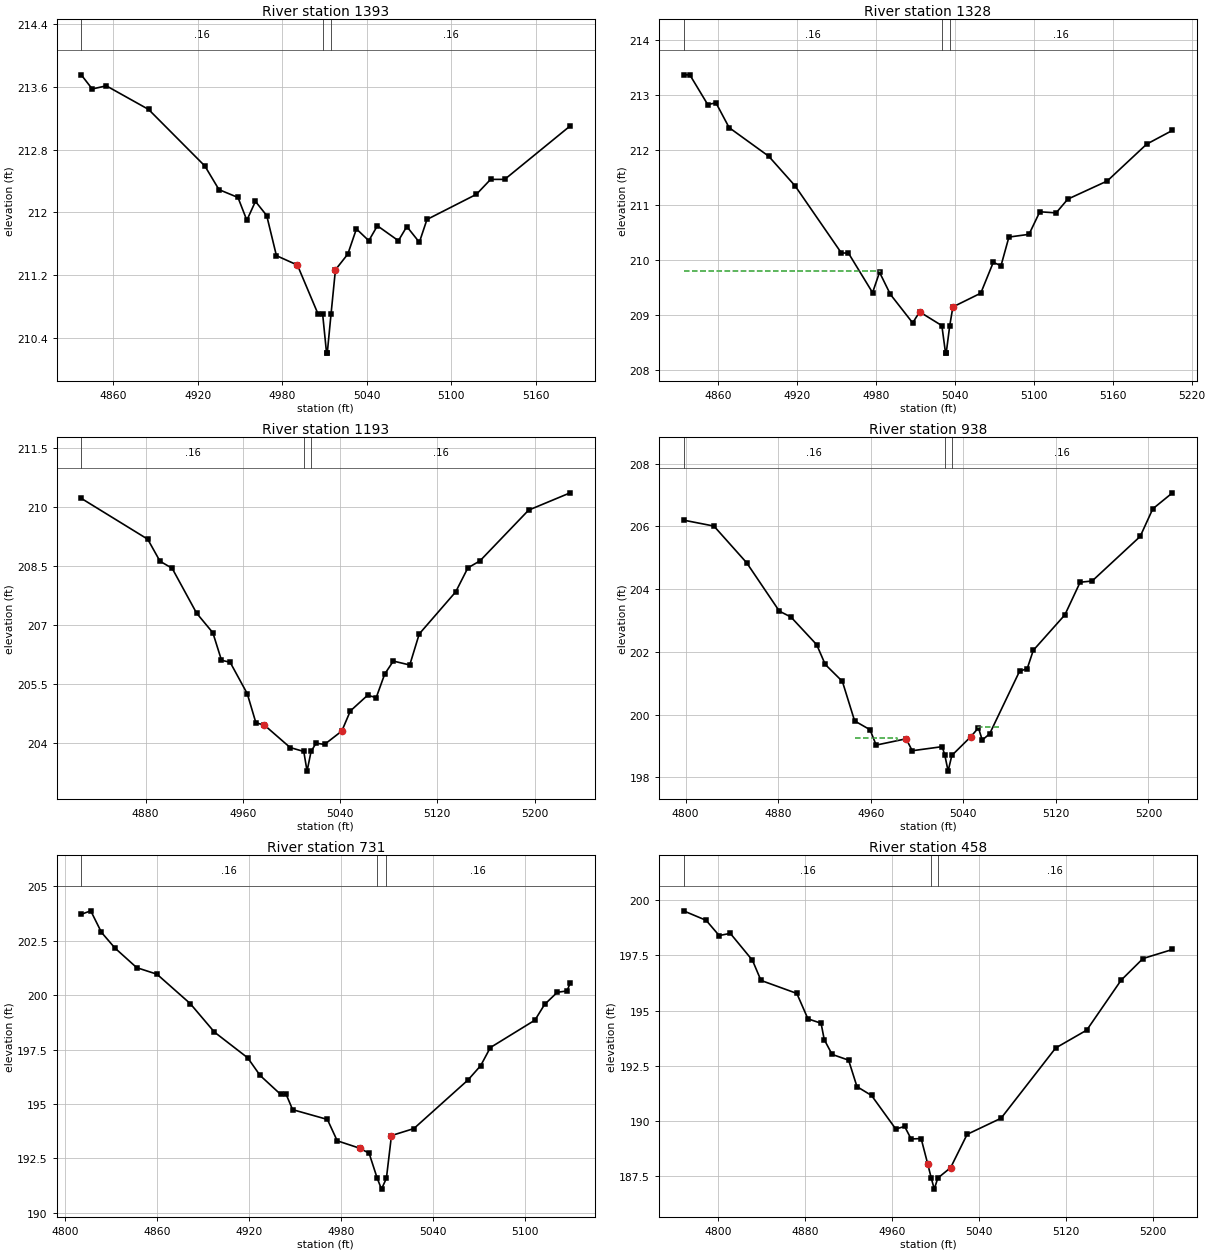
Type RM Length L Ch R = 1 ,1393    ,65,65,65
BEGIN DESCRIPTION:
UNT305 IN PECR 2.0
END DESCRIPTION:
XS GIS Cut Line= 4
      2290879.83     13187174.61      2290879.83      13187065.5
      2290802.42      13186952.9      2290701.52     13186963.34
#Sta/Elev= 30
  4837.2  213.75    4845  213.57    4855  213.61    4885  213.31    4925  212.59
    4935  212.29  4948.5  212.19  4954.8   211.9  4960.9  212.14  4968.9  211.96
  4975.8  211.45  4990.7  211.33  5005.3  210.71  5008.6  210.71  5011.4  210.21
  5011.9  210.21  5014.6  210.71  5017.7  211.27  5026.5  211.47  5032.6  211.79
  5041.4  211.64  5047.5  211.83  5062.4  211.64  5068.4  211.82  5077.3  211.62
  5082.7  211.91  5117.8  212.23  5127.9  212.42  5137.9  212.42  5184.4   213.1
#Mann= 3 ,-1 , 0
  4837.2     .16       0  5008.6     .07       0  5014.6     .16       0
Bank Sta=4990.7,5017.7
XS Rating Curve= 0 ,0
Exp/Cntr=0.3,0.1

Type RM Length L Ch R = 1 ,1328    ,135,135,135
XS GIS Cut Line= 5
      2290911.23     13187151.41      2290921.64     13187031.62
      2290891.69     13186949.59       2290830.5     13186911.83
      2290738.08     13186911.83
#Sta/Elev= 30
  4833.4  213.37  4838.2  213.37  4851.8  212.83  4858.1  212.86  4868.1  212.41
  4898.2  211.89  4918.3  211.35  4953.5  210.13  4958.8  210.13  4977.2  209.41
  4982.5  209.78  4990.7  209.38  5007.7  208.86    5013  209.06  5029.9  208.81
  5032.7  208.31  5033.2  208.31  5035.9  208.81  5038.3  209.15  5059.5   209.4
    5069  209.96  5074.9   209.9  5080.9  210.42  5096.2  210.47  5104.4  210.88
  5116.8  210.86  5125.7  211.11  5155.7  211.44  5185.7  212.11  5205.3  212.36
#Mann= 3 ,-1 , 0
  4833.4     .16       0  5029.9     .07       0  5035.9     .16       0
#XS Ineff= 2 , 0
       0 4982.51   209.8               0
Permanent Ineff=
       T       F
Bank Sta=5013,5038.3
XS Rating Curve= 0 ,0
Exp/Cntr=0.3,0.1

Type RM Length L Ch R = 1 ,1193    ,255,255,255
BEGIN DESCRIPTION:
Mapping XS 171c0727
END DESCRIPTION:
XS GIS Cut Line= 4
      2291082.11     13187081.39      2291073.43     13186979.02
      2290953.66     13186859.26      2290823.49     13186857.52
#Sta/Elev= 30
    4827  210.23  4881.7  209.19  4891.8  208.63  4901.8  208.45  4921.9  207.31
  4935.3  206.81  4942.4  206.11  4949.5  206.06  4963.6  205.26  4970.7  204.52
  4977.7  204.46  4998.9  203.89  5010.1  203.79  5012.8  203.29  5016.1  203.79
  5020.2     204  5027.2  203.97  5041.4  204.31  5048.4  204.82  5062.6  205.22
  5069.7  205.16  5076.7  205.76  5083.8  206.09  5097.3  205.99  5105.1  206.78
  5135.1  207.85  5145.1  208.46  5155.1  208.64  5195.1  209.93  5229.3  210.37
#Mann= 3 ,-1 , 0
    4827     .16       0  5010.1     .07       0  5016.1     .16       0
Bank Sta=4977.7,5041.4
XS Rating Curve= 0 ,0
Exp/Cntr=0.3,0.1

Type RM Length L Ch R = 1 ,938     ,207,207,207
BEGIN DESCRIPTION:
Mapping XS 678d8f92
END DESCRIPTION:
XS GIS Cut Line= 4
       2291236.6      13186850.6      2291172.37     13186716.93
      2291066.49     13186680.48      2290911.49      13186728.7
#Sta/Elev= 30
  4798.2   206.2  4824.5  206.01  4852.8  204.84    4881   203.3  4891.1  203.11
  4913.3  202.23  4920.7   201.6  4935.5  201.06  4946.1   199.8  4959.4  199.52
  4964.7  199.03  4990.6  199.23  4995.9  198.85  5021.8  198.98  5024.1   198.7
  5026.9   198.2  5030.1   198.7  5046.6   199.3  5053.1  199.58  5056.4  199.19
  5062.8  199.39  5088.6  201.38  5095.3  201.47  5100.5  202.05  5127.8  203.18
    5141  204.22  5151.4  204.26  5192.9  205.68  5203.8  206.56  5220.8  207.07
#Mann= 3 ,-1 , 0
  4798.2     .16       0  5024.1     .07       0  5030.1     .16       0
#XS Ineff= 2 ,-1
 4946.54 4983.02  199.24 5052.83 5072.96  199.62
Permanent Ineff=
       T       T
Bank Sta=4990.6,5046.6
XS Rating Curve= 0 ,0
Exp/Cntr=0.3,0.1

Type RM Length L Ch R = 1 ,731     ,273,273,273
BEGIN DESCRIPTION:
Mapping XS a560a01e
END DESCRIPTION:
XS GIS Cut Line= 3
      2291325.12     13186668.34      2291259.15     13186552.04
      2291111.33     13186440.31
#Sta/Elev= 30
  4810.4  203.71  4816.6  203.87  4823.6  202.88  4832.4  202.16  4846.6  201.26
  4859.8  200.96  4881.5  199.61  4897.3   198.3    4919  197.12  4927.1  196.31
  4940.5  195.44  4944.1  195.44  4948.3  194.74    4971  194.29  4977.4  193.31
    4992  192.97  4998.2  192.74  5003.5  191.59  5006.3  191.09  5009.5  191.59
  5012.8  193.55  5027.4  193.87  5062.7   196.1    5071  196.76  5077.3  197.59
  5106.4  198.85  5112.7  199.57    5121  200.13  5127.3  200.19  5129.4  200.55
#Mann= 3 ,-1 , 0
  4810.4     .16       0  5003.5     .07       0  5009.5     .16       0
Bank Sta=4992,5012.8
XS Rating Curve= 0 ,0
Exp/Cntr=0.3,0.1

Type RM Length L Ch R = 1 ,458     ,341,341,341
BEGIN DESCRIPTION:
Mapping XS a7059e9a
END DESCRIPTION:
XS GIS Cut Line= 4
      2291477.84     13186598.94      2291503.89     13186472.19
      2291425.78     13186350.69       2291250.7     13186335.24
#Sta/Elev= 30
  4768.2  199.52    4789  199.09    4801   198.4  4811.2   198.5  4831.6  197.28
  4839.4  196.37  4872.4  195.78  4882.6  194.63  4894.7  194.43  4897.6  193.69
  4904.8  193.02    4920  192.76  4927.7  191.56  4941.1  191.16  4963.4  189.64
  4971.5  189.76  4977.5  189.19  4986.7  189.21  4992.7  188.07    4996  187.42
  4998.8  186.92    5002  187.42  5013.8  187.89    5029   189.4  5060.2  190.13
  5110.4  193.31    5139  194.12  5170.6  196.38  5190.7  197.36  5217.8  197.77
#Mann= 3 ,-1 , 0
  4768.2     .16       0    4996     .07       0    5002     .16       0
Bank Sta=4992.7,5013.8
XS Rating Curve= 0 ,0
Exp/Cntr=0.3,0.1

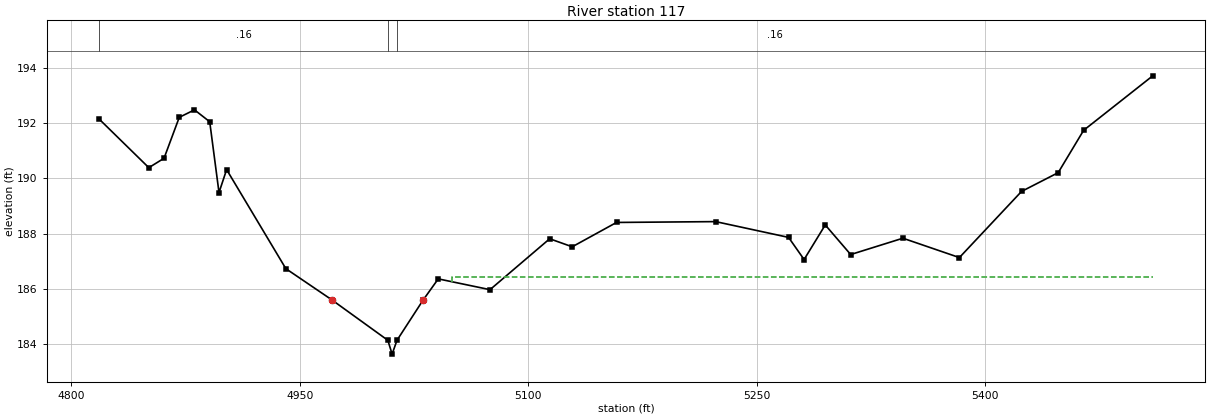
Type RM Length L Ch R = 1 ,117     ,0,0,0
BEGIN DESCRIPTION:
UNT305 IN PECR 1.0
END DESCRIPTION:
XS GIS Cut Line= 4
      2291734.93     13186569.33      2291727.89     13186315.97
      2291604.73       13186228.      2291323.21      13186284.3
#Sta/Elev= 30
  4818.3  192.13  4850.8  190.38  4860.8  190.72  4870.8   192.2  4880.8  192.47
  4890.8  192.04  4896.9  189.48  4901.9  190.31  4940.8  186.73  4970.8  185.61
  5007.8  184.14  5010.6  183.64  5013.8  184.14  5030.9  185.59  5040.9  186.36
  5074.9  185.97  5114.1  187.81  5128.9  187.52    5158   188.4  5223.1  188.43
    5271  187.86  5281.2  187.06  5295.1  188.31  5311.8  187.24  5346.1  187.83
  5383.2  187.13    5424  189.52  5448.1   190.2  5464.8  191.73  5510.2   193.7
#Mann= 3 ,-1 , 0
  4818.3     .16       0  5007.8     .07       0  5013.8     .16       0
#XS Ineff= 2 , 0
       0                  5049.9       0  186.44
Permanent Ineff=
       F       T
Bank Sta=4970.8,5030.9
XS Rating Curve= 0 ,0
Exp/Cntr=0.3,0.1

Chan Stop Cuts=-1
Use User Specified Reach Order=0
Composite Channel Slope=5