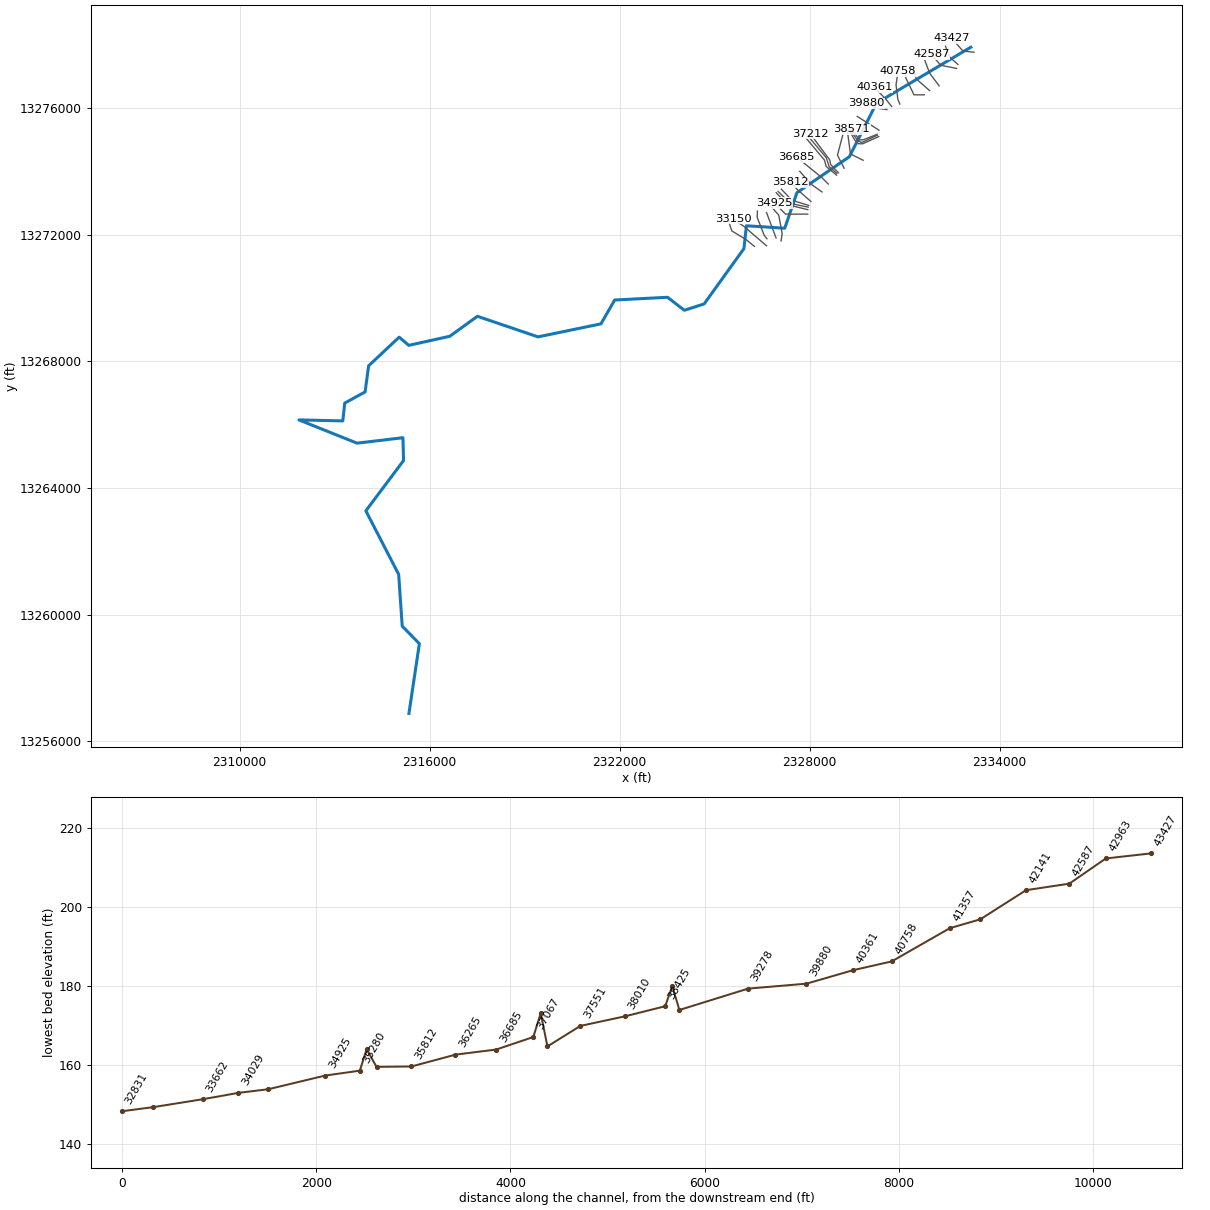
--- UNT008 IN PECR.prj (project) ---

Proj Title=UNT008 IN PECR Base Level Engineering
Current Plan=p01
Default Exp/Contr=0.3,0.1
English Units
Geom File=g01
Flow File=f01
Plan File=p01
Y Axis Title=Elevation
X Axis Title(PF)=Main Channel Distance
X Axis Title(XS)=Station
BEGIN DESCRIPTION:
UNT008 IN PECR
END DESCRIPTION:
DSS Export Rating Curves= 0
DSS Export Rating Curve Sorted= 0
DSS Export Volume Flow Curves= 0
DXF OffsetX= 0
DXF OffsetY= 0
DXF ScaleX= 1
DXF ScaleY= 10

--- UNT008 IN PECR.p01 (plan) ---

Plan Title=Multiple Run
Short Identifier=Multiple
Geom File=g01
Flow File=f01
Subcritical Flow
K Sum by GR= 0
Std Step Tol= 0.01
Critical Tol= 0.01
Num of Std Step Trials= 20
Max Error Tol= 0.3
Flow Tol Ratio= 0.001
Split Flow NTrial= 30
Split Flow Tol= 0.02
Split Flow Ratio= 0.02
Log Output Level= 0
Friction Slope Method= 1
Unsteady Friction Slope Method= 2
Unsteady Bridges Friction Slope Method= 1
Parabolic Critical Depth
Global Vel Dist=  1 , 1 , 1
Global Log Level= 0
CheckData=True
Encroach Param= -1, 0, 0, 0
BEGIN DESCRIPTION:
Multiple Run
END DESCRIPTION:

--- UNT008 IN PECR.f01 (steady flow) ---

Flow Title=Multiple
Program Version=4.10
Number of Profiles= 7
Profile Names=10-year,25-year,50-year,1pct_min,100-year,1pct_plu,500-year
River Rch & RM=UNT008 IN PECR,Reach-1         ,43427
     433     585     707     623     842    1139    1200
River Rch & RM=UNT008 IN PECR,Reach-1         ,42963
     697     977    1209    1090    1474    1994    2202
River Rch & RM=UNT008 IN PECR,Reach-1         ,37212
     957    1364    1707    1556    2104    2846    3212
River Rch & RM=UNT008 IN PECR,Reach-1         ,34338
    1484    2161    2742    2530    3422    4627    5356
River Rch & RM=UNT008 IN PECR,Reach-1         ,26606
    2091    3090    3961    3689    4989    6747    7955
River Rch & RM=UNT008 IN PECR,Reach-1         ,25239
    2108    3115    3994    3720    5031    6804    8025
River Rch & RM=UNT008 IN PECR,Reach-1         ,22875
    2145    3170    4064    3785    5119    6922    8162
Boundary for River Rch & Prof#=UNT008 IN PECR,Reach-1         , 1
Up Type= 0
Dn Type= 3
Dn Slope=0.0013
Boundary for River Rch & Prof#=UNT008 IN PECR,Reach-1         , 2
Up Type= 0
Dn Type= 3
Dn Slope=0.0013
Boundary for River Rch & Prof#=UNT008 IN PECR,Reach-1         , 3
Up Type= 0
Dn Type= 3
Dn Slope=0.0013
Boundary for River Rch & Prof#=UNT008 IN PECR,Reach-1         , 4
Up Type= 0
Dn Type= 3
Dn Slope=0.0013
Boundary for River Rch & Prof#=UNT008 IN PECR,Reach-1         , 5
Up Type= 0
Dn Type= 3
Dn Slope=0.0013
Boundary for River Rch & Prof#=UNT008 IN PECR,Reach-1         , 6
Up Type= 0
Dn Type= 3
Dn Slope=0.0013
Boundary for River Rch & Prof#=UNT008 IN PECR,Reach-1         , 7
Up Type= 0
Dn Type= 3
Dn Slope=0.0013
DSS Import GetInterval= 0
DSS Import GetPeak= 0
DSS Import FillOption= 0

--- UNT008 IN PECR.g01 (geometry) ---

Geom Title=Existing Conditions
Program Version=4.10

River Reach=UNT008 IN PECR  ,Reach-1
Reach XY= 30
      2333087.72     13277916.86       2330110.7     13276150.38
      2329252.71     13274458.25      2327597.54     13273323.49
      2327213.47     13272201.05      2326002.85     13272279.37
      2325924.14      13271558.3      2324667.45     13269810.51
      2324042.71     13269611.03      2323511.55     13270021.02
      2321843.16     13269934.48      2321410.21      13269182.2
      2319422.82     13268771.08      2317508.67     13269420.78
       2316637.1     13268790.01      2315341.67     13268503.55
      2315038.76     13268762.47      2314074.36     13267857.07
      2313963.27     13267032.35      2313320.91     13266680.78
      2313257.98     13266117.73       2311873.3     13266149.83
      2313708.41     13265415.12      2315157.72     13265586.85
      2315177.72     13264866.85      2313986.93     13263278.12
       2315023.7     13261271.55      2315134.82     13259639.61
      2315676.48     13259084.05      2315347.72     13256883.46

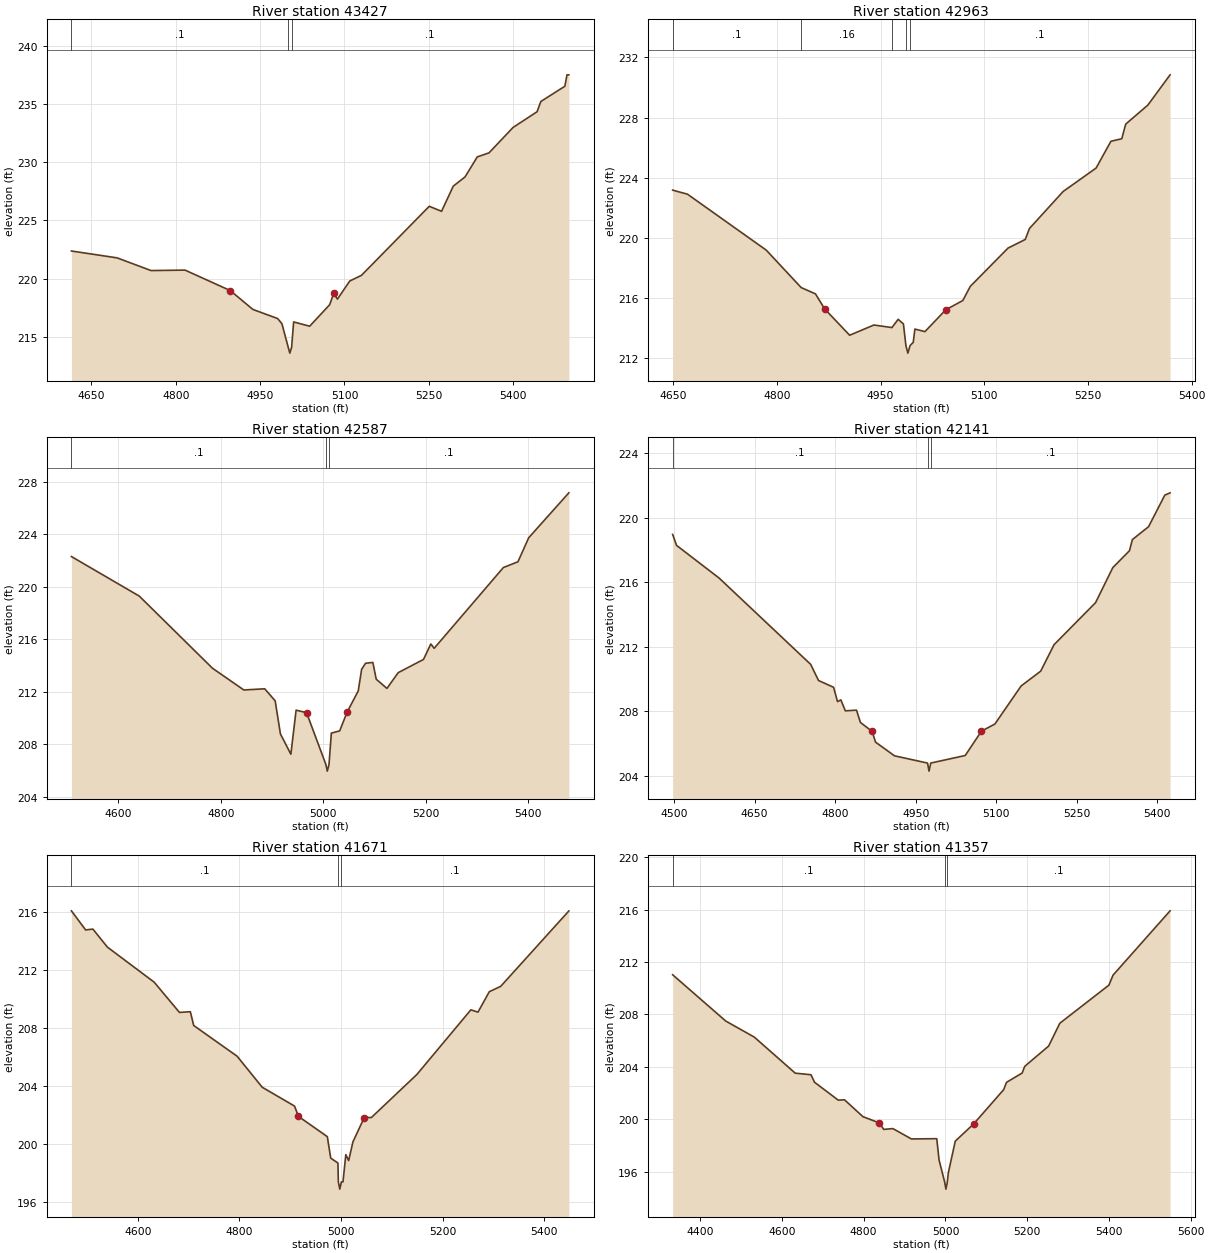
Type RM Length L Ch R = 1 ,43427   ,464,464,464
BEGIN DESCRIPTION:
UNT008 IN PECR 65.0
END DESCRIPTION:
XS GIS Cut Line= 3
      2333188.48     13277757.88      2332837.72     13277796.85
      2332487.73     13278196.84
#Sta/Elev= 30
  4614.5  222.38  4695.8  221.79  4756.1   220.7  4816.5  220.74    4897  218.98
  4937.2  217.36  4981.2  216.58  4988.8  216.13    5000  214.11  5002.8  213.61
    5006  214.11  5009.6  216.29  5038.1  215.92  5073.7  217.77  5080.8  218.74
  5087.5  218.25  5109.3   219.8  5130.2  220.29  5250.7  226.22  5272.6  225.79
  5293.4  227.95  5314.3  228.74  5336.1  230.46    5357  230.81  5399.7  232.99
  5442.4  234.34  5449.1  235.22  5491.8  236.53  5495.6  237.51  5498.9  237.51
#Mann= 3 ,-1 , 0
  4614.5      .1       0    5000     .07       0    5006      .1       0
Bank Sta=4897,5080.8
XS Rating Curve= 0 ,0
Exp/Cntr=0.3,0.1

Type RM Length L Ch R = 1 ,42963   ,376,376,376
BEGIN DESCRIPTION:
UNT008 IN PECR 64.0
END DESCRIPTION:
XS GIS Cut Line= 3
      2332683.39     13277371.66      2332419.21     13277602.31
      2332287.72     13277946.87
#Sta/Elev= 30
  4649.3  223.17  4670.8   222.9  4784.7  219.18  4835.2  216.69  4855.9  216.27
  4869.2  215.27  4905.3  213.52  4940.4   214.2  4966.5  214.03  4975.5  214.58
  4983.1  214.27  4986.7  212.83  4989.5  212.33  4992.7  212.83  4997.3  213.05
  4999.7  213.93  5014.2  213.76  5044.3  215.21    5069  215.83  5079.8  216.77
  5134.5  219.32  5159.3  219.89  5165.4  220.62  5214.1  223.08  5261.8  224.64
  5283.2  226.42  5298.9  226.59  5304.6  227.56  5336.7  228.83  5368.8  230.84
#Mann= 5 ,-1 , 0
  4649.3      .1       0  4835.2     .16       0  4966.5      .1       0
  4986.7     .07       0  4992.7      .1       0
Bank Sta=4869.2,5044.3
XS Rating Curve= 0 ,0
Exp/Cntr=0.3,0.1

Type RM Length L Ch R = 1 ,42587   ,446,446,446
BEGIN DESCRIPTION:
UNT008 IN PECR 63.0
END DESCRIPTION:
XS GIS Cut Line= 3
      2332637.67     13277246.86      2332137.72     13277346.85
      2331837.74     13277696.83
#Sta/Elev= 30
  4508.5  222.31    4641  219.29  4783.8  213.79    4845  212.13  4885.8  212.22
  4906.2   211.3  4916.4  208.78  4936.8  207.23    4947  210.59  4967.4   210.4
  5005.2  206.44  5007.9  205.94  5011.2  206.44  5015.8  208.84  5032.1  209.01
  5046.3  210.42  5068.3  212.06  5074.9  213.71  5082.6  214.17  5096.8  214.23
  5103.4  212.95  5124.3  212.25  5146.2  213.45  5195.6  214.46  5209.9  215.64
  5216.5  215.31  5351.5  221.47    5380  221.91  5400.9  223.74  5479.3  227.17
#Mann= 3 ,-1 , 0
  4508.5      .1       0  5005.2     .07       0  5011.2      .1       0
Bank Sta=4967.4,5046.3
XS Rating Curve= 0 ,0
Exp/Cntr=0.3,0.1

Type RM Length L Ch R = 1 ,42141   ,470,470,470
BEGIN DESCRIPTION:
UNT008 IN PECR 62.0
END DESCRIPTION:
XS GIS Cut Line= 3
      2332087.71     13276696.87      2331787.72     13277096.85
      2331637.71     13277496.87
#Sta/Elev= 30
  4497.1  218.97  4504.4  218.29  4583.5  216.27  4754.4  210.91    4769  209.91
  4797.1  209.49  4804.4   208.6  4810.6  208.71    4819  208.03  4839.8  208.07
  4847.1  207.31    4869  206.75  4875.2  206.09  4910.6  205.24  4972.2  204.79
    4975  204.29  4978.2  204.79  5042.5  205.26  5072.7  206.77  5097.7  207.21
  5146.6  209.57  5183.1  210.49    5208  212.13  5285.4  214.74  5317.5  216.91
  5348.6  217.96    5354  218.65  5384.2  219.45  5414.5  221.41  5424.3  221.55
#Mann= 3 ,-1 , 0
  4497.1      .1       0  4972.2     .07       0  4978.2      .1       0
Bank Sta=4869,5072.7
XS Rating Curve= 0 ,0
Exp/Cntr=0.3,0.1

Type RM Length L Ch R = 1 ,41671   ,314,314,314
BEGIN DESCRIPTION:
UNT008 IN PECR 61.0
END DESCRIPTION:
XS GIS Cut Line= 3
      2331787.73     13276546.84      2331387.72     13276896.85
      2331187.74     13277296.82
#Sta/Elev= 30
  4469.5  216.11  4497.5  214.79  4511.8  214.85  4540.2  213.61  4632.3  211.19
  4682.1   209.1  4703.5  209.15  4710.1   208.2  4795.5  206.08  4844.9  203.94
  4908.5  202.64  4916.1  201.93    4973  200.53  4979.7  199.05  4993.9  198.71
  4994.7  197.41  4997.5  196.91  5000.7  197.41  5003.8  197.41  5009.4  199.29
    5015  198.88  5023.4  200.17  5045.7  201.85  5059.7  201.85  5149.2  204.82
  5255.4  209.28  5269.4  209.12  5291.7  210.53  5314.1   210.9  5448.2   216.1
#Mann= 3 ,-1 , 0
  4469.5      .1       0  4994.7     .07       0  5000.7      .1       0
Bank Sta=4916.1,5045.7
XS Rating Curve= 0 ,0
Exp/Cntr=0.3,0.1

Type RM Length L Ch R = 1 ,41357   ,599,599,599
BEGIN DESCRIPTION:
UNT008 IN PECR 60.0
END DESCRIPTION:
XS GIS Cut Line= 4
       2331617.4     13276413.08       2331294.5     13276413.08
      2331034.08     13276949.54      2331039.29     13277246.37
#Sta/Elev= 30
  4333.1  211.03  4462.8   207.5  4532.8  206.27  4632.8  203.52  4671.3   203.4
  4679.9  202.83    4738  201.46  4753.2  201.49  4798.3   200.2  4837.9  199.73
  4849.2  199.23  4871.6  199.29  4916.7   198.5  4978.8  198.52  4984.4   196.9
  4998.4  195.17  5001.1  194.67  5004.4  195.17    5007  195.91    5024  198.33
  5069.1  199.65  5142.3  202.26  5149.3  202.82  5187.5  203.53  5193.8  204.04
  5252.3  205.59  5279.6  207.33  5399.7  210.24  5409.7     211  5549.2  215.91
#Mann= 3 ,-1 , 0
  4333.1      .1       0  4998.4     .07       0  5004.4      .1       0
Bank Sta=4837.9,5069.1
XS Rating Curve= 0 ,0
Exp/Cntr=0.3,0.1

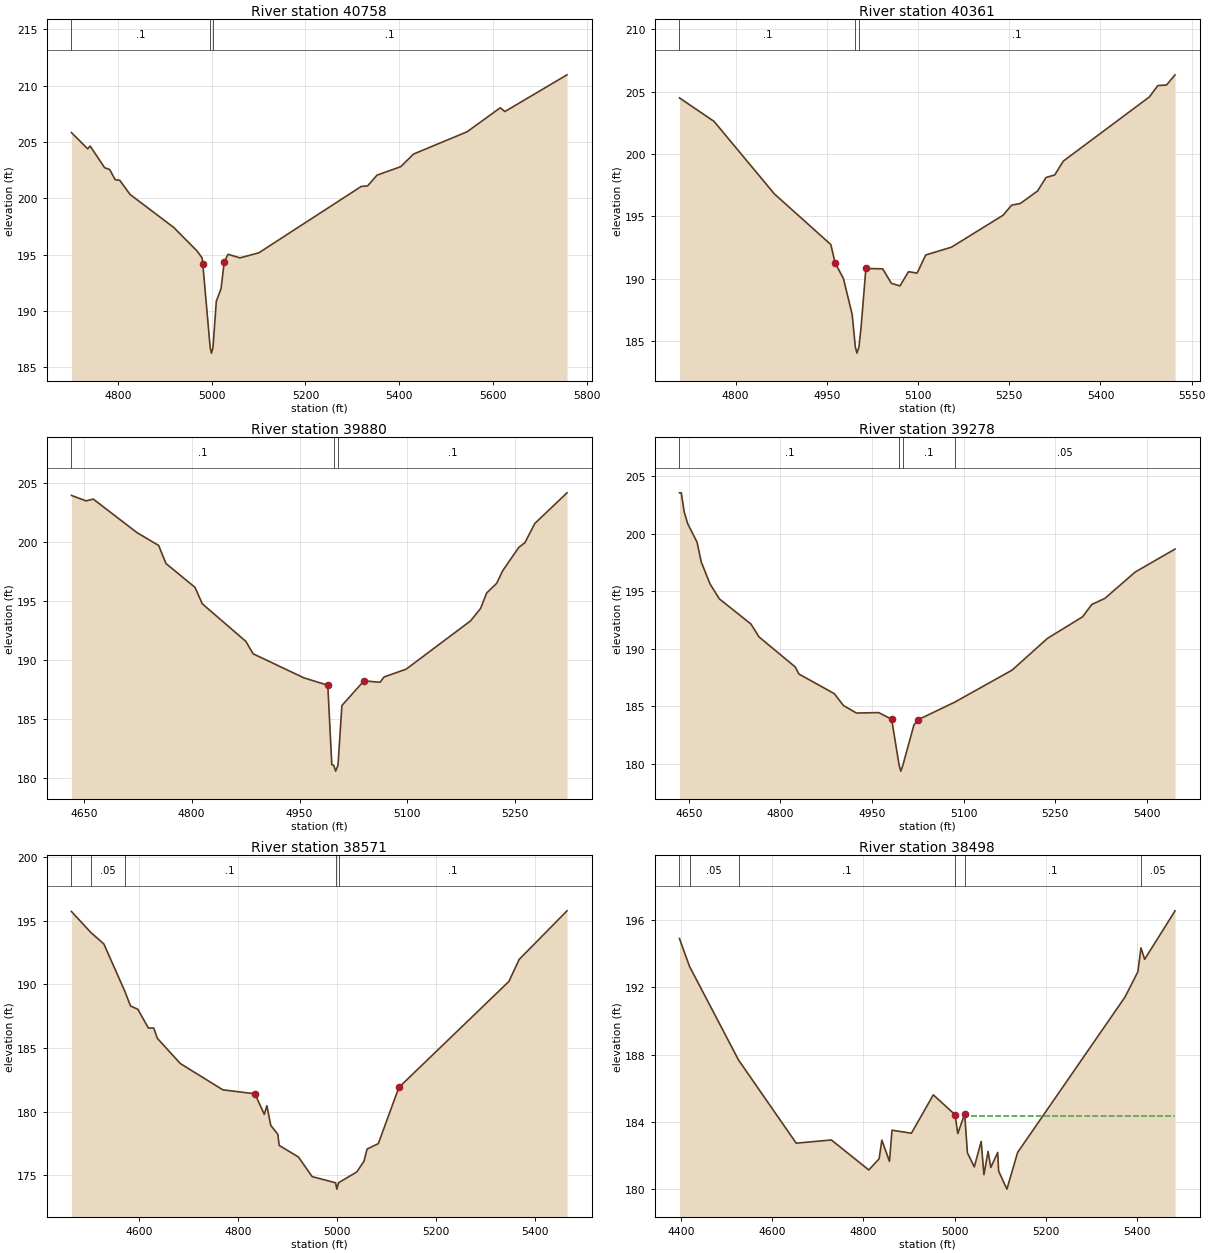
Type RM Length L Ch R = 1 ,40758   ,397,397,397
BEGIN DESCRIPTION:
UNT008 IN PECR 59.0
END DESCRIPTION:
XS GIS Cut Line= 4
      2330846.58     13276121.41      2330784.08     13276272.46
      2330726.79     13276725.58      2330789.29     13277157.89
#Sta/Elev= 30
  4700.9  205.83  4735.5  204.39  4740.9  204.63  4771.7  202.71  4782.5  202.55
  4794.1  201.65  4804.2  201.58  4825.8  200.34  4919.2   197.4  4969.6  195.28
  4979.7  194.69 4981.14  194.12  4996.8  186.74  4999.6  186.24  5002.8  186.74
  5009.9  190.85    5020  191.96 5026.82  194.35  5034.9  195.02  5060.3   194.7
  5100.6  195.15  5319.2  201.05  5332.5  201.09  5352.7  202.05  5403.2   202.8
  5430.4  203.92  5544.7   205.9  5615.4  208.03  5625.5   207.7  5757.9  210.96
#Mann= 3 ,-1 , 0
  4700.9      .1       0  4996.8     .07       0  5002.8      .1       0
Bank Sta=4981.14,5026.82
XS Rating Curve= 0 ,0
Exp/Cntr=0.3,0.1

Type RM Length L Ch R = 1 ,40361   ,481,481,481
BEGIN DESCRIPTION:
UNT008 IN PECR 58.0
END DESCRIPTION:
XS GIS Cut Line= 3
      2330587.73     13276046.85      2330387.72     13276296.85
      2330037.75     13276646.83
#Sta/Elev= 30
  4707.6  204.49  4764.4  202.61  4863.7  196.79  4956.5  192.73  4963.7  191.25
  4977.3     190  4991.7  187.11  4996.8  184.52  4999.5  184.02  5002.8  184.52
  5006.2  186.04  5014.2  190.81  5041.9  190.78  5056.1  189.62  5070.2  189.41
  5084.3  190.55  5098.5  190.44  5112.6  191.89    5155  192.52  5239.9  195.08
    5254  195.89  5268.2  196.02  5296.5  197.02  5310.6  198.11  5324.8  198.31
  5338.9  199.42  5480.3  204.56  5494.5  205.48  5508.6  205.52  5522.7  206.34
#Mann= 3 ,-1 , 0
  4707.6      .1       0  4996.8     .07       0  5002.8      .1       0
Bank Sta=4963.7,5014.2
XS Rating Curve= 0 ,0
Exp/Cntr=0.3,0.1

Type RM Length L Ch R = 1 ,39880   ,602,602,602
BEGIN DESCRIPTION:
UNT008 IN PECR 57.0
END DESCRIPTION:
XS GIS Cut Line= 3
      2330437.77     13275946.85      2330087.72     13275996.85
      2329787.73     13276146.85
#Sta/Elev= 30
  4632.9  203.93  4653.2  203.47  4663.3  203.62  4723.9  200.79  4754.2  199.69
  4764.3  198.17  4804.7  196.15  4814.8  194.76  4875.4  191.58  4885.5  190.53
  4956.2  188.49  4989.3  187.87  4994.9  181.14  4997.5   181.1  5000.2   180.6
  5003.5   181.1  5008.9  186.15  5039.6  188.24    5062  188.12  5067.6  188.57
  5098.3  189.23  5187.7  193.31  5201.7  194.36  5210.1  195.67  5224.1  196.49
  5232.5  197.56  5254.8  199.53  5263.2  199.92  5277.2  201.56  5321.9  204.15
#Mann= 3 ,-1 , 0
  4632.9      .1       0  4997.5     .07       0  5003.5      .1       0
Bank Sta=4989.3,5039.6
XS Rating Curve= 0 ,0
Exp/Cntr=0.3,0.1

Type RM Length L Ch R = 1 ,39278   ,707,707,707
BEGIN DESCRIPTION:
UNT008 IN PECR 56.0
END DESCRIPTION:
XS GIS Cut Line= 2
      2330187.74     13275296.84      2329502.54     13275731.43
#Sta/Elev= 30
  4634.9  203.54  4637.9  203.54  4642.6  201.89  4648.5  200.84  4663.7  199.25
  4670.5  197.54  4684.9  195.62  4700.2  194.32  4751.9  192.13  4765.2  191.01
  4824.4   188.4  4830.6  187.78  4888.3  186.08  4903.5  185.04  4924.7  184.39
  4961.1  184.43  4982.3  183.85  4994.6  179.84  4997.3  179.34  5000.6  179.84
  5018.7  183.34  5025.7  183.81  5085.3  185.33  5179.7  188.13  5237.3  190.88
  5294.9  192.76  5309.9  193.83  5331.4  194.36    5381  196.65  5446.3  198.65
#Mann= 4 ,-1 , 0
  4634.9      .1       0  4994.6     .07       0  5000.6      .1       0
  5085.3     .05       0
Bank Sta=4982.3,5025.7
XS Rating Curve= 0 ,0
Exp/Cntr=0.3,0.1

Type RM Length L Ch R = 1 ,38571   ,73,73,73
BEGIN DESCRIPTION:
UNT008 IN PECR 55.0
END DESCRIPTION:
XS GIS Cut Line= 5
      2330132.45     13275166.47      2329744.47     13275012.84
      2329671.56     13274992.01       2329575.2     13274992.01
       2329325.2     13275320.14
#Sta/Elev= 30
    4463  195.71  4502.5  194.05  4528.6  193.16  4570.8  189.46  4582.6  188.29
  4597.2  188.04  4618.7  186.56  4629.4  186.57  4636.7  185.76  4683.2  183.78
  4769.1  181.72  4833.9  181.41  4852.9   179.8  4858.2  180.47    4866  178.93
  4880.3  178.23    4883  177.36    4922  176.45  4949.7  174.91    4997  174.43
  4999.7  173.93    5003  174.43    5040  175.28  5054.5  176.12  5060.7  177.07
  5083.5   177.5  5125.1  181.91  5347.5  190.22  5368.3  191.95    5465  195.76
#Mann= 5 ,-1 , 0
    4463      .1       0  4502.5     .05       0  4570.8      .1       0
    4997     .07       0    5003      .1       0
Bank Sta=4833.9,5125.1
XS Rating Curve= 0 ,0
Exp/Cntr=0.3,0.1

Type RM Length L Ch R = 1 ,38498   ,73,73,73
BEGIN DESCRIPTION:
UNT008 IN PECR 54.0
END DESCRIPTION:
XS GIS Cut Line= 5
      2330138.54     13275139.56       2329700.2     13274931.25
      2329622.08     13274909.55      2329509.23     13274983.33
      2329283.54     13275295.82
#Sta/Elev= 30
  4396.5  194.89  4418.5  193.24    4526  187.68  4652.5  182.74  4729.6  182.93
  4811.6  181.15  4834.3  181.81  4840.3  182.92    4857  181.66  4862.5  183.51
  4905.1  183.33  4953.1  185.61  5000.8  184.43  5006.8  183.31  5021.9  184.48
  5027.9  182.17    5043  181.33  5058.1  182.84  5064.1  180.87  5073.2  182.25
  5079.2   181.3  5094.3  182.19  5096.4  181.08  5114.5  180.01    5138  182.19
  5373.5  191.42  5401.7  192.92  5408.5  194.34  5416.5  193.66  5483.2  196.54
#Mann= 6 ,-1 , 0
  4396.5      .1       0  4418.5     .05       0    4526      .1       0
  5000.8     .07       0  5021.9      .1       0  5408.5     .05       0
#XS Ineff= 2 , 0
       0  4991.4  184.61 5022.59       0  184.33
Permanent Ineff=
       T       T
Bank Sta=5000.8,5021.9
XS Rating Curve= 0 ,0
Exp/Cntr=0.3,0.1

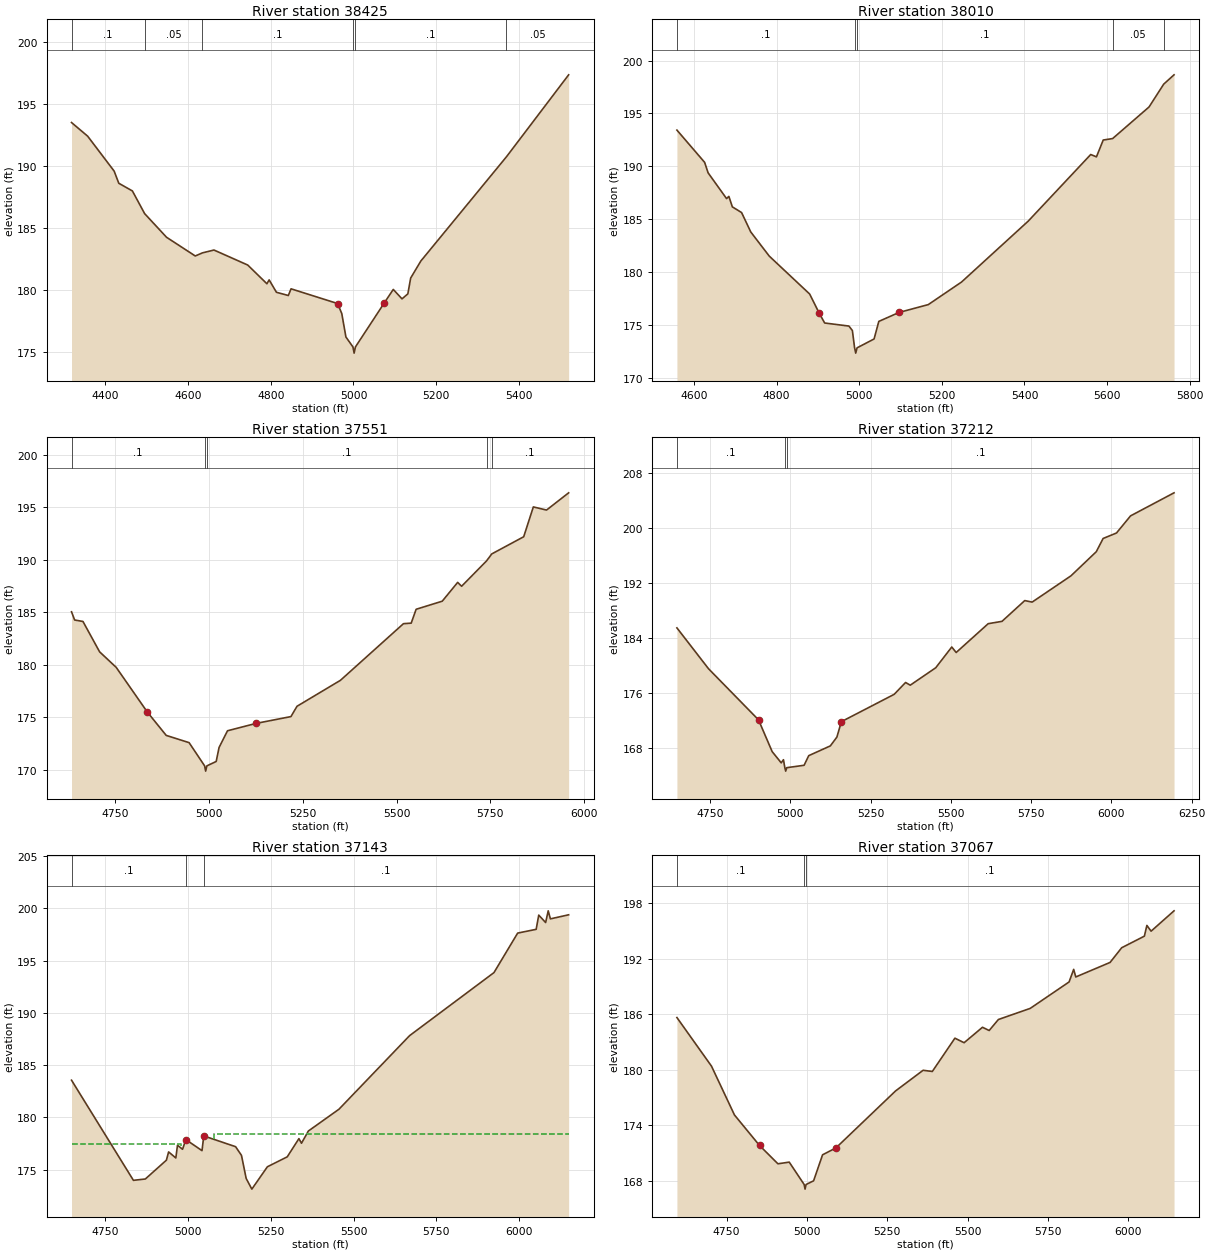
Type RM Length L Ch R = 1 ,38425   ,415,415,415
BEGIN DESCRIPTION:
Mapping XS d9d84626
END DESCRIPTION:
XS GIS Cut Line= 5
      2330182.01      13275096.2      2329669.82     13274866.14
      2329530.93     13274870.48      2329431.11     13274974.65
       2329249.1     13275282.33
#Sta/Elev= 30
  4318.2  193.49  4357.2  192.39  4421.3  189.57  4432.5  188.59  4465.4  187.97
    4495  186.14    4548  184.23  4617.5  182.72  4634.7  182.97  4662.7   183.2
  4744.3  181.99  4790.7  180.48  4796.1  180.79  4813.8  179.79  4842.5  179.53
  4849.1  180.07  4961.8  178.88  4971.8  178.07  4981.8  176.18  4998.8  175.38
  5001.6  174.88  5004.8  175.38  5074.9  178.95  5096.3  180.02  5117.4  179.26
  5131.5  179.66  5138.4  180.94  5162.9  182.31  5370.1  190.73  5520.4  197.34
#Mann= 6 ,-1 , 0
  4318.2      .1       0    4495     .05       0  4634.7      .1       0
  4998.8     .07       0  5004.8      .1       0  5370.1     .05       0
Bank Sta=4961.8,5074.9
XS Rating Curve= 0 ,0
Exp/Cntr=0.3,0.1

Type RM Length L Ch R = 1 ,38010   ,459,459,459
BEGIN DESCRIPTION:
UNT008 IN PECR 53.0
END DESCRIPTION:
XS GIS Cut Line= 3
      2329687.75     13274346.84      2329287.72     13274546.85
      2329187.72     13275296.87
#Sta/Elev= 30
  4558.4  193.42  4625.5  190.37  4633.9  189.38  4678.6  186.94  4684.2  187.15
  4692.6  186.16    4715  185.62  4737.3  183.78    4782   181.5  4879.9  177.91
  4902.2  176.16  4916.2  175.17  4974.9  174.88  4983.3  174.46  4988.7  172.82
  4991.4  172.32  4994.7  172.82  5035.9  173.66  5047.3  175.32  5096.4  176.17
  5167.1  176.91  5247.8  179.05  5409.2  184.81  5560.5  191.11  5574.4  190.89
  5590.8  192.48  5613.6  192.62  5701.8  195.61  5737.3  197.77  5762.3  198.65
#Mann= 5 ,-1 , 0
  4558.4      .1       0  4988.7     .07       0  4994.7      .1       0
  5613.6     .05       0  5737.3      .1       0
Bank Sta=4902.2,5096.4
XS Rating Curve= 0 ,0
Exp/Cntr=0.3,0.1

Type RM Length L Ch R = 1 ,37551   ,339,339,339
BEGIN DESCRIPTION:
UNT008 IN PECR 52.0
END DESCRIPTION:
XS GIS Cut Line= 3
      2329087.71     13274096.87      2328877.11     13274507.46
      2329096.68     13275342.73
#Sta/Elev= 30
  4633.7  185.05    4642  184.27  4664.2  184.13  4708.6  181.24  4752.9  179.76
    4836   175.5  4886.1  173.29  4947.1   172.6  4988.5  170.39  4991.2  169.89
  4994.5  170.39  5019.3  170.81    5027  172.14  5049.5  173.73  5125.5  174.43
  5218.6  175.08  5234.7  176.06  5350.5  178.53  5518.5  183.92  5539.1  183.97
  5552.3  185.29  5621.9  186.06    5663  187.85  5673.5  187.48  5739.9  189.89
    5754  190.56    5839  192.19  5864.7  195.03  5899.9  194.73  5958.8  196.37
#Mann= 5 ,-1 , 0
  4633.7      .1       0  4988.5     .07       0  4994.5      .1       0
  5739.9     .05       0    5754      .1       0
Bank Sta=4836,5125.5
XS Rating Curve= 0 ,0
Exp/Cntr=0.3,0.1

Type RM Length L Ch R = 1 ,37212   ,69,69,69
BEGIN DESCRIPTION:
Mapping XS f1f52bd9
END DESCRIPTION:
XS GIS Cut Line= 4
       2328910.3     13273950.31      2328662.88     13274210.76
      2328632.49     13274358.33       2328012.3     13275191.05
#Sta/Elev= 30
  4646.8  185.52  4745.2  179.58  4900.9  172.15  4943.4  167.53  4971.7  165.89
  4978.6  166.35  4982.9  165.19  4985.6  164.69  4988.9  165.19  5042.9  165.54
  5057.3  166.94  5124.6  168.36    5145  169.64  5158.9  171.88  5323.5  175.86
  5358.9  177.58  5373.5  177.19  5452.8  179.72  5502.8  182.74  5516.5  181.94
  5616.2  186.13  5659.2  186.47  5730.1  189.49  5753.1  189.27    5874  193.09
  5952.9   196.6  5974.1  198.52  6015.8  199.32  6059.6  201.81    6195  205.16
#Mann= 3 ,-1 , 0
  4646.8      .1       0  4982.9     .07       0  4988.9      .1       0
Bank Sta=4900.9,5158.9
XS Rating Curve= 0 ,0
Exp/Cntr=0.3,0.1

Type RM Length L Ch R = 1 ,37143   ,76,76,76
BEGIN DESCRIPTION:
UNT008 IN PECR 51.0
END DESCRIPTION:
XS GIS Cut Line= 4
      2328858.22     13273932.95      2328615.13     13274145.66
      2328523.99     13274427.77      2327956.66     13275103.37
#Sta/Elev= 30
  4648.1  183.56  4835.1  173.98  4871.1  174.11  4934.7  175.91  4941.4   176.7
  4963.2  176.12  4968.2  177.34  4983.5  176.95  4993.4  177.88  5042.3  176.82
  5047.6  178.23  5143.7   177.2  5161.5  176.37  5175.7  174.16  5192.8  173.14
  5239.8  175.28  5299.8  176.23    5335  177.97  5342.8  177.53  5363.6   178.7
  5455.9  180.78  5669.3  187.82  5924.2  193.85  5995.8  197.63  6051.7  197.99
  6059.5  199.35  6080.3  198.64  6088.1  199.76  6094.7  198.99  6149.8  199.38
#Mann= 3 , 0 , 0
  4648.1      .1       0  4993.4     .07       0  5047.6      .1       0
#XS Ineff= 2 , 0
       0 4977.84  177.41 5079.52       0  178.37
Permanent Ineff=
       T       T
Bank Sta=4993.4,5047.6
XS Rating Curve= 0 ,0
Exp/Cntr=0.3,0.1

Type RM Length L Ch R = 1 ,37067   ,382,382,382
BEGIN DESCRIPTION:
Mapping XS 34b4d692
END DESCRIPTION:
XS GIS Cut Line= 4
      2328849.54     13273876.54      2328523.99       13274150.
      2328463.22     13274358.33      2327882.59     13275051.63
#Sta/Elev= 30
  4595.4  185.63  4702.9  180.38  4774.4   175.1  4852.4   171.8  4909.6  169.82
  4944.8     170  4991.2  167.58    4994  167.08  4997.2  167.58  5020.6  167.98
  5048.5  170.79  5090.2  171.54  5275.4  177.69  5361.3  179.93  5389.9   179.8
  5460.2   183.4  5488.8  182.91    5546  184.58  5566.8  184.23  5595.5  185.42
  5694.4  186.62  5815.4  189.48  5829.7  190.84  5836.2  190.02  5942.9  191.59
  5979.1  193.18  6049.6  194.43  6057.4  195.59  6070.5  194.97  6141.9  197.17
#Mann= 3 ,-1 , 0
  4595.4      .1       0  4991.2     .07       0  4997.2      .1       0
Bank Sta=4852.4,5090.2
XS Rating Curve= 0 ,0
Exp/Cntr=0.3,0.1

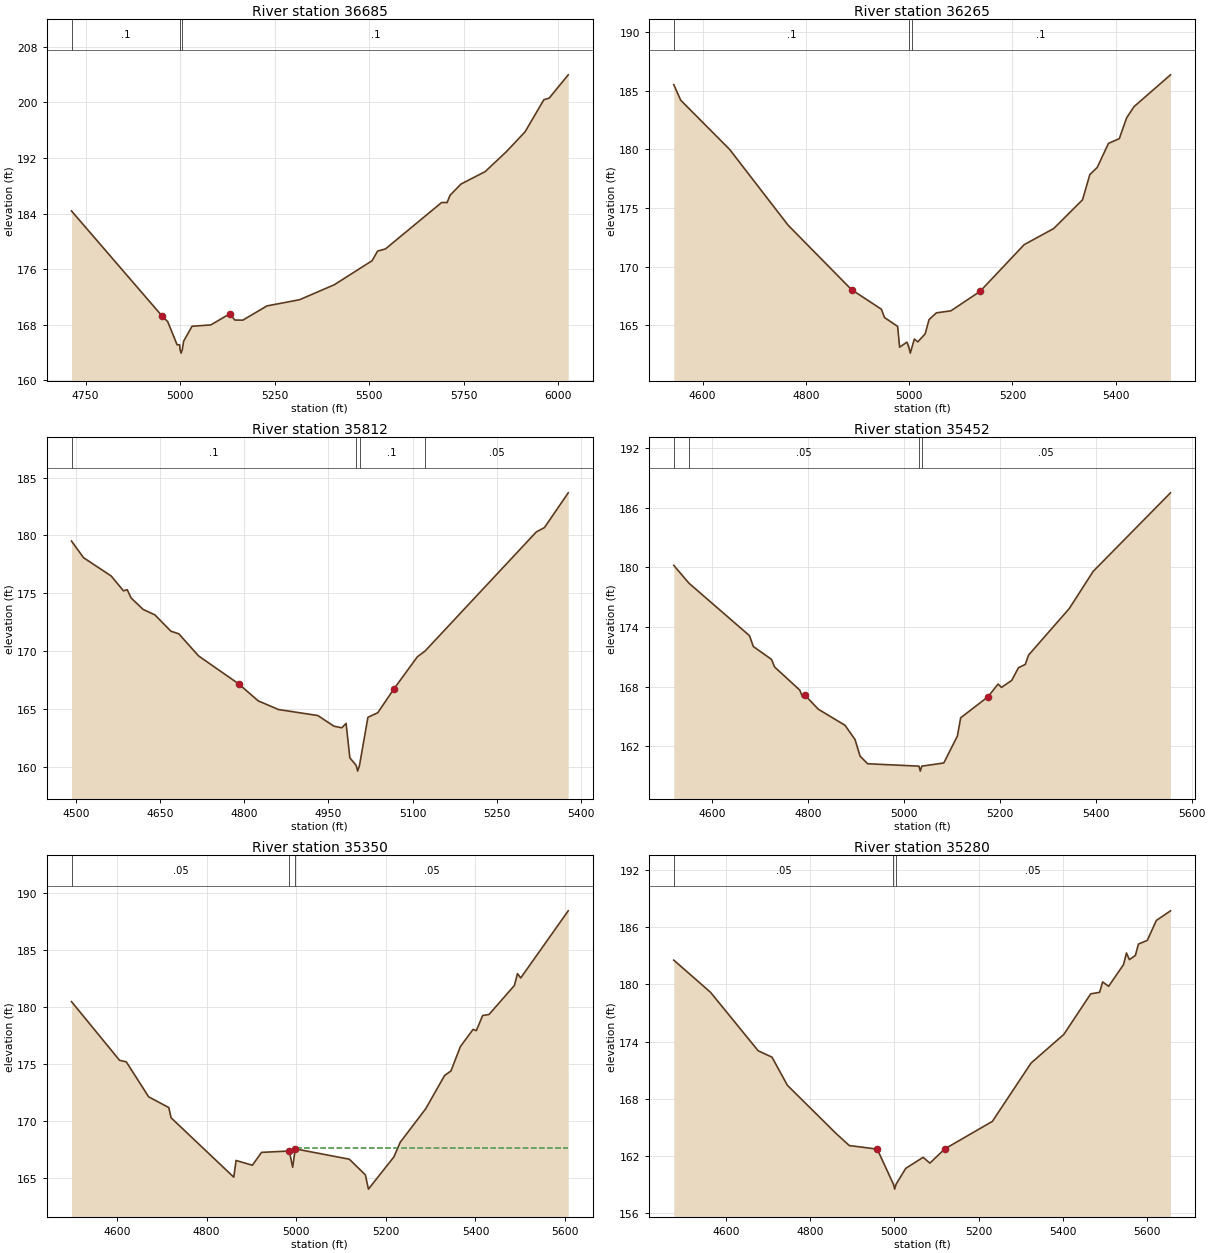
Type RM Length L Ch R = 1 ,36685   ,420,420,420
BEGIN DESCRIPTION:
UNT008 IN PECR 50.0
END DESCRIPTION:
XS GIS Cut Line= 3
      2328587.71     13273596.86      2328387.72     13273796.85
      2327587.73     13274446.85
#Sta/Elev= 30
  4712.8  184.38  4953.2   169.2  4967.3  168.44  4992.1  165.11  4998.9  165.11
  4999.8  164.41  5002.6  163.91  5005.8  164.41  5009.3  165.63  5031.6  167.78
  5081.1  167.97  5130.7  169.55    5145  168.67  5165.9  168.66  5229.8  170.71
    5316   171.6  5407.9  173.76  5507.8  177.22  5522.2   178.6    5543  178.91
  5691.7   185.6    5706  185.59    5714  186.64  5742.7  188.25  5806.6  190.04
  5862.6   192.9  5912.2  195.77    5962   200.4  5976.1  200.63  6026.4  203.98
#Mann= 3 ,-1 , 0
  4712.8      .1       0  4999.8     .07       0  5005.8      .1       0
Bank Sta=4953.2,5130.7
XS Rating Curve= 0 ,0
Exp/Cntr=0.3,0.1

Type RM Length L Ch R = 1 ,36265   ,453,453,453
BEGIN DESCRIPTION:
UNT008 IN PECR 49.0
END DESCRIPTION:
XS GIS Cut Line= 3
      2328387.73     13273346.85      2328037.72     13273596.85
      2327687.74     13273996.83
#Sta/Elev= 30
  4544.3  185.53  4557.8   184.2  4652.5     180  4765.5  173.54  4888.4  168.03
  4946.2  166.36  4952.3  165.65  4977.7  164.89  4981.5  163.12  4995.8  163.55
  4999.4  163.11  5002.2  162.61  5005.4  163.11    5010  163.81  5016.7  163.57
  5030.9  164.25  5038.5  165.47  5052.7  166.05  5080.7  166.22  5137.2  167.88
  5222.6  171.87  5279.6  173.24  5335.6   175.7  5349.8  177.86    5364  178.46
  5385.9  180.52  5406.8  180.92    5421   182.7  5435.2  183.65  5505.9  186.37
#Mann= 3 ,-1 , 0
  4544.3      .1       0  4999.4     .07       0  5005.4      .1       0
Bank Sta=4888.4,5137.2
XS Rating Curve= 0 ,0
Exp/Cntr=0.3,0.1

Type RM Length L Ch R = 1 ,35812   ,360,360,360
BEGIN DESCRIPTION:
UNT008 IN PECR 48.0
END DESCRIPTION:
XS GIS Cut Line= 3
      2328037.75     13273046.83      2327637.72     13273396.85
      2327387.72     13273646.85
#Sta/Elev= 30
  4492.2  179.52  4513.6  178.08    4563  176.49  4584.8  175.21  4591.4  175.31
  4598.5  174.59  4619.9   173.6  4640.8  173.13  4669.3  171.72  4683.5  171.49
  4718.6  169.58  4789.8  167.17  4824.9  165.69    4861  164.94  4931.2  164.42
  4959.7   163.5  4973.9  163.36  4981.5  163.74  4988.2  160.76  4999.4  160.11
  5002.1  159.61  5005.4  160.11  5020.4  164.27  5037.9  164.66  5066.2  166.69
  5108.6  169.51    5122  169.99  5320.7  180.32  5334.9  180.68  5377.3  183.69
#Mann= 4 ,-1 , 0
  4492.2      .1       0  4999.4     .07       0  5005.4      .1       0
    5122     .05       0
Bank Sta=4789.8,5066.2
XS Rating Curve= 0 ,0
Exp/Cntr=0.3,0.1

Type RM Length L Ch R = 1 ,35452   ,102,102,102
BEGIN DESCRIPTION:
Mapping XS a4b20de8
END DESCRIPTION:
XS GIS Cut Line= 3
       2327968.4     13272921.71      2327438.92     13273086.63
      2327105.69     13273432.84
#Sta/Elev= 30
  4520.8  180.19  4552.7  178.39  4678.6  173.13  4686.6  172.04  4724.4  170.75
    4731  169.98  4783.4  167.66  4789.5  166.92  4794.7  167.12    4822  165.74
  4877.6  164.13  4898.6  162.69    4909  161.03  4924.8  160.26  5031.7  160.02
  5034.5  159.52  5037.7  160.02  5083.5  160.34  5111.8  163.04  5118.7  164.88
  5175.3  166.98  5196.7  168.27  5203.6  167.93    5225  168.63  5239.1  169.91
  5253.3  170.24  5260.2  171.18  5345.1  175.86  5394.8  179.59  5555.9  187.48
#Mann= 4 ,-1 , 0
  4520.8      .1       0  4552.7     .05       0  5031.7     .04       0
  5037.7     .05       0
Bank Sta=4794.7,5175.3
XS Rating Curve= 0 ,0
Exp/Cntr=0.3,0.1

Type RM Length L Ch R = 1 ,35350   ,70,70,70
BEGIN DESCRIPTION:
UNT008 IN PECR 47.0
END DESCRIPTION:
XS GIS Cut Line= 4
      2327952.78     13272867.02      2327482.32      13272965.1
      2327343.43     13273034.55      2327002.96     13273362.09
#Sta/Elev= 30
  4498.6  180.46  4605.9   175.3  4620.8  175.17  4670.8  172.09  4715.7  171.15
  4720.8  170.25  4860.7  165.03  4865.8   166.5  4902.2  166.08  4922.6  167.21
  4984.5  167.33  4992.1   165.9  4997.7  167.52  5118.5  166.61  5154.4  165.23
  5161.1  163.98  5217.9  166.81  5232.1   168.1  5288.7  171.03  5331.1  173.97
  5345.3  174.37  5366.3  176.51  5394.6  178.02  5401.9  177.91    5416  179.24
  5430.2  179.33  5486.8  181.88  5493.7  182.92  5500.9  182.54  5606.9  188.44
#Mann= 3 , 0 , 0
  4498.6     .05       0  4984.5    .035       0  4997.7     .05       0
#XS Ineff= 2 , 0
       0 4979.52  167.32 5002.13       0   167.6
Permanent Ineff=
       T       T
Bank Sta=4984.5,4997.7
XS Rating Curve= 0 ,0
Exp/Cntr=0.3,0.1

Type RM Length L Ch R = 1 ,35280   ,355,355,355
BEGIN DESCRIPTION:
Mapping XS 152c453a
END DESCRIPTION:
XS GIS Cut Line= 3
      2327942.34     13272787.16      2327304.37      13272943.4
      2326944.13       13273321.
#Sta/Elev= 30
  4476.6  182.52  4563.7  179.16    4677  173.03  4709.8  172.36  4746.2  169.42
  4862.3  164.35  4893.2  163.11  4959.4  162.74    4998  159.05  5000.8  158.55
    5004  159.05    5027  160.72  5068.2  161.88  5084.3  161.27  5119.7  162.76
  5232.6  165.64  5324.5  171.75  5402.1  174.74    5466  178.99  5487.1  179.15
  5494.3  180.24  5508.5  179.78  5543.7  182.04  5550.9  183.27  5557.8  182.57
    5572  183.01  5579.2   184.2  5600.3  184.59  5621.7  186.67  5655.3  187.68
#Mann= 3 ,-1 , 0
  4476.6     .05       0    4998    .035       0    5004     .05       0
Bank Sta=4959.4,5119.7
XS Rating Curve= 0 ,0
Exp/Cntr=0.3,0.1

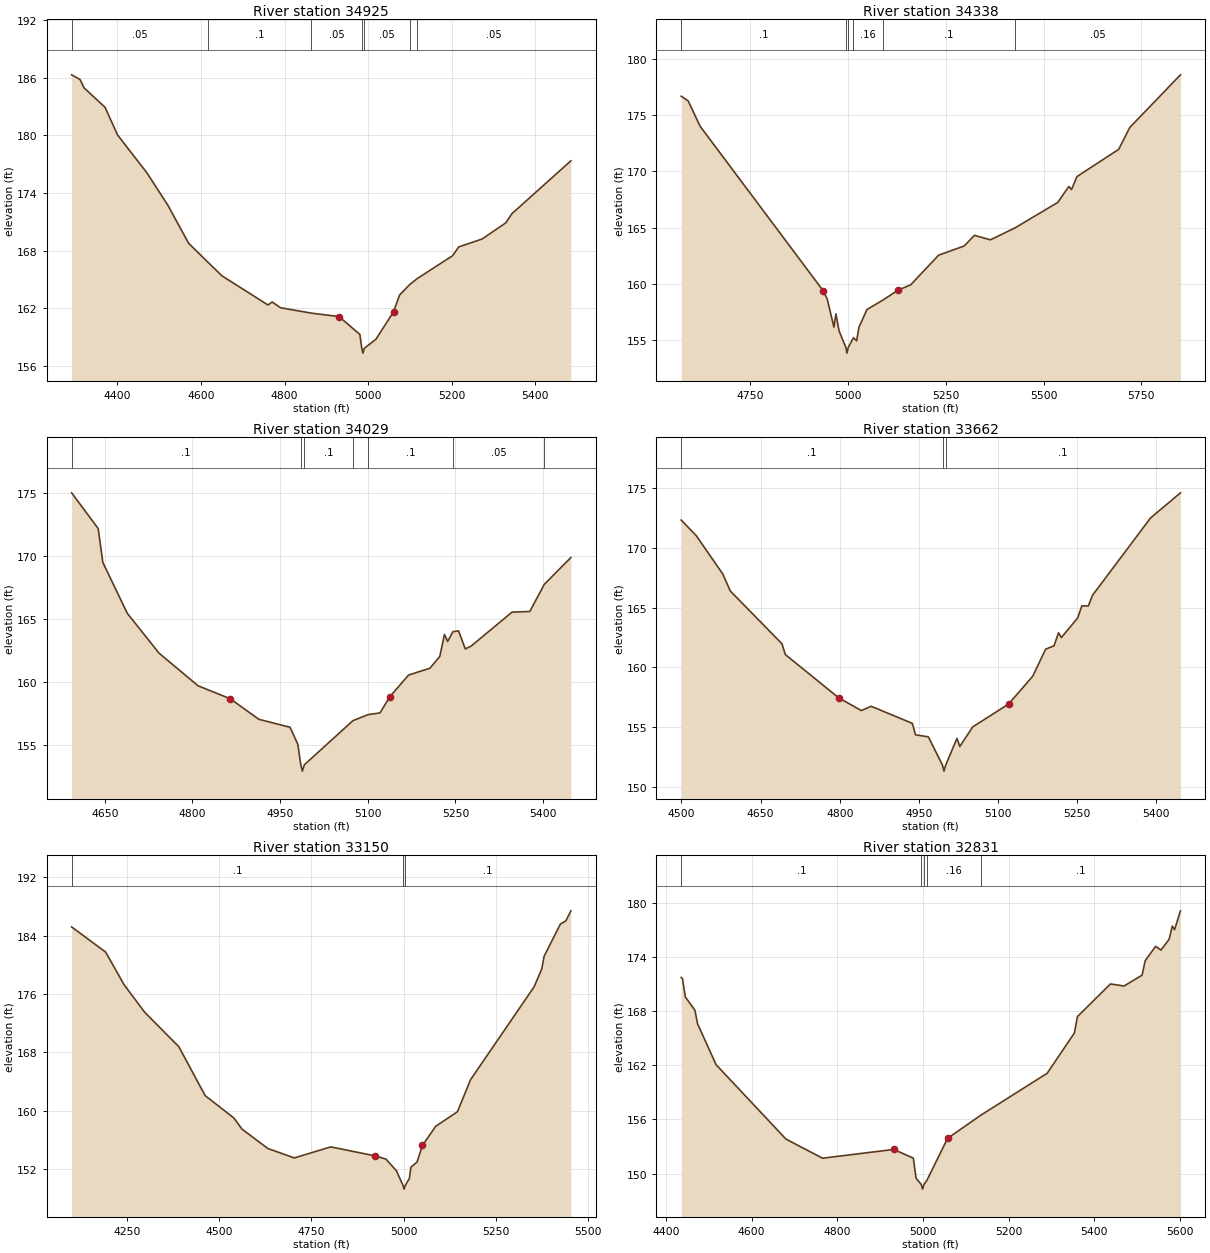
Type RM Length L Ch R = 1 ,34925   ,587,587,587
BEGIN DESCRIPTION:
UNT008 IN PECR 46.0
END DESCRIPTION:
XS GIS Cut Line= 3
      2327937.74     13272646.85      2327237.72     13272646.85
      2326887.72     13272996.86
#Sta/Elev= 30
  4290.4  186.32  4310.4  185.84  4320.4  184.95  4370.4  182.94  4400.4  180.05
  4470.4  176.12  4520.4  172.76  4570.4  168.77  4617.2  166.77  4650.4  165.37
  4760.4  162.34  4770.4  162.65  4790.4  162.05    4864  161.49  4930.4  161.13
  4980.4  159.27  4984.9  157.82  4987.7  157.32  4990.9  157.82  5018.7  158.76
  5061.1  161.64  5075.3  163.37  5099.4  164.46  5118.1   165.1  5202.6  167.48
  5216.7  168.38  5273.3  169.22  5329.8   170.9    5344  171.84  5485.4  177.36
#Mann= 7 ,-1 , 0
  4290.4     .05       0  4617.2      .1       0    4864     .05       0
  4984.9    .035       0  4990.9     .05       0  5099.4      .1       0
  5118.1     .05       0
Bank Sta=4930.4,5061.1
XS Rating Curve= 0 ,0
Exp/Cntr=0.3,0.1

Type RM Length L Ch R = 1 ,34338   ,309,309,309
BEGIN DESCRIPTION:
UNT008 IN PECR 45.0
END DESCRIPTION:
XS GIS Cut Line= 5
      2327097.03     13271799.16      2327131.75      13272029.2
      2327023.24     13272615.14      2326801.89     13272866.88
       2326715.1     13272936.31
#Sta/Elev= 30
  4574.8  176.66  4592.7  176.24    4623     174  4937.3  159.39  4947.4  158.69
  4964.8  156.16  4969.9  157.34  4977.9  155.83  4995.3  154.35    4998  153.85
  5001.3  154.35  5014.7  155.22  5022.7  154.94  5028.8  156.15  5049.1  157.72
  5090.3  158.57  5128.5  159.44    5161  159.92  5232.2  162.55  5297.3  163.36
  5323.7  164.31  5364.4  163.91  5427.3  164.97  5536.3  167.23  5564.7  168.65
  5571.4  168.37  5585.6  169.53  5691.9  171.94  5720.4  173.89  5849.7  178.56
#Mann= 6 ,-1 , 0
  4574.8      .1       0  4995.3     .07       0  5001.3      .1       0
  5014.7     .16       0  5090.3      .1       0  5427.3     .05       0
Bank Sta=4937.3,5128.5
XS Rating Curve= 0 ,0
Exp/Cntr=0.3,0.1

Type RM Length L Ch R = 1 ,34029   ,367,367,367
BEGIN DESCRIPTION:
UNT008 IN PECR 44.0
END DESCRIPTION:
XS GIS Cut Line= 3
      2326937.72     13271896.86      2326787.72     13272296.85
      2326637.72     13272696.86
#Sta/Elev= 30
  4593.2  174.99  4638.6  172.16  4646.6  169.47  4688.4  165.44  4742.7  162.28
  4809.5  159.69  4864.6  158.66  4913.6  157.03    4967   156.4  4980.3  155.05
  4985.4  153.42  4988.1  152.92  4991.4  153.42  5074.6  156.92  5100.5   157.4
    5121  157.54  5137.9  158.83  5169.9  160.54  5206.4  161.08  5223.3  162.02
  5231.3  163.76  5236.7   163.2  5245.8  163.98  5255.4  164.04  5266.9  162.61
  5276.7  162.83    5347  165.53  5377.3  165.58  5402.1  167.73  5447.6  169.86
#Mann= 7 ,-1 , 0
  4593.2      .1       0  4985.4     .07       0  4991.4      .1       0
  5074.6     .16       0  5100.5      .1       0  5245.8     .05       0
  5402.1      .1       0
Bank Sta=4864.6,5137.9
XS Rating Curve= 0 ,0
Exp/Cntr=0.3,0.1

Type RM Length L Ch R = 1 ,33662   ,512,512,512
BEGIN DESCRIPTION:
UNT008 IN PECR 43.0
END DESCRIPTION:
XS GIS Cut Line= 4
      2326649.97     13271868.63      2326563.17     13271981.46
      2326341.82      13272545.7      2326350.42     13272743.55
#Sta/Elev= 30
  4499.5  172.33  4528.3  171.01  4578.1  167.83  4592.6  166.39  4690.6  161.97
  4696.9  161.07    4798  157.45    4841  156.38  4859.6  156.74  4937.7  155.31
  4943.7  154.35  4968.1  154.18  4994.9  151.81  4997.7  151.31  5000.9  151.81
  5022.3  154.05  5027.7  153.37  5052.1  155.01  5120.3  156.93    5166  159.26
  5190.4  161.52  5206.2   161.8  5214.9  162.89  5220.2  162.49    5251  164.13
  5259.1  165.15  5271.4  165.14  5279.1  166.02  5389.2   172.5    5446  174.61
#Mann= 3 ,-1 , 0
  4499.5      .1       0  4994.9     .07       0  5000.9      .1       0
Bank Sta=4798,5120.3
XS Rating Curve= 0 ,0
Exp/Cntr=0.3,0.1

Type RM Length L Ch R = 1 ,33150   ,319,319,319
BEGIN DESCRIPTION:
UNT008 IN PECR 42.0
END DESCRIPTION:
XS GIS Cut Line= 3
      2326637.72     13271646.85      2325937.72     13272246.85
       2325587.7     13272496.87
#Sta/Elev= 30
  4100.7  185.18  4192.9  181.73  4242.8  177.27  4298.8  173.49    4391  168.79
  4462.4  162.09  4540.3  159.03  4561.7  157.53  4632.5  154.85  4703.8  153.57
  4802.6  155.08  4923.3  153.84  4951.9  153.41  4980.4  151.81  4998.3   149.8
    5001   149.3  5004.3   149.8  5015.5  150.76  5019.4  152.29  5036.2  153.01
  5050.9  155.28  5086.6  157.89  5145.6  159.89  5181.2  164.28  5353.2  176.98
  5374.1  179.44  5380.3  181.16  5424.5  185.58  5439.3     186  5452.8  187.38
#Mann= 3 ,-1 , 0
  4100.7      .1       0  4998.3     .07       0  5004.3      .1       0
Bank Sta=4923.3,5050.9
XS Rating Curve= 0 ,0
Exp/Cntr=0.3,0.1

Type RM Length L Ch R = 1 ,32831   ,618,618,618
BEGIN DESCRIPTION:
UNT008 IN PECR 41.0
END DESCRIPTION:
XS GIS Cut Line= 4
      2326254.55     13271629.42      2325985.48      13271846.4
      2325542.77      13272115.5      2325447.32     13272401.88
#Sta/Elev= 30
  4435.5  171.75  4438.6   171.6    4445   169.6  4467.4  168.12  4473.8   166.6
    4517  162.07  4680.1  153.82  4765.4   151.7  4931.5  152.67  4977.5  151.71
  4983.8  149.49  4996.2  148.77    4999  148.27  5002.2  148.77  5009.6  149.29
  5057.4   153.9  5134.3  156.45  5289.9  161.12  5353.4  165.58  5360.6  167.41
  5437.7  171.03  5469.3   170.8  5511.5     172  5518.8  173.61  5543.1   175.2
  5555.7  174.79  5574.7  175.99    5582  177.45  5587.3  177.04  5601.1  179.14
#Mann= 5 ,-1 , 0
  4435.5      .1       0  4996.2     .07       0  5002.2      .1       0
  5009.6     .16       0  5134.3      .1       0
Bank Sta=4931.5,5057.4
XS Rating Curve= 0 ,0
Exp/Cntr=0.3,0.1