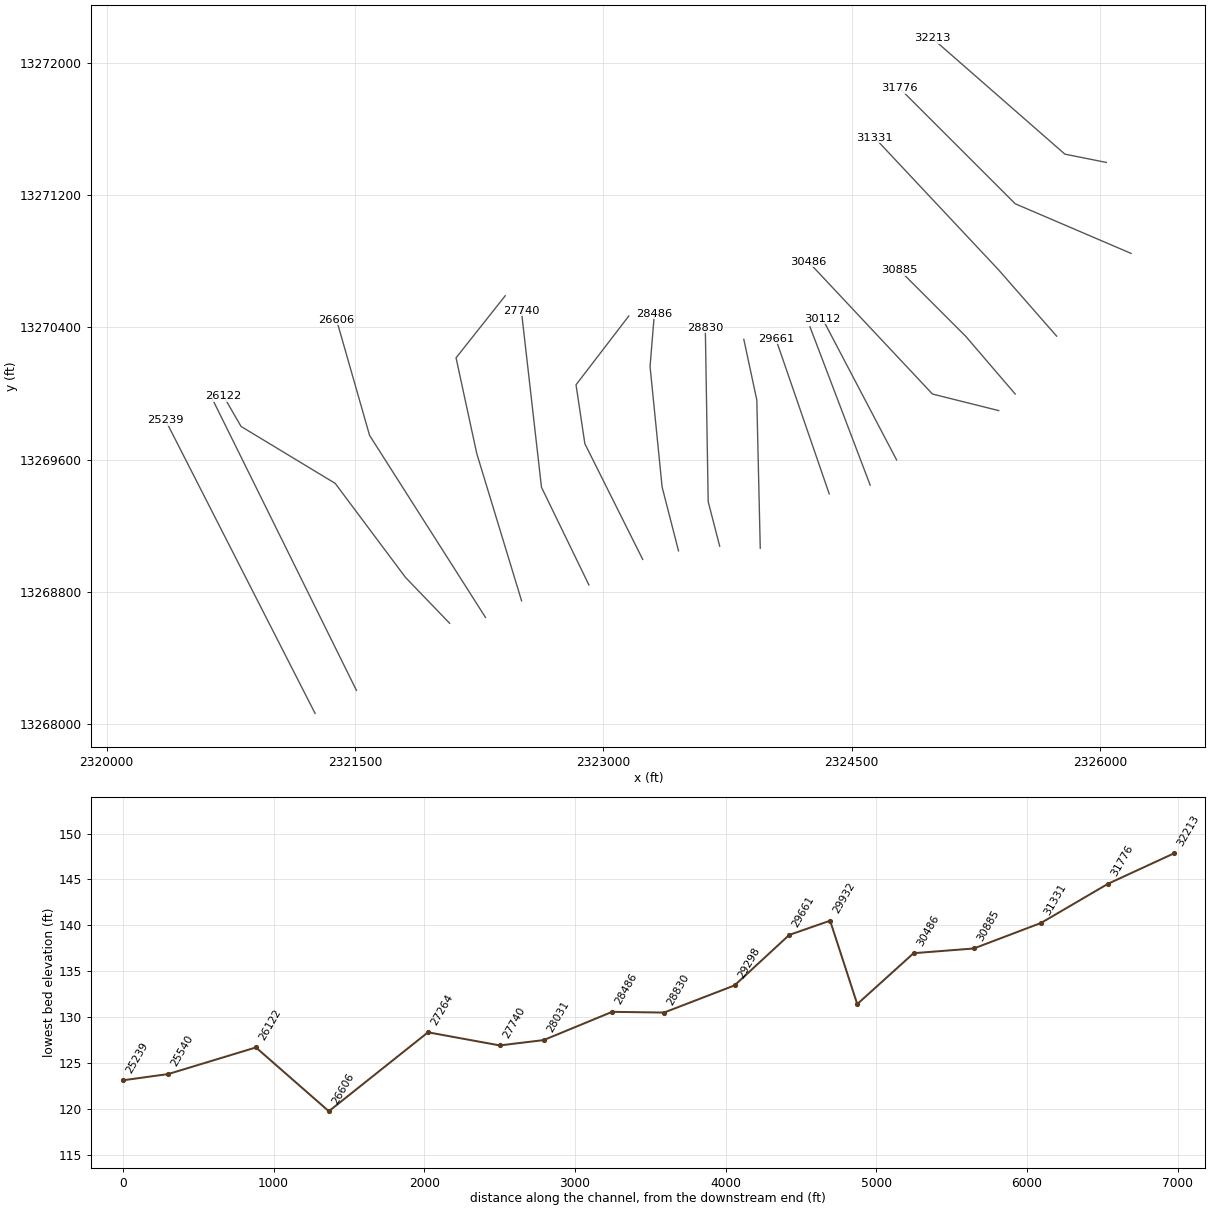
HEC-RAS study UNT008 IN PECR.prj: UNT008 IN PECR Base Level Engineering

--- UNT008 IN PECR.g01 (geometry) --- (continued)

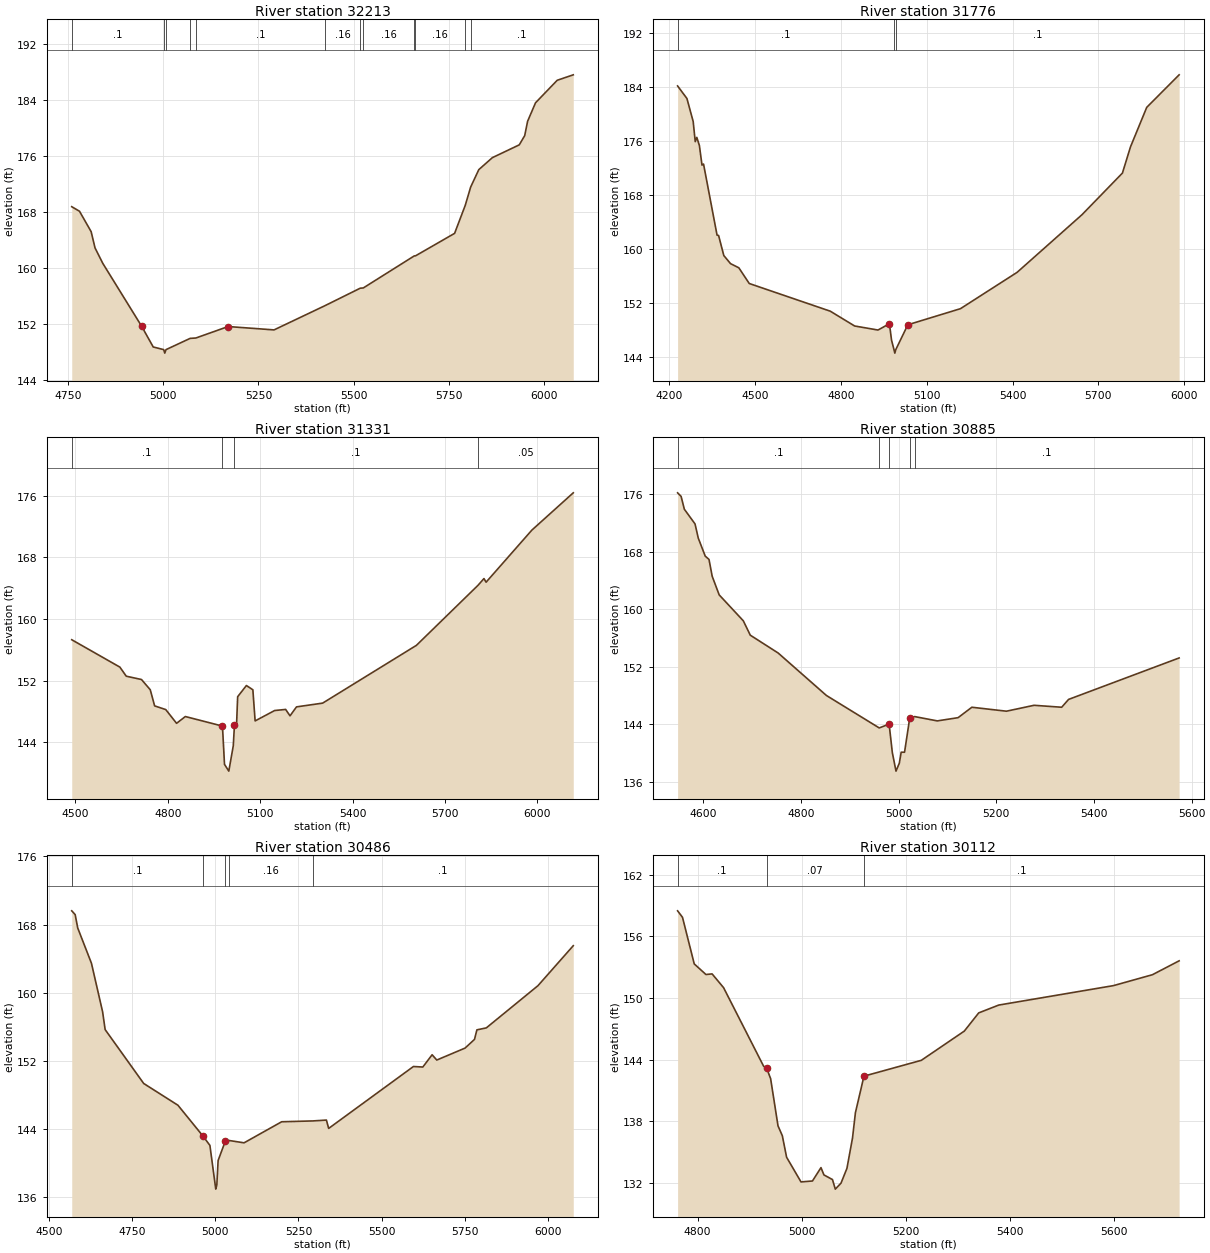
Type RM Length L Ch R = 1 ,32213   ,437,437,437
BEGIN DESCRIPTION:
UNT008 IN PECR 40.0
END DESCRIPTION:
XS GIS Cut Line= 3
      2326037.68     13271396.86      2325787.72     13271446.85
      2324987.74     13272146.84
#Sta/Elev= 30
  4759.5  168.77  4779.9  168.12  4810.5   165.2  4820.7  162.88    4841  160.68
    4943   151.7  4973.6  148.72  5001.2  148.34    5004  147.84  5007.2  148.34
  5070.7  149.95  5085.6     150  5170.5  151.64  5291.1  151.16  5425.2  154.63
  5517.6  157.12  5525.8  157.16  5659.7  161.74  5662.7  161.74  5765.6  164.96
  5793.6  168.97  5807.8  171.58  5829.2  174.07  5864.8  175.78  5935.5  177.61
  5949.8  178.93  5957.4  180.98  5978.2  183.62  6035.2  186.84  6077.4  187.62
#Mann= 12 ,-1 , 0
  4759.5      .1       0  5001.2     .07       0  5007.2      .1       0
  5070.7     .16       0  5085.6      .1       0  5425.2     .16       0
  5517.6      .1       0  5525.8     .16       0  5659.7      .1       0
  5662.7     .16       0  5793.6     .05       0  5807.8      .1       0
Bank Sta=4943,5170.5
XS Rating Curve= 0 ,0
Exp/Cntr=0.3,0.1

Type RM Length L Ch R = 1 ,31776   ,445,445,445
BEGIN DESCRIPTION:
UNT008 IN PECR 39.0
END DESCRIPTION:
XS GIS Cut Line= 3
       2326187.7     13270846.86      2325487.72     13271146.85
      2324787.73     13271846.85
#Sta/Elev= 30
  4230.4  184.21    4263  182.34  4284.8  178.93    4292  175.94  4297.5  176.57
  4306.5  175.36  4315.6  172.45    4321  172.61  4368.2  162.05  4373.6     162
  4391.8  159.02  4415.3  157.82  4444.3   157.2  4480.6  154.87  4763.5  150.76
  4848.7  148.56  4930.3  147.96  4970.2   148.9  4977.5  146.47  4986.2  145.03
    4989  144.53  4992.2  145.03  5034.4  148.74  5218.2  151.13  5416.2  156.53
  5642.5  165.08  5783.9  171.27  5812.2  175.18  5868.8  181.03  5981.9  185.86
#Mann= 3 ,-1 , 0
  4230.4      .1       0  4986.2     .07       0  4992.2      .1       0
Bank Sta=4970.2,5034.4
XS Rating Curve= 0 ,0
Exp/Cntr=0.3,0.1

Type RM Length L Ch R = 1 ,31331   ,446,446,446
BEGIN DESCRIPTION:
UNT008 IN PECR 38.0
END DESCRIPTION:
XS GIS Cut Line= 3
      2325737.74     13270346.83      2325387.72     13270746.85
      2324637.74     13271546.84
#Sta/Elev= 30
  4488.5   157.3  4644.7  153.75  4665.5  152.57  4714.9  152.14  4743.4  150.81
  4757.6  148.72  4793.7  148.24  4828.8  146.46  4857.3  147.34  4977.8   146.1
  4984.4  141.14  4998.4  140.26  5012.9  143.55  5016.7  146.21  5023.5  146.21
  5027.1  149.91  5055.5  151.36  5076.5  150.81  5083.8  146.77  5147.3  148.12
  5182.9  148.26  5197.1  147.43  5218.1  148.59  5303.1  149.08  5607.4  156.57
  5807.2  164.35  5826.7  165.23  5833.6  164.76  5982.1  171.51  6116.6  176.35
#Mann= 4 ,-1 , 0
  4488.5      .1       0  4977.8     .07       0  5016.7      .1       0
  5807.2     .05       0
Bank Sta=4977.8,5016.7
XS Rating Curve= 0 ,0
Exp/Cntr=0.3,0.1

Type RM Length L Ch R = 1 ,30885   ,399,399,399
BEGIN DESCRIPTION:
UNT008 IN PECR 37.0
END DESCRIPTION:
XS GIS Cut Line= 3
      2325487.75     13269996.82      2325187.72     13270346.85
      2324787.73     13270746.85
#Sta/Elev= 30
  4547.7  176.21  4554.9  175.71  4561.5  173.93  4583.4  171.88    4590  169.91
  4604.3   167.4    4612  166.94  4618.5   164.6  4632.8  162.01  4682.2   158.4
  4696.5   156.4  4753.5  153.92  4852.3  148.01  4960.5  143.49  4980.7  144.03
  4987.3  140.05  4994.8  137.48  5001.6  138.59  5005.4  140.11  5012.3  140.11
  5022.9  144.87    5033  145.07  5079.4  144.47  5121.9  144.92  5150.1  146.37
  5220.9  145.82  5277.4  146.64    5334  146.37  5348.1  147.46  5574.4  153.23
#Mann= 5 ,-1 , 0
  4547.7      .1       0  4960.5     .16       0  4980.7     .07       0
  5022.9     .16       0    5033      .1       0
Bank Sta=4980.7,5022.9
XS Rating Curve= 0 ,0
Exp/Cntr=0.3,0.1

Type RM Length L Ch R = 1 ,30486   ,374,374,374
BEGIN DESCRIPTION:
UNT008 IN PECR 36.0
END DESCRIPTION:
XS GIS Cut Line= 3
      2325387.71     13269896.86      2324987.72     13269996.85
      2324237.71     13270796.87
#Sta/Elev= 30
    4568  169.61  4578.3  169.17    4586   167.6  4627.3  163.46  4660.8  157.78
  4668.5  155.68  4784.5  149.36  4887.5  146.81  4962.3  143.22  4983.7   142.1
  5001.3  136.97  5004.5  137.47  5008.4  140.33  5029.9  142.58  5040.4  142.68
  5086.5   142.4  5199.6  144.87  5294.4  144.97  5334.2  145.07    5341  144.09
    5596  151.35  5624.3  151.29  5652.2  152.73  5666.3  152.11  5751.3  153.51
  5779.7  154.53    5787  155.65  5815.3  155.88  5970.7  160.83  6076.9  165.52
#Mann= 5 ,-1 , 0
    4568      .1       0  4962.3     .07       0  5029.9      .1       0
  5040.4     .16       0  5294.4      .1       0
Bank Sta=4962.3,5029.9
XS Rating Curve= 0 ,0
Exp/Cntr=0.3,0.1

Type RM Length L Ch R = 1 ,30112   ,180,180,180
BEGIN DESCRIPTION:
UNT008 IN PECR 35.0
END DESCRIPTION:
XS GIS Cut Line= 2
      2324771.14     13269598.55      2324323.45     13270452.29
#Sta/Elev= 30
  4761.6  158.47    4771  157.84  4793.6  153.31  4816.1  152.28  4827.9  152.34
    4850     151  4926.9  143.37  4932.6   143.2  4940.4  142.16  4954.6  137.57
  4962.9  136.61  4971.1  134.52  4998.8  132.12  5020.8  132.21  5037.2  133.51
  5042.9   132.8  5059.3  132.35  5064.7  131.42  5075.7     132  5087.1  133.44
  5097.8  136.39  5103.4  138.85  5119.8   142.4  5230.1  143.94  5312.7  146.78
  5340.4  148.55  5378.9  149.31  5599.4   151.2  5674.3  152.26  5725.6  153.61
#Mann= 3 , 0 , 0
  4761.6      .1       0  4932.6     .07       0  5119.8      .1       0
Bank Sta=4932.6,5119.8
XS Rating Curve= 0 ,0
Exp/Cntr=0.3,0.1

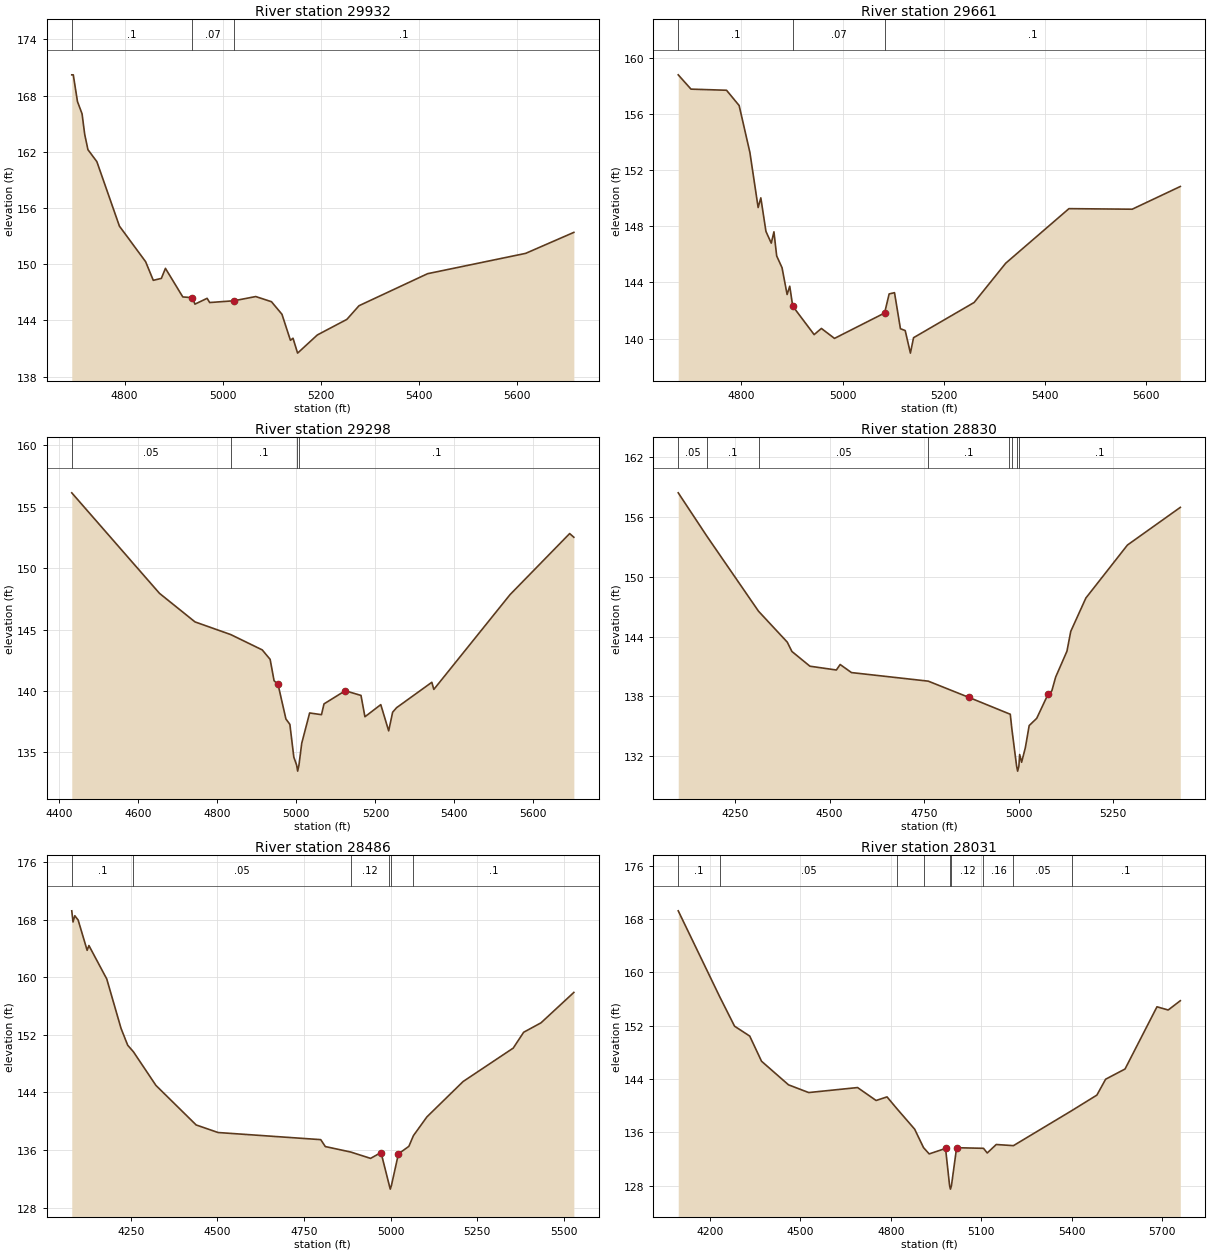
Type RM Length L Ch R = 1 ,29932   ,271,271,271
BEGIN DESCRIPTION:
Mapping XS 22dbf967
END DESCRIPTION:
XS GIS Cut Line= 2
      2324611.65     13269446.02      2324247.73     13270403.49
#Sta/Elev= 30
  4692.3  170.22  4695.4  170.22  4703.9  167.37  4713.3  166.06  4718.7  163.86
  4725.3  162.23  4743.5  160.95  4789.5  154.07    4843  150.27  4858.6  148.28
  4875.1  148.49  4883.4  149.56  4918.8  146.51  4938.3  146.43  4943.6  145.74
  4968.4  146.36  4973.7  145.91  5023.3   146.1  5067.6  146.55  5099.7     146
  5121.1  144.66  5138.4  141.88  5143.7   142.1    5153  140.51  5193.3  142.45
  5253.5  144.11  5278.3  145.57  5418.2  148.99  5618.3  151.16  5716.6   153.4
#Mann= 3 , 0 , 0
  4692.3      .1       0  4938.3     .07       0  5023.3      .1       0
#XS Ineff= 2 , 0
       0                 5098.41       0  145.96
Permanent Ineff=
       F       T
Bank Sta=4938.3,5023.3
XS Rating Curve= 0 ,0
Exp/Cntr=0.3,0.1

Type RM Length L Ch R = 1 ,29661   ,363,363,363
BEGIN DESCRIPTION:
UNT008 IN PECR 34.0
END DESCRIPTION:
XS GIS Cut Line= 2
      2324364.26     13269393.08      2324041.36     13270330.52
#Sta/Elev= 30
  4675.6   158.8  4700.8  157.78    4771   157.7  4795.9  156.61  4817.1  153.27
  4833.4  149.34  4838.7  150.03  4848.8  147.64  4859.3   146.8  4864.6  147.61
    4870  145.89  4880.6  145.05  4890.6  143.14  4895.8  143.73  4901.7  142.31
    4944  140.28  4958.3  140.72  4984.2  140.01  5083.1  141.82  5092.1  143.18
  5102.7  143.27  5114.4   140.7  5123.8  140.57  5134.1  138.96  5140.3  140.06
  5259.9  142.57  5322.3  145.37  5447.2  149.26  5572.1  149.22  5667.1  150.84
#Mann= 3 , 0 , 0
  4675.6      .1       0  4901.7     .07       0  5083.1      .1       0
#XS Ineff= 2 , 0
                         5104.55           142.7
Permanent Ineff=
       F       F
Bank Sta=4901.7,5083.1
XS Rating Curve= 0 ,0
Exp/Cntr=0.3,0.1

Type RM Length L Ch R = 1 ,29298   ,468,468,468
BEGIN DESCRIPTION:
UNT008 IN PECR 33.0
END DESCRIPTION:
XS GIS Cut Line= 3
       2323947.6     13269064.91      2323926.77     13269960.76
      2323848.32     13270327.27
#Sta/Elev= 30
  4431.4  156.14  4653.4  147.95  4743.4  145.62  4833.7  144.59  4913.5  143.34
  4933.5  142.57  4943.5  140.83  4953.5  140.53  4973.5  137.71  4983.5  137.27
  4993.5   134.6  5000.5  133.96  5003.2  133.46  5006.5  133.96  5013.5  135.73
  5033.5   138.2  5063.5  138.06  5069.9  138.94  5123.5  140.01  5163.5  139.63
  5173.5  137.89  5213.6  138.88  5233.6  136.74  5243.6  138.26  5253.6  138.63
  5342.8   140.7  5347.9  140.12  5540.7  147.84  5691.7  152.82  5702.3  152.52
#Mann= 4 ,-1 , 0
  4431.4     .05       0  4833.7      .1       0  5000.5     .07       0
  5006.5      .1       0
Bank Sta=4953.5,5123.5
XS Rating Curve= 0 ,0
Exp/Cntr=0.3,0.1

Type RM Length L Ch R = 1 ,28830   ,344,344,344
BEGIN DESCRIPTION:
UNT008 IN PECR 32.0
END DESCRIPTION:
XS GIS Cut Line= 3
       2323702.5     13269077.29      2323633.05      13269346.4
      2323615.69     13270396.73
#Sta/Elev= 30
  4099.3  158.43  4174.9  154.09  4311.7  146.55  4387.7  143.45    4400  142.51
  4447.7  141.03  4517.7  140.65  4527.7   141.2  4557.7  140.39  4760.9  139.53
  4867.7  137.91  4973.7  136.27  4977.8  136.21  4982.1  134.71  4994.6     131
  4997.3   130.5  5000.6     131  5002.6  132.17  5007.8  131.39  5017.8  132.87
  5027.8  135.07  5047.8   135.8  5077.8  138.22  5087.8  138.56  5097.8  139.93
  5127.8  142.54  5137.8  144.52  5177.8  147.87  5287.8  153.19  5427.7  156.97
#Mann= 8 ,-1 , 0
  4099.3     .05       0  4174.9      .1       0  4311.7     .05       0
  4760.9      .1       0  4973.7     .12       0  4982.1      .1       0
  4994.6     .07       0  5000.6      .1       0
Bank Sta=4867.7,5077.8
XS Rating Curve= 0 ,0
Exp/Cntr=0.3,0.1

Type RM Length L Ch R = 1 ,28486   ,455,455,455
BEGIN DESCRIPTION:
UNT008 IN PECR 31.0
END DESCRIPTION:
XS GIS Cut Line= 4
      2323453.78       13269049.      2323354.83     13269434.41
      2323281.91     13270163.57      2323307.95      13270481.3
#Sta/Elev= 30
  4079.8  169.22  4083.4  167.67  4088.6  168.54  4098.2  167.94  4124.2  163.74
  4129.3   164.4  4180.8  159.76  4222.1  152.89  4241.3  150.56  4257.8  149.65
  4322.8  144.98  4438.9  139.49  4502.1  138.44  4798.6  137.45  4811.8  136.49
  4885.2  135.73  4942.5  134.85  4972.6  135.66  4996.6  131.08  4999.3  130.58
  5002.6  131.08  5022.9  135.48    5053  136.52  5066.2  138.01  5105.1  140.61
  5209.6  145.52  5354.3  150.16  5384.4  152.36  5434.5  153.67  5529.3  157.89
#Mann= 6 ,-1 , 0
  4079.8      .1       0  4257.8     .05       0  4885.2     .12       0
  4996.6     .07       0  5002.6     .12       0  5066.2      .1       0
Bank Sta=4972.6,5022.9
XS Rating Curve= 0 ,0
Exp/Cntr=0.3,0.1

Type RM Length L Ch R = 1 ,28031   ,291,291,291
BEGIN DESCRIPTION:
UNT008 IN PECR 30.0
END DESCRIPTION:
XS GIS Cut Line= 4
      2323237.52     13268997.24      2322888.14     13269696.44
      2322834.75     13270052.77      2323153.49     13270468.51
#Sta/Elev= 30
    4095  169.23  4232.8  156.33  4281.9  151.93  4332.2  150.45  4371.3  146.68
  4460.8  143.14  4527.9  141.98    4690  142.73  4751.5  140.79  4787.7  141.33
  4821.7   139.5  4879.4  136.49  4908.9  133.72  4927.6  132.78  4981.9   133.6
  4995.4     128  4998.1   127.5  5001.4     128  5018.6  133.71  5107.8  133.62
  5120.2  132.92  5150.1  134.19  5207.2  134.02  5400.7  139.27    5484   141.6
    5513  143.98  5577.4  145.51  5683.4  154.84  5720.6  154.36  5760.8  155.75
#Mann= 9 ,-1 , 0
    4095      .1       0  4232.8     .05       0  4821.7     .16       0
  4908.9     .12       0  4995.4     .07       0  5001.4     .12       0
  5107.8     .16       0  5207.2     .05       0  5400.7      .1       0
Bank Sta=4981.9,5018.6
XS Rating Curve= 0 ,0
Exp/Cntr=0.3,0.1

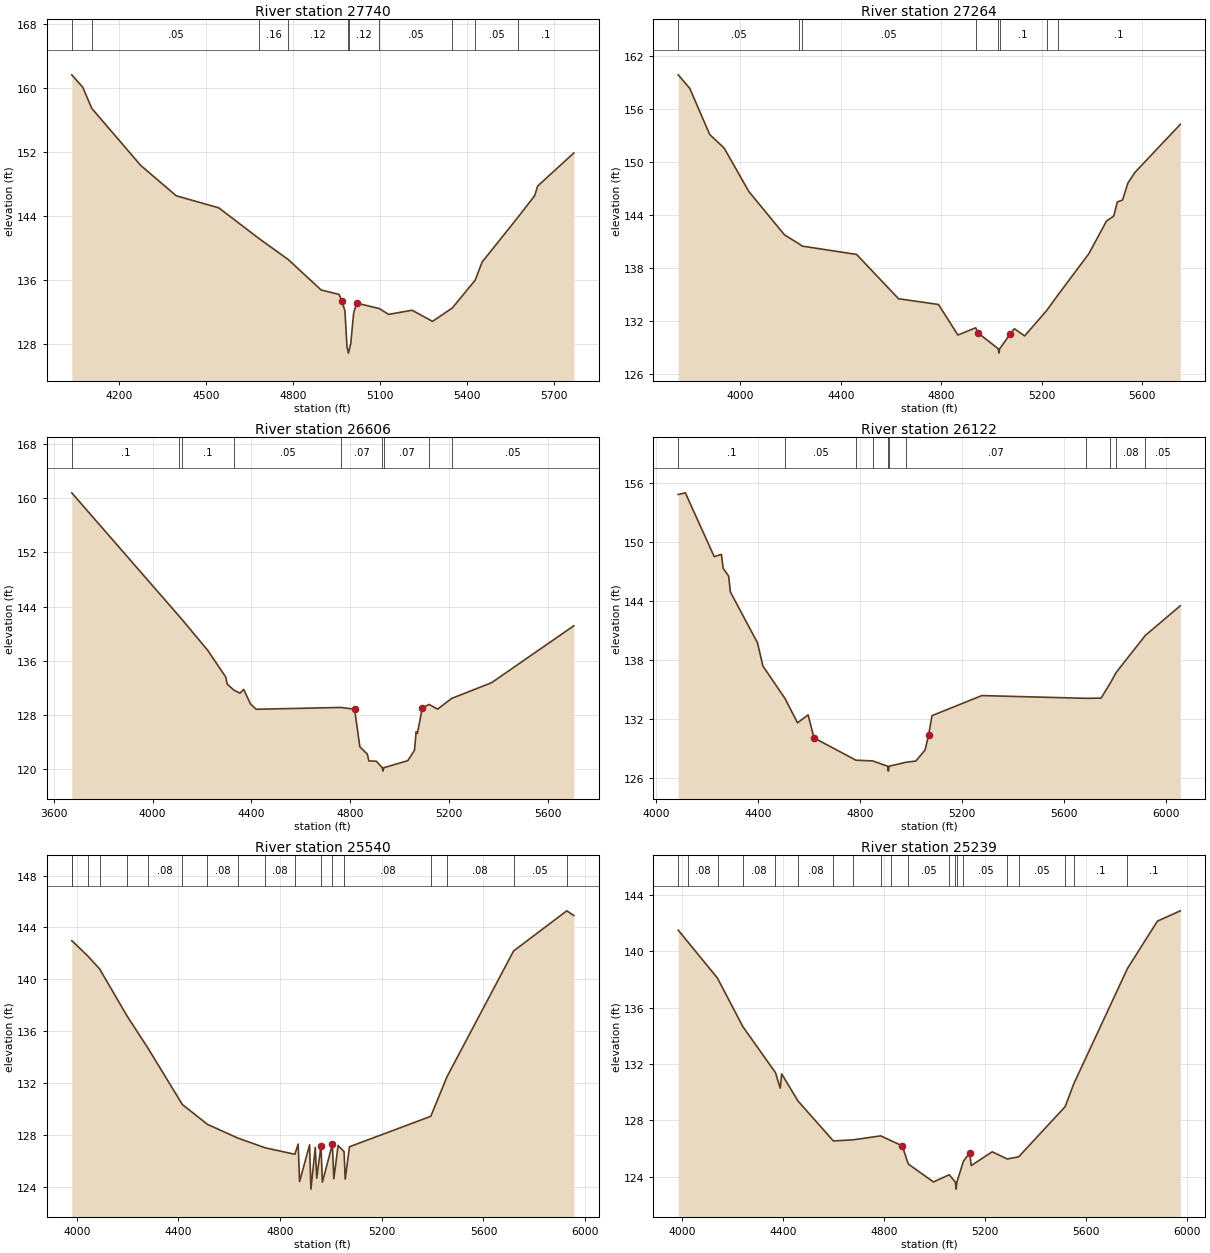
Type RM Length L Ch R = 1 ,27740   ,476,476,476
BEGIN DESCRIPTION:
UNT008 IN PECR 29.0
END DESCRIPTION:
XS GIS Cut Line= 3
      2322912.57     13268842.91      2322626.11     13269433.21
      2322504.58     13270500.88
#Sta/Elev= 30
  4037.6  161.69  4075.3  160.15  4106.7  157.49  4275.4  150.37  4397.7  146.58
  4544.4  145.07  4684.2  141.21    4784  138.61  4897.1  134.81  4959.1  134.26
  4969.1   133.4  4979.2   132.2  4986.6  127.58  4988.6  127.42  4991.4  126.92
  4994.6  127.42  4999.3  128.12  5009.4  131.94  5019.5  133.17  5097.4  132.49
  5130.2  131.76  5210.7  132.28  5281.1  130.89  5349.3  132.56  5428.3  136.04
  5452.2   138.3  5577.3  143.97  5633.4   146.6  5643.5  147.79  5768.3  151.93
#Mann= 10 ,-1 , 0
  4037.6      .1       0  4106.7     .05       0  4684.2     .16       0
    4784     .12       0  4988.6     .07       0  4994.6     .12       0
  5097.4     .05       0  5349.3      .1       0  5428.3     .05       0
  5577.3      .1       0
Bank Sta=4969.1,5019.5
XS Rating Curve= 0 ,0
Exp/Cntr=0.3,0.1

Type RM Length L Ch R = 1 ,27264   ,658,658,658
BEGIN DESCRIPTION:
UNT008 IN PECR 28.0
END DESCRIPTION:
XS GIS Cut Line= 4
      2322505.87     13268746.89      2322235.04     13269637.53
      2322110.04     13270215.66      2322406.92     13270590.67
#Sta/Elev= 30
  3752.4  159.87  3798.5  158.33  3877.8  153.11  3935.2  151.58  4033.8  146.65
  4175.7  141.75  4232.4  140.75  4246.5  140.47  4463.1  139.53  4630.3  134.51
  4789.5  133.86  4866.8   130.4  4937.8  131.22  4948.6   130.6  5027.5  128.85
  5030.3  128.35  5033.5  128.85  5074.7   130.5  5091.9  131.11  5132.8   130.3
  5220.6  133.18  5263.8  134.87  5388.3   139.6  5458.8   143.3  5487.7  143.87
  5502.1  145.47  5522.9  145.69  5544.2  147.61  5572.6  148.83  5753.1  154.26
#Mann= 8 ,-1 , 0
  3752.4     .05       0  4232.4     .16       0  4246.5     .05       0
  4937.8      .1       0  5027.5     .07       0  5033.5      .1       0
  5220.6     .05       0  5263.8      .1       0
Bank Sta=4948.6,5074.7
XS Rating Curve= 0 ,0
Exp/Cntr=0.3,0.1

Type RM Length L Ch R = 1 ,26606   ,484,484,484
BEGIN DESCRIPTION:
UNT008 IN PECR 27.0
END DESCRIPTION:
XS GIS Cut Line= 3
      2322287.73     13268646.84      2321587.72     13269746.85
      2321387.71     13270446.88
#Sta/Elev= 30
  3672.7  160.78  4106.2  142.64  4120.5  142.04    4223  137.56  4295.9  133.62
  4301.8  132.58    4329  131.69  4353.4  131.24  4368.7   131.8  4395.8  129.66
  4419.5  128.87  4761.7  129.14  4817.4  128.88  4838.6  123.34    4869  122.25
    4875  121.25  4905.4  121.21  4929.5  120.25  4932.3  119.75  4935.5  120.25
  5032.5  121.29  5059.8  122.83  5066.3  125.55  5071.5   125.3    5091  129.02
  5118.9  129.59  5153.4  128.89  5210.2  130.47  5371.8  132.79  5704.6  141.18
#Mann= 9 ,-1 , 0
  3672.7      .1       0  4106.2     .05       0  4120.5      .1       0
    4329     .05       0  4761.7     .07       0  4929.5     .07       0
  4935.5     .07       0  5118.9      .1       0  5210.2     .05       0
Bank Sta=4817.4,5091
XS Rating Curve= 0 ,0
Exp/Cntr=0.3,0.1

Type RM Length L Ch R = 1 ,26122   ,582,582,582
BEGIN DESCRIPTION:
UNT008 IN PECR 26.0
END DESCRIPTION:
XS GIS Cut Line= 5
      2322071.34     13268611.16      2321804.62      13268888.4
      2321379.93     13269456.99      2320811.34     13269800.96
      2320706.51     13269982.65
#Sta/Elev= 30
  4086.6  154.82  4114.4  154.99  4227.6  148.51  4255.9  148.73  4262.8  147.31
  4284.2  146.53  4291.1  144.91  4397.4  139.74  4418.5  137.39    4506  134.05
  4554.3  131.61  4595.9  132.42  4618.9  130.08  4783.5  127.81  4848.7  127.74
  4907.7   127.2  4910.5   126.7  4913.7   127.2  4979.6   127.6  5018.6  127.73
  5054.6  128.86  5068.5  130.39  5081.6  132.34  5277.1  134.38    5687   134.1
  5744.6  134.12  5781.1  135.67  5803.8  136.73  5917.9  140.49  6055.3  143.51
#Mann= 11 ,-1 , 0
  4086.6      .1       0    4506     .05       0  4783.5      .1       0
  4848.7     .05       0  4907.7     .07       0  4913.7     .05       0
  4979.6     .07       0    5687     .05       0  5781.1      .1       0
  5803.8     .08       0  5917.9     .05       0
Bank Sta=4618.9,5068.5
XS Rating Curve= 0 ,0
Exp/Cntr=0.3,0.1

Type RM Length L Ch R = 1 ,25540   ,301,301,301
BEGIN DESCRIPTION:
UNT008 IN PECR 25.0
END DESCRIPTION:
XS GIS Cut Line= 2
      2321508.37     13268205.54      2320633.38     13269976.36
#Sta/Elev= 30
  3980.2  142.97    3981  142.97  4042.9   141.8  4089.6   140.8  4198.2  137.15
  4278.5  134.73  4415.3  130.33  4514.1   128.8  4632.5  127.75  4741.1  126.99
  4857.9  126.49  4870.9  127.28  4876.5  124.38  4915.8  127.22  4921.1   123.8
  4938.2  127.02  4943.8  124.64  4960.6  127.15  4966.2  124.34  5005.5  127.27
  5011.1   124.6    5028  127.17  5051.5  126.69    5056  124.57  5072.8  127.07
  5392.6  129.42  5456.5  132.48  5718.3  142.18  5927.7  145.28  5955.4  144.92
#Mann= 18 ,-1 , 0
  3980.2     .08       0    3981      .1       0  4042.9     .08       0
  4089.6     .05       0  4198.2      .1       0  4278.5     .08       0
  4415.3     .05       0  4514.1     .08       0  4632.5     .05       0
  4741.1     .08       0  4857.9      .1       0  4960.6     .07       0
  5005.5      .1       0  5051.5     .08       0  5392.6     .07       0
  5456.5     .08       0  5718.3     .05       0  5927.7      .1       0
Bank Sta=4960.6,5005.5
XS Rating Curve= 0 ,0
Exp/Cntr=0.3,0.1

Type RM Length L Ch R = 1 ,25239   ,952,952,952
BEGIN DESCRIPTION:
UNT008 IN PECR 24.0
END DESCRIPTION:
XS GIS Cut Line= 2
      2321258.38     13268066.64      2320355.59     13269837.49
#Sta/Elev= 30
  3986.2   141.5  4023.2  140.69  4141.7  138.09  4241.7  134.66  4371.1  131.39
  4389.9  130.29  4395.6   131.3  4460.1  129.38  4600.4  126.54  4678.5  126.62
  4787.7   126.9  4829.8  126.55  4873.2  126.19    4897   124.9  4996.7  123.63
  5059.1  124.14  5083.4  123.62  5086.2  123.12  5089.4  123.62  5115.4  125.11
  5140.3   125.7  5145.9  124.79  5229.2  125.77  5288.5  125.26  5333.8  125.41
  5517.8  128.97  5552.3   130.6  5764.7  138.78  5883.4  142.14  5973.9  142.87
#Mann= 20 ,-1 , 0
  3986.2      .1       0  4023.2     .08       0  4141.7      .1       0
  4241.7     .08       0  4371.1      .1       0  4460.1     .08       0
  4600.4      .1       0  4678.5     .08       0  4787.7      .1       0
  4829.8     .12       0    4897     .05       0  5059.1     .12       0
  5083.4     .04       0  5089.4     .12       0  5115.4     .05       0
  5288.5     .12       0  5333.8     .05       0  5517.8     .12       0
  5552.3      .1       0  5764.7      .1       0
Bank Sta=4873.2,5140.3
XS Rating Curve= 0 ,0
Exp/Cntr=0.3,0.1