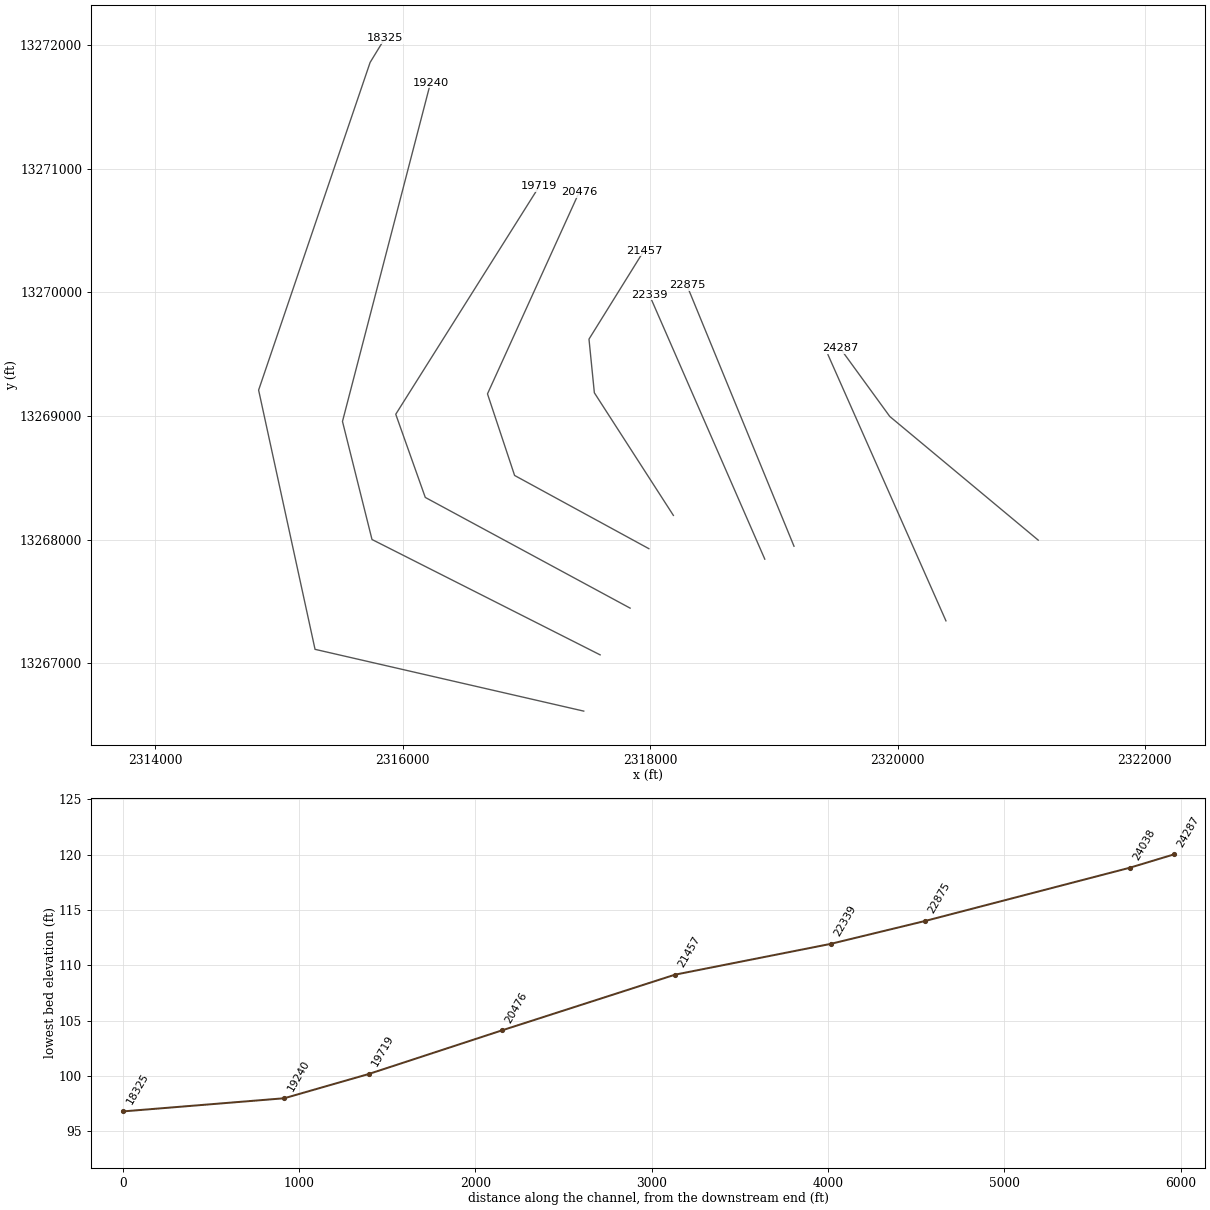
HEC-RAS study UNT008 IN PECR.prj: UNT008 IN PECR Base Level Engineering

--- UNT008 IN PECR.g01 (geometry) --- (continued)

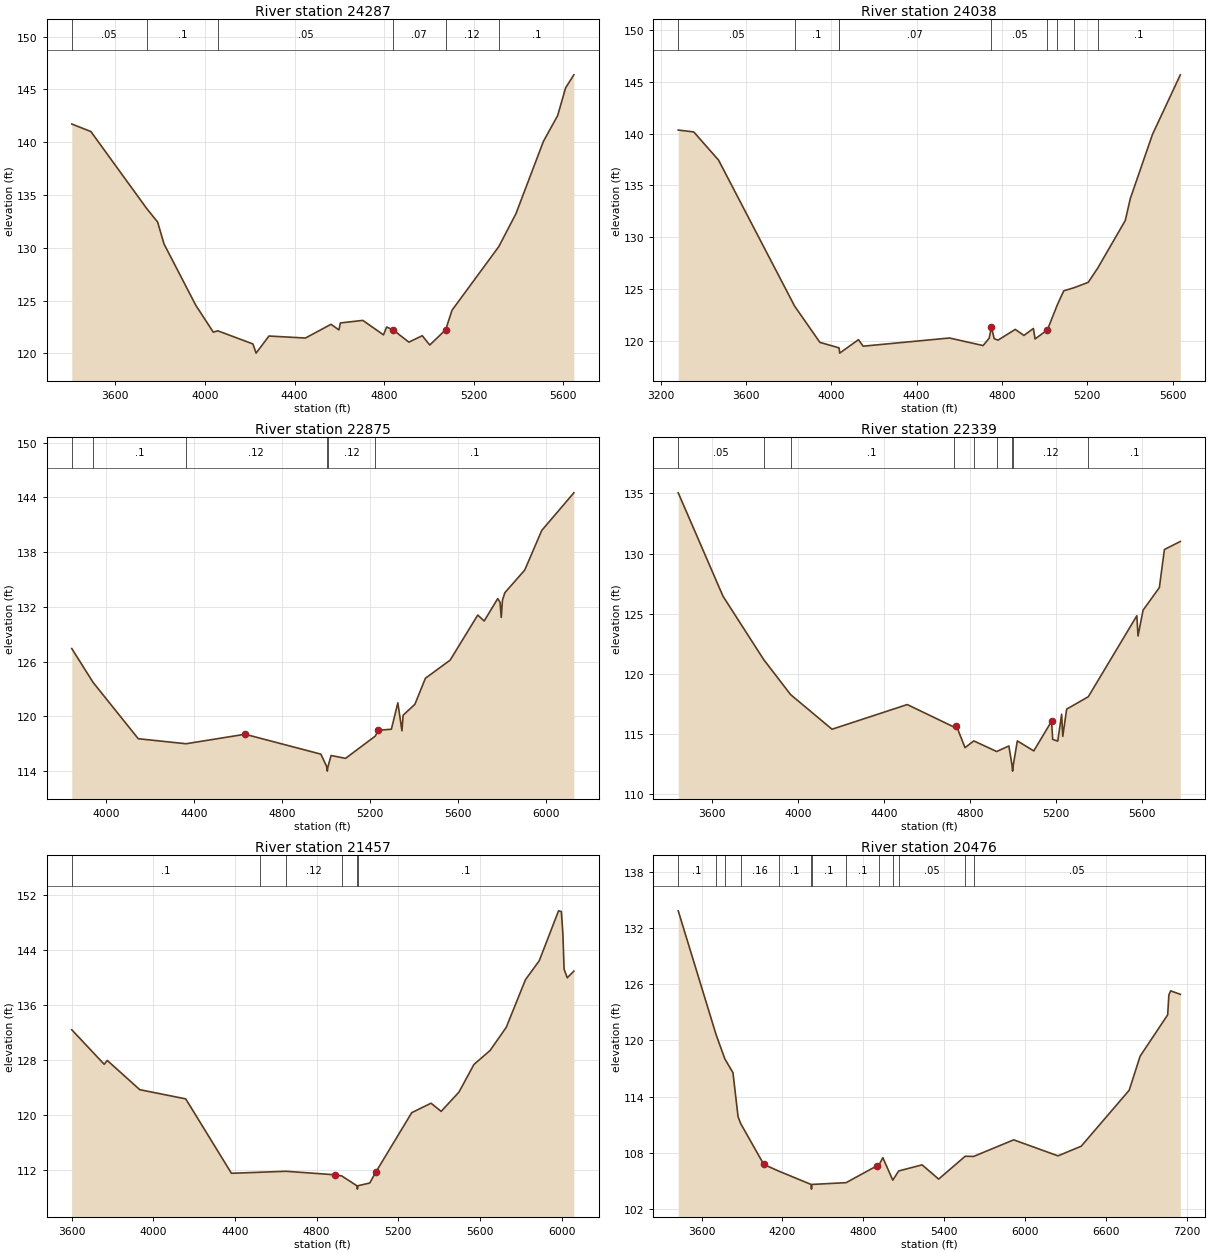
Type RM Length L Ch R = 1 ,24287   ,249,249,249
BEGIN DESCRIPTION:
UNT008 IN PECR 23.0
END DESCRIPTION:
XS GIS Cut Line= 3
      2321137.75     13267996.83      2319937.72     13268996.85
       2319537.7     13269546.88
#Sta/Elev= 30
  3405.2  141.72  3490.5  141.01  3740.5   133.7  3788.6  132.44  3817.2  130.36
  3959.1  124.55  4037.2  122.01  4057.8  122.13  4214.3  120.89  4228.3  120.02
  4285.8  121.64  4448.6  121.45  4563.1  122.75  4598.3  122.22  4604.8  122.88
    4705  123.12  4797.4  121.75  4811.1  122.49  4839.1  122.24  4910.7  121.06
  4970.4  121.67    5004  120.79  5075.1  122.24  5103.3  124.08  5312.2  130.11
  5388.9  133.23  5511.4  140.07  5575.1  142.52  5610.7  145.15  5647.4  146.38
#Mann= 6 ,-1 , 0
  3405.2     .05       0  3740.5      .1       0  4057.8     .05       0
  4839.1     .07       0  5075.1     .12       0  5312.2      .1       0
Bank Sta=4839.1,5075.1
XS Rating Curve= 0 ,0
Exp/Cntr=0.3,0.1

Type RM Length L Ch R = 1 ,24038   ,1163,1163,1163
BEGIN DESCRIPTION:
UNT008 IN PECR 22.0
END DESCRIPTION:
XS GIS Cut Line= 2
      2320391.62     13267343.98      2319437.74     13269496.82
#Sta/Elev= 30
  3281.7  140.35  3354.5  140.17  3470.8  137.45  3827.2  123.37    3946  119.86
  4033.9  119.34  4036.2  119.32  4038.9  118.82    4127  120.12  4148.9  119.49
  4553.6  120.28  4711.5  119.55  4740.2  120.27  4750.5  121.34  4763.5  120.22
  4781.3  120.07  4862.1  121.11  4903.2  120.53  4947.4   121.2  4955.2  120.19
    5013  121.06  5059.4  123.47  5089.6  124.83  5137.6  125.13  5204.4  125.65
  5248.6  127.01  5378.3  131.62  5401.6  133.72  5505.7  139.92  5636.4  145.68
#Mann= 9 ,-1 , 0
  3281.7     .05       0  3827.2      .1       0  4033.9     .05       0
  4036.2     .07       0  4750.5     .05       0    5013     .12       0
  5059.4      .1       0  5137.6     .12       0  5248.6      .1       0
Bank Sta=4750.5,5013
XS Rating Curve= 0 ,0
Exp/Cntr=0.3,0.1

Type RM Length L Ch R = 1 ,22875   ,536,536,536
BEGIN DESCRIPTION:
UNT008 IN PECR 20.0
END DESCRIPTION:
XS GIS Cut Line= 2
      2319163.02     13267947.45      2318297.44     13270056.64
#Sta/Elev= 30
  3844.3  127.43  3941.2  123.72  4146.3  117.55  4363.2     117  4631.3  118.04
  4975.5  115.86  5001.8   114.5  5004.6     114  5007.8   114.5  5021.9  115.71
  5087.6   115.4  5222.1  117.83  5236.9  118.48  5295.6  118.59    5325  121.48
  5343.6  118.42    5349  120.13  5402.4  121.32  5450.3  124.18  5562.5  126.16
  5687.8   131.1  5717.1  130.45  5778.5   132.9  5789.1   132.5  5794.5  130.84
  5800.1  132.74    5811  133.55  5901.2  136.03  5978.5  140.37  6124.2  144.49
#Mann= 6 ,-1 , 0
  3844.3     .05       0  3941.2      .1       0  4363.2     .12       0
  5001.8     .07       0  5007.8     .12       0  5222.1      .1       0
Bank Sta=4631.3,5236.9
XS Rating Curve= 0 ,0
Exp/Cntr=0.3,0.1

Type RM Length L Ch R = 1 ,22339   ,882,882,882
BEGIN DESCRIPTION:
UNT008 IN PECR 19.0
END DESCRIPTION:
XS GIS Cut Line= 2
      2318926.78     13267843.11      2317993.62      13269980.7
#Sta/Elev= 30
  3444.9  135.05  3652.9  126.46  3841.8   121.2  3966.8  118.29  4159.3  115.41
  4508.8  117.46  4724.1  115.61  4736.5  115.72  4777.2  113.88  4817.9  114.44
  4924.3  113.56  4980.9  114.02  4995.4  112.43  4998.2  111.93  5001.4  112.43
  5020.2  114.44  5096.6  113.61  5179.1  116.07  5184.5  114.57  5207.9  114.42
  5225.9  116.65  5231.3  114.82  5249.3  117.08  5349.9  118.11  5575.4  124.84
  5580.9  123.16  5604.3   125.3    5680  127.18  5703.4  130.34  5777.3  131.01
#Mann= 9 ,-1 , 0
  3444.9     .05       0  3841.8     .08       0  3966.8      .1       0
  4724.1     .12       0  4817.9      .1       0  4924.3     .12       0
  4995.4     .07       0  5001.4     .12       0  5349.9      .1       0
Bank Sta=4736.5,5179.1
XS Rating Curve= 0 ,0
Exp/Cntr=0.3,0.1

Type RM Length L Ch R = 1 ,21457   ,981,981,981
BEGIN DESCRIPTION:
UNT008 IN PECR 17.0
END DESCRIPTION:
XS GIS Cut Line= 4
      2318187.74     13268196.83      2317548.73     13269188.63
      2317505.32     13269622.65       2317950.2      13270338.8
#Sta/Elev= 30
  3600.9  132.37  3759.7  127.34  3774.9   127.9    3934  123.64  4159.1   122.3
  4382.9  111.46  4522.7  111.61  4650.4  111.75  4889.5  111.24  4922.8  111.08
    4997  109.65  4999.8  109.15    5003  109.65  5060.3  110.04  5090.5  111.65
    5266  120.29  5360.4  121.67  5410.2  120.48  5497.4  123.29  5570.6  127.31
  5649.7  129.35  5728.8  132.72  5823.3  139.68  5890.6  142.43  5985.1   149.7
  5998.9  149.59  6006.3  146.38  6012.2  141.21  6027.6  139.94    6060  140.91
#Mann= 6 ,-1 , 0
  3600.9      .1       0  4522.7     .08       0  4650.4     .12       0
  4922.8      .1       0    4997     .07       0    5003      .1       0
Bank Sta=4889.5,5090.5
XS Rating Curve= 0 ,0
Exp/Cntr=0.3,0.1

Type RM Length L Ch R = 1 ,20476   ,757,757,757
BEGIN DESCRIPTION:
UNT008 IN PECR 16.0
END DESCRIPTION:
XS GIS Cut Line= 4
      2317989.47     13267927.72      2316903.82     13268519.89
      2316684.58     13269179.94       2317426.5     13270812.18
#Sta/Elev= 30
  3426.6  133.82  3707.8  120.59  3772.5  118.02  3832.5  116.55  3870.5  111.86
  3889.5  111.13  4061.3  106.76  4172.8  106.04  4412.3  104.62  4415.1  104.12
  4418.3  104.62  4672.3  104.81  4902.4  106.62  4915.5  106.67  4944.6  107.48
  5018.5  105.08  5062.2  106.06    5236  106.71  5358.8  105.19  5555.7  107.63
  5618.3  107.61  5915.6  109.38    6244  107.67  6416.5   108.7  6772.4  114.67
  6853.7  118.31    7058  122.72  7066.8  124.84  7079.9  125.28  7151.7  124.91
#Mann= 13 ,-1 , 0
  3426.6      .1       0  3707.8     .16       0  3772.5      .1       0
  3889.5     .16       0  4172.8      .1       0  4412.3     .07       0
  4418.3      .1       0  4672.3      .1       0  4915.5     .08       0
  5018.5      .1       0  5062.2     .05       0  5555.7      .1       0
  5618.3     .05       0
Bank Sta=4061.3,4902.4
XS Rating Curve= 0 ,0
Exp/Cntr=0.3,0.1

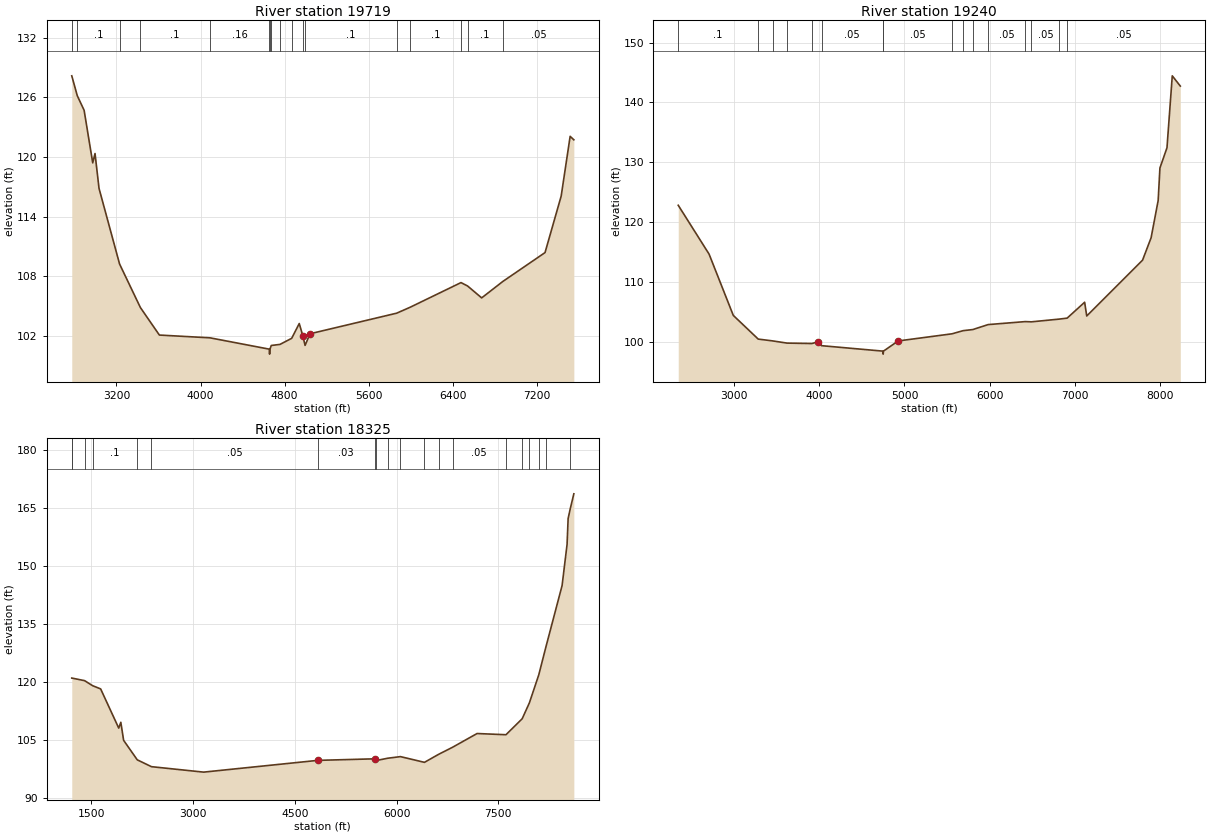
Type RM Length L Ch R = 1 ,19719   ,479,479,479
BEGIN DESCRIPTION:
UNT008 IN PECR 15.0
END DESCRIPTION:
XS GIS Cut Line= 4
      2317837.74     13267446.84      2316181.54     13268342.27
      2315942.82     13269015.01      2317103.27     13270858.71
#Sta/Elev= 30
  2775.3  128.18  2827.8  126.18  2892.8  124.71  2974.7  119.42  2996.5  120.36
  3034.6  116.85    3230  109.24  3427.9  104.86  3608.4  102.09  4090.2  101.81
    4654  100.67  4656.7  100.17    4660  100.67  4672.9  101.04    4756  101.15
  4866.8  101.76  4938.8  103.25  4972.2  102.04  4994.2  101.05  5041.4  102.22
    5865  104.29  5992.1  104.88  6477.3  107.37  6539.5  107.03  6673.8  105.83
  6875.8  107.49  7276.4  110.39    7430  116.08  7515.2  122.09  7550.4  121.74
#Mann= 17 ,-1 , 0
  2775.3     .16       0  2827.8      .1       0    3230     .16       0
  3427.9      .1       0  4090.2     .16       0    4654     .07       0
    4660     .16       0  4672.9      .1       0    4756     .16       0
  4866.8      .1       0  4972.2     .05       0  4994.2      .1       0
    5865     .05       0  5992.1      .1       0  6477.3     .05       0
  6539.5      .1       0  6875.8     .05       0
Bank Sta=4972.2,5041.4
XS Rating Curve= 0 ,0
Exp/Cntr=0.3,0.1

Type RM Length L Ch R = 1 ,19240   ,915,915,915
BEGIN DESCRIPTION:
UNT008 IN PECR 2.0
END DESCRIPTION:
XS GIS Cut Line= 4
      2317595.36     13267068.79      2315750.74     13268001.95
      2315512.03     13268956.81      2316224.49     13271698.07
#Sta/Elev= 30
  2348.9  122.83  2710.3  114.68  2994.4  104.44  3286.3  100.49  3454.5  100.19
  3623.4   99.82  3914.5   99.75  3991.5  100.03    4029   99.39    4748   98.48
  4750.8   97.98    4754   98.48  4926.3  100.18  5557.1  101.37  5688.2   101.9
  5800.4  102.08  5980.5  102.91  6415.5  103.41  6487.9  103.37  6815.6  103.83
  6906.4  103.99  7111.5  106.64  7136.2  104.35  7790.4  113.67  7890.5  117.41
  7973.1  123.62  7993.8  129.05  8076.5  132.43  8138.5  144.44  8232.7  142.73
#Mann= 16 ,-1 , 0
  2348.9      .1       0  3286.3     .16       0  3454.5      .1       0
  3623.4     .16       0  3914.5      .1       0    4029     .05       0
    4748     .04       0    4754     .05       0  5557.1      .1       0
  5688.2     .05       0  5800.4      .1       0  5980.5     .05       0
  6415.5      .1       0  6487.9     .05       0  6815.6      .1       0
  6906.4     .05       0
Bank Sta=3991.5,4926.3
XS Rating Curve= 0 ,0
Exp/Cntr=0.3,0.1

Type RM Length L Ch R = 1 ,18325   ,0,0,0
BEGIN DESCRIPTION:
UNT008 IN PECR 1.0
END DESCRIPTION:
XS GIS Cut Line= 5
      2317462.92     13266613.81       2315290.2     13267113.53
      2314833.92     13269210.24      2315735.61     13271860.99
       2315855.1     13272056.52
#Sta/Elev= 30
    1211  121.11  1211.2  121.11  1400.2  120.44  1517.2  119.15    1637   118.3
  1903.8  108.17  1934.6  109.67  1975.7  105.01  2176.9   99.97  2386.1    98.2
  3155.4   96.79  4840.1   99.83  5679.3  100.23  5702.2   99.79    5873  100.39
    6058   100.8  6412.2   99.32    6623  101.41  6825.8  103.21  7188.2  106.77
  7614.5  106.46  7853.5  110.59  7959.9  114.71  8098.3  121.95  8203.7  129.18
    8442  145.03  8515.5  155.69  8530.9  162.34  8562.5  164.89  8615.3  168.74
#Mann= 20 ,-1 , 0
    1211     .16       0  1211.2      .1       0  1400.2     .16       0
  1517.2      .1       0  2176.9     .16       0  2386.1     .05       0
  4840.1     .03       0  5679.3     .05       0  5702.2      .1       0
    5873     .05       0    6058      .1       0  6412.2      .1       0
    6623     .05       0  6825.8     .05       0  7614.5      .1       0
  7853.5      .1       0  7959.9     .05       0  8098.3     .08       0
  8203.7     .05       0  8562.5      .1       0
Bank Sta=4840.1,5679.3
XS Rating Curve= 0 ,0
Exp/Cntr=0.3,0.1

Chan Stop Cuts=-1
Use User Specified Reach Order=0
Composite Channel Slope=5