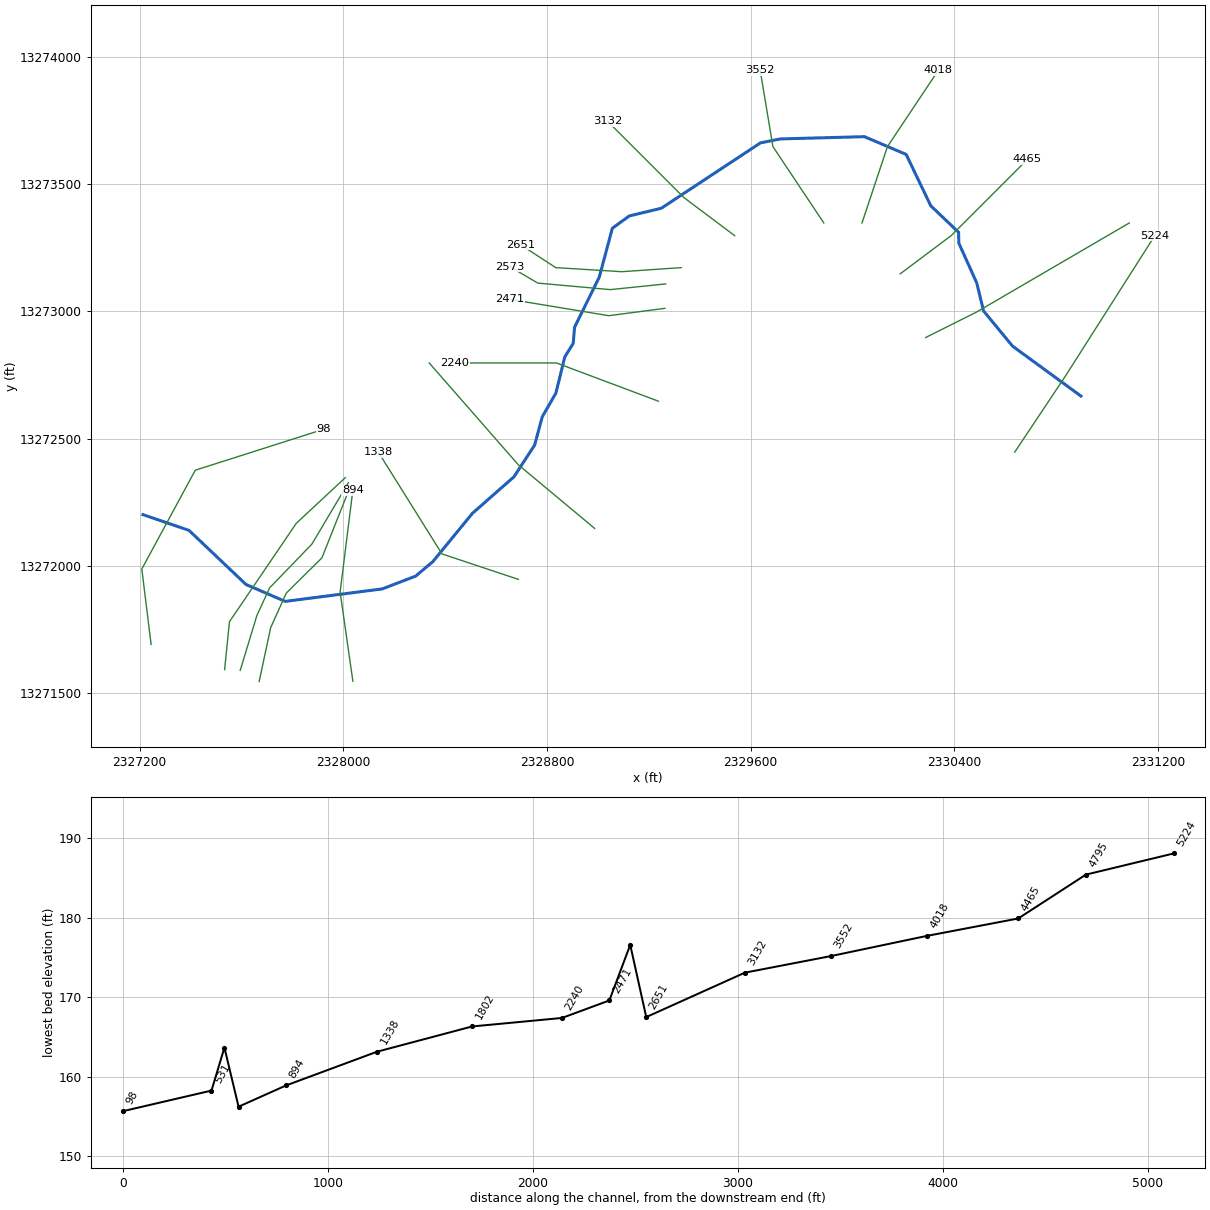
--- UNT009 IN PECR.prj (project) ---

Proj Title=UNT009 IN PECR Base Level Engineering
Current Plan=p01
Default Exp/Contr=0.3,0.1
English Units
Geom File=g01
Flow File=f01
Plan File=p01
Y Axis Title=Elevation
X Axis Title(PF)=Main Channel Distance
X Axis Title(XS)=Station
BEGIN DESCRIPTION:
UNT009 IN PECR
END DESCRIPTION:
DSS Export Rating Curves= 0
DSS Export Rating Curve Sorted= 0
DSS Export Volume Flow Curves= 0
DXF OffsetX= 0
DXF OffsetY= 0
DXF ScaleX= 1
DXF ScaleY= 10

--- UNT009 IN PECR.p01 (plan) ---

Plan Title=Multiple Run
Short Identifier=Multiple
Geom File=g01
Flow File=f01
Subcritical Flow
K Sum by GR= 0
Std Step Tol= 0.01
Critical Tol= 0.01
Num of Std Step Trials= 20
Max Error Tol= 0.3
Flow Tol Ratio= 0.001
Split Flow NTrial= 30
Split Flow Tol= 0.02
Split Flow Ratio= 0.02
Log Output Level= 0
Friction Slope Method= 1
Unsteady Friction Slope Method= 2
Unsteady Bridges Friction Slope Method= 1
Parabolic Critical Depth
Global Vel Dist=  1 , 1 , 1
Global Log Level= 0
CheckData=True
Encroach Param= -1, 0, 0, 0
BEGIN DESCRIPTION:
Multiple Run
END DESCRIPTION:

--- UNT009 IN PECR.f01 (steady flow) ---

Flow Title=Multiple
Program Version=4.10
Number of Profiles= 7
Profile Names=10-year,25-year,50-year,1pct_min,100-year,1pct_plu,500-year
River Rch & RM=UNT009 IN PECR,Reach-1         ,5224
     597     833    1028     925    1251    1692    1861
Boundary for River Rch & Prof#=UNT009 IN PECR,Reach-1         , 1
Up Type= 0
Dn Type= 3
Dn Slope=0.005
Boundary for River Rch & Prof#=UNT009 IN PECR,Reach-1         , 2
Up Type= 0
Dn Type= 3
Dn Slope=0.005
Boundary for River Rch & Prof#=UNT009 IN PECR,Reach-1         , 3
Up Type= 0
Dn Type= 3
Dn Slope=0.005
Boundary for River Rch & Prof#=UNT009 IN PECR,Reach-1         , 4
Up Type= 0
Dn Type= 3
Dn Slope=0.005
Boundary for River Rch & Prof#=UNT009 IN PECR,Reach-1         , 5
Up Type= 0
Dn Type= 3
Dn Slope=0.005
Boundary for River Rch & Prof#=UNT009 IN PECR,Reach-1         , 6
Up Type= 0
Dn Type= 3
Dn Slope=0.005
Boundary for River Rch & Prof#=UNT009 IN PECR,Reach-1         , 7
Up Type= 0
Dn Type= 3
Dn Slope=0.005
DSS Import GetInterval= 0
DSS Import GetPeak= 0
DSS Import FillOption= 0

--- UNT009 IN PECR.g01 (geometry) ---

Geom Title=Existing Conditions

River Reach=UNT009 IN PECR,Reach-1
Reach XY= 30
      2330897.72     13272666.86      2330628.99     13272863.10
      2330515.27     13273001.12      2330488.36     13273111.37
      2330418.05     13273267.62      2330417.18     13273310.15
      2330307.81     13273414.32      2330211.16     13273616.07
      2330047.24     13273685.79      2329717.54     13273676.96
      2329639.41     13273661.71      2329249.65     13273404.77
      2329123.78     13273374.39      2329057.14     13273326.28
      2329005.57     13273133.79      2328908.47     13272937.00
      2328903.41     13272873.90      2328870.44     13272821.08
      2328835.05     13272677.96      2328781.62     13272585.24
      2328751.77     13272474.33      2328670.39     13272349.53
      2328507.79     13272206.71      2328351.63     13272016.15
      2328284.08     13271959.49      2328153.34     13271909.38
      2327772.00     13271860.35      2327618.03     13271926.71
      2327394.07     13272139.28      2327213.47     13272201.05

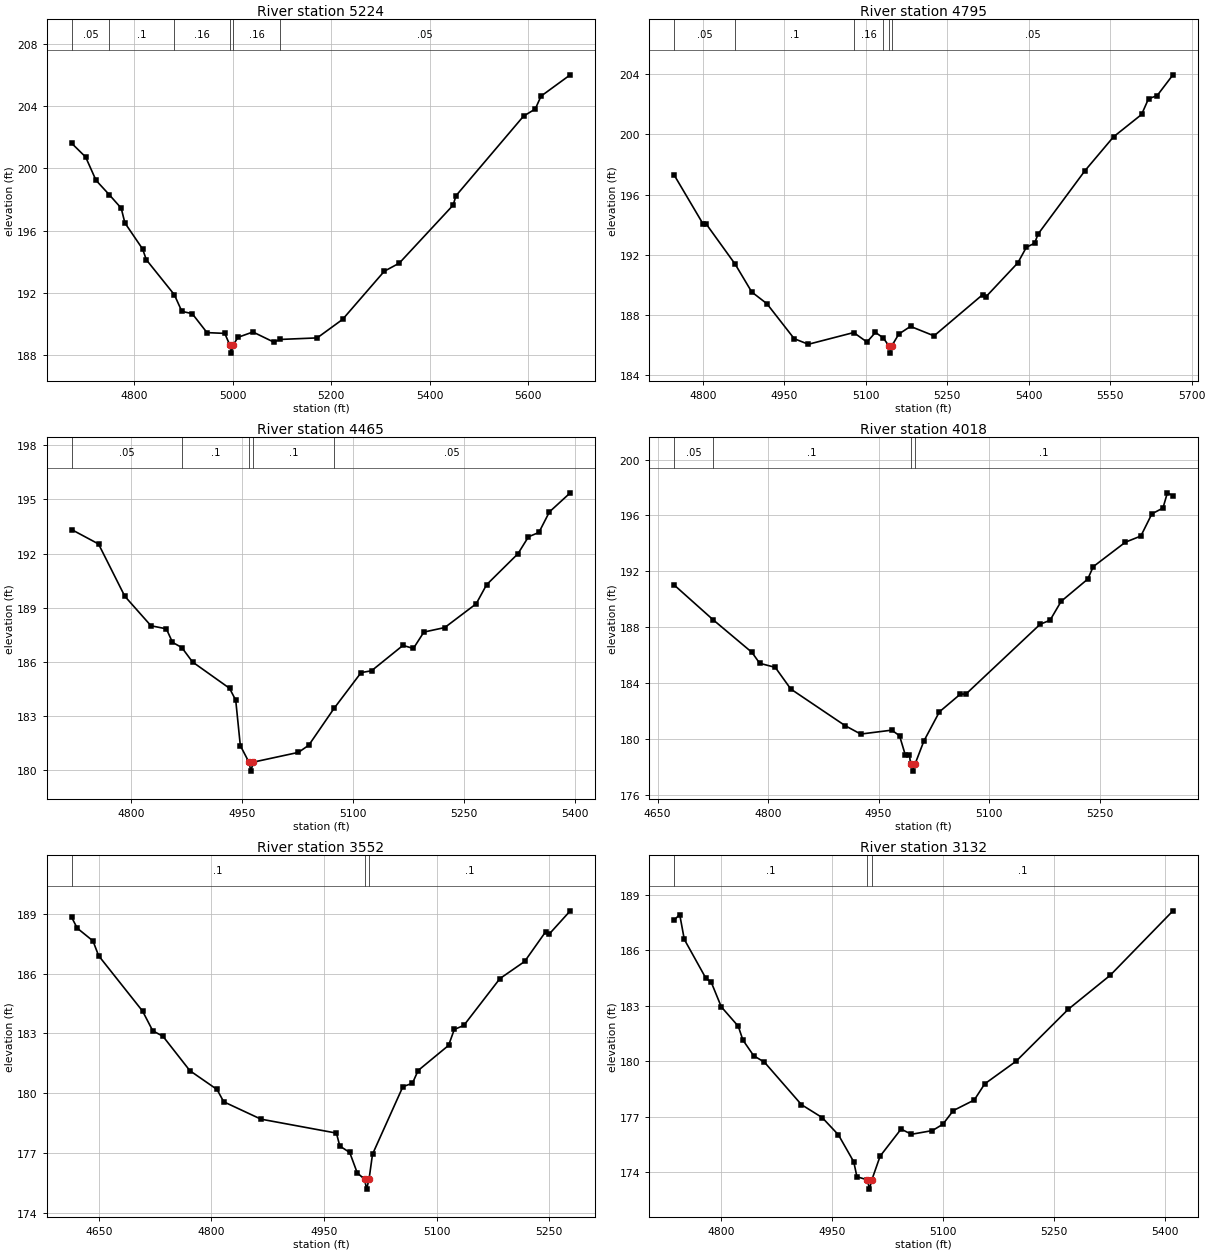
Type RM Length L Ch R = 1,5224,429,429,429
BEGIN DESCRIPTION:
UNT009 IN PECR 12.0
END DESCRIPTION:
XS GIS Cut Line= 3
      2330637.72     13272446.86      2330837.72     13272746.85
      2331187.74     13273296.88
#Sta/Elev= 30
  4673.2  201.62  4701.7  200.73  4722.8  199.23  4749.8  198.30  4773.9  197.44
  4781.4  196.49  4817.4  194.81  4824.9  194.12  4881.8  191.87  4897.0  190.80
  4918.1  190.65  4948.1  189.43  4984.2  189.38  4994.7  188.61  4997.4  188.11
  5000.7  188.61  5011.2  189.13  5041.4  189.47  5083.7  188.82  5096.2  188.99
  5171.8  189.09  5223.4  190.28  5308.1  193.38  5338.5  193.90  5447.8  197.63
  5453.7  198.24  5590.8  203.36  5614.6  203.82  5626.4  204.65  5685.7  206.02
#Mann=6,-1,0
  4673.2    0.05       0  4749.8     0.1       0  4881.8    0.16       0
  4994.7    0.07       0  5000.7    0.16       0  5096.2    0.05       0
Bank Sta=4994.7,5000.7
Exp/Cntr=0.3,0.1

Type RM Length L Ch R = 1,4795,330,330,330
BEGIN DESCRIPTION:
UNT009 IN PECR 11.0
END DESCRIPTION:
XS GIS Cut Line= 3
      2330287.71     13272896.85      2330487.72     13272996.85
      2331087.68     13273346.83
#Sta/Elev= 30
  4747.4  197.28  4800.5  194.03  4806.1  194.04  4859.5  191.36  4890.0  189.51
  4917.9  188.73  4968.2  186.40  4994.2  186.03  5077.7  186.81  5102.1  186.18
  5117.8  186.82  5132.2  186.45  5142.1  185.94  5144.8  185.44  5148.1  185.94
  5160.8  186.71  5182.3  187.22  5225.7  186.59  5315.4  189.34  5321.2  189.19
  5379.9  191.45  5395.7  192.49  5410.9  192.76  5417.2  193.37  5503.6  197.59
  5556.1  199.84  5607.8  201.33  5620.6  202.38  5636.3  202.58  5665.6  203.97
#Mann=6,-1,0
  4747.4    0.05       0  4859.5     0.1       0  5077.7    0.16       0
  5132.2    0.05       0  5142.1    0.07       0  5148.1    0.05       0
Bank Sta=5142.1,5148.1
Exp/Cntr=0.3,0.1

Type RM Length L Ch R = 1,4465,447,447,447
BEGIN DESCRIPTION:
UNT009 IN PECR 10.0
END DESCRIPTION:
XS GIS Cut Line= 3
      2330187.73     13273146.86      2330387.72     13273296.85
      2330687.69     13273596.82
#Sta/Elev= 30
  4719.7  193.33  4756.1  192.53  4791.6  189.63  4827.0  187.99  4847.8  187.82
  4856.1  187.07  4868.7  186.78  4883.2  185.98  4933.2  184.52  4941.6  183.86
  4947.8  181.34  4959.4  180.42  4962.1  179.92  4965.4  180.42  5026.3  180.96
  5040.4  181.36  5074.5  183.40  5111.1  185.39  5125.2  185.49  5167.7  186.90
  5181.8  186.73  5196.0  187.64  5224.2  187.89  5266.7  189.21  5280.8  190.27
  5323.2  191.99  5337.4  192.93  5351.5  193.17  5365.7  194.31  5393.9  195.37
#Mann=5,-1,0
  4719.7    0.05       0  4868.7     0.1       0  4959.4    0.07       0
  4965.4     0.1       0  5074.5    0.05       0
Bank Sta=4959.4,4965.4
Exp/Cntr=0.3,0.1

Type RM Length L Ch R = 1,4018,466,466,466
BEGIN DESCRIPTION:
UNT009 IN PECR 9.0
END DESCRIPTION:
XS GIS Cut Line= 3
      2330037.73     13273346.88      2330137.72     13273646.85
      2330337.74     13273946.89
#Sta/Elev= 30
  4672.8  191.02  4725.3  188.55  4778.2  186.21  4788.7  185.43  4809.8  185.14
  4830.9  183.59  4904.7  180.97  4925.8  180.37  4967.9  180.65  4978.5  180.25
  4986.4  178.86  4992.0  178.86  4993.5  178.22  4996.3  177.72  4999.5  178.22
  5011.5  179.87  5032.6  181.96  5061.1  183.23  5068.6  183.23  5169.3  188.22
  5182.8  188.51  5197.8  189.86  5233.9  191.45  5241.4  192.34  5285.0  194.09
  5306.0  194.53  5321.0  196.12  5336.0  196.53  5342.0  197.62  5349.6  197.41
#Mann=4,-1,0
  4672.8    0.05       0  4725.3     0.1       0  4993.5    0.07       0
  4999.5     0.1       0
Bank Sta=4993.5,4999.5
Exp/Cntr=0.3,0.1

Type RM Length L Ch R = 1,3552,420,420,420
BEGIN DESCRIPTION:
UNT009 IN PECR 8.0
END DESCRIPTION:
XS GIS Cut Line= 3
      2329887.71     13273346.86      2329687.72     13273646.85
      2329637.72     13273946.87
#Sta/Elev= 30
  4613.6  188.83  4621.1  188.28  4642.1  187.64  4649.6  186.90  4708.2  184.12
  4721.8  183.13  4735.3  182.86  4771.3  181.13  4807.4  180.19  4816.4  179.57
  4866.0  178.70  4966.6  178.00  4971.1  177.35  4984.3  177.03  4994.4  176.00
  5004.1  175.69  5006.8  175.19  5010.1  175.69  5014.7  176.94  5055.2  180.33
  5067.9  180.50  5075.5  181.14  5116.1  182.40  5123.7  183.20  5136.4  183.40
  5184.5  185.75  5217.5  186.61  5245.3  188.09  5250.4  187.99  5278.3  189.15
#Mann=3,-1,0
  4613.6     0.1       0  5004.1    0.07       0  5010.1     0.1       0
Bank Sta=5004.1,5010.1
Exp/Cntr=0.3,0.1

Type RM Length L Ch R = 1,3132,481,481,481
BEGIN DESCRIPTION:
UNT009 IN PECR 7.0
END DESCRIPTION:
XS GIS Cut Line= 3
      2329537.72     13273296.85      2329337.72     13273446.85
      2329037.70     13273746.88
#Sta/Elev= 30
  4736.6  187.63  4743.9  187.92  4750.1  186.58  4779.3  184.48  4786.6  184.26
  4800.1  182.94  4823.1  181.89  4829.3  181.15  4843.9  180.30  4858.5  179.95
  4908.5  177.66  4936.6  176.96  4958.5  176.03  4979.3  174.57  4983.5  173.77
  4997.7  173.60  5000.5  173.10  5003.7  173.60  5014.9  174.88  5043.2  176.34
  5057.3  176.06  5085.6  176.26  5099.7  176.60  5113.9  177.34  5142.2  177.91
  5156.3  178.78  5198.7  180.00  5269.4  182.81  5326.0  184.64  5410.9  188.12
#Mann=3,-1,0
  4736.6     0.1       0  4997.7    0.07       0  5003.7     0.1       0
Bank Sta=4997.7,5003.7
Exp/Cntr=0.3,0.1

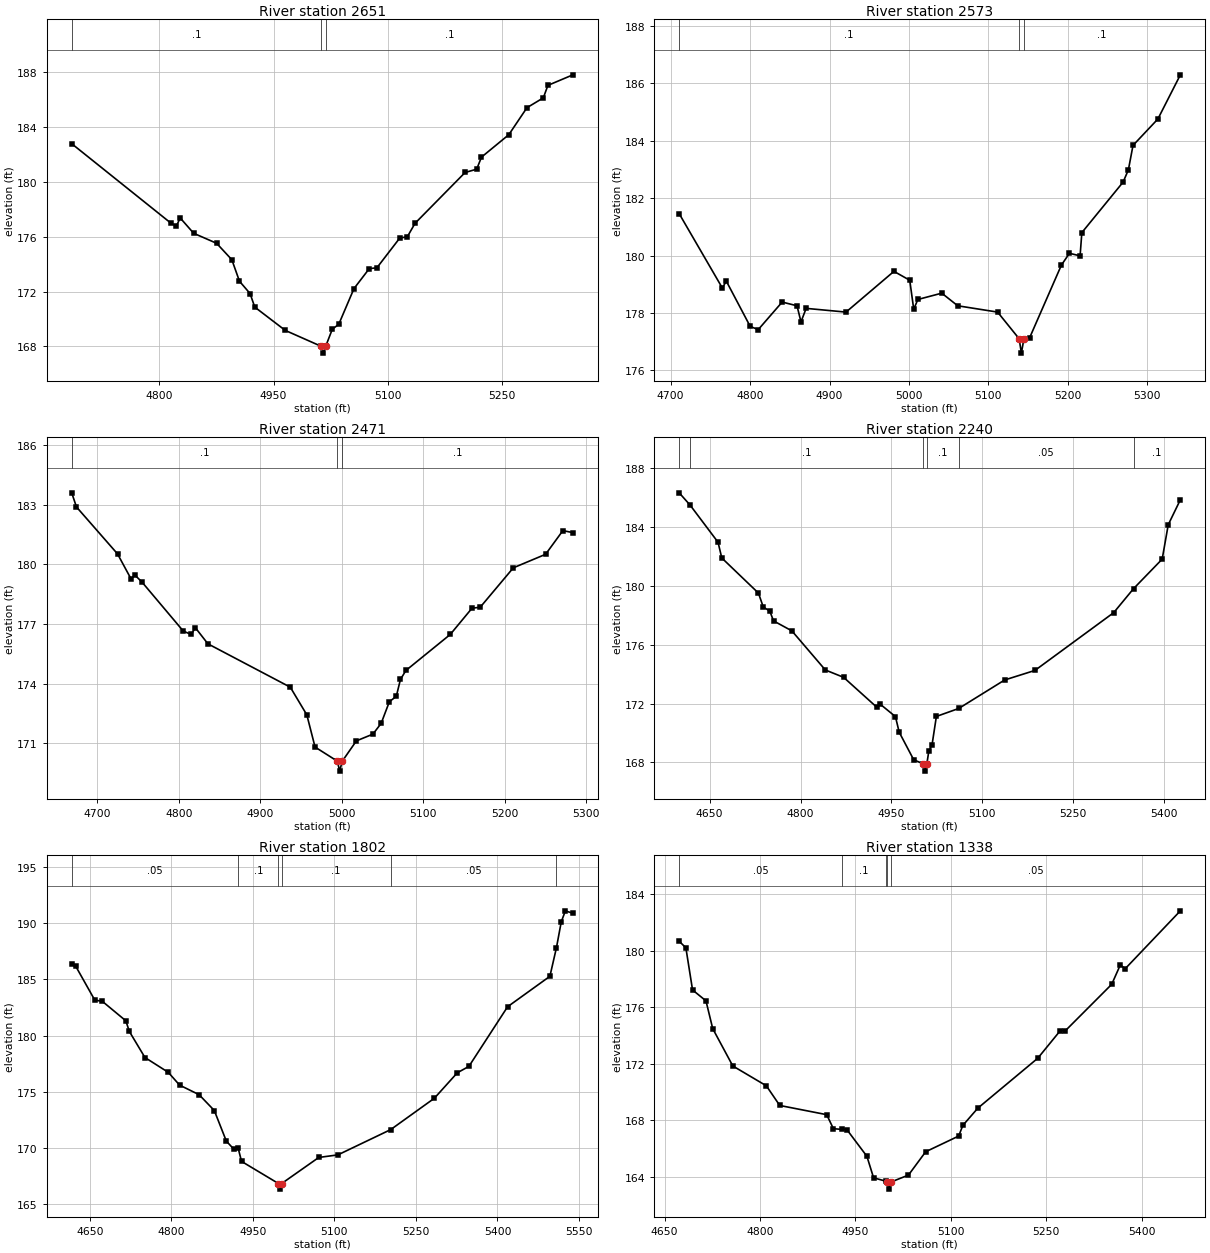
Type RM Length L Ch R = 1,2651,78,78,78
BEGIN DESCRIPTION:
Mapping XS bd256952
END DESCRIPTION:
XS GIS Cut Line= 4
      2329327.43     13273171.40      2329093.90     13273155.41
      2328834.75     13273171.40      2328697.16     13273260.99
#Sta/Elev= 30
  4685.0  182.80  4815.0  177.01  4822.4  176.79  4827.4  177.38  4845.1  176.26
  4875.2  175.53  4895.2  174.33  4905.2  172.76  4919.1  171.86  4925.3  170.87
  4965.3  169.17  5012.4  168.01  5015.2  167.51  5018.4  168.01  5027.1  169.26
  5035.5  169.61  5055.5  172.22  5075.6  173.68  5085.6  173.74  5115.6  175.91
  5125.6  176.01  5135.7  176.99  5201.4  180.70  5216.6  180.94  5222.9  181.82
  5258.8  183.46  5282.6  185.43  5304.1  186.15  5310.1  187.06  5342.9  187.83
#Mann=3,-1,0
  4685.0     0.1       0  5012.4    0.07       0  5018.4     0.1       0
Bank Sta=5012.4,5018.4
Exp/Cntr=0.3,0.1

Type RM Length L Ch R = 1,2573,102,102,102
BEGIN DESCRIPTION:
UNT009 IN PECR 6.0
END DESCRIPTION:
XS GIS Cut Line= 4
      2329266.66     13273107.41      2329049.11     13273085.02
      2328764.36     13273110.61      2328655.58     13273174.60
#Sta/Elev= 30
  4710.8  181.46  4765.1  178.87  4770.1  179.11  4800.2  177.53  4810.3  177.42
  4840.4  178.38  4859.1  178.25  4864.1  177.69  4870.6  178.16  4920.8  178.03
  4981.1  179.45  5001.0  179.14  5006.0  178.13  5011.2  178.47  5041.3  178.69
  5061.4  178.25  5111.6  178.03  5138.7  177.10  5141.5  176.60  5144.7  177.10
  5151.8  177.13  5191.9  179.67  5202.0  180.08  5215.4  179.99  5217.6  180.80
  5269.5  182.56  5276.2  182.99  5282.0  183.84  5313.3  184.76  5341.6  186.30
#Mann=3,-1,0
  4710.8     0.1       0  5138.7    0.07       0  5144.7     0.1       0
Bank Sta=5138.7,5144.7
Exp/Cntr=0.3,0.1

Type RM Length L Ch R = 1,2471,231,231,231
BEGIN DESCRIPTION:
Mapping XS d9f636ff
END DESCRIPTION:
XS GIS Cut Line= 3
      2329263.45     13273011.43      2329042.71     13272982.64
      2328655.57     13273046.63
#Sta/Elev= 30
  4668.7  183.59  4674.5  182.88  4724.9  180.52  4741.4  179.27  4746.4  179.45
  4755.2  179.09  4805.6  176.64  4815.3  176.47  4820.4  176.81  4835.8  176.00
  4936.9  173.82  4957.2  172.43  4967.3  170.81  4994.7  170.10  4997.5  169.60
  5000.7  170.10  5018.0  171.12  5038.3  171.46  5048.4  172.00  5058.5  173.09
  5067.0  173.36  5072.1  174.21  5078.8  174.66  5133.2  176.47  5159.9  177.79
  5170.0  177.84  5210.6  179.82  5250.2  180.50  5271.4  181.69  5283.7  181.59
#Mann=3,-1,0
  4668.7     0.1       0  4994.7    0.07       0  5000.7     0.1       0
Bank Sta=4994.7,5000.7
Exp/Cntr=0.3,0.1

Type RM Length L Ch R = 1,2240,438,438,438
BEGIN DESCRIPTION:
UNT009 IN PECR 5.0
END DESCRIPTION:
XS GIS Cut Line= 3
      2329237.70     13272646.86      2328837.72     13272796.85
      2328437.70     13272796.85
#Sta/Elev= 30
  4599.7  186.33  4617.8  185.49  4663.8  182.97  4670.0  181.90  4730.5  179.51
  4738.5  178.56  4749.2  178.29  4755.4  177.62  4785.7  176.94  4840.9  174.28
  4871.1  173.78  4926.3  171.73  4931.6  171.95  4956.6  171.11  4962.8  170.05
  4986.8  168.17  5002.5  167.90  5005.3  167.40  5008.5  167.90  5011.7  168.76
  5017.1  169.20  5024.2  171.12  5061.0  171.66  5136.9  173.60  5186.9  174.25
  5316.9  178.18  5349.6  179.81  5396.9  181.82  5406.9  184.16  5426.9  185.86
#Mann=6,-1,0
  4599.7    0.05       0  4617.8     0.1       0  5002.5    0.07       0
  5008.5     0.1       0  5061.0    0.05       0  5349.6     0.1       0
Bank Sta=5002.5,5008.5
Exp/Cntr=0.3,0.1

Type RM Length L Ch R = 1,1802,464,464,464
BEGIN DESCRIPTION:
UNT009 IN PECR 4.0
END DESCRIPTION:
XS GIS Cut Line= 3
      2328987.69     13272146.88      2328687.72     13272396.85
      2328337.71     13272796.87
#Sta/Elev= 30
  4616.8  186.40  4623.9  186.20  4659.1  183.17  4673.4  183.04  4716.3  181.32
  4722.8  180.37  4751.5  178.05  4794.4  176.73  4815.3  175.59  4851.1  174.74
  4879.1  173.33  4901.2  170.61  4915.5  169.86  4922.9  170.00  4929.2  168.80
  4997.1  166.83  4999.9  166.33  5003.1  166.83  5071.3  169.15  5106.5  169.38
  5203.6  171.63  5283.9  174.42  5326.2  176.69  5347.5  177.26  5418.7  182.57
  5496.5  185.28  5508.6  187.84  5517.4  190.13  5525.0  191.11  5538.8  190.89
#Mann=6,-1,0
  4616.8    0.05       0  4922.9     0.1       0  4997.1    0.07       0
  5003.1     0.1       0  5203.6    0.05       0  5508.6     0.1       0
Bank Sta=4997.1,5003.1
Exp/Cntr=0.3,0.1

Type RM Length L Ch R = 1,1338,444,444,444
BEGIN DESCRIPTION:
UNT009 IN PECR 3.0
END DESCRIPTION:
XS GIS Cut Line= 3
      2328687.67     13271946.87      2328387.72     13272046.85
      2328137.71     13272446.87
#Sta/Elev= 30
  4673.0  180.66  4683.5  180.20  4694.0  177.22  4715.1  176.45  4725.7  174.49
  4757.3  171.85  4810.0  170.45  4831.1  169.06  4904.9  168.41  4915.4  167.42
  4928.6  167.37  4936.5  167.36  4968.1  165.47  4978.6  163.95  4998.0  163.71
  4999.7  163.65  5002.5  163.15  5005.7  163.65  5033.4  164.14  5060.5  165.79
  5112.4  166.90  5118.9  167.65  5142.5  168.87  5236.8  172.40  5272.2  174.35
  5279.9  174.33  5353.0  177.62  5366.5  178.99  5374.2  178.72  5460.9  182.81
#Mann=5,-1,0
  4673.0    0.05       0  4928.6     0.1       0  4998.0    0.05       0
  4999.7    0.03       0  5005.7    0.05       0
Bank Sta=4999.7,5005.7
Exp/Cntr=0.3,0.1

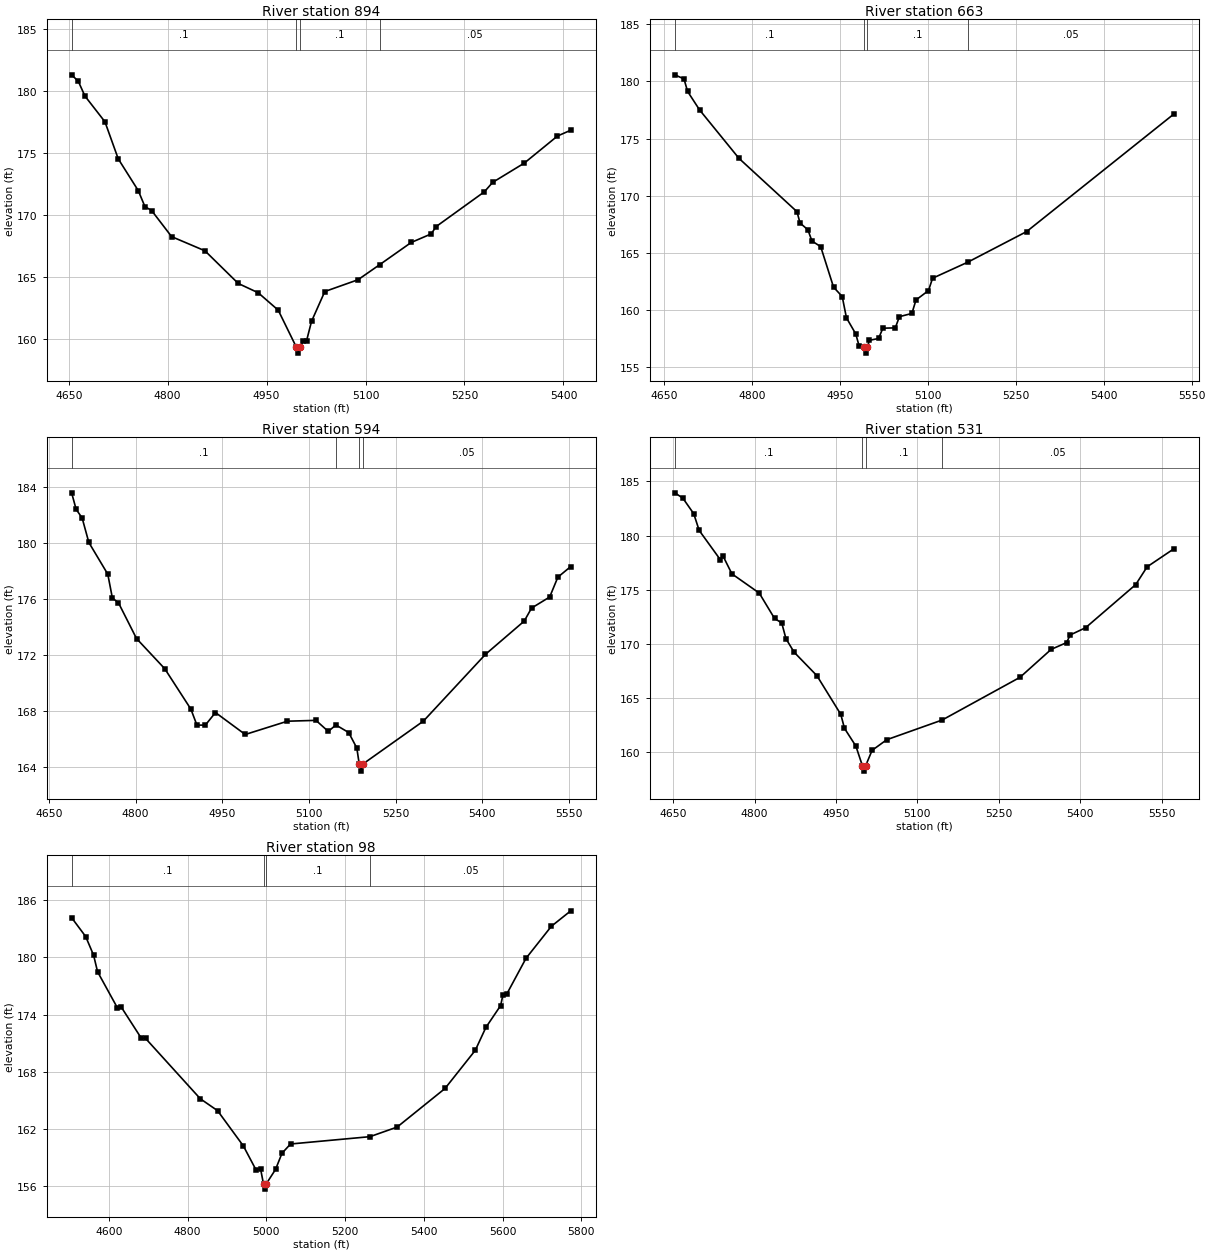
Type RM Length L Ch R = 1,894,231,231,231
BEGIN DESCRIPTION:
UNT009 IN PECR 2.0
END DESCRIPTION:
XS GIS Cut Line= 3
      2328037.73     13271546.82      2327987.72     13271896.85
      2328037.72     13272296.86
#Sta/Elev= 30
  4654.4  181.31  4664.5  180.79  4674.6  179.60  4704.9  177.53  4725.1  174.54
  4755.4  171.99  4765.5  170.70  4775.7  170.38  4806.0  168.28  4856.5  167.14
  4907.0  164.51  4937.3  163.76  4967.6  162.36  4994.9  159.40  4997.6  158.90
  5000.9  159.40  5005.5  159.88  5010.5  159.88  5018.1  161.46  5038.2  163.86
  5088.6  164.81  5121.6  166.03  5169.2  167.81  5199.5  168.50  5207.0  169.09
  5280.1  171.89  5292.7  172.65  5340.6  174.20  5390.9  176.38  5411.1  176.85
#Mann=4,-1,0
  4654.4     0.1       0  4994.9    0.07       0  5000.9     0.1       0
  5121.6    0.05       0
Bank Sta=4994.9,5000.9
Exp/Cntr=0.3,0.1

Type RM Length L Ch R = 1,663,69,69,69
BEGIN DESCRIPTION:
Mapping XS 137ad87f
END DESCRIPTION:
XS GIS Cut Line= 5
      2327669.65     13271545.63      2327714.87     13271757.13
      2327776.13     13271892.79      2327916.17     13272031.37
      2328023.24     13272300.50
#Sta/Elev= 30
  4668.1  180.57  4683.7  180.21  4689.8  179.12  4710.3  177.50  4777.6  173.26
  4876.5  168.60  4881.7  167.61  4895.1  167.02  4902.0  166.04  4917.0  165.54
  4938.9  162.00  4953.7  161.18  4960.9  159.32  4976.8  157.91  4982.8  156.81
  4990.8  156.73  4993.6  156.23  4996.8  156.73  5000.0  157.35  5015.7  157.51
  5023.1  158.41  5044.3  158.44  5051.3  159.42  5072.6  159.70  5079.6  160.88
  5100.9  161.70  5107.9  162.78  5167.8  164.18  5268.4  166.86  5519.9  177.15
#Mann=4,-1,0
  4668.1     0.1       0  4990.8    0.07       0  4996.8     0.1       0
  5167.8    0.05       0
Bank Sta=4990.8,4996.8
Exp/Cntr=0.3,0.1

Type RM Length L Ch R = 1,594,63,63,63
BEGIN DESCRIPTION:
Mapping XS edc19d82
END DESCRIPTION:
XS GIS Cut Line= 5
      2327595.26     13271589.40      2327660.90     13271805.27
      2327710.49     13271913.21      2327876.78     13272085.34
      2328019.74     13272326.03
#Sta/Elev= 30
  4689.3  183.57  4697.1  182.39  4707.5  181.77  4719.1  180.02  4751.9  177.75
  4759.8  176.05  4770.3  175.71  4801.6  173.15  4850.5  170.99  4895.7  168.10
  4906.1  166.96  4920.7  166.96  4938.2  167.86  4989.7  166.29  5062.7  167.24
  5112.1  167.30  5133.4  166.51  5146.6  166.97  5168.7  166.43  5182.8  165.32
  5187.0  164.17  5189.8  163.67  5193.0  164.17  5298.1  167.25  5405.4  172.02
  5472.5  174.40  5485.2  175.33  5516.5  176.12  5530.7  177.54  5553.0  178.30
#Mann=4,-1,0
  4689.3     0.1       0  5146.6    0.05       0  5187.0    0.07       0
  5193.0    0.05       0
Bank Sta=5187,5193
Exp/Cntr=0.3,0.1

Type RM Length L Ch R = 1,531,433,433,433
BEGIN DESCRIPTION:
Mapping XS 2330298c
END DESCRIPTION:
XS GIS Cut Line= 4
      2327533.99     13271592.26      2327552.95     13271780.47
      2327815.52     13272167.03      2328008.03     13272346.41
#Sta/Elev= 30
  4653.2  183.95  4667.9  183.46  4688.0  182.02  4698.0  180.48  4736.8  177.79
  4741.8  178.13  4758.3  176.47  4808.6  174.70  4836.9  172.35  4850.1  171.94
  4857.9  170.48  4872.9  169.24  4914.9  167.07  4958.9  163.50  4965.7  162.21
  4986.7  160.57  4998.7  158.76  5001.4  158.26  5004.7  158.76  5016.6  160.18
  5043.6  161.16  5145.8  162.98  5289.1  166.92  5346.5  169.50  5374.8  170.12
  5381.6  170.83  5410.0  171.50  5502.3  175.48  5523.3  177.12  5572.8  178.79
#Mann=4,-1,0
  4653.2     0.1       0  4998.7    0.07       0  5004.7     0.1       0
  5145.8    0.05       0
Bank Sta=4998.7,5004.7
Exp/Cntr=0.3,0.1

Type RM Length L Ch R = 1,98,0,0,0
BEGIN DESCRIPTION:
UNT009 IN PECR 1.0
END DESCRIPTION:
XS GIS Cut Line= 4
      2327245.18     13271691.45      2327208.70     13271987.61
      2327418.75     13272375.62      2327921.98     13272536.07
#Sta/Elev= 30
  4505.3  184.17  4541.0  182.19  4561.1  180.23  4571.2  178.49  4621.6  174.70
  4631.7  174.76  4682.0  171.53  4693.1  171.49  4832.2  165.15  4876.0  163.90
  4941.6  160.19  4973.4  157.70  4985.3  157.77  4992.8  156.16  4995.6  155.66
  4998.8  156.16  5023.4  157.74  5039.6  159.43  5061.4  160.40  5263.1  161.17
  5332.2  162.18  5453.7  166.23  5530.6  170.24  5557.6  172.65  5595.0  174.94
  5600.7  176.04  5611.2  176.20  5659.4  179.90  5723.9  183.27  5773.1  184.89
#Mann=4,-1,0
  4505.3     0.1       0  4992.8    0.07       0  4998.8     0.1       0
  5263.1    0.05       0
Bank Sta=4992.8,4998.8
Exp/Cntr=0.3,0.1

Chan Stop Cuts=-1