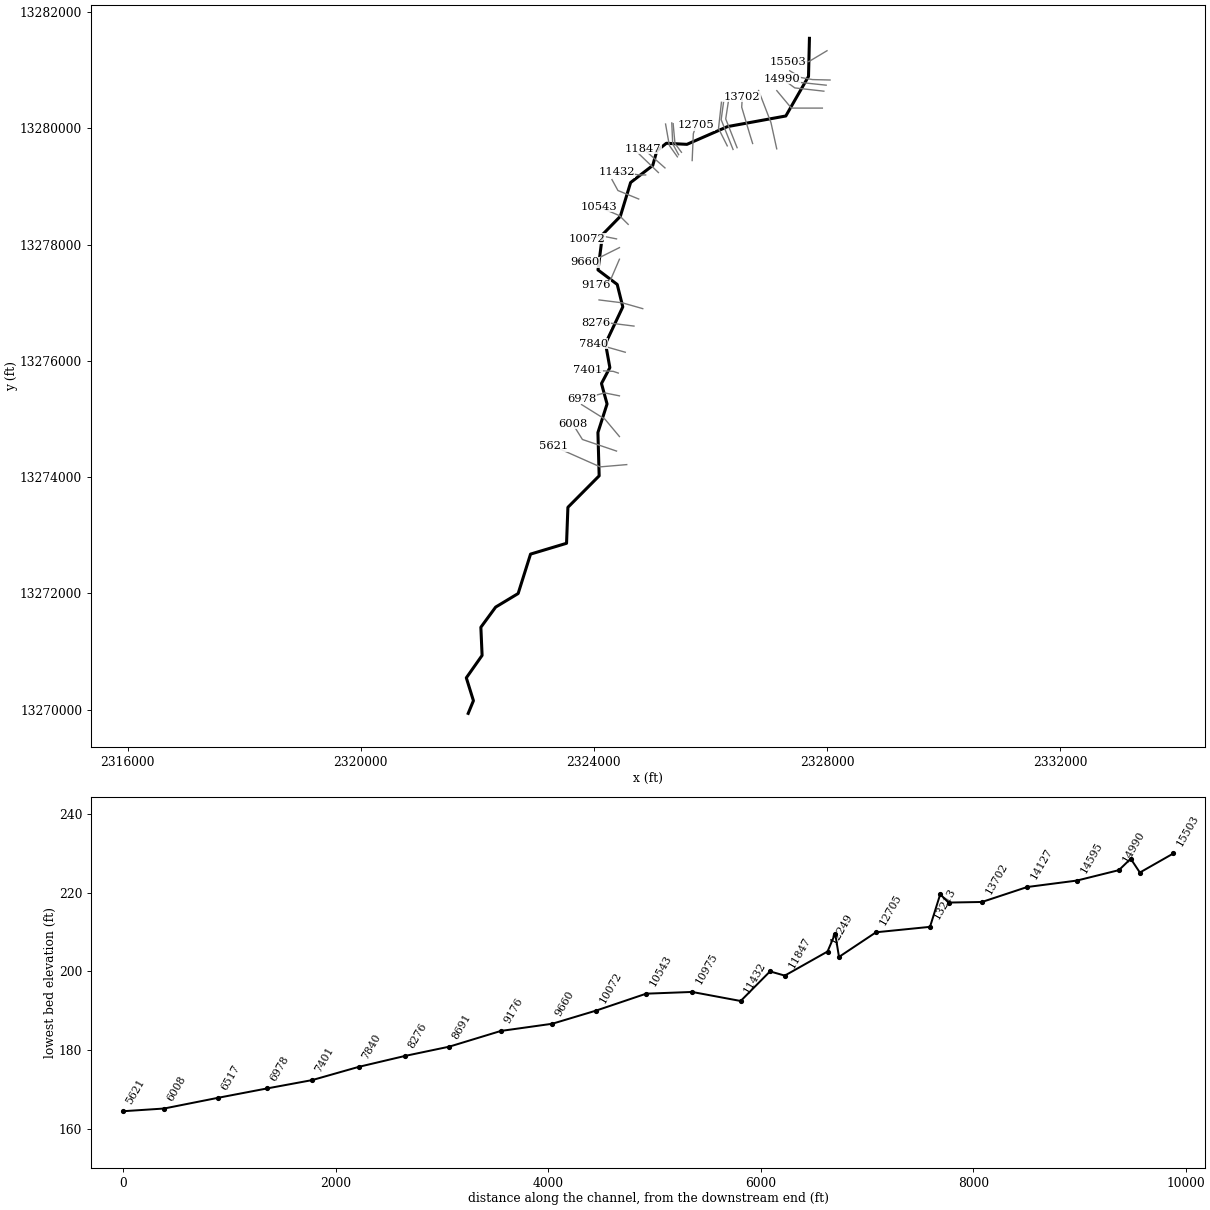
--- UNT010 IN PECR.prj (project) ---

Proj Title=UNT010 IN PECR Base Level Engineering
Current Plan=p01
Default Exp/Contr=0.3,0.1
English Units
Geom File=g01
Flow File=f01
Plan File=p01
Y Axis Title=Elevation
X Axis Title(PF)=Main Channel Distance
X Axis Title(XS)=Station
BEGIN DESCRIPTION:
UNT010 IN PECR
END DESCRIPTION:
DSS Export Rating Curves= 0
DSS Export Rating Curve Sorted= 0
DSS Export Volume Flow Curves= 0
DXF OffsetX= 0
DXF OffsetY= 0
DXF ScaleX= 1
DXF ScaleY= 10

--- UNT010 IN PECR.p01 (plan) ---

Plan Title=Multiple Run
Short Identifier=Multiple
Geom File=g01
Flow File=f01
Subcritical Flow
K Sum by GR= 0
Std Step Tol= 0.01
Critical Tol= 0.01
Num of Std Step Trials= 20
Max Error Tol= 0.3
Flow Tol Ratio= 0.001
Split Flow NTrial= 30
Split Flow Tol= 0.02
Split Flow Ratio= 0.02
Log Output Level= 0
Friction Slope Method= 1
Unsteady Friction Slope Method= 2
Unsteady Bridges Friction Slope Method= 1
Parabolic Critical Depth
Global Vel Dist=  1 , 1 , 1
Global Log Level= 0
CheckData=True
Encroach Param= -1, 0, 0, 0
BEGIN DESCRIPTION:
Multiple Run
END DESCRIPTION:

--- UNT010 IN PECR.f01 (steady flow) ---

Flow Title=Multiple
Program Version=4.10
Number of Profiles= 7
Profile Names=10-year,25-year,50-year,1pct_min,100-year,1pct_plu,500-year
River Rch & RM=UNT010 IN PECR,Reach-1         ,15503
     380     512     617     542     733     991    1039
River Rch & RM=UNT010 IN PECR,Reach-1         ,14127
     915    1306    1635    1492    2018    2730    3089
Boundary for River Rch & Prof#=UNT010 IN PECR,Reach-1         , 1
Up Type= 0
Dn Type= 3
Dn Slope=0.0066
Boundary for River Rch & Prof#=UNT010 IN PECR,Reach-1         , 2
Up Type= 0
Dn Type= 3
Dn Slope=0.0066
Boundary for River Rch & Prof#=UNT010 IN PECR,Reach-1         , 3
Up Type= 0
Dn Type= 3
Dn Slope=0.0066
Boundary for River Rch & Prof#=UNT010 IN PECR,Reach-1         , 4
Up Type= 0
Dn Type= 3
Dn Slope=0.0066
Boundary for River Rch & Prof#=UNT010 IN PECR,Reach-1         , 5
Up Type= 0
Dn Type= 3
Dn Slope=0.0066
Boundary for River Rch & Prof#=UNT010 IN PECR,Reach-1         , 6
Up Type= 0
Dn Type= 3
Dn Slope=0.0066
Boundary for River Rch & Prof#=UNT010 IN PECR,Reach-1         , 7
Up Type= 0
Dn Type= 3
Dn Slope=0.0066
DSS Import GetInterval= 0
DSS Import GetPeak= 0
DSS Import FillOption= 0

--- UNT010 IN PECR.g01 (geometry) ---

Geom Title=Existing Conditions
Program Version=4.10

River Reach=UNT010 IN PECR  ,Reach-1
Reach XY= 30
      2327697.72     13281546.86      2327681.77     13280892.37
      2327292.45     13280211.15      2326291.75     13280028.36
       2325595.4      13279723.1      2325243.44     13279741.98
      2325079.59     13279611.77      2325009.06     13279360.03
       2324629.6     13279066.43      2324452.79     13278484.34
      2324147.94     13278171.66      2324069.91     13277562.58
      2324399.61     13277313.22      2324495.39     13276927.31
      2324198.77     13276296.42       2324273.5     13275881.99
      2324129.59     13275608.85      2324225.37     13275256.96
      2324068.71     13274766.24      2324089.88     13274020.88
      2323553.55     13273479.27      2323530.33     13272860.42
      2322912.58     13272674.31       2322699.9     13271996.15
      2322313.83      13271762.8       2322060.2     13271415.83
      2322081.42     13270931.69      2321810.69     13270545.92
      2321932.76     13270152.61      2321843.16     13269934.48

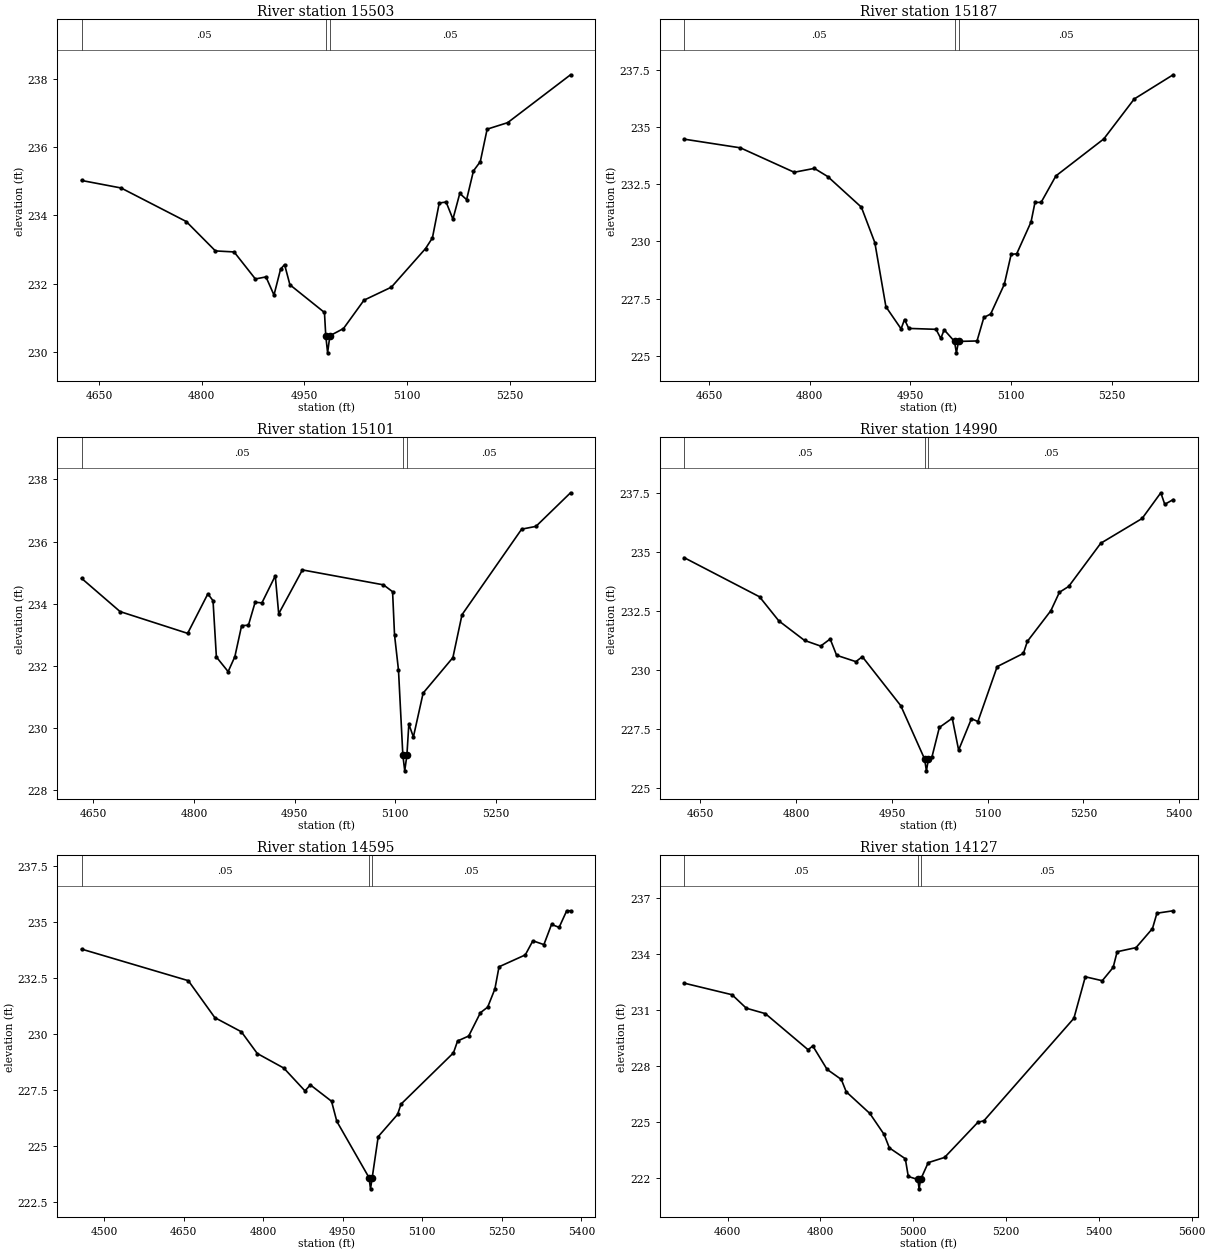
Type RM Length L Ch R = 1 ,15503   ,316,316,316
BEGIN DESCRIPTION:
UNT010 IN PECR 34.0
END DESCRIPTION:
XS GIS Cut Line= 3
      2327998.91     13281333.57      2327687.72     13281146.85
      2327335.82     13281146.85
#Sta/Elev= 30
  4624.4  235.02  4682.2   234.8  4777.4  233.82  4820.1  232.96  4847.4  232.93
  4878.5  232.14    4894   232.2  4905.7  231.67  4915.4  232.43  4921.2  232.56
    4929  231.97  4979.5  231.16  4981.4  230.48  4984.1  229.98  4987.4  230.48
  5007.3  230.69  5037.3  231.52  5077.3   231.9  5127.3  233.03  5137.3  233.34
  5147.3  234.36  5157.3  234.39  5167.3  233.89  5177.3  234.64  5187.3  234.46
  5197.3   235.3  5207.3  235.57  5217.3  236.52  5247.3  236.71  5339.2  238.11
#Mann= 3 ,-1 , 0
  4624.4     .05       0  4981.4    .035       0  4987.4     .05       0
Bank Sta=4981.4,4987.4
XS Rating Curve= 0 ,0
Exp/Cntr=0.3,0.1

Type RM Length L Ch R = 1 ,15187   ,86,86,86
BEGIN DESCRIPTION:
Mapping XS 26ade936
END DESCRIPTION:
XS GIS Cut Line= 4
      2328051.44     13280829.87      2327749.84     13280837.47
      2327554.53     13280872.19      2327359.25     13280989.36
#Sta/Elev= 30
  4613.2  234.48  4696.9   234.1    4777  233.03    4807   233.2    4827  232.84
    4877   231.5    4897  229.95  4913.5  227.14  4936.1  226.17  4941.2  226.58
  4947.5  226.19  4988.1  226.15  4995.2  225.75  5000.2  226.13  5015.6  225.62
  5018.4  225.12  5021.6  225.62  5049.1  225.64  5059.3  226.67  5069.4  226.82
  5089.7  228.12  5099.9  229.43  5108.2  229.46  5129.5  230.85  5135.4  231.71
  5144.5  231.71  5166.5  232.87  5237.8  234.49  5283.1  236.24    5341   237.3
#Mann= 3 ,-1 , 0
  4613.2     .05       0  5015.6    .035       0  5021.6     .05       0
Bank Sta=5015.6,5021.6
XS Rating Curve= 0 ,0
Exp/Cntr=0.3,0.1

Type RM Length L Ch R = 1 ,15101   ,111,111,111
BEGIN DESCRIPTION:
UNT010 IN PECR 33.0
END DESCRIPTION:
XS GIS Cut Line= 3
       2327984.8     13280740.98      2327524.15     13280789.73
      2327298.47      13280928.6
#Sta/Elev= 30
  4632.7  234.82  4690.1  233.75  4790.7  233.05  4820.8  234.32  4828.5   234.1
  4833.5  232.29    4851  231.82    4861   232.3  4871.1   233.3  4881.2  233.31
  4891.2  234.05  4901.3  234.03  4921.2   234.9  4926.3  233.68  4961.6  235.09
  5082.3  234.61  5095.9  234.39  5098.8     233  5104.7  231.87  5111.2  229.13
    5114  228.63  5117.2  229.13  5120.1  230.13  5126.9  229.72  5141.4  231.13
  5185.7  232.27  5199.3  233.65  5288.1   236.4  5309.4  236.49  5360.9  237.57
#Mann= 3 ,-1 , 0
  4632.7     .05       0  5111.2    .035       0  5117.2     .05       0
Bank Sta=5111.2,5117.2
XS Rating Curve= 0 ,0
Exp/Cntr=0.3,0.1

Type RM Length L Ch R = 1 ,14990   ,395,395,395
BEGIN DESCRIPTION:
Mapping XS 6aefd686
END DESCRIPTION:
XS GIS Cut Line= 3
      2327945.12     13280637.82      2327446.02     13280694.24
      2327233.33      13280850.5
#Sta/Elev= 30
  4624.4  234.77  4742.5  233.11  4772.7  232.09    4813  231.26  4838.3  231.02
  4853.2  231.32  4863.3  230.63  4893.5  230.36  4903.6  230.57  4963.9  228.49
  5001.2  226.23    5004  225.73  5007.2  226.23  5012.8  226.33  5024.3  227.57
  5044.5  227.96  5054.5  226.61  5074.6  227.94  5084.7  227.82  5114.9  230.15
    5156  230.71  5162.2  231.22    5199  232.52  5212.4   233.3    5227  233.55
  5277.2  235.38    5342  236.43  5371.3  237.52  5377.5  237.03  5390.6  237.23
#Mann= 3 ,-1 , 0
  4624.4     .05       0  5001.2    .035       0  5007.2     .05       0
Bank Sta=5001.2,5007.2
XS Rating Curve= 0 ,0
Exp/Cntr=0.3,0.1

Type RM Length L Ch R = 1 ,14595   ,468,468,468
BEGIN DESCRIPTION:
UNT010 IN PECR 32.0
END DESCRIPTION:
XS GIS Cut Line= 3
      2327919.07     13280346.85      2327387.72     13280346.85
       2327137.7     13280646.88
#Sta/Elev= 30
  4457.7  233.78    4659  232.37    4709  230.72    4759  230.09    4789  229.12
    4839  228.47    4879  227.45    4889  227.72    4929  226.99    4939  226.09
  4999.7  223.58  5002.5  223.08  5005.7  223.58    5017  225.41  5053.5   226.4
    5060  226.86  5158.9  229.15  5166.7  229.68  5187.6   229.9  5209.7  230.94
  5223.4  231.19    5237     232  5244.8  232.99  5294.3  233.52  5308.6  234.15
  5329.4  233.98  5343.8  234.88  5358.1  234.75  5372.4  235.49  5379.6  235.49
#Mann= 3 ,-1 , 0
  4457.7     .05       0  4999.7    .035       0  5005.7     .05       0
Bank Sta=4999.7,5005.7
XS Rating Curve= 0 ,0
Exp/Cntr=0.3,0.1

Type RM Length L Ch R = 1 ,14127   ,425,425,425
BEGIN DESCRIPTION:
UNT010 IN PECR 31.0
END DESCRIPTION:
XS GIS Cut Line= 3
      2327136.34     13279646.04      2327037.72     13280096.85
       2326825.2     13280649.42
#Sta/Elev= 30
  4506.6  232.44  4609.8  231.82  4640.5   231.1  4681.5  230.81  4773.6  228.88
  4783.8  229.08  4814.5  227.83  4845.2  227.29  4855.8  226.63  4906.7  225.47
  4937.4  224.35  4948.7  223.63  4983.1  223.05  4989.5   222.1  5010.1  221.94
  5012.8  221.44  5016.1  221.94  5032.4  222.84  5067.7  223.12  5139.5     225
  5152.4  225.08  5346.3  230.56  5370.9  232.78  5407.4  232.57  5430.9  233.28
  5439.5  234.12  5480.2  234.34  5515.6  235.36  5525.2  236.18  5560.1  236.31
#Mann= 3 ,-1 , 0
  4506.6     .05       0  5010.1    .035       0  5016.1     .05       0
Bank Sta=5010.1,5016.1
XS Rating Curve= 0 ,0
Exp/Cntr=0.3,0.1

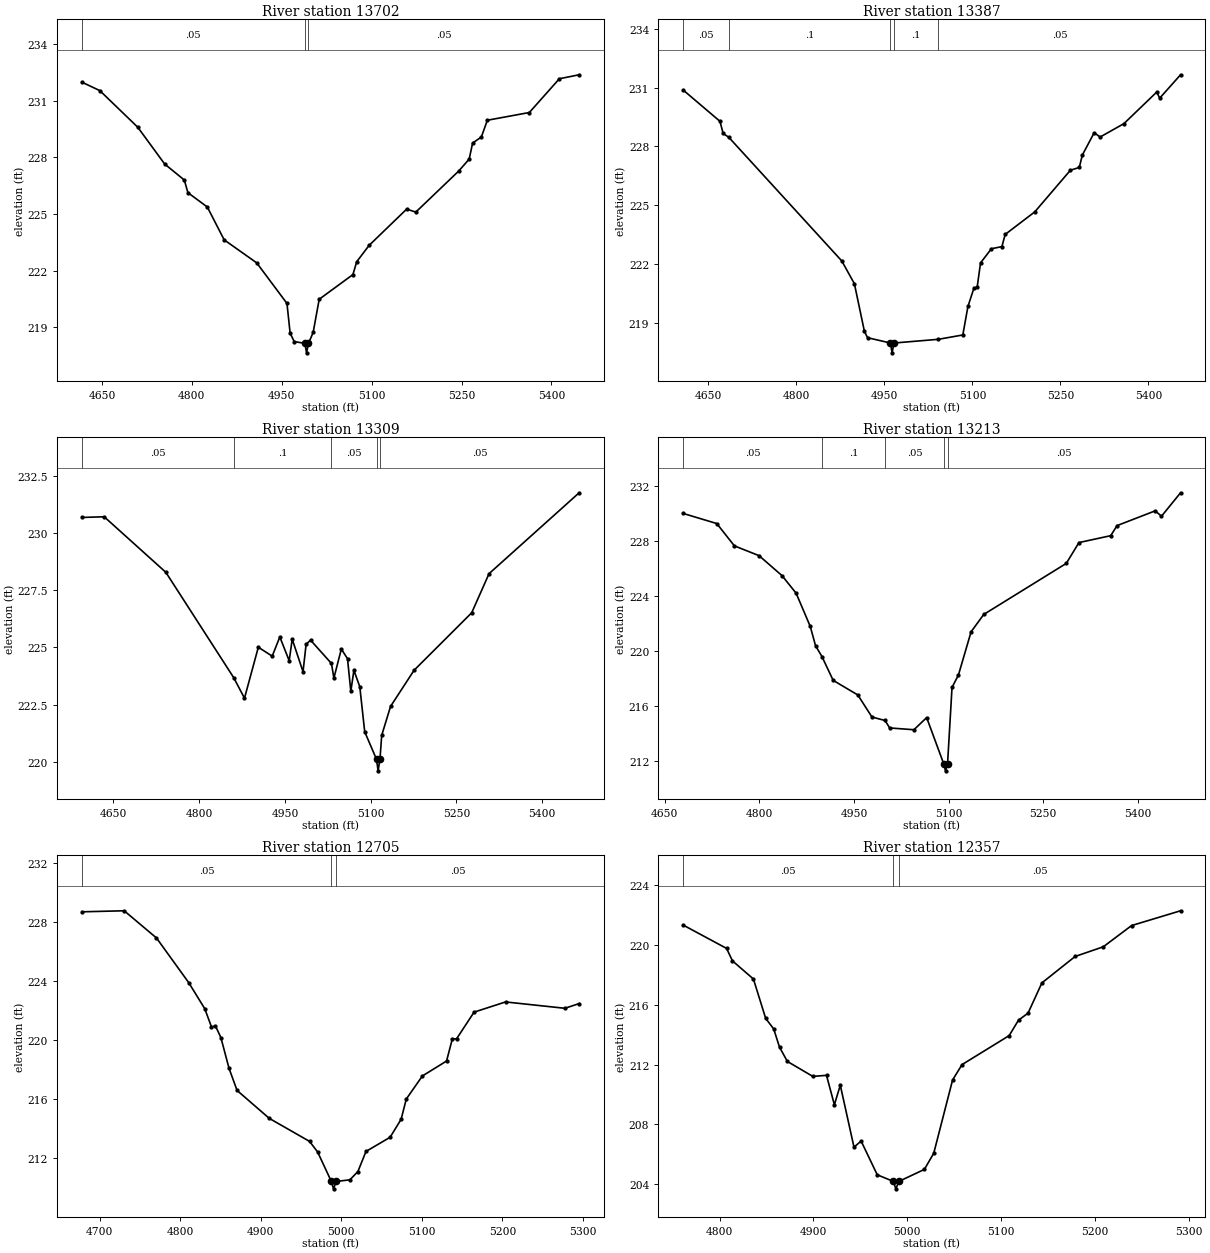
Type RM Length L Ch R = 1 ,13702   ,315,315,315
BEGIN DESCRIPTION:
UNT010 IN PECR 30.0
END DESCRIPTION:
XS GIS Cut Line= 4
      2326723.02     13279737.71      2326676.14     13279888.77
      2326535.52     13280362.73      2326545.93     13280539.78
#Sta/Elev= 30
  4616.4  231.99  4646.4  231.54  4709.7   229.6  4754.6  227.65  4787.4   226.8
  4793.4  226.13  4825.8  225.37  4853.9  223.63  4908.2  222.41  4958.7  220.26
    4964  218.68  4970.8  218.24  4988.6  218.14  4991.4  217.64  4994.6  218.14
  5002.4  218.72  5012.5  220.48  5068.8  221.79  5075.1  222.47  5095.9  223.34
  5158.5  225.26  5173.7   225.1  5245.4  227.28  5262.8  227.91  5268.5  228.76
  5283.1  229.08  5293.1  229.97  5363.2  230.38  5413.3  232.17  5446.3  232.38
#Mann= 3 ,-1 , 0
  4616.4     .05       0  4988.6    .035       0  4994.6     .05       0
Bank Sta=4988.6,4994.6
XS Rating Curve= 0 ,0
Exp/Cntr=0.3,0.1

Type RM Length L Ch R = 1 ,13387   ,78,78,78
BEGIN DESCRIPTION:
Mapping XS 8bb98595
END DESCRIPTION:
XS GIS Cut Line= 3
      2326456.46     13279665.55      2326261.13     13280160.38
      2326308.79     13280472.37
#Sta/Elev= 30
  4607.1  230.87  4669.7  229.28  4675.1  228.66  4684.6  228.47  4877.3  222.17
  4898.8  221.01  4915.9  218.58  4921.3  218.26  4960.3  217.99    4963  217.49
  4966.3  217.99  5042.1  218.18  5083.6   218.4  5092.3  219.85  5102.6  220.79
    5108  220.82  5113.8  222.07  5132.3  222.79  5150.2   222.9  5155.8  223.52
  5206.3  224.67    5267  226.79  5282.1  226.93  5287.3  227.56  5307.5   228.7
  5317.6  228.48  5358.1  229.16  5414.1  230.77  5419.2  230.46  5454.7  231.65
#Mann= 5 ,-1 , 0
  4607.1     .05       0  4684.6      .1       0  4960.3     .07       0
  4966.3      .1       0  5042.1     .05       0
Bank Sta=4960.3,4966.3
XS Rating Curve= 0 ,0
Exp/Cntr=0.3,0.1

Type RM Length L Ch R = 1 ,13309   ,96,96,96
BEGIN DESCRIPTION:
Mapping XS d5a8f4aa
END DESCRIPTION:
XS GIS Cut Line= 3
      2326387.01     13279635.17        2326183.     13280147.36
      2326226.24     13280462.99
#Sta/Elev= 30
  4594.7  230.69  4633.8  230.72  4741.6  228.29  4860.3  223.68  4879.2  222.78
  4903.4  225.01  4927.7  224.62    4941  225.46  4957.4  224.42  4962.7  225.36
  4981.6  223.94    4987  225.14  4994.8  225.32  5031.3   224.3  5035.6  223.66
  5048.6  224.93  5059.4  224.51  5065.2  223.08  5070.6     224  5080.9  223.28
  5089.5  221.31  5110.2   220.1  5112.9   219.6  5116.2   220.1  5119.2  221.15
  5134.7  222.42  5175.8     224  5276.7  226.52    5307  228.23  5464.6  231.77
#Mann= 5 ,-1 , 0
  4594.7     .05       0  4860.3      .1       0  5031.3     .05       0
  5110.2     .07       0  5116.2     .05       0
Bank Sta=5110.2,5116.2
XS Rating Curve= 0 ,0
Exp/Cntr=0.3,0.1

Type RM Length L Ch R = 1 ,13213   ,508,508,508
BEGIN DESCRIPTION:
UNT010 IN PECR 29.0
END DESCRIPTION:
XS GIS Cut Line= 3
      2326287.74     13279696.82      2326137.72     13279996.85
      2326187.72     13280446.84
#Sta/Elev= 30
  4679.5  229.98  4732.6  229.25  4760.6  227.63  4799.7  226.92  4836.1  225.47
  4858.4   224.2  4880.8  221.79  4889.2  220.39  4899.4   219.6  4917.1  217.88
  4956.2  216.82  4978.6  215.22  4999.4  214.97  5006.6  214.43  5045.1   214.3
  5065.3  215.18  5092.4  211.82  5095.2  211.32  5098.4  211.82  5105.5  217.37
  5115.6  218.26  5135.7   221.4  5155.8  222.66  5286.6  226.36  5306.7  227.87
    5357  228.37  5367.1   229.1  5427.5  230.17  5437.5  229.78  5467.7  231.48
#Mann= 5 ,-1 , 0
  4679.5     .05       0  4899.4      .1       0  4999.4     .05       0
  5092.4    .035       0  5098.4     .05       0
Bank Sta=5092.4,5098.4
XS Rating Curve= 0 ,0
Exp/Cntr=0.3,0.1

Type RM Length L Ch R = 1 ,12705   ,348,348,348
BEGIN DESCRIPTION:
UNT010 IN PECR 28.0
END DESCRIPTION:
XS GIS Cut Line= 3
      2325685.61     13279444.27      2325705.63     13279906.31
      2325754.48     13280053.65
#Sta/Elev= 30
  4677.7  228.69  4730.3  228.76  4770.4  226.92  4810.4   223.9  4830.4  222.13
  4838.7   220.9  4843.7  220.96  4850.4  220.18  4860.5   218.1  4870.5   216.6
  4910.5  214.71  4960.6  213.15  4970.6  212.43  4987.6  210.44  4990.3  209.94
  4993.6  210.44  5010.6  210.55  5020.6  211.11  5030.6  212.47  5060.6  213.43
  5074.3  214.65  5080.7  216.02  5100.7  217.58  5130.7  218.59  5137.9  220.09
  5143.1  220.09  5164.9   221.9    5204  222.59  5277.7  222.16  5295.4  222.48
#Mann= 3 ,-1 , 0
  4677.7     .05       0  4987.6     .03       0  4993.6     .05       0
Bank Sta=4987.6,4993.6
XS Rating Curve= 0 ,0
Exp/Cntr=0.3,0.1

Type RM Length L Ch R = 1 ,12357   ,36,36,36
BEGIN DESCRIPTION:
UNT010 IN PECR 27.0
END DESCRIPTION:
XS GIS Cut Line= 3
      2325501.57     13279586.61      2325390.47     13279737.64
      2325359.21     13280078.82
#Sta/Elev= 30
  4761.3  221.34  4807.5  219.78  4813.7  218.95  4836.1  217.73  4849.2  215.09
  4857.7  214.39  4863.9  213.17  4872.3  212.21  4899.4  211.21    4914  211.28
  4922.4  209.31  4928.7  210.62  4943.3  206.47  4950.9  206.88  4968.1  204.62
  4985.2  204.18  4987.9  203.68  4991.2  204.18  5018.3  204.98  5028.3  206.06
  5048.4  210.97  5058.5     212  5108.7  213.94  5118.7  214.98  5128.8  215.44
  5143.6  217.47    5179  219.24  5209.1  219.89  5239.2  221.31  5291.4   222.3
#Mann= 3 ,-1 , 0
  4761.3     .05       0  4985.2    .035       0  4991.2     .05       0
Bank Sta=4985.2,4991.2
XS Rating Curve= 0 ,0
Exp/Cntr=0.3,0.1

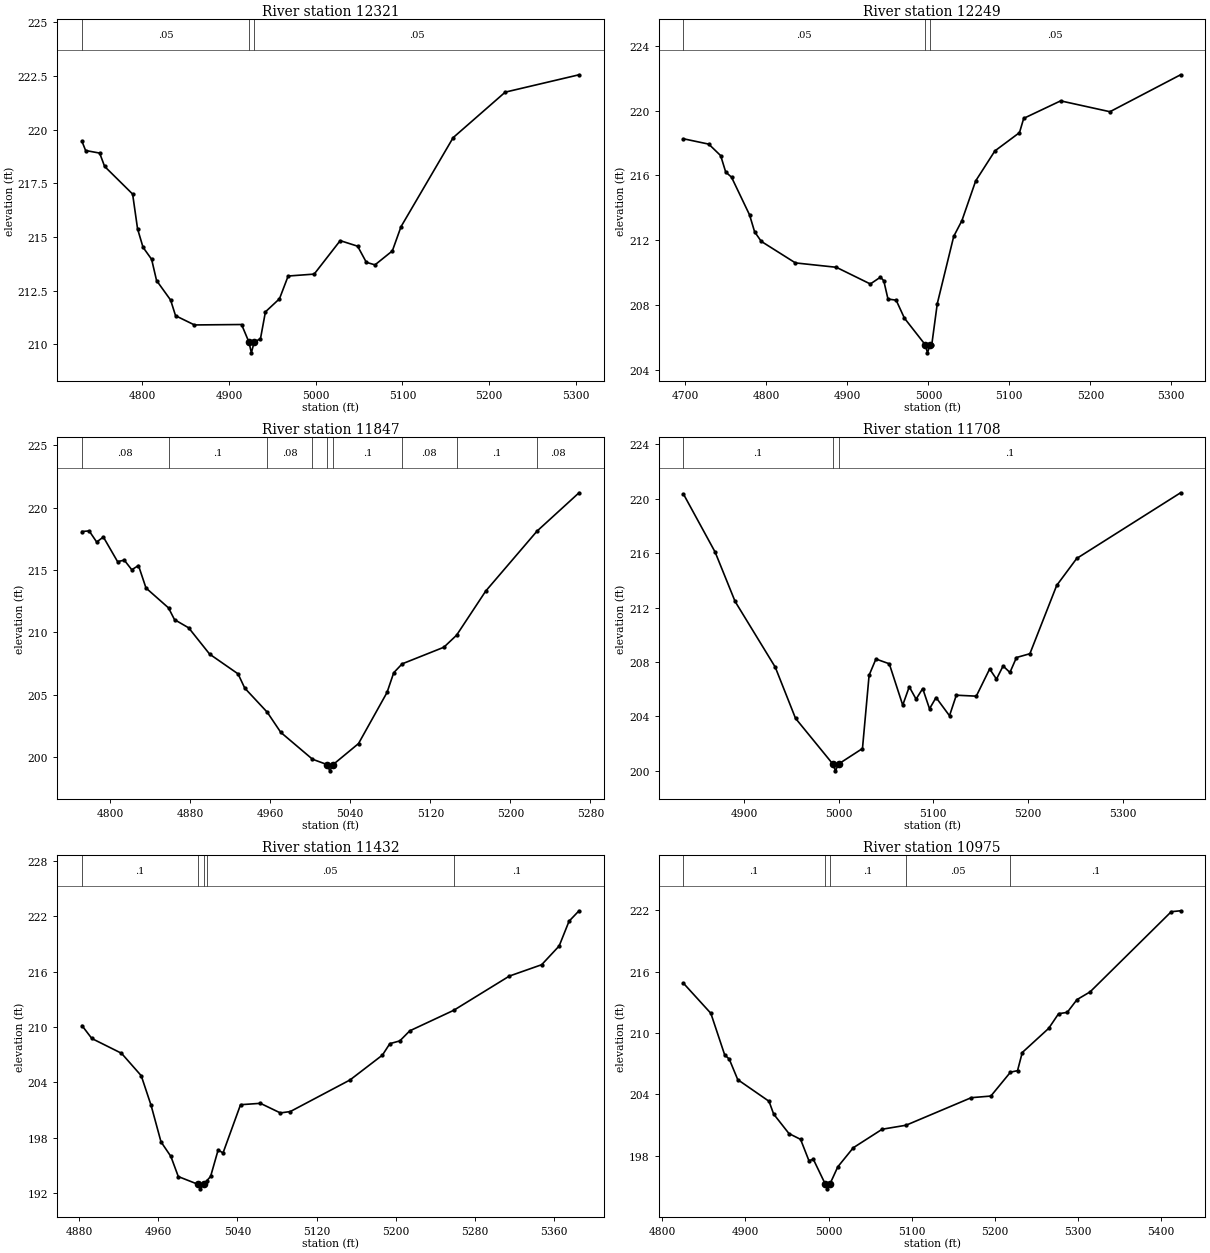
Type RM Length L Ch R = 1 ,12321   ,72,72,72
BEGIN DESCRIPTION:
Mapping XS 4229496d
END DESCRIPTION:
XS GIS Cut Line= 3
      2325452.97     13279544.93       2325351.4     13279732.43
      2325335.78     13280091.85
#Sta/Elev= 30
  4730.5  219.46  4734.7  219.03  4750.9  218.91  4756.6  218.29  4788.9     217
  4794.6  215.38  4800.9  214.52  4810.8  213.96  4816.5  212.97  4832.7  212.06
  4838.4  211.33  4860.2   210.9  4914.5  210.92    4923   210.1  4925.8   209.6
    4929   210.1  4936.3  210.26    4942  211.51  4958.2  212.12  4968.2  213.18
  4998.2  213.27  5028.2  214.83  5048.3  214.57  5058.3  213.82  5068.3   213.7
  5088.3  214.35  5098.3  215.48  5158.4  219.63  5218.4  221.75  5303.5  222.56
#Mann= 3 ,-1 , 0
  4730.5     .05       0    4923     .03       0    4929     .05       0
Bank Sta=4923,4929
XS Rating Curve= 0 ,0
Exp/Cntr=0.3,0.1

Type RM Length L Ch R = 1 ,12249   ,402,402,402
BEGIN DESCRIPTION:
Mapping XS 66fde247
END DESCRIPTION:
XS GIS Cut Line= 3
      2325432.15     13279508.46      2325294.11     13279703.79
      2325229.16     13280072.73
#Sta/Elev= 30
  4697.6  218.26  4728.8  217.93  4743.5  217.22  4749.7  216.21  4756.9  215.89
  4779.2  213.56  4785.4  212.52  4793.6  211.93  4835.8   210.6  4886.3  210.33
  4928.3   209.3  4940.8  209.72  4944.9   209.5  4950.1  208.37  4960.2   208.3
  4970.4  207.19  4996.1  205.55  4998.9  205.05  5002.1  205.55  5004.2  205.56
    5011  208.09  5031.3  212.24  5041.4  213.21  5058.4  215.66  5082.1  217.51
  5112.5  218.64  5117.7  219.52  5163.3   220.6  5224.2  219.93  5311.4  222.21
#Mann= 3 ,-1 , 0
  4697.6     .05       0  4996.1    .035       0  5002.1     .05       0
Bank Sta=4996.1,5002.1
XS Rating Curve= 0 ,0
Exp/Cntr=0.3,0.1

Type RM Length L Ch R = 1 ,11847   ,139,139,139
BEGIN DESCRIPTION:
UNT010 IN PECR 26.0
END DESCRIPTION:
XS GIS Cut Line= 2
      2325219.01     13279317.95      2324847.51     13279647.79
#Sta/Elev= 30
  4771.8  218.08    4779  218.13  4786.5  217.24  4793.2  217.64  4807.4  215.67
  4814.1  215.79  4821.6  215.02  4828.3  215.36  4835.8  213.56  4858.3  211.97
  4864.3  211.03  4878.5  210.37  4899.4  208.27  4927.8  206.69  4934.5  205.55
    4957  203.62  4970.5  202.01  5002.2  199.86  5016.8  199.43  5019.5  198.93
  5022.8  199.43  5048.2  201.11  5076.7   205.2  5083.4  206.78  5091.8  207.49
  5133.5  208.82  5146.2  209.78  5175.3  213.31  5226.6  218.11  5268.6  221.18
#Mann= 9 ,-1 , 0
  4771.8     .08       0  4858.3      .1       0    4957     .08       0
  5002.2      .1       0  5016.8     .07       0  5022.8      .1       0
  5091.8     .08       0  5146.2      .1       0  5226.6     .08       0
Bank Sta=5016.8,5022.8
XS Rating Curve= 0 ,0
Exp/Cntr=0.3,0.1

Type RM Length L Ch R = 1 ,11708   ,276,276,276
BEGIN DESCRIPTION:
Mapping XS 0929245d
END DESCRIPTION:
XS GIS Cut Line= 2
      2325106.16     13279238.09      2324728.13     13279602.25
#Sta/Elev= 30
  4836.2  220.34  4869.6  216.08  4890.7  212.45  4933.1  207.62  4954.5  203.86
  4993.9   200.5  4996.7     200  4999.9   200.5  5025.2  201.64  5032.2  207.03
  5039.4  208.22  5053.5  207.87  5067.7  204.83  5074.6  206.18  5081.8  205.27
  5088.8  206.05    5096  204.56  5102.9  205.39  5117.1  204.05  5124.3  205.56
  5145.4  205.49  5159.5  207.49  5166.7  206.74  5173.7  207.71  5180.9  207.23
  5187.8  208.33    5202  208.61  5230.3  213.63  5251.4  215.61  5361.1  220.44
#Mann= 3 ,-1 , 0
  4836.2      .1       0  4993.9     .07       0  4999.9      .1       0
Bank Sta=4993.9,4999.9
XS Rating Curve= 0 ,0
Exp/Cntr=0.3,0.1

Type RM Length L Ch R = 1 ,11432   ,457,457,457
BEGIN DESCRIPTION:
UNT010 IN PECR 25.0
END DESCRIPTION:
XS GIS Cut Line= 3
      2324887.72     13279196.85      2324787.72     13279196.85
      2324387.73     13279246.85
#Sta/Elev= 30
  4882.6  210.16  4892.6  208.76  4922.6  207.16  4942.6  204.73  4952.6  201.51
  4962.6  197.57  4972.6  195.99  4980.1  193.81  4999.8  192.98  5002.5  192.48
  5005.8  192.98    5009  193.36  5012.8  193.82  5020.4  196.68  5025.4  196.37
  5043.1  201.59  5063.2  201.74  5083.4   200.7  5093.5  200.85  5153.9  204.27
  5186.7  206.96  5194.2   208.2  5204.3   208.5  5214.4  209.59    5259  211.82
  5315.2  215.52  5347.9  216.75  5365.6  218.78  5375.6  221.46  5385.7  222.59
#Mann= 5 ,-1 , 0
  4882.6      .1       0  4999.8     .07       0  5005.8      .1       0
    5009     .05       0    5259      .1       0
Bank Sta=4999.8,5005.8
XS Rating Curve= 0 ,0
Exp/Cntr=0.3,0.1

Type RM Length L Ch R = 1 ,10975   ,432,432,432
BEGIN DESCRIPTION:
UNT010 IN PECR 24.0
END DESCRIPTION:
XS GIS Cut Line= 3
      2324768.13     13278782.88      2324412.25     13278928.71
      2324309.84     13279116.16
#Sta/Elev= 30
  4825.4  214.85  4858.3  211.92    4875  207.85  4880.4  207.46  4890.7  205.44
  4928.3  203.33  4933.9  202.08  4952.3  200.18  4966.3  199.61  4976.3  197.54
  4981.7  197.66  4995.8  195.28  4998.5  194.78  5001.8  195.28  5011.1  196.93
  5029.7  198.79  5064.5   200.6  5093.2  200.99  5171.7  203.68  5195.3  203.84
  5218.9  206.17  5227.4  206.32  5233.1  208.09  5264.9  210.45  5276.8  211.88
  5287.2  212.01    5299  213.26  5314.7  214.01  5412.4  221.84  5423.6  221.93
#Mann= 5 ,-1 , 0
  4825.4      .1       0  4995.8     .07       0  5001.8      .1       0
  5093.2     .05       0  5218.9      .1       0
Bank Sta=4995.8,5001.8
XS Rating Curve= 0 ,0
Exp/Cntr=0.3,0.1

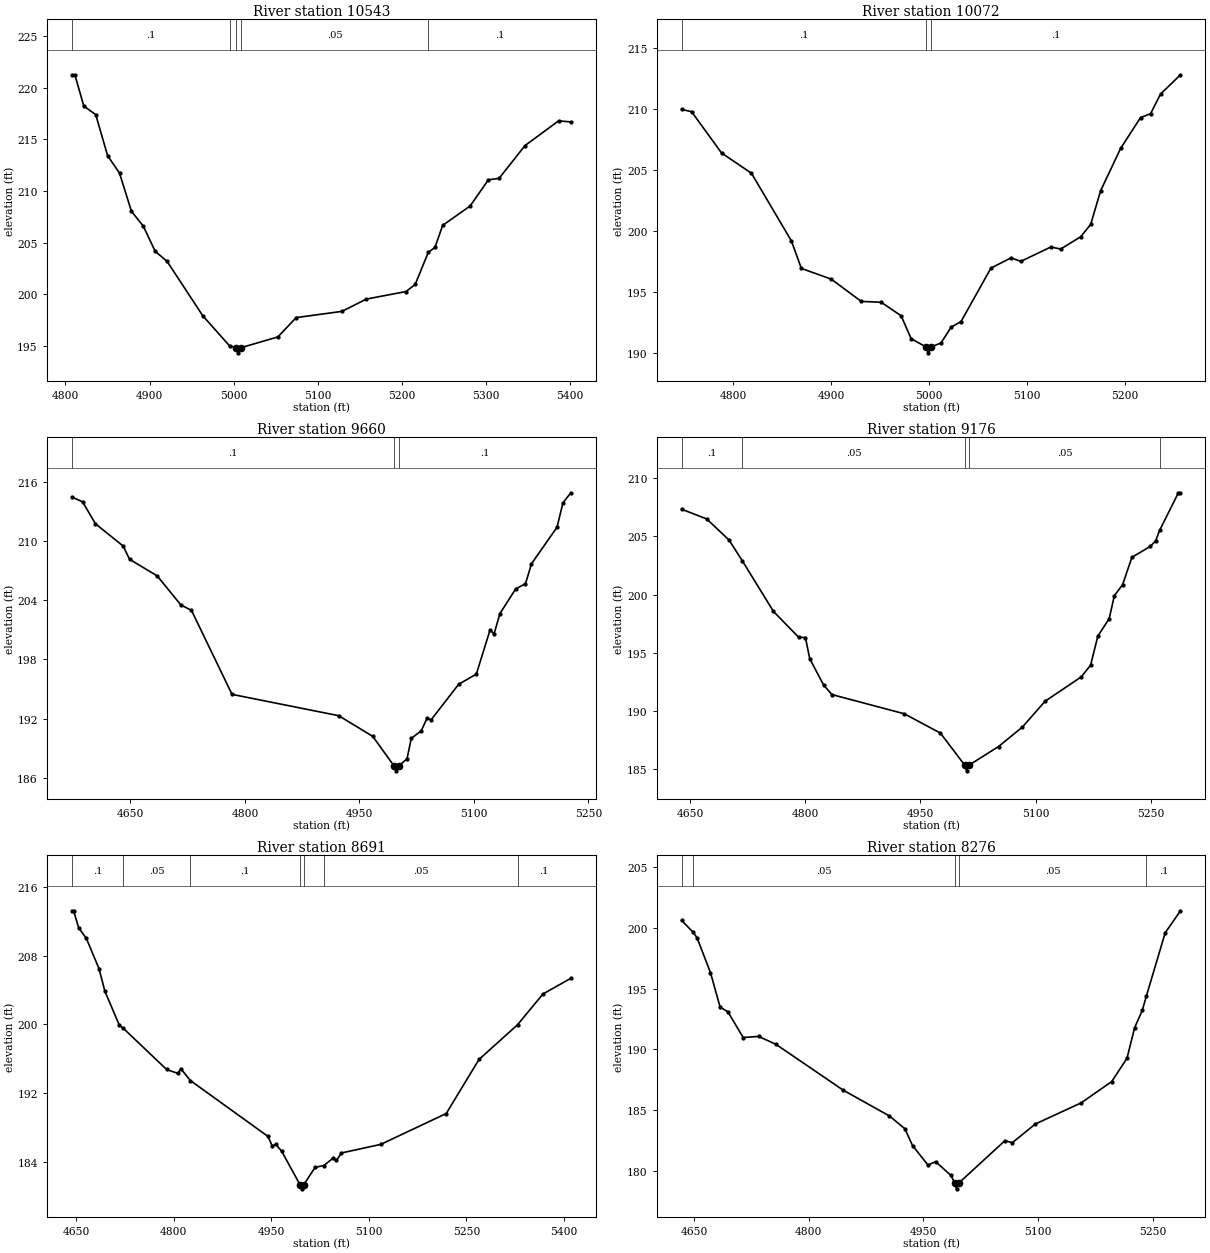
Type RM Length L Ch R = 1 ,10543   ,471,471,471
BEGIN DESCRIPTION:
UNT010 IN PECR 23.0
END DESCRIPTION:
XS GIS Cut Line= 3
      2324587.71     13278346.87      2324437.72     13278496.85
      2324087.73     13278646.85
#Sta/Elev= 30
  4807.7  221.24  4811.2  221.24  4821.8  218.22    4836  217.38  4850.1  213.42
  4864.3  211.72  4878.4  208.04  4892.5   206.6  4906.7  204.16  4920.8  203.19
  4963.2  197.93    4995  195.02  5002.7  194.84  5005.4  194.34  5008.7  194.84
  5052.5  195.88  5074.2  197.75  5128.6  198.35  5157.6  199.54  5204.8  200.27
  5215.7  200.96  5231.2  204.05  5239.2  204.54  5248.3  206.67  5280.9  208.54
  5302.7  211.08  5315.4  211.22  5346.2  214.39  5386.1  216.78  5400.6  216.68
#Mann= 5 ,-1 , 0
  4807.7      .1       0    4995     .05       0  5002.7     .03       0
  5008.7     .05       0  5231.2      .1       0
Bank Sta=5002.7,5008.7
XS Rating Curve= 0 ,0
Exp/Cntr=0.3,0.1

Type RM Length L Ch R = 1 ,10072   ,412,412,412
BEGIN DESCRIPTION:
UNT010 IN PECR 22.0
END DESCRIPTION:
XS GIS Cut Line= 3
      2324387.74     13278096.85      2324137.72     13278146.85
      2323887.74     13278096.86
#Sta/Elev= 30
  4747.1  209.96  4757.3  209.78  4787.9   206.4  4818.5  204.74  4859.3   199.2
  4869.5  196.95  4900.1  196.07  4930.7  194.25  4951.1  194.18  4971.5  193.07
  4981.7   191.2  4996.5  190.54  4999.3  190.04  5002.5  190.54  5012.3  190.85
  5022.5  192.14  5032.7   192.6  5063.3  196.98  5083.7  197.81  5093.9  197.53
  5124.4   198.7  5134.6  198.54    5155  199.54  5165.2  200.55  5175.4  203.31
  5195.8  206.77  5216.2   209.3  5226.4  209.61  5236.6  211.22    5257   212.8
#Mann= 3 ,-1 , 0
  4747.1      .1       0  4996.5     .07       0  5002.5      .1       0
Bank Sta=4996.5,5002.5
XS Rating Curve= 0 ,0
Exp/Cntr=0.3,0.1

Type RM Length L Ch R = 1 ,9660    ,484,484,484
BEGIN DESCRIPTION:
UNT010 IN PECR 21.0
END DESCRIPTION:
XS GIS Cut Line= 3
      2324437.75     13277946.87      2324037.72     13277746.85
      2323837.72     13277696.86
#Sta/Elev= 30
  4573.4  214.45  4587.4  213.96  4604.2  211.74  4640.5  209.48  4648.9  208.14
  4685.2  206.45    4716  203.52    4730  202.96  4783.1  194.45  4922.8  192.29
  4967.5  190.19  4995.3   187.2    4998   186.7  5001.3   187.2  5012.3  187.91
  5017.9  189.99    5031  190.76  5038.7  192.07  5043.8  191.86  5079.9  195.47
  5103.1   196.5  5121.1  200.99  5126.3  200.57    5134  202.64  5154.6  205.13
  5167.5  205.67  5175.3  207.68  5208.8  211.39  5216.5  213.85  5226.8  214.88
#Mann= 3 ,-1 , 0
  4573.4      .1       0  4995.3     .07       0  5001.3      .1       0
Bank Sta=4995.3,5001.3
XS Rating Curve= 0 ,0
Exp/Cntr=0.3,0.1

Type RM Length L Ch R = 1 ,9176    ,485,485,485
BEGIN DESCRIPTION:
UNT010 IN PECR 20.0
END DESCRIPTION:
XS GIS Cut Line= 3
      2324437.74     13277746.89      2324287.72     13277396.85
      2324037.71     13277296.85
#Sta/Elev= 30
  4638.8  207.34  4671.5   206.5  4700.5   204.7  4717.7  202.93  4758.5  198.56
  4791.2  196.35  4800.2  196.31  4805.7  194.51  4823.8  192.24  4834.7  191.42
    4929  189.77  4976.1  188.11  5007.6  185.37  5010.3  184.87  5013.6  185.37
  5051.9  186.96  5082.9  188.63  5112.5  190.85  5159.6  192.94  5171.8  193.95
  5181.2  196.44    5196  197.94  5202.7  199.91  5213.5  200.86  5225.6  203.21
  5249.8  204.15  5256.6  204.63  5261.7  205.52  5286.2  208.75  5288.9  208.75
#Mann= 5 ,-1 , 0
  4638.8      .1       0  4717.7     .05       0  5007.6     .03       0
  5013.6     .05       0  5261.7      .1       0
Bank Sta=5007.6,5013.6
XS Rating Curve= 0 ,0
Exp/Cntr=0.3,0.1

Type RM Length L Ch R = 1 ,8691    ,415,415,415
BEGIN DESCRIPTION:
UNT010 IN PECR 19.0
END DESCRIPTION:
XS GIS Cut Line= 3
      2324837.71     13276896.86      2324487.72     13276996.85
      2324087.73     13277046.85
#Sta/Elev= 30
  4643.3  213.22  4645.9  213.22  4653.7  211.23  4665.4  210.02  4684.9   206.5
    4694  203.86  4716.1  199.93  4722.5  199.54  4788.9  194.76  4805.8  194.32
    4811  194.83  4825.4  193.48  4944.9  186.97  4951.4  185.84  4956.6  186.08
  4965.7  185.27  4993.9  181.38  4996.6  180.88  4999.9  181.38  5017.4  183.39
  5030.5  183.58  5045.1  184.46  5050.1  184.18  5057.7  185.05  5118.2  186.05
  5218.9  189.64  5269.3  195.93  5328.5  199.96  5367.6  203.54  5410.4  205.36
#Mann= 7 ,-1 , 0
  4643.3      .1       0  4722.5     .05       0  4825.4      .1       0
  4993.9     .07       0  4999.9      .1       0  5030.5     .05       0
  5328.5      .1       0
Bank Sta=4993.9,4999.9
XS Rating Curve= 0 ,0
Exp/Cntr=0.3,0.1

Type RM Length L Ch R = 1 ,8276    ,436,436,436
BEGIN DESCRIPTION:
UNT010 IN PECR 18.0
END DESCRIPTION:
XS GIS Cut Line= 3
      2324687.72     13276596.85      2324287.72     13276646.85
      2324037.74     13276646.85
#Sta/Elev= 30
  4633.5   200.6  4648.6  199.62  4653.7  199.17  4671.3   196.3  4683.9  193.47
    4694  193.09  4714.1  190.97  4734.3  191.06    4757  190.41  4845.1  186.64
  4905.6  184.52  4925.8  183.47  4935.8  182.09    4956  180.49  4966.1  180.76
  4986.2  179.63  4990.8  179.03  4993.5  178.53  4996.8  179.03  5056.6  182.48
  5066.6  182.33  5096.6  183.86  5156.6   185.6  5196.6  187.35  5216.6  189.27
  5226.6  191.78  5236.6   193.2  5242.1  194.41  5266.6  199.58  5286.6  201.39
#Mann= 5 ,-1 , 0
  4633.5      .1       0  4648.6     .05       0  4990.8    .035       0
  4996.8     .05       0  5242.1      .1       0
Bank Sta=4990.8,4996.8
XS Rating Curve= 0 ,0
Exp/Cntr=0.3,0.1

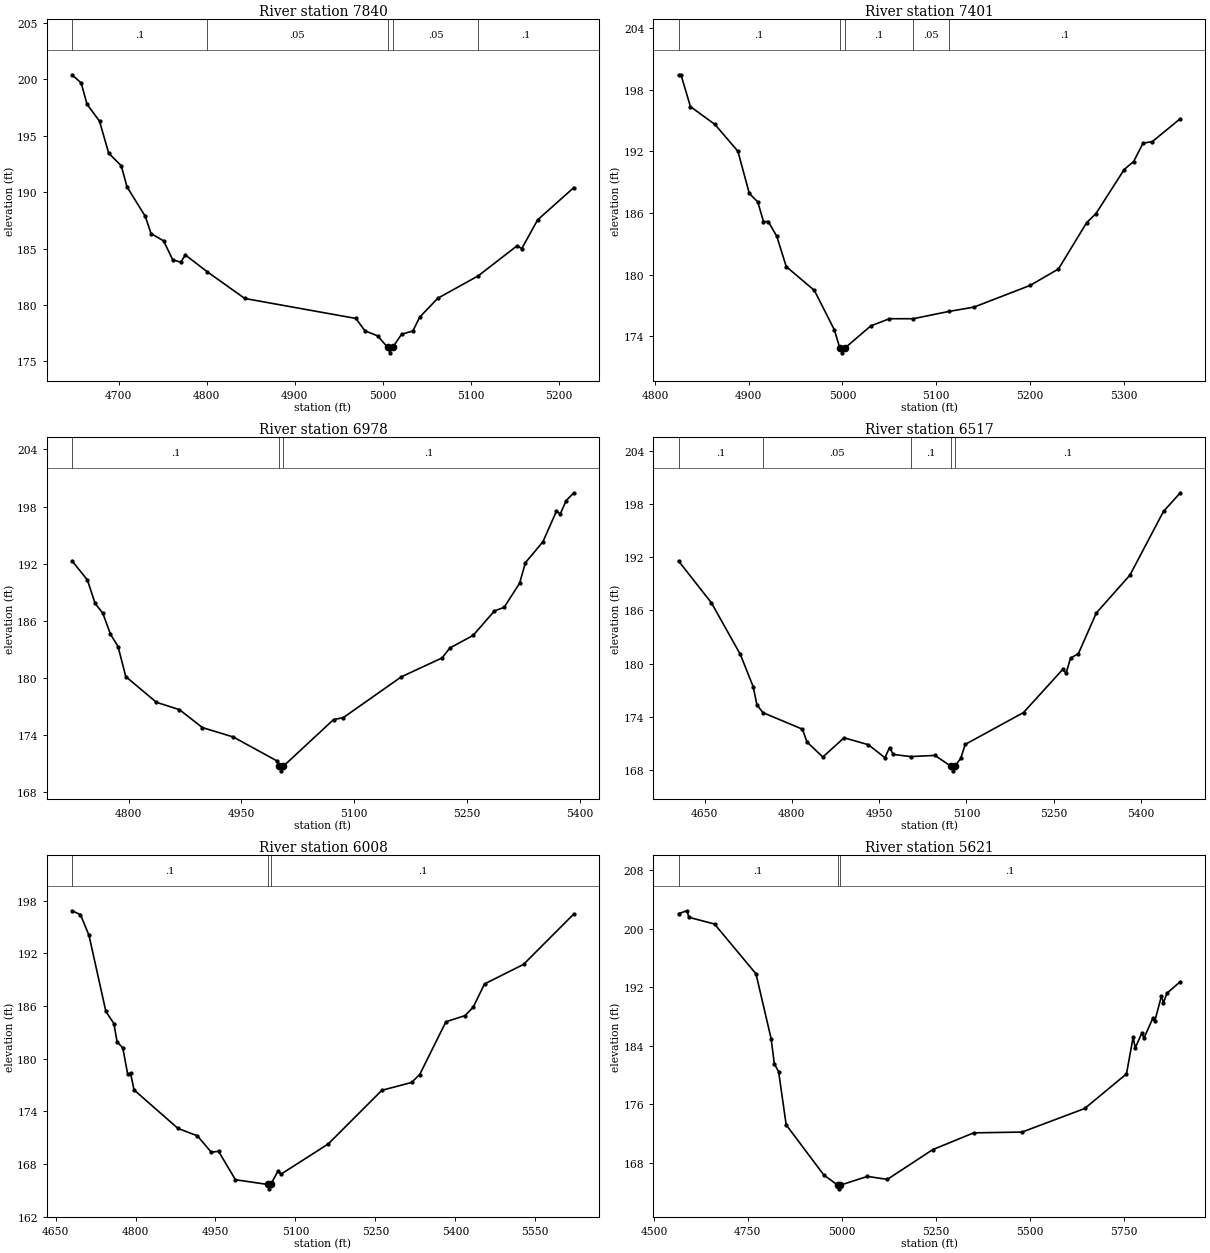
Type RM Length L Ch R = 1 ,7840    ,439,439,439
BEGIN DESCRIPTION:
UNT010 IN PECR 17.0
END DESCRIPTION:
XS GIS Cut Line= 3
      2324537.71     13276146.86      2324187.72     13276246.85
      2323987.76     13276296.84
#Sta/Elev= 30
    4647  200.41  4657.4  199.68  4663.9  197.81  4678.2  196.29  4688.6  193.46
  4702.9  192.34  4709.4  190.47  4730.2  187.85  4736.7  186.33    4751  185.68
  4761.4     184  4770.5  183.79  4775.7  184.43  4800.4  182.95  4843.3  180.57
  4969.4   178.8  4979.8   177.7  4994.1  177.26  5005.4  176.25  5008.1  175.75
  5011.4  176.25  5021.3  177.39  5034.2  177.69  5041.9  178.91  5062.5  180.59
  5108.3  182.57  5152.7  185.25  5157.9  184.99  5175.9  187.54  5217.1  190.41
#Mann= 5 ,-1 , 0
    4647      .1       0  4800.4     .05       0  5005.4     .03       0
  5011.4     .05       0  5108.3      .1       0
Bank Sta=5005.4,5011.4
XS Rating Curve= 0 ,0
Exp/Cntr=0.3,0.1

Type RM Length L Ch R = 1 ,7401    ,423,423,423
BEGIN DESCRIPTION:
UNT010 IN PECR 16.0
END DESCRIPTION:
XS GIS Cut Line= 3
      2324417.69     13275788.77      2324331.05     13275818.19
      2323887.94     13275841.08
#Sta/Elev= 30
  4825.2  199.44  4827.8  199.44  4837.9  196.34    4864  194.61  4888.5     192
  4900.7  187.89  4909.7  187.07  4915.8  185.16  4920.9  185.16    4930  183.72
  4940.1  180.77  4970.1  178.45  4991.4  174.62  4997.1  172.88  4999.9  172.38
  5003.1  172.88  5030.2     175  5050.2   175.7  5075.4   175.7  5113.6  176.41
  5140.3  176.83  5200.4  178.95  5230.4  180.54  5260.5  185.05  5270.5  185.94
  5300.5  190.22  5310.6     191  5320.6  192.78  5330.6  192.94  5360.4  195.17
#Mann= 5 ,-1 , 0
  4825.2      .1       0  4997.1     .07       0  5003.1      .1       0
  5075.4     .05       0  5113.6      .1       0
Bank Sta=4997.1,5003.1
XS Rating Curve= 0 ,0
Exp/Cntr=0.3,0.1

Type RM Length L Ch R = 1 ,6978    ,461,461,461
BEGIN DESCRIPTION:
UNT010 IN PECR 15.0
END DESCRIPTION:
XS GIS Cut Line= 3
       2324437.7     13275396.86      2324187.72     13275446.85
      2323787.76     13275346.86
#Sta/Elev= 30
  4724.8   192.3  4745.2   190.3  4755.4  187.84  4765.6  186.82  4775.8  184.62
    4786   183.3  4796.2  180.16    4837  177.46  4867.6  176.69  4898.1  174.81
  4938.9  173.83  4997.8  171.29  4999.9  170.77  5002.7  170.27  5005.9  170.77
  5072.5  175.65  5085.4  175.85  5162.7  180.14  5216.8  182.12  5227.1  183.16
    5258  184.48  5286.4  187.05  5299.3  187.43  5319.9  189.96  5327.6  192.12
  5350.8   194.3  5368.8  197.51    5374  197.24  5381.7  198.62    5392  199.45
#Mann= 3 ,-1 , 0
  4724.8      .1       0  4999.9     .07       0  5005.9      .1       0
Bank Sta=4999.9,5005.9
XS Rating Curve= 0 ,0
Exp/Cntr=0.3,0.1

Type RM Length L Ch R = 1 ,6517    ,509,509,509
BEGIN DESCRIPTION:
UNT010 IN PECR 14.0
END DESCRIPTION:
XS GIS Cut Line= 3
      2324437.74     13274696.84      2324187.72     13274996.85
      2323787.75     13275246.84
#Sta/Elev= 30
  4605.3  191.58  4661.9  186.84  4711.4  181.04  4733.5   177.4  4740.1  175.31
  4750.6  174.45  4818.2  172.59    4826  171.14  4853.3  169.45  4889.7  171.62
  4931.4  170.84    4960  169.37  4967.8  170.51  4974.4  169.74    5004   169.5
    5046  169.63  5073.6  168.39  5076.4  167.89  5079.6  168.39  5090.2  169.29
  5097.8  170.87  5198.1  174.47  5265.3  179.33  5271.2  178.91  5278.9  180.61
  5292.4  181.12  5323.1   185.7  5380.9  189.98  5438.6  197.17  5467.5  199.27
#Mann= 5 ,-1 , 0
  4605.3      .1       0  4750.6     .05       0    5004      .1       0
  5073.6     .03       0  5079.6      .1       0
Bank Sta=5073.6,5079.6
XS Rating Curve= 0 ,0
Exp/Cntr=0.3,0.1

Type RM Length L Ch R = 1 ,6008    ,387,387,387
BEGIN DESCRIPTION:
UNT010 IN PECR 13.0
END DESCRIPTION:
XS GIS Cut Line= 3
      2324387.72     13274446.86      2323802.71     13274646.24
      2323631.91     13274920.55
#Sta/Elev= 30
    4681  196.85  4696.7  196.41  4712.7  194.06  4744.4  185.38  4759.4     184
  4765.5  181.91  4776.1  181.22  4785.4  178.22  4790.7  178.33  4797.2  176.44
  4879.5  172.05  4916.1   171.2  4942.2  169.33  4955.7  169.44  4987.4   166.2
  5047.8  165.66  5050.5  165.16  5053.8  165.66  5067.5  167.23  5072.8  166.83
  5161.6  170.28  5262.1  176.39  5317.7  177.28  5333.1  178.19  5382.2   184.2
    5418   184.9  5433.4  185.86  5454.6  188.51  5527.8  190.74  5622.2  196.49
#Mann= 3 ,-1 , 0
    4681      .1       0  5047.8     .07       0  5053.8      .1       0
Bank Sta=5047.8,5053.8
XS Rating Curve= 0 ,0
Exp/Cntr=0.3,0.1

Type RM Length L Ch R = 1 ,5621    ,450,450,450
BEGIN DESCRIPTION:
UNT010 IN PECR 12.0
END DESCRIPTION:
XS GIS Cut Line= 3
      2324563.07     13274213.94      2324107.39     13274174.88
      2323305.31     13274531.65
#Sta/Elev= 30
  4565.6  202.08    4588  202.47    4593  201.58  4661.3  200.66  4771.7  193.85
  4811.9     185  4820.5  181.57  4831.9  180.48    4852  173.22  4952.4  166.35
  4989.5  164.97  4992.3  164.47  4995.5  164.97  5068.3  166.17  5121.1  165.76
    5242  169.83  5350.9  172.12  5479.9  172.23  5646.4  175.45  5757.5  180.18
  5775.3   185.2  5780.8  183.72  5798.5  185.77    5804  185.06  5827.3  187.75
  5832.7  187.36  5850.5  190.81    5856  189.91  5865.3  191.21  5900.8  192.79
#Mann= 3 ,-1 , 0
  4565.6      .1       0  4989.5     .07       0  4995.5      .1       0
Bank Sta=4989.5,4995.5
XS Rating Curve= 0 ,0
Exp/Cntr=0.3,0.1