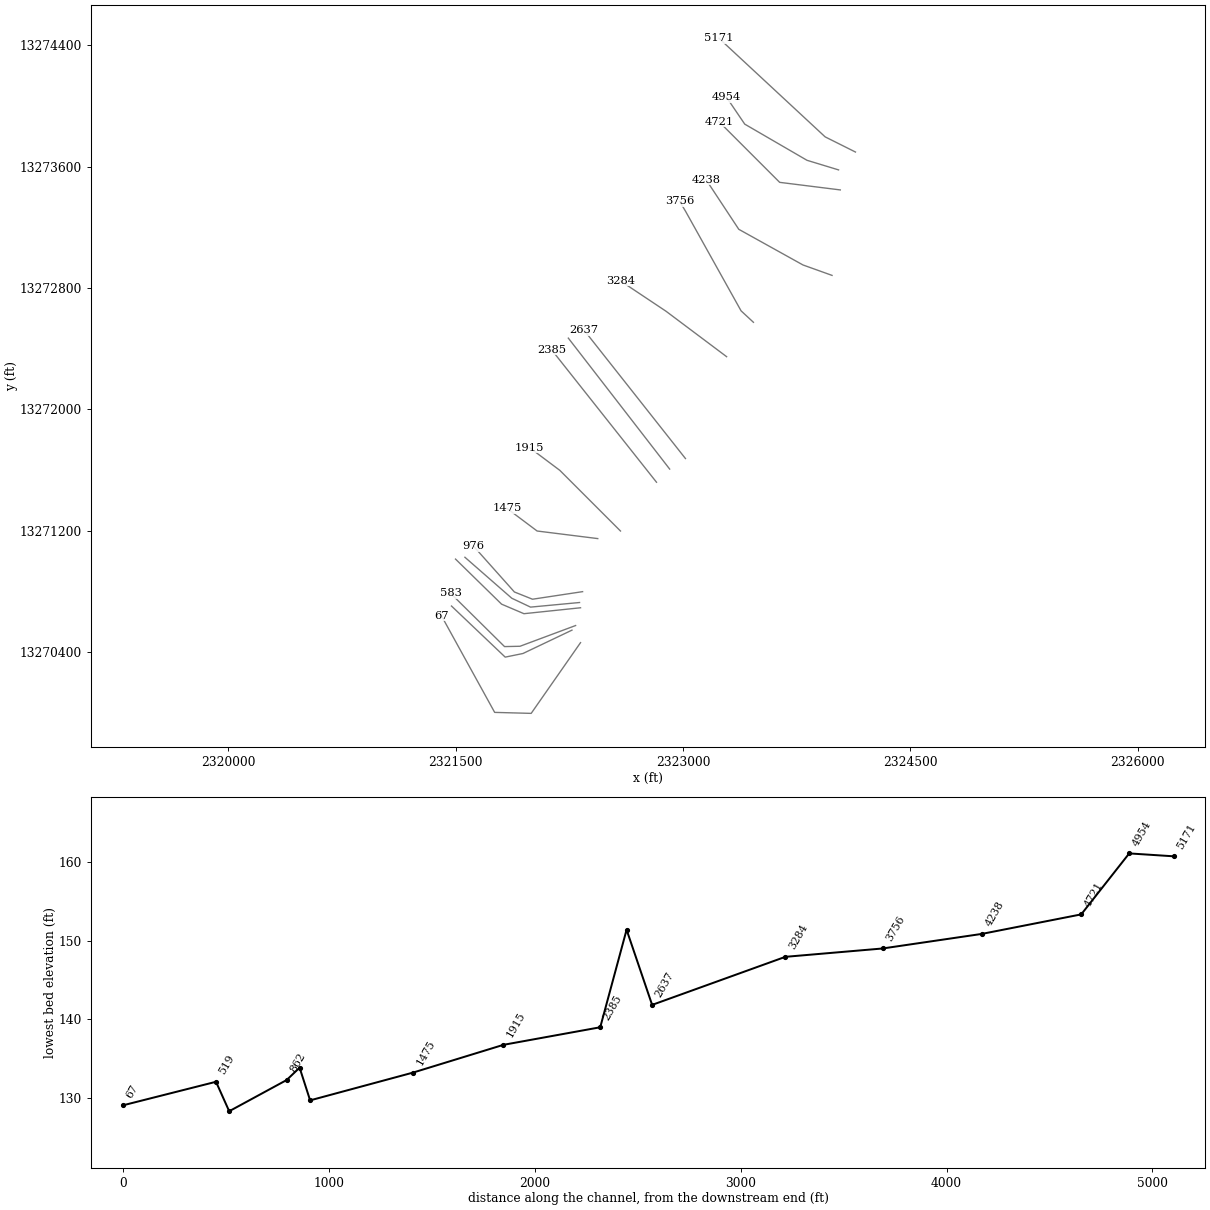
HEC-RAS study UNT010 IN PECR.prj: UNT010 IN PECR Base Level Engineering

--- UNT010 IN PECR.g01 (geometry) --- (continued)

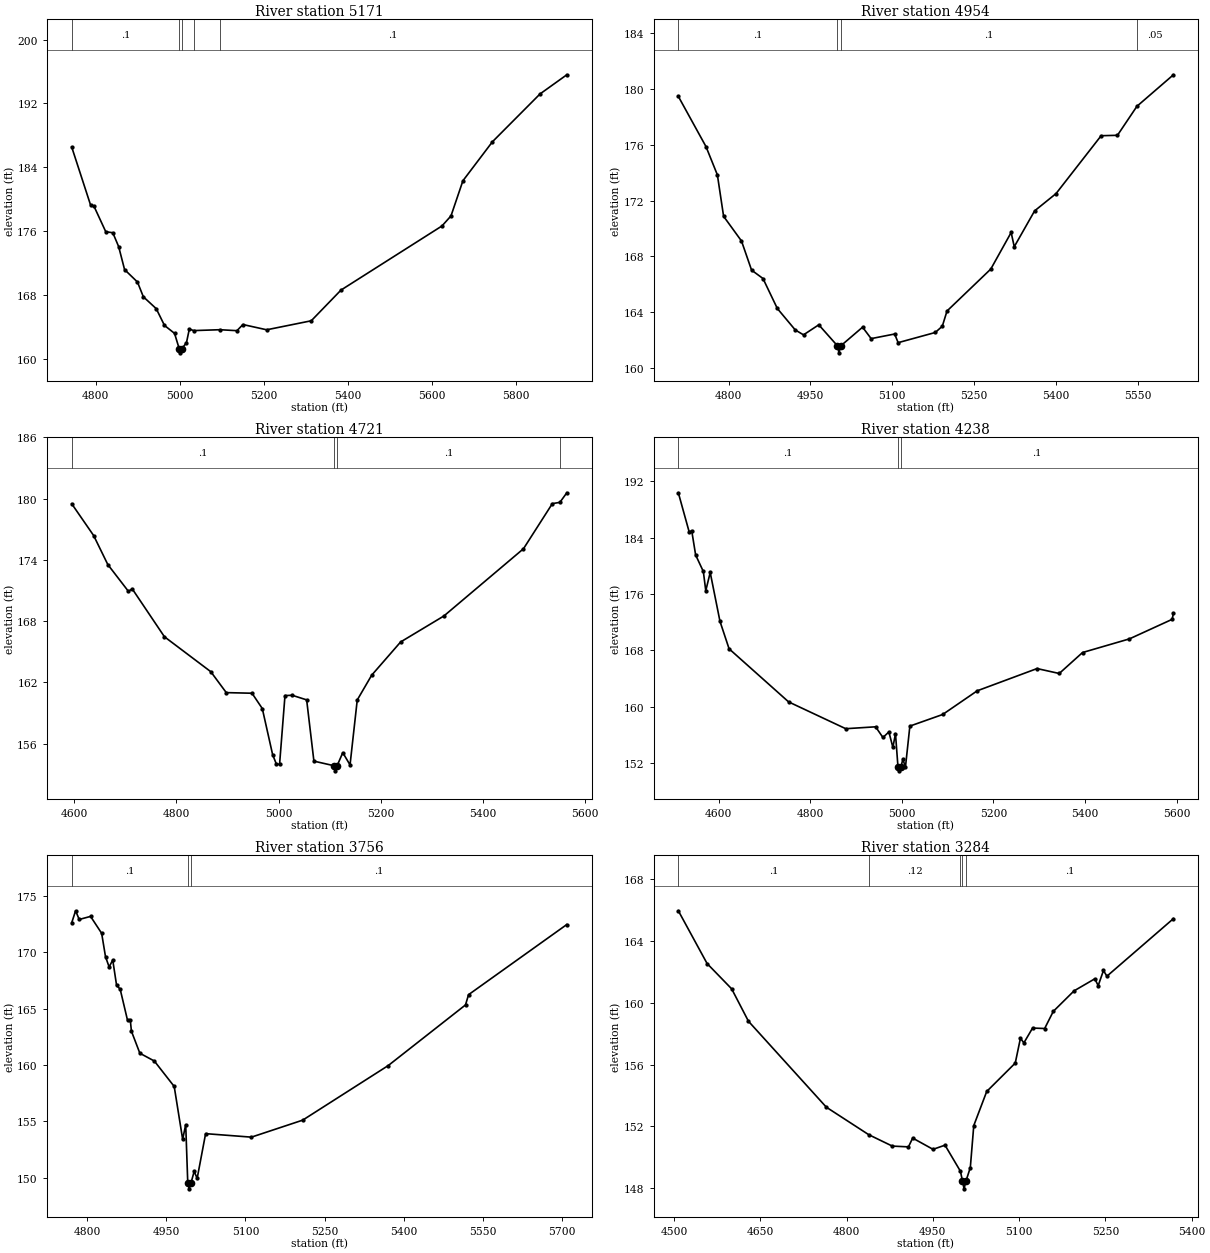
Type RM Length L Ch R = 1 ,5171    ,217,217,217
BEGIN DESCRIPTION:
UNT010 IN PECR 11.0
END DESCRIPTION:
XS GIS Cut Line= 3
      2324137.71     13273696.86      2323937.72     13273796.85
      2323237.75     13274446.83
#Sta/Elev= 30
    4743  186.51  4787.7  179.27  4796.1  179.08    4824   175.9  4840.8  175.77
  4854.8  174.02  4868.8  171.15  4899.5  169.59  4913.5  167.74  4944.2  166.25
  4963.8  164.15  4987.8  163.15    4999  161.21  5001.8  160.71    5005  161.21
  5016.2  161.99    5023  163.69  5033.5   163.5  5095.5  163.61  5136.4  163.49
  5150.6  164.26  5207.2   163.6  5313.3  164.73  5384.1  168.58  5624.5  176.62
    5646  177.88  5674.4  182.29  5744.7  187.18  5858.1  193.18  5921.8  195.58
#Mann= 5 ,-1 , 0
    4743      .1       0    4999     .07       0    5005      .1       0
  5033.5     .16       0  5095.5      .1       0
Bank Sta=4999,5005
XS Rating Curve= 0 ,0
Exp/Cntr=0.3,0.1

Type RM Length L Ch R = 1 ,4954    ,233,233,233
BEGIN DESCRIPTION:
Mapping XS 7064458a
END DESCRIPTION:
XS GIS Cut Line= 4
      2324026.22     13273578.95      2323817.93     13273642.35
      2323407.36     13273880.84      2323286.62     13274058.93
#Sta/Elev= 30
  4707.9  179.47  4758.6  175.87  4779.5  173.84  4790.9  170.87  4823.7   169.1
  4842.2  167.01  4863.1  166.41  4889.4  164.26  4922.3  162.72  4937.4  162.37
  4965.4  163.09  4999.7  161.58  5002.4  161.08  5005.7  161.58  5045.7  162.92
  5061.4   162.1  5104.5  162.43  5110.9  161.81    5179  162.54  5191.9  162.99
  5200.5  164.08  5280.8  167.09  5318.1  169.71  5323.8  168.69  5361.1  171.26
  5400.4   172.5  5483.1  176.65    5513  176.68  5548.7  178.76  5615.6  181.02
#Mann= 4 ,-1 , 0
  4707.9      .1       0  4999.7     .07       0  5005.7      .1       0
  5548.7     .05       0
Bank Sta=4999.7,5005.7
XS Rating Curve= 0 ,0
Exp/Cntr=0.3,0.1

Type RM Length L Ch R = 1 ,4721    ,483,483,483
BEGIN DESCRIPTION:
UNT010 IN PECR 10.0
END DESCRIPTION:
XS GIS Cut Line= 3
      2324037.75     13273446.85      2323637.72     13273496.85
      2323237.74     13273896.84
#Sta/Elev= 30
    4595  179.49  4637.9  176.38  4665.6  173.54  4705.9  170.92  4713.4  171.16
  4776.4  166.47  4867.1  163.05  4897.4     161  4947.8  160.94  4967.9  159.44
  4988.1  154.93  4995.6  153.98  5001.7  153.98  5012.3  160.71  5026.4  160.74
  5054.7  160.29  5068.9  154.29  5108.3  153.84    5111  153.34  5114.3  153.84
  5125.4  155.12  5139.6  153.92  5153.7  160.28    5182  162.71  5238.6  165.96
  5323.4  168.51    5479  175.09  5535.5  179.51  5550.2  179.63  5563.8  180.57
#Mann= 4 ,-1 , 0
    4595      .1       0  5108.3     .07       0  5114.3      .1       0
  5550.2     .08       0
Bank Sta=5108.3,5114.3
XS Rating Curve= 0 ,0
Exp/Cntr=0.3,0.1

Type RM Length L Ch R = 1 ,4238    ,482,482,482
BEGIN DESCRIPTION:
UNT010 IN PECR 9.0
END DESCRIPTION:
XS GIS Cut Line= 4
      2323983.26      13272883.1      2323791.47     13272951.85
      2323368.04     13273187.09      2323151.84       13273515.
#Sta/Elev= 30
  4512.2  190.39  4536.1  184.77  4541.4  185.01    4550  181.54  4566.8   179.2
  4572.1  176.47  4581.8  179.06  4603.1  172.12    4623  168.21    4753  160.66
  4877.7  156.85  4942.9  157.12  4958.9   155.6  4971.9  156.39  4980.6  154.19
  4986.3  156.15  4991.8  151.36  4994.5  150.86  4997.8  151.36  5002.4  152.49
  5008.1  151.42  5017.7  157.22  5089.3  158.87  5164.8  162.24  5295.4   165.4
  5343.8   164.7  5394.7  167.68  5497.1  169.62  5590.4   172.4  5593.1  173.28
#Mann= 3 ,-1 , 0
  4512.2      .1       0  4991.8     .07       0  4997.8      .1       0
Bank Sta=4991.8,4997.8
XS Rating Curve= 0 ,0
Exp/Cntr=0.3,0.1

Type RM Length L Ch R = 1 ,3756    ,472,472,472
BEGIN DESCRIPTION:
UNT010 IN PECR 8.0
END DESCRIPTION:
XS GIS Cut Line= 4
      2323464.69     13272573.69      2323383.21     13272649.14
      2323017.93     13273304.23       2322978.7     13273370.61
#Sta/Elev= 30
  4770.8  172.64  4778.1   173.7    4785  172.93  4806.5   173.2  4827.5   171.7
  4834.8  169.62  4841.7  168.71  4848.5  169.33  4855.8  167.08  4862.6  166.74
  4876.5  163.98  4881.8  163.98  4883.9  163.01  4899.9  161.05  4927.3  160.36
    4965   158.1    4981  153.41  4986.8  154.71  4990.7  149.51  4993.5  149.01
  4996.7  149.51  5002.8  150.56  5008.5  149.94  5024.5  153.91  5111.3   153.6
  5208.5  155.11  5370.7  159.96    5517  165.34  5522.8  166.25    5709  172.48
#Mann= 3 ,-1 , 0
  4770.8      .1       0  4990.7     .07       0  4996.7      .1       0
Bank Sta=4990.7,4996.7
XS Rating Curve= 0 ,0
Exp/Cntr=0.3,0.1

Type RM Length L Ch R = 1 ,3284    ,647,647,647
BEGIN DESCRIPTION:
UNT010 IN PECR 7.0
END DESCRIPTION:
XS GIS Cut Line= 3
      2323287.71     13272346.86      2322887.72     13272646.85
      2322587.76     13272846.83
#Sta/Elev= 30
  4507.7  165.97  4557.7  162.55  4600.4  160.91  4629.6  158.81    4765  153.24
  4838.6  151.46  4879.6  150.72  4907.7  150.67    4915  151.24  4950.4  150.51
  4971.2  150.78    4998  149.09  5001.6  148.45  5004.3  147.95  5007.6  148.45
  5015.2  149.33  5021.2  152.05  5043.7  154.26  5093.3   156.1  5102.3  157.71
  5108.3  157.41  5123.4  158.37  5144.4  158.34  5159.4  159.45  5195.5  160.78
  5231.5  161.56  5237.5  161.12  5246.6   162.1  5252.6  161.73  5368.2  165.46
#Mann= 5 ,-1 , 0
  4507.7      .1       0  4838.6     .12       0    4998      .1       0
  5001.6     .07       0  5007.6      .1       0
Bank Sta=5001.6,5007.6
XS Rating Curve= 0 ,0
Exp/Cntr=0.3,0.1

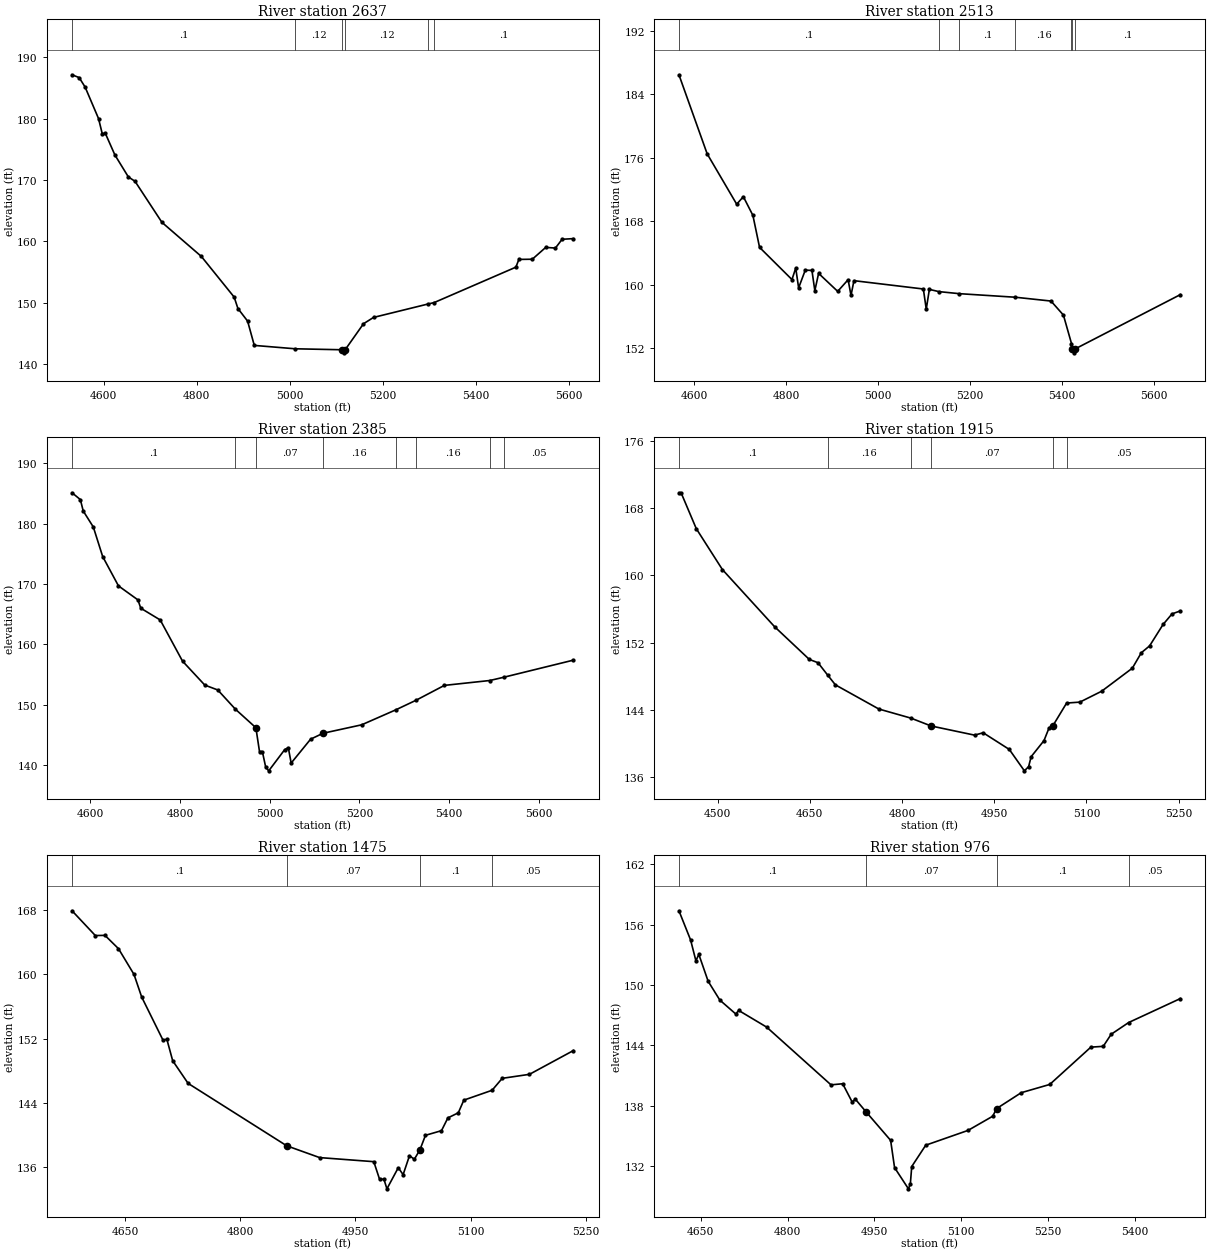
Type RM Length L Ch R = 1 ,2637    ,124,124,124
BEGIN DESCRIPTION:
UNT010 IN PECR 6.0
END DESCRIPTION:
XS GIS Cut Line= 2
      2323016.25     13271674.88      2322347.82     13272521.27
#Sta/Elev= 30
  4531.9  187.15  4547.2  186.69    4560  185.15  4588.9  180.01  4596.9  177.53
  4603.3  177.64  4624.1  174.08    4653  170.51  4667.4  169.79  4725.2  163.11
  4810.1  157.55  4880.6  150.93  4888.7  149.07  4909.5  147.02  4923.9  143.06
    5012  142.51  5113.3  142.35  5116.1  141.85  5119.3  142.35  5158.8  146.59
  5180.4  147.62  5298.4  149.82  5310.5  150.03  5486.6  155.81    5493  157.07
  5521.9   157.1  5550.8  159.03  5571.6  158.92    5586  160.35  5610.4  160.46
#Mann= 6 ,-1 , 0
  4531.9      .1       0    5012     .12       0  5113.3     .07       0
  5119.3     .12       0  5298.4     .16       0  5310.5      .1       0
Bank Sta=5113.3,5119.3
XS Rating Curve= 0 ,0
Exp/Cntr=0.3,0.1

Type RM Length L Ch R = 1 ,2513    ,128,128,128
BEGIN DESCRIPTION:
UNT010 IN PECR 5.0
END DESCRIPTION:
XS GIS Cut Line= 2
       2322912.1     13271605.42      2322243.66     13272469.18
#Sta/Elev= 30
  4566.2  186.45  4627.7  176.48    4692  170.13  4706.5  171.08  4727.3  168.72
  4741.8  164.69  4812.4  160.63  4820.6  162.08  4826.9  159.58  4841.4  161.82
  4855.9  161.78  4862.2  159.23  4870.4  161.41    4912  159.14  4934.7  160.61
    4941  158.63  4947.4  160.49  5098.6  159.44  5104.9   156.9  5111.7  159.39
  5132.4  159.11  5177.1  158.85  5299.2   158.4  5376.6  157.92  5403.7  156.15
  5421.3  152.56  5423.4  151.89  5426.1  151.39  5429.4  151.89  5658.4  158.73
#Mann= 7 ,-1 , 0
  4566.2      .1       0  5132.4     .16       0  5177.1      .1       0
  5299.2     .16       0  5421.3      .1       0  5423.4     .07       0
  5429.4      .1       0
Bank Sta=5423.4,5429.4
XS Rating Curve= 0 ,0
Exp/Cntr=0.3,0.1

Type RM Length L Ch R = 1 ,2385    ,470,470,470
BEGIN DESCRIPTION:
Mapping XS 9c738999
END DESCRIPTION:
XS GIS Cut Line= 2
      2322825.26     13271518.65      2322131.78     13272394.17
#Sta/Elev= 30
  4559.7  185.12  4578.2  183.99  4584.6   182.1  4607.1  179.44  4627.9  174.55
  4663.1  169.68  4706.4  167.36  4712.8  165.98  4756.1  164.03  4805.8   157.2
  4855.4  153.23  4884.3  152.42  4923.6  149.23  4969.2  146.16  4977.3  142.19
  4983.7  142.18  4991.1  139.61  4997.8  139.01  5033.3  142.52  5041.4  142.86
  5047.8   140.3  5091.1  144.26  5118.7  145.24  5204.8  146.64  5280.7  149.12
  5326.1  150.72  5389.1  153.18  5490.3  153.99  5521.4  154.53  5676.6  157.37
#Mann= 8 ,-1 , 0
  4559.7      .1       0  4923.6     .16       0  4969.2     .07       0
  5118.7     .16       0  5280.7      .1       0  5326.1     .16       0
  5490.3      .1       0  5521.4     .05       0
Bank Sta=4969.2,5118.7
XS Rating Curve= 0 ,0
Exp/Cntr=0.3,0.1

Type RM Length L Ch R = 1 ,1915    ,440,440,440
BEGIN DESCRIPTION:
UNT010 IN PECR 4.0
END DESCRIPTION:
XS GIS Cut Line= 3
      2322587.69     13271196.89      2322187.72     13271596.85
      2321987.75     13271746.83
#Sta/Elev= 30
  4437.1   169.8  4440.6   169.8  4465.3  165.54  4507.8  160.68  4592.6   153.9
  4649.2  150.01  4663.3  149.62    4679  148.15  4691.6  146.99  4762.3  144.12
  4814.4  143.04  4847.2  142.11  4917.9  141.02    4932   141.3  4974.5  139.32
    4999  136.78  5005.9  137.28    5010  138.46  5030.9  140.37  5039.2  141.89
  5045.4  142.14  5067.7  144.83  5089.2  144.94  5124.6  146.23  5174.6  148.97
  5189.2   150.8  5202.7  151.62  5224.6  154.16  5239.2  155.42  5252.7  155.77
#Mann= 6 ,-1 , 0
  4437.1      .1       0    4679     .16       0  4814.4      .1       0
  4847.2     .07       0  5045.4      .1       0  5067.7     .05       0
Bank Sta=4847.2,5045.4
XS Rating Curve= 0 ,0
Exp/Cntr=0.3,0.1

Type RM Length L Ch R = 1 ,1475    ,499,499,499
BEGIN DESCRIPTION:
UNT010 IN PECR 3.0
END DESCRIPTION:
XS GIS Cut Line= 3
      2322437.76     13271146.85      2322037.72     13271196.85
      2321837.68     13271346.88
#Sta/Elev= 30
  4580.9  167.95  4611.2  164.86  4623.8  164.88  4641.4  163.22  4661.6  160.01
  4671.6  157.19  4699.4   151.8  4704.4  151.92    4712  149.24  4732.1  146.41
  4860.6  138.62  4903.4  137.15    4974  136.64  4981.5  134.45  4987.2  134.45
  4991.1  133.25  5005.9  135.89  5012.2  135.02  5020.5  137.39  5026.8  136.94
  5034.1  138.12  5041.3  139.93  5062.2  140.51  5070.5   142.1  5084.1  142.74
  5091.3  144.32  5128.1  145.55  5141.3  147.04  5176.8  147.54  5234.1  150.51
#Mann= 4 ,-1 , 0
  4580.9      .1       0  4860.6     .07       0  5034.1      .1       0
  5128.1     .05       0
Bank Sta=4860.6,5034.1
XS Rating Curve= 0 ,0
Exp/Cntr=0.3,0.1

Type RM Length L Ch R = 1 ,976     ,51,51,51
BEGIN DESCRIPTION:
UNT010 IN PECR 2.0
END DESCRIPTION:
XS GIS Cut Line= 4
      2322337.67     13270796.85      2322007.28     13270746.93
      2321887.92     13270794.67      2321618.84      13271096.3
#Sta/Elev= 30
  4612.3  157.38  4632.5  154.47  4641.6  152.41  4646.7  153.04  4662.8  150.37
    4683   148.5  4710.5  147.12  4715.6  147.47    4764  145.81  4875.2  140.07
  4895.4  140.18    4912  138.34  4917.1  138.66  4935.9  137.38  4978.3  134.55
  4985.1  131.84  5009.1  129.73  5012.4  130.23  5014.8  131.95    5039  134.07
  5112.1  135.54  5154.8  136.95  5161.5  137.71  5204.1  139.29  5253.4  140.11
  5324.5  143.82  5345.9   143.9  5359.6   145.1  5389.9  146.27  5479.2  148.65
#Mann= 4 ,-1 , 0
  4612.3      .1       0  4935.9     .07       0  5161.5      .1       0
  5389.9     .05       0
Bank Sta=4935.9,5161.5
XS Rating Curve= 0 ,0
Exp/Cntr=0.3,0.1

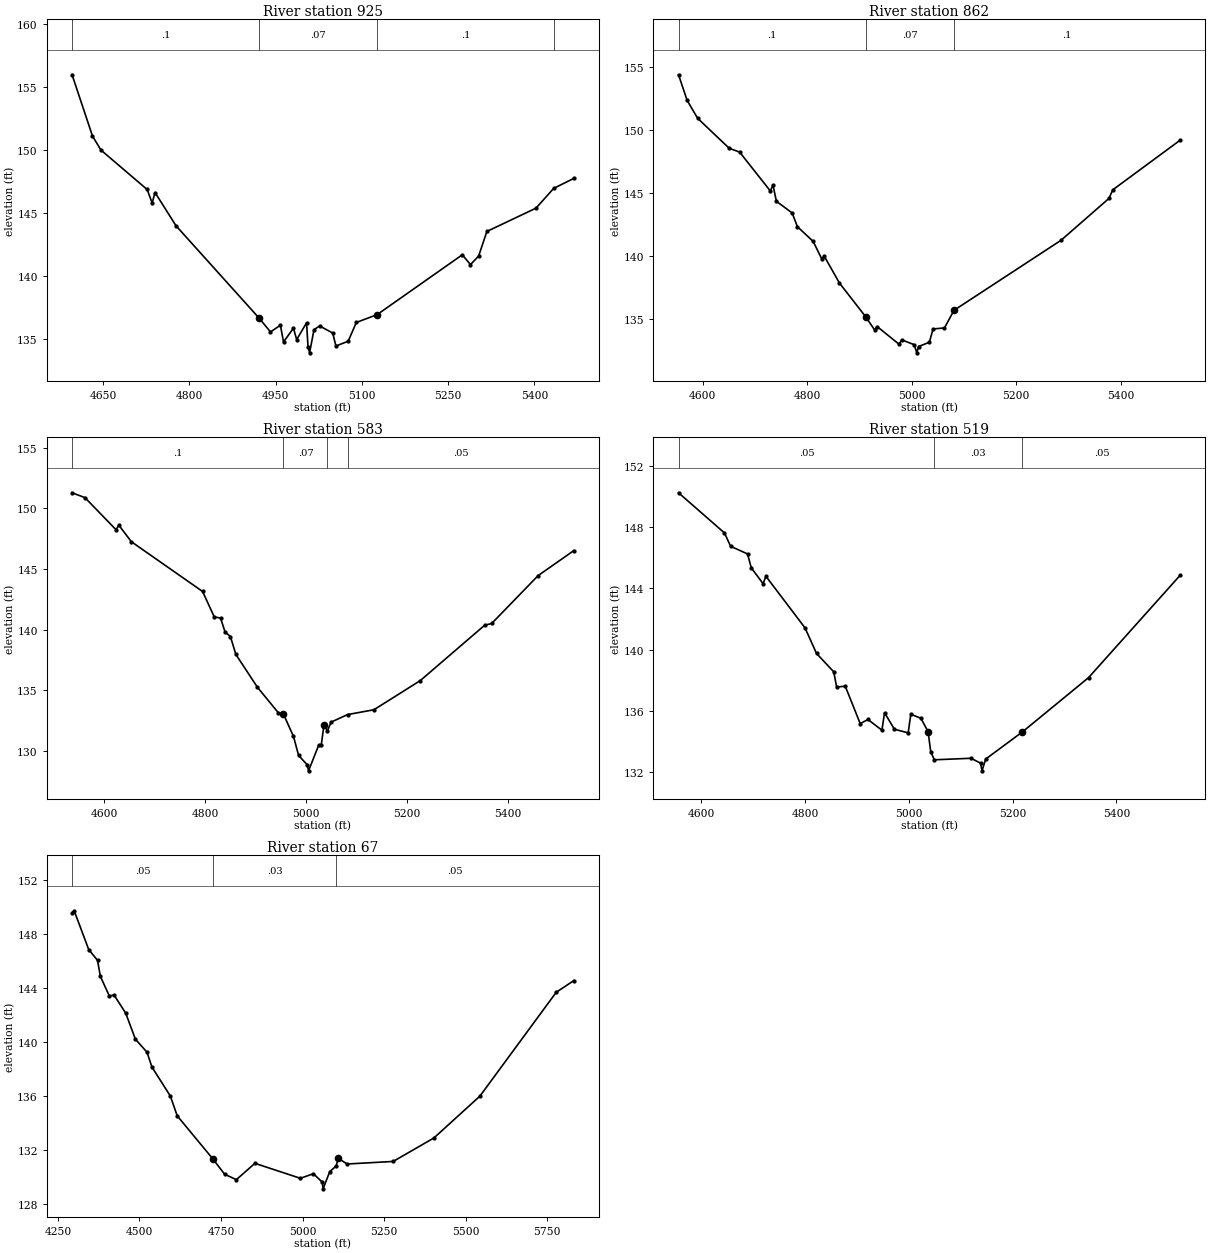
Type RM Length L Ch R = 1 ,925     ,63,63,63
BEGIN DESCRIPTION:
Mapping XS 46475f68
END DESCRIPTION:
XS GIS Cut Line= 4
       2322317.6     13270725.23      2321994.26     13270694.85
      2321870.56     13270753.44      2321561.45     13271023.64
#Sta/Elev= 30
  4596.4  155.94  4631.9  151.08  4646.5  149.97  4726.9  146.84  4735.6  145.77
  4740.6   146.6  4777.1  143.96  4921.2  136.65  4941.3  135.54  4958.5  136.07
    4964  134.74  4981.2  135.84  4986.8  134.93    5004  136.26  5006.5  134.38
  5009.3  133.88  5016.9  135.72  5026.7  136.01  5049.5  135.45    5055  134.42
  5076.3   134.8  5090.5  136.29  5126.6  136.91  5274.7  141.66  5288.9  140.88
  5303.1  141.56  5317.4  143.51  5402.8  145.36  5433.6  146.93  5468.6  147.72
#Mann= 4 ,-1 , 0
  4596.4      .1       0  4921.2     .07       0  5126.6      .1       0
  5433.6     .05       0
Bank Sta=4921.2,5126.6
XS Rating Curve= 0 ,0
Exp/Cntr=0.3,0.1

Type RM Length L Ch R = 1 ,862     ,279,279,279
BEGIN DESCRIPTION:
Mapping XS b9410f0f
END DESCRIPTION:
XS GIS Cut Line= 4
      2322324.12     13270690.51      2321950.85     13270651.44
      2321803.28     13270714.38      2321499.48     13271011.67
#Sta/Elev= 30
  4553.4  154.42  4569.9  152.38    4590  150.96  4650.3  148.58  4670.4  148.27
  4729.2  145.18  4734.2  145.65  4740.8  144.36    4771  143.43    4781  142.34
  4811.2  141.17  4827.5  139.79  4832.5  139.99  4861.5  137.86  4911.7  135.18
  4928.7  134.14  4933.7   134.4  4975.5     133  4980.9  133.34  5004.5  132.96
  5009.7  132.31  5012.9  132.81  5033.6  133.15  5040.8  134.21  5062.6  134.29
  5080.8  135.69  5285.8  141.26  5377.6  144.59  5384.8  145.27  5514.2  149.23
#Mann= 3 , 0 , 0
  4553.4      .1       0  4911.7     .07       0  5080.8      .1       0
Bank Sta=4911.7,5080.8
XS Rating Curve= 0 ,0
Exp/Cntr=0.3,0.1

Type RM Length L Ch R = 1 ,583     ,64,64,64
BEGIN DESCRIPTION:
Mapping XS bd6910e1
END DESCRIPTION:
XS GIS Cut Line= 4
       2322291.6     13270573.33      2321924.81      13270436.6
      2321822.82     13270434.43      2321466.93     13270785.97
#Sta/Elev= 30
  4536.8  151.29  4562.3  150.89  4623.9  148.24  4629.3  148.62  4654.3  147.25
  4795.2  143.15  4818.4  141.05  4830.9  140.95  4839.8   139.8  4850.4  139.43
  4861.2  137.95  4903.8  135.25  4945.3  133.14  4955.3  133.04  4975.3  131.19
  4985.4  129.62  5002.4  128.85  5005.1  128.35  5025.3  130.48  5030.3  130.48
  5035.6  132.12  5042.6  131.66  5049.8  132.37  5082.3  132.99  5134.6  133.39
  5226.5   135.8  5353.8  140.36  5367.9  140.51  5459.8  144.46  5530.5  146.52
#Mann= 4 ,-1 , 0
  4536.8      .1       0  4955.3     .07       0  5042.6      .1       0
  5082.3     .05       0
Bank Sta=4955.3,5035.6
XS Rating Curve= 0 ,0
Exp/Cntr=0.3,0.1

Type RM Length L Ch R = 1 ,519     ,452,452,452
BEGIN DESCRIPTION:
Mapping XS 5d235147
END DESCRIPTION:
XS GIS Cut Line= 4
      2322267.65     13270542.92      2321944.34     13270388.86
      2321827.16     13270364.99      2321472.87     13270701.99
#Sta/Elev= 30
  4556.5  150.23    4645  147.61  4656.8  146.74  4689.4  146.24  4696.7  145.33
  4719.4   144.3  4724.9  144.78  4800.1  141.42  4822.3  139.75  4855.5  138.55
  4861.1  137.56  4877.7  137.61  4906.5  135.17  4921.4  135.44  4948.3  134.74
  4953.4  135.88  4972.4   134.8  4998.9  134.57    5004  135.78  5023.4  135.52
 5037.32  134.64  5042.3  133.35  5049.2  132.81    5120  132.91  5138.4  132.59
  5141.1  132.09  5148.3  132.86    5219  134.63  5346.4  138.17  5523.2  144.86
#Mann= 3 ,-1 , 0
  4556.5     .05       0  5049.2     .03       0    5219     .05       0
Bank Sta=5037.32,5219
XS Rating Curve= 0 ,0
Exp/Cntr=0.3,0.1

Type RM Length L Ch R = 1 ,67      ,0,0,0
BEGIN DESCRIPTION:
UNT010 IN PECR 1.0
END DESCRIPTION:
XS GIS Cut Line= 4
      2322324.13     13270460.49       2321998.6     13269993.89
      2321757.71      13270000.4      2321406.14     13270638.44
#Sta/Elev= 30
  4293.5  149.56    4300   149.7  4344.5  146.83  4371.5  146.03  4380.3  144.84
  4407.7  143.39  4422.1  143.46  4457.9  142.12  4487.6  140.19  4523.3  139.22
  4538.2  138.13  4594.9  135.97  4615.8  134.51  4724.7  131.33  4761.3  130.18
  4797.3  129.78    4854  130.99  4993.4  129.88  5033.4  130.22  5060.4   129.6
  5063.1   129.1  5083.4  130.37  5103.4   130.8  5109.4  131.36  5136.9  130.94
  5277.9  131.13  5402.9  132.87  5543.9  135.97  5777.8  143.66  5831.9  144.53
#Mann= 3 ,-1 , 0
  4293.5     .05       0  4724.7     .03       0  5103.4     .05       0
Bank Sta=4724.7,5109.4
XS Rating Curve= 0 ,0
Exp/Cntr=0.3,0.1

Chan Stop Cuts=-1
Use User Specified Reach Order=0
Composite Channel Slope=5