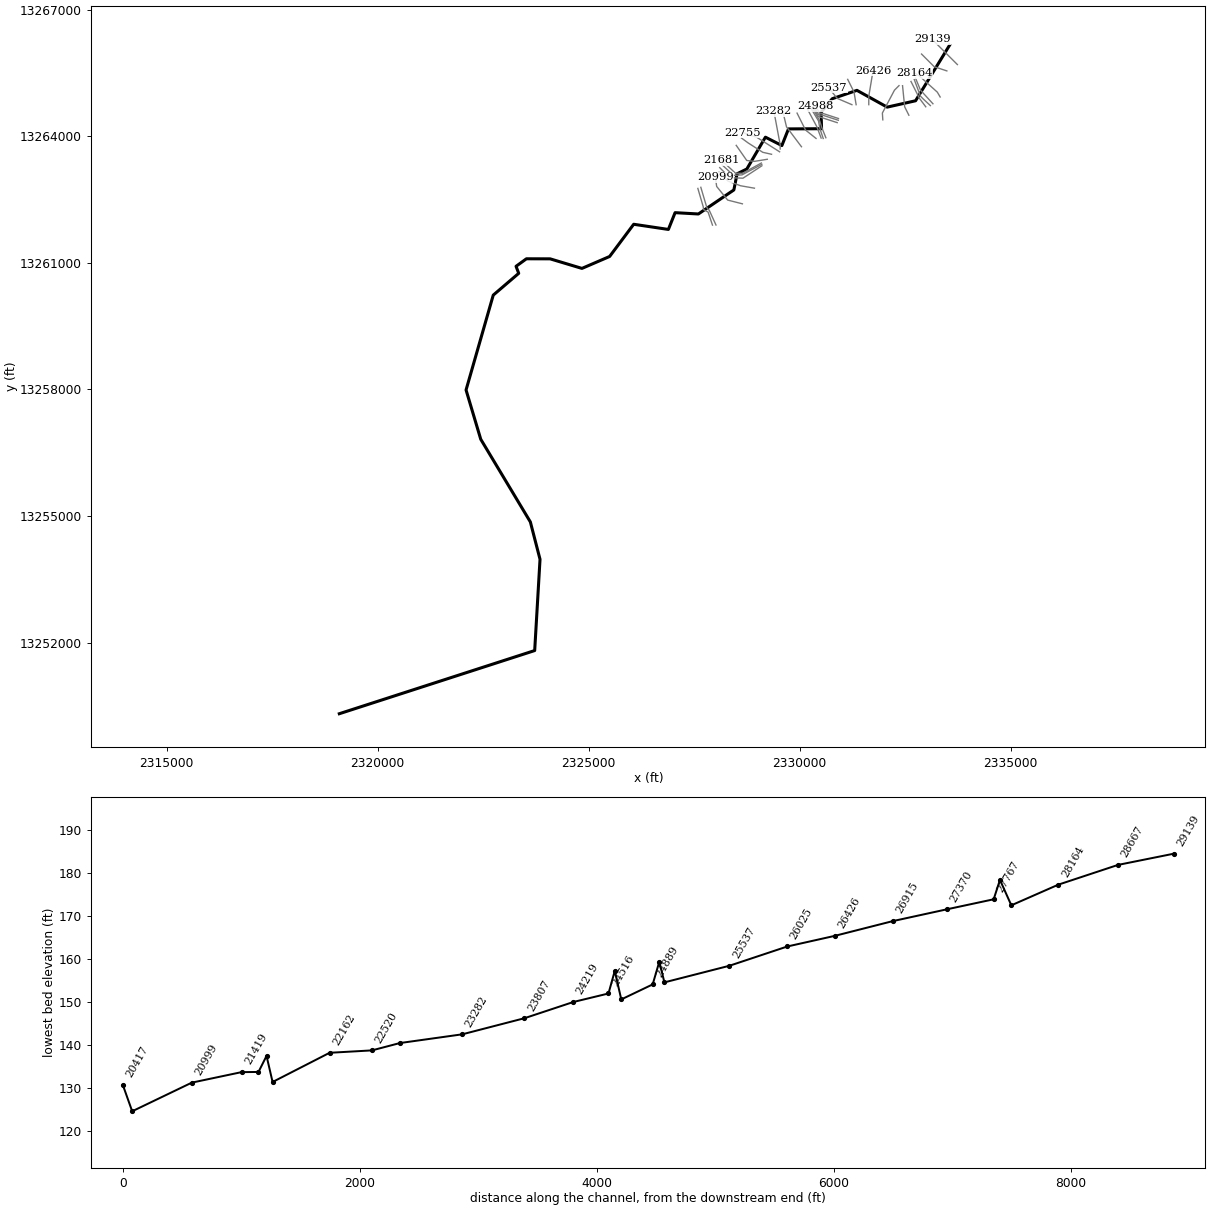
--- UNT011 IN PECR.prj (project) ---

Proj Title=UNT011 IN PECR Base Level Engineering
Current Plan=p01
Default Exp/Contr=0.3,0.1
English Units
Geom File=g01
Flow File=f01
Plan File=p01
Y Axis Title=Elevation
X Axis Title(PF)=Main Channel Distance
X Axis Title(XS)=Station
BEGIN DESCRIPTION:
UNT011 IN PECR
END DESCRIPTION:
DSS Export Rating Curves= 0
DSS Export Rating Curve Sorted= 0
DSS Export Volume Flow Curves= 0
DXF OffsetX= 0
DXF OffsetY= 0
DXF ScaleX= 1
DXF ScaleY= 10

--- UNT011 IN PECR.p01 (plan) ---

Plan Title=Multiple Run
Short Identifier=Multiple
Geom File=g01
Flow File=f01
Subcritical Flow
K Sum by GR= 0
Std Step Tol= 0.01
Critical Tol= 0.01
Num of Std Step Trials= 20
Max Error Tol= 0.3
Flow Tol Ratio= 0.001
Split Flow NTrial= 30
Split Flow Tol= 0.02
Split Flow Ratio= 0.02
Log Output Level= 0
Friction Slope Method= 1
Unsteady Friction Slope Method= 2
Unsteady Bridges Friction Slope Method= 1
Parabolic Critical Depth
Global Vel Dist=  1 , 1 , 1
Global Log Level= 0
CheckData=True
Encroach Param= -1, 0, 0, 0
BEGIN DESCRIPTION:
Multiple Run
END DESCRIPTION:

--- UNT011 IN PECR.f01 (steady flow) ---

Flow Title=Multiple
Program Version=4.10
Number of Profiles= 7
Profile Names=10-year,25-year,50-year,1pct_min,100-year,1pct_plu,500-year
River Rch & RM=UNT011 IN PECR,Reach-1         ,29139
     465     637     777     691     935    1264    1358
River Rch & RM=UNT011 IN PECR,Reach-1         ,28164
    1056    1519    1912    1754    2371    3207    3665
River Rch & RM=UNT011 IN PECR,Reach-1         ,16826
    1090    1573    1984    1822    2464    3333    3822
River Rch & RM=UNT011 IN PECR,Reach-1         ,14626
    1302    1892    2399    2214    2994    4048    4684
Boundary for River Rch & Prof#=UNT011 IN PECR,Reach-1         , 1
Up Type= 0
Dn Type= 3
Dn Slope=0.0045
Boundary for River Rch & Prof#=UNT011 IN PECR,Reach-1         , 2
Up Type= 0
Dn Type= 3
Dn Slope=0.0045
Boundary for River Rch & Prof#=UNT011 IN PECR,Reach-1         , 3
Up Type= 0
Dn Type= 3
Dn Slope=0.0045
Boundary for River Rch & Prof#=UNT011 IN PECR,Reach-1         , 4
Up Type= 0
Dn Type= 3
Dn Slope=0.0045
Boundary for River Rch & Prof#=UNT011 IN PECR,Reach-1         , 5
Up Type= 0
Dn Type= 3
Dn Slope=0.0045
Boundary for River Rch & Prof#=UNT011 IN PECR,Reach-1         , 6
Up Type= 0
Dn Type= 3
Dn Slope=0.0045
Boundary for River Rch & Prof#=UNT011 IN PECR,Reach-1         , 7
Up Type= 0
Dn Type= 3
Dn Slope=0.0045
DSS Import GetInterval= 0
DSS Import GetPeak= 0
DSS Import FillOption= 0

--- UNT011 IN PECR.g01 (geometry) ---

Geom Title=Existing Conditions
Program Version=4.10

River Reach=UNT011 IN PECR  ,Reach-1
Reach XY= 30
      2333551.66     13266155.04      2332746.42     13264839.46
      2332073.34     13264688.72      2331357.04     13265086.17
      2330772.61     13264888.27      2330506.46     13264566.91
      2330518.44     13264177.33      2329734.57     13264172.64
      2329577.84     13263778.13      2329187.72     13263976.86
      2328747.61     13263222.82      2328515.84      13263109.1
       2328440.2     13262726.47      2327599.17     13262156.84
      2327047.09     13262188.09      2326888.23     13261790.53
      2326066.18     13261912.92      2325495.87      13261149.9
      2324839.62     13260867.17      2324086.15     13261093.74
      2323523.49     13261095.16      2323277.72     13260916.85
      2323341.36     13260750.64      2322737.78     13260234.38
      2322093.01     13257986.65      2322441.42     13256818.75
      2323616.97     13254859.98      2323846.13     13253974.56
       2323719.7     13251812.06      2319089.35      13250315.3

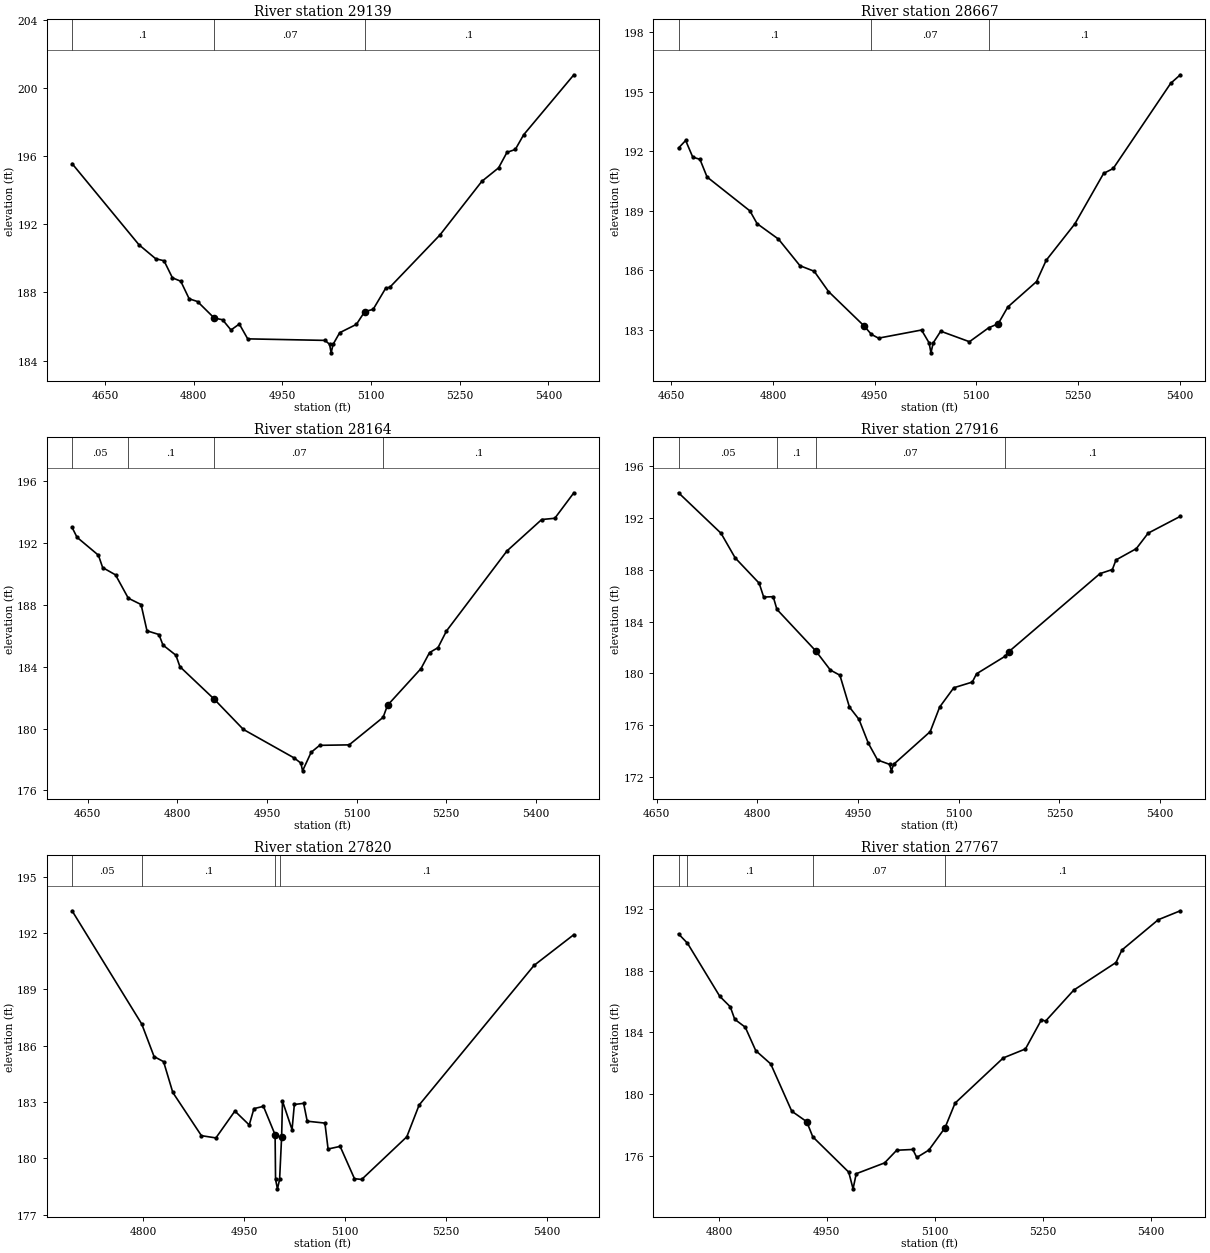
Type RM Length L Ch R = 1 ,29139   ,472,472,472
BEGIN DESCRIPTION:
UNT011 IN PECR 53.0
END DESCRIPTION:
XS GIS Cut Line= 3
       2333737.7     13265696.88      2333437.72     13265996.85
      2333137.72     13266296.86
#Sta/Elev= 30
  4594.5  195.56  4707.6   190.8  4735.9  189.98    4750  189.86  4764.2  188.86
  4778.3  188.66  4792.5  187.63  4806.6  187.47  4834.9   186.5    4849   186.4
  4863.2   185.8  4877.3  186.15  4891.5  185.28  5022.3  185.19  5029.9  184.96
  5032.6  184.46  5035.9  184.96    5047  185.64  5075.3  186.13  5089.4  186.88
  5103.6  187.01  5124.8  188.25  5131.9  188.31  5216.7  191.38  5287.4  194.52
  5315.7  195.31  5329.9  196.22    5344  196.39  5358.1  197.25    5443  200.77
#Mann= 3 , 0 , 0
  4594.5      .1       0  4834.9     .07       0  5089.4      .1       0
Bank Sta=4834.9,5089.4
XS Rating Curve= 0 ,0
Exp/Cntr=0.3,0.1

Type RM Length L Ch R = 1 ,28667   ,503,503,503
BEGIN DESCRIPTION:
UNT011 IN PECR 52.0
END DESCRIPTION:
XS GIS Cut Line= 3
      2333487.69     13265546.87      2333187.72     13265646.85
      2332887.69     13265946.89
#Sta/Elev= 30
  4660.7  192.17  4671.2  192.55  4681.7  191.71  4692.3   191.6  4702.8  190.71
  4766.1     189  4776.6  188.36  4808.2  187.58  4839.9  186.24  4860.9  185.96
    4882  184.94  4934.7   183.2  4945.3  182.78  4955.8  182.59  5019.3     183
  5030.5  182.35  5033.2  181.85  5036.5  182.35  5047.6  182.94    5090  182.41
  5118.3  183.11  5132.5  183.32  5146.6  184.16    5189  185.44  5203.2  186.51
  5245.6  188.35    5288  190.89  5302.2  191.14    5387  195.43  5401.2  195.86
#Mann= 3 ,-1 , 0
  4660.7      .1       0  4945.3     .07       0  5118.3      .1       0
Bank Sta=4934.7,5132.5
XS Rating Curve= 0 ,0
Exp/Cntr=0.3,0.1

Type RM Length L Ch R = 1 ,28164   ,397,397,397
BEGIN DESCRIPTION:
UNT011 IN PECR 51.0
END DESCRIPTION:
XS GIS Cut Line= 4
      2333329.46     13264928.91      2333261.75      13265043.5
      2332834.66     13265428.91      2332721.43     13265495.82
#Sta/Elev= 30
  4623.8  193.02  4632.1  192.38  4667.9  191.22    4675  190.42  4696.5  189.95
  4717.9  188.44  4739.3  188.03  4749.2  186.33  4769.2  186.09  4775.9  185.41
  4797.6  184.75  4804.3  184.01  4861.1  181.93  4910.5  179.95  4995.7   178.1
  5006.8  177.77  5009.6  177.27    5024  178.47  5038.2  178.92  5087.6  178.95
  5144.4  180.73  5151.8  181.51  5207.9  183.89  5222.1  184.92  5236.3  185.24
  5250.5  186.32  5351.8   191.5  5409.9  193.53  5431.8  193.61  5463.7  195.26
#Mann= 4 ,-1 , 0
  4623.8     .05       0  4717.9      .1       0  4861.1     .07       0
  5144.4      .1       0
Bank Sta=4861.1,5151.8
XS Rating Curve= 0 ,0
Exp/Cntr=0.3,0.1

Type RM Length L Ch R = 1 ,27916   ,96,96,96
BEGIN DESCRIPTION:
Mapping XS 3a430da2
END DESCRIPTION:
XS GIS Cut Line= 3
      2333158.23     13264768.17      2332863.08     13265091.09
      2332745.03     13265377.53
#Sta/Elev= 30
  4682.7  193.96    4746  190.83    4767  188.93  4802.8  186.97  4809.5   185.9
  4823.7  185.93  4829.2  184.95  4887.2  181.73  4908.8  180.26    4923  179.86
  4937.2   177.4  4951.4  176.45  4965.4   174.6  4979.1  173.31    4997  172.97
  4999.8  172.47    5003  172.97  5057.5   175.5  5071.6   177.4  5092.6  178.89
  5120.2  179.33  5126.5  179.97  5168.9  181.32  5174.4  181.67  5310.3  187.71
  5328.8  188.03  5334.2  188.77  5364.4  189.64  5382.1  190.84    5430  192.14
#Mann= 4 ,-1 , 0
  4682.7     .05       0  4829.2      .1       0  4887.2     .07       0
  5168.9      .1       0
Bank Sta=4887.2,5174.4
XS Rating Curve= 0 ,0
Exp/Cntr=0.3,0.1

Type RM Length L Ch R = 1 ,27820   ,53,53,53
BEGIN DESCRIPTION:
Mapping XS f040a55c
END DESCRIPTION:
XS GIS Cut Line= 5
      2333097.43      13264724.8      2332930.79     13264879.29
      2332857.87     13264953.94      2332842.25     13265000.82
       2332715.7     13265342.33
#Sta/Elev= 30
  4694.8  193.18  4798.3  187.15  4816.6  185.42  4830.7  185.15  4844.4  183.51
  4886.9  181.21  4908.4  181.09  4936.6  182.52  4957.9  181.78  4964.9  182.65
    4979  182.77 4996.31  181.26    4997  178.88  4999.8  178.38    5003  178.88
 5006.02  181.16  5007.3  183.05  5021.5  181.53  5024.9  182.87  5038.7  182.93
    5044  181.98  5070.3  181.88    5075   180.5  5092.9  180.64  5114.2  178.92
  5124.9  178.88  5191.9  181.15  5210.2  182.84  5380.8  190.27    5440  191.91
#Mann= 4 ,-1 , 0
  4694.8     .05       0  4798.3      .1       0 4996.31     .07       0
    5003      .1       0
Bank Sta=4996.31,5006.02
XS Rating Curve= 0 ,0
Exp/Cntr=0.3,0.1

Type RM Length L Ch R = 1 ,27767   ,397,397,397
BEGIN DESCRIPTION:
UNT011 IN PECR 50.0
END DESCRIPTION:
XS GIS Cut Line= 3
      2332987.72     13264696.86      2332837.72     13264896.85
      2332637.72     13265296.85
#Sta/Elev= 30
  4743.9  190.38  4756.3  189.78  4801.2  186.34  4815.8  185.66    4822  184.85
  4836.6  184.34  4851.2  182.82    4872  181.96  4901.2   178.9    4922  178.22
  4930.4  177.24  4980.4  174.95  4986.4  173.87  4990.8  174.85  5030.2  175.55
    5047  176.37  5069.4  176.42  5074.9   175.9  5091.7  176.38  5114.1  177.82
  5128.1  179.42  5195.1  182.35  5225.9  182.93  5248.2  184.83  5253.8  184.73
    5293  186.74  5351.7  188.53    5360  189.34  5410.4   191.3  5441.1  191.88
#Mann= 4 ,-1 , 0
  4743.9     .05       0  4756.3      .1       0  4930.4     .07       0
  5114.1      .1       0
Bank Sta=4922,5114.1
XS Rating Curve= 0 ,0
Exp/Cntr=0.3,0.1

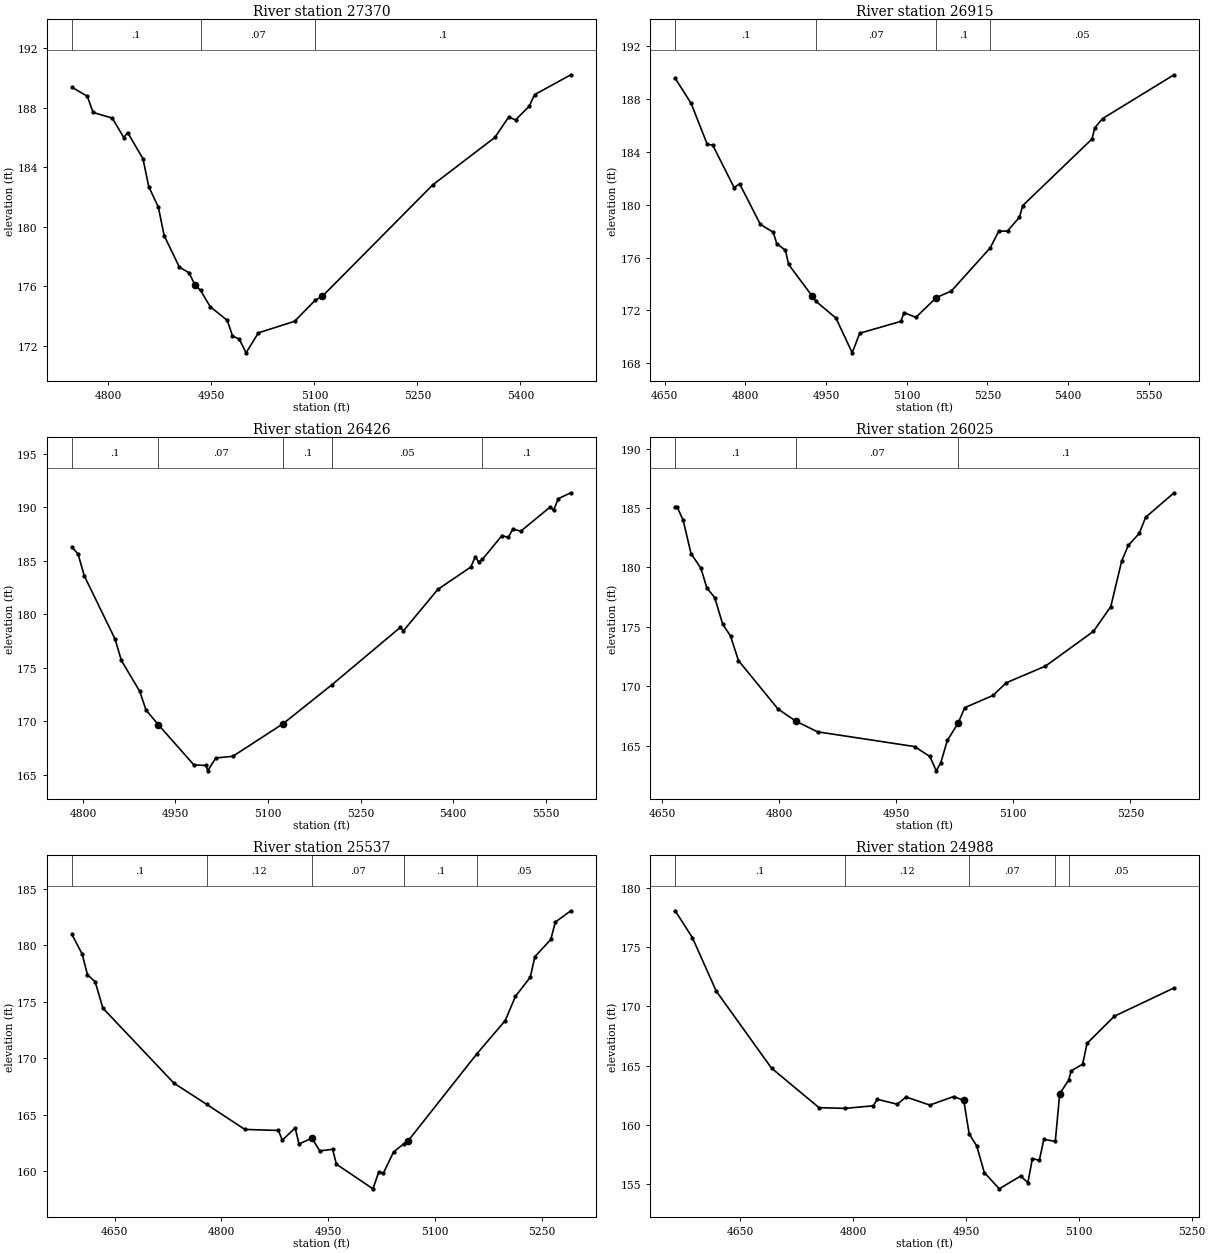
Type RM Length L Ch R = 1 ,27370   ,455,455,455
BEGIN DESCRIPTION:
UNT011 IN PECR 49.0
END DESCRIPTION:
XS GIS Cut Line= 3
      2332587.72     13264496.85      2332487.72     13264696.85
      2332437.72     13265196.85
#Sta/Elev= 30
  4747.1  189.37  4769.5  188.77  4777.9  187.68  4805.8   187.3  4822.6  185.99
  4828.2  186.33  4850.5  184.57  4858.9   182.7  4872.9  181.32  4881.3  179.41
  4903.6  177.28  4917.6  176.91    4926   176.1  4934.4  175.72  4948.4  174.63
  4973.2  173.71  4980.8  172.67  4990.8  172.44  5000.6  171.53  5018.4  172.87
  5071.2  173.65  5101.4  175.07  5111.4  175.32  5272.2  182.81  5362.7     186
  5382.8  187.37  5392.8  187.18  5412.9  188.11  5420.4  188.87  5473.2  190.21
#Mann= 3 ,-1 , 0
  4747.1      .1       0  4934.4     .07       0  5101.4      .1       0
Bank Sta=4926,5111.4
XS Rating Curve= 0 ,0
Exp/Cntr=0.3,0.1

Type RM Length L Ch R = 1 ,26915   ,489,489,489
BEGIN DESCRIPTION:
UNT011 IN PECR 48.0
END DESCRIPTION:
XS GIS Cut Line= 4
      2331970.08     13264387.28      2331959.66      13264548.7
      2332246.12     13265090.37      2332354.09     13265198.34
#Sta/Elev= 30
  4669.7  189.55  4699.3  187.65  4729.4  184.55  4739.4   184.5  4779.2  181.29
  4789.5  181.57    4828  178.51    4852  177.91  4858.5  177.05  4874.6  176.55
  4880.5  175.48  4924.5  173.08  4931.2   172.7  4968.6  171.42  4998.8   168.8
  5012.6  170.28  5089.3  171.18  5094.9  171.84    5117  171.48  5155.3  172.98
    5183  173.47  5255.2  176.73    5271  177.98  5287.4  178.01  5309.4  179.04
  5315.8  179.93  5444.2  184.95  5449.9  185.82  5464.1   186.5  5596.9  189.81
#Mann= 4 ,-1 , 0
  4669.7      .1       0  4931.2     .07       0  5155.3      .1       0
  5255.2     .05       0
Bank Sta=4924.5,5155.3
XS Rating Curve= 0 ,0
Exp/Cntr=0.3,0.1

Type RM Length L Ch R = 1 ,26426   ,401,401,401
BEGIN DESCRIPTION:
UNT011 IN PECR 47.0
END DESCRIPTION:
XS GIS Cut Line= 3
      2331637.72     13264746.84      2331637.72     13264946.85
      2331737.72     13265546.87
#Sta/Elev= 30
  4782.2  186.29  4792.2  185.61  4802.2  183.59  4852.2  177.67  4862.2   175.7
  4892.2  172.79  4902.2  171.06  4922.2  169.69  4979.7  165.94  4999.5  165.88
  5002.2  165.38  5015.2  166.58    5043  166.74  5124.1  169.77  5203.1   173.4
  5314.2  178.77  5319.3  178.45  5375.1  182.32  5428.3   184.4  5435.9  185.37
    5441  184.88  5447.4  185.13    5479  187.35  5489.1  187.17  5496.7  187.96
  5509.4  187.75  5557.5  190.03  5562.6   189.7  5570.2  190.79  5590.5  191.34
#Mann= 5 ,-1 , 0
  4782.2      .1       0  4922.2     .07       0  5124.1      .1       0
  5203.1     .05       0  5447.4      .1       0
Bank Sta=4922.2,5124.1
XS Rating Curve= 0 ,0
Exp/Cntr=0.3,0.1

Type RM Length L Ch R = 1 ,26025   ,488,488,488
BEGIN DESCRIPTION:
UNT011 IN PECR 46.0
END DESCRIPTION:
XS GIS Cut Line= 3
      2331337.73     13264746.83      2331287.72     13265046.85
      2331137.71     13265346.88
#Sta/Elev= 30
  4666.4  185.07    4669  185.07  4676.6  183.98  4686.7  181.17  4699.4  179.94
    4707  178.28  4717.1  177.47  4727.3  175.24  4737.4  174.24  4747.5  172.18
  4798.2  168.11    4821  167.09  4848.9  166.19  4973.4  164.95  4992.9  164.12
  5001.1  162.91  5006.9  163.58  5015.3  165.46  5029.3  166.94  5037.6  168.22
    5074  169.25  5090.8  170.31  5141.1  171.71  5202.6  174.63  5224.9  176.71
  5238.9  180.55  5247.3  181.85  5261.3  182.86  5269.6  184.22    5306  186.28
#Mann= 3 , 0 , 0
  4666.4      .1       0    4821     .07       0  5029.3      .1       0
Bank Sta=4821,5029.3
XS Rating Curve= 0 ,0
Exp/Cntr=0.3,0.1

Type RM Length L Ch R = 1 ,25537   ,549,549,549
BEGIN DESCRIPTION:
UNT011 IN PECR 45.0
END DESCRIPTION:
XS GIS Cut Line= 3
      2331237.73     13264746.85      2330887.72     13264896.85
      2330687.69     13265146.89
#Sta/Elev= 30
    4590  180.97  4604.5  179.21  4611.8   177.4  4622.6  176.78  4633.5  174.44
  4733.3   167.8  4779.6  165.91    4833   163.7  4880.1  163.61  4885.6  162.75
  4903.7  163.83  4909.1  162.41  4927.3  162.93  4938.2   161.8  4956.3  161.94
  4961.7  160.62    5013  158.44  5021.2  159.94  5027.6  159.82    5042  161.71
  5056.4  162.43  5062.8  162.72  5159.2  170.41  5198.9  173.34  5213.3  175.49
  5234.1  177.18  5240.5  178.99  5262.9  180.52  5269.3  182.06    5291  183.06
#Mann= 5 ,-1 , 0
    4590      .1       0  4779.6     .12       0  4927.3     .07       0
  5056.4      .1       0  5159.2     .05       0
Bank Sta=4927.3,5062.8
XS Rating Curve= 0 ,0
Exp/Cntr=0.3,0.1

Type RM Length L Ch R = 1 ,24988   ,43,43,43
BEGIN DESCRIPTION:
Mapping XS 5ff962ec
END DESCRIPTION:
XS GIS Cut Line= 4
       2330919.5     13264418.73      2330554.88      13264538.1
      2330476.75     13264546.79      2330368.26     13264716.03
#Sta/Elev= 30
  4563.2  178.08  4586.1  175.81  4617.7   171.3  4691.3  164.78  4754.5  161.44
  4789.2  161.38  4826.6   161.6  4831.9  162.15  4858.5  161.73  4870.2  162.34
  4901.8  161.66  4933.4  162.38  4946.9  162.05  4954.1  159.22  4964.1  158.21
  4974.2  155.96  4994.1  154.58  5022.5  155.66  5032.2  155.11  5038.2  157.14
  5047.4  156.99  5053.4  158.76  5068.6  158.59  5074.5  162.62  5086.4  163.77
  5089.7  164.55  5104.9  165.11  5110.9  166.88  5147.2  169.17  5226.5  171.56
#Mann= 5 ,-1 , 0
  4563.2      .1       0  4789.2     .12       0  4954.1     .07       0
  5068.6      .1       0  5086.4     .05       0
Bank Sta=4946.9,5074.5
XS Rating Curve= 0 ,0
Exp/Cntr=0.3,0.1

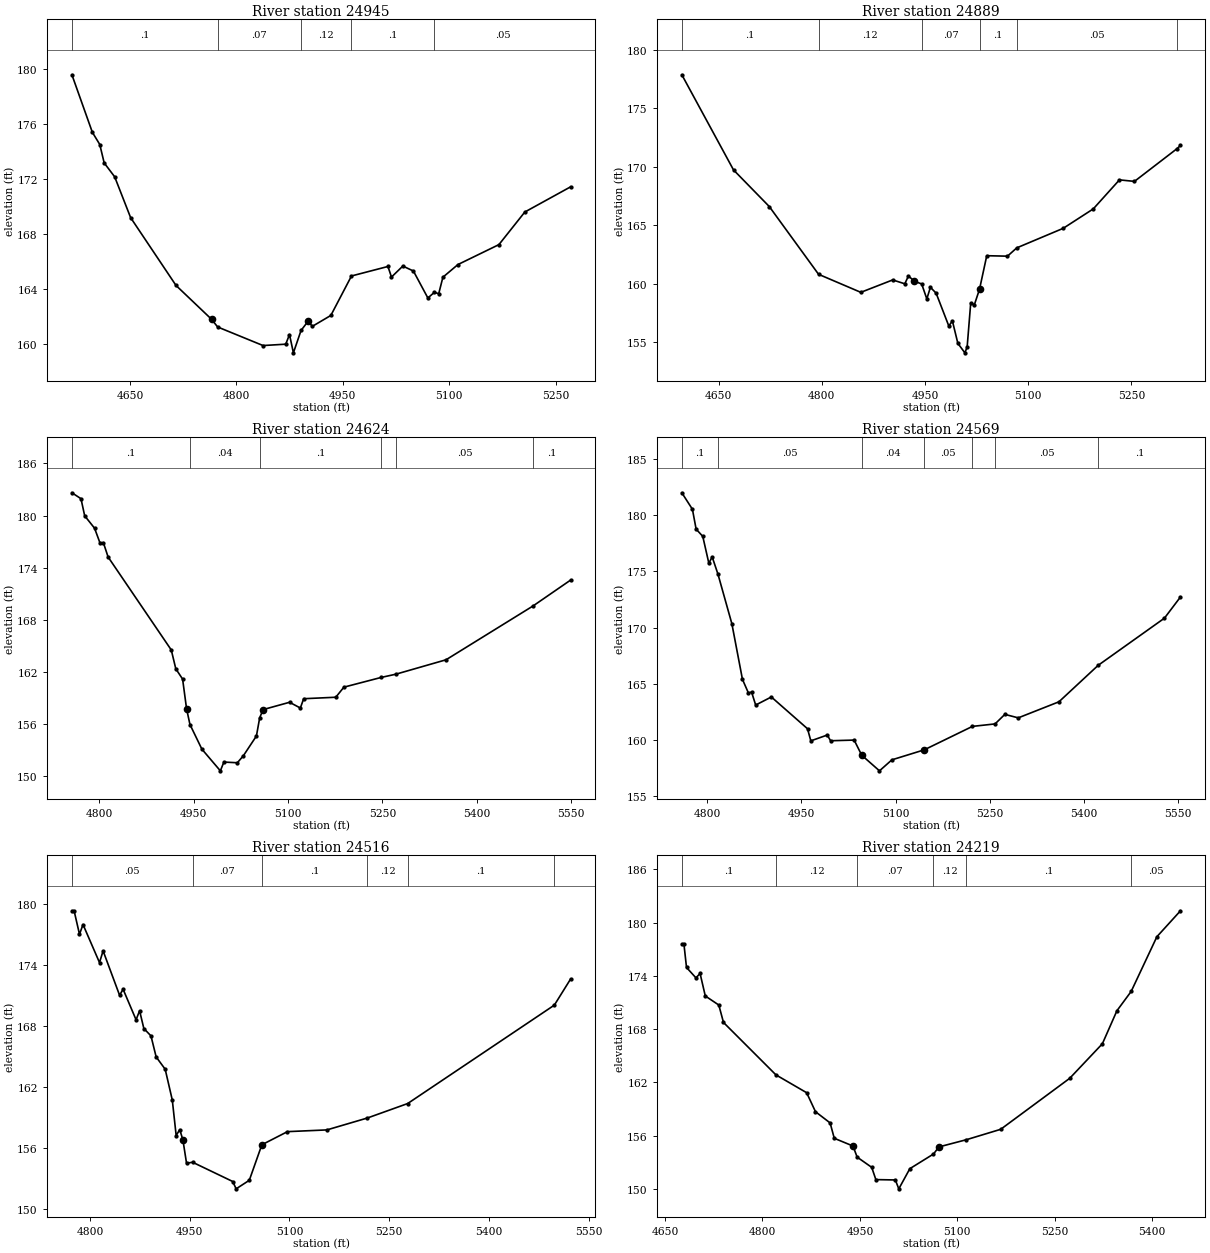
Type RM Length L Ch R = 1 ,24945   ,56,56,56
BEGIN DESCRIPTION:
UNT011 IN PECR 44.0
END DESCRIPTION:
XS GIS Cut Line= 4
      2330915.09     13264377.52      2330539.69     13264499.04
      2330455.05     13264503.38      2330336.45     13264693.14
#Sta/Elev= 30
    4568  179.61  4596.8  175.43  4607.3  174.54  4613.5   173.2  4628.3  172.19
  4650.8  169.22  4714.8  164.29  4764.9  161.83  4773.5  161.27  4837.5  159.92
  4869.5  160.02  4874.8  160.72  4880.3  159.39  4891.1  161.02  4901.5  161.72
  4906.8  161.31  4933.1  162.11  4962.2  164.98  5013.6  165.67  5018.6   164.9
  5034.6   165.7  5049.5  165.34  5069.9  163.38  5079.1  163.79  5085.2  163.69
  5091.1  164.89  5112.3  165.81  5170.1  167.26  5206.6  169.63  5271.1  171.46
#Mann= 5 ,-1 , 0
    4568      .1       0  4773.5     .07       0  4891.1     .12       0
  4962.2      .1       0  5079.1     .05       0
Bank Sta=4764.9,4901.5
XS Rating Curve= 0 ,0
Exp/Cntr=0.3,0.1

Type RM Length L Ch R = 1 ,24889   ,265,265,265
BEGIN DESCRIPTION:
Mapping XS 599bce0d
END DESCRIPTION:
XS GIS Cut Line= 3
      2330889.12     13264321.08      2330442.03     13264466.49
      2330320.49     13264690.04
#Sta/Elev= 30
  4596.6  177.87  4671.7  169.74  4723.7  166.61  4795.3  160.82  4856.7  159.28
    4903  160.34  4920.6  160.01  4925.9  160.68  4934.6  160.22  4945.1     160
  4952.6  158.72  4957.8  159.71  4966.1  159.21  4984.5  156.41  4989.8  156.83
  4997.7  154.92  5007.9  154.11  5011.2  154.61  5016.4  158.38  5021.7  158.22
  5029.2  159.55  5039.7  162.41  5069.8  162.37  5083.3  163.08  5150.8  164.75
  5194.5  166.41  5232.5  168.89  5254.3  168.76  5315.8  171.54  5321.2  171.83
#Mann= 6 ,-1 , 0
  4596.6      .1       0  4795.3     .12       0  4945.1     .07       0
  5029.2      .1       0  5083.3     .05       0  5315.8      .1       0
Bank Sta=4934.6,5029.2
XS Rating Curve= 0 ,0
Exp/Cntr=0.3,0.1

Type RM Length L Ch R = 1 ,24624   ,55,55,55
BEGIN DESCRIPTION:
Mapping XS 568c7f4e
END DESCRIPTION:
XS GIS Cut Line= 4
      2330620.42     13263963.44      2330524.06     13264205.64
      2330474.58     13264361.89      2330295.72     13264683.32
#Sta/Elev= 30
  4756.6  182.62    4771  181.94  4776.9  179.97  4792.6  178.54  4801.2  176.85
  4806.6  176.88  4814.1  175.23  4914.5  164.53  4921.7  162.36  4932.5  161.18
  4938.8  157.76  4944.2  155.95  4963.1  153.12  4992.5  150.62  4998.1  151.63
  5019.5  151.55    5029  152.35  5049.8  154.63    5055  156.73  5060.5  157.67
  5102.5  158.51  5119.6  157.85  5124.9  158.92  5175.9  159.09  5188.8  160.25
  5248.1  161.37  5271.3  161.74  5351.1   163.4  5489.5   169.6    5549  172.57
#Mann= 6 ,-1 , 0
  4756.6      .1       0  4944.2     .04       0    5055      .1       0
  5248.1      .1       0  5271.3     .05       0  5489.5      .1       0
Bank Sta=4938.8,5060.5
XS Rating Curve= 0 ,0
Exp/Cntr=0.3,0.1

Type RM Length L Ch R = 1 ,24569   ,53,53,53
BEGIN DESCRIPTION:
Mapping XS 04def733
END DESCRIPTION:
XS GIS Cut Line= 4
      2330557.91     13263945.25      2330479.79     13264176.99
      2330445.94     13264361.89      2330259.19     13264673.13
#Sta/Elev= 30
  4759.1  182.01    4776  180.54  4781.9  178.77  4792.5  178.13  4802.2  175.73
  4807.5   176.3  4816.8  174.75  4838.9  170.35  4855.8  165.39  4865.2  164.19
  4870.4  164.25  4876.9   163.1  4901.9  163.82  4959.6  160.99  4964.9  159.91
  4991.1  160.43  4996.4  159.92    5034  159.98  5046.1  158.63  5074.4  157.24
  5094.2  158.22  5145.8  159.11  5222.7   161.2  5258.8  161.42  5274.4  162.27
  5295.8  161.96  5360.7  163.39  5423.3  166.64    5529  170.84  5554.6  172.73
#Mann= 7 ,-1 , 0
  4759.1      .1       0  4816.8     .05       0  5046.1     .04       0
  5145.8     .05       0  5222.7      .1       0  5258.8     .05       0
  5423.3      .1       0
Bank Sta=5046.1,5145.8
XS Rating Curve= 0 ,0
Exp/Cntr=0.3,0.1

Type RM Length L Ch R = 1 ,24516   ,297,297,297
BEGIN DESCRIPTION:
UNT011 IN PECR 43.0
END DESCRIPTION:
XS GIS Cut Line= 3
      2330508.42     13263955.67      2330406.87     13264223.87
      2330188.35      13264632.3
#Sta/Elev= 30
  4772.8  179.32  4776.1  179.32  4784.2  177.01  4789.5  177.97  4814.3  174.23
  4819.7  175.38  4844.5  171.02  4849.8  171.61  4869.3  168.61  4874.6   169.5
    4881  167.75  4891.7  167.03  4899.5  164.96  4913.1  163.75  4923.8  160.72
  4929.6  157.24    4935  157.82 4939.77   156.8  4945.2  154.52  4954.4  154.61
  5014.7  152.72  5019.8     152  5039.6  152.84  5058.5  156.33    5097  157.62
  5156.3  157.79  5217.2  158.96  5277.8  160.38  5498.4  170.05  5522.8  172.61
#Mann= 6 ,-1 , 0
  4772.8     .05       0  4954.4     .07       0  5058.5      .1       0
  5217.2     .12       0  5277.8      .1       0  5498.4     .05       0
Bank Sta=4939.77,5058.5
XS Rating Curve= 0 ,0
Exp/Cntr=0.3,0.1

Type RM Length L Ch R = 1 ,24219   ,412,412,412
BEGIN DESCRIPTION:
UNT011 IN PECR 42.0
END DESCRIPTION:
XS GIS Cut Line= 3
      2330387.76     13263946.83      2330137.72     13264146.85
      2329937.73     13264546.84
#Sta/Elev= 30
    4676  177.59  4679.2  177.59  4683.2  174.94  4697.7  173.77  4704.1  174.26
  4712.1  171.73  4732.9  170.71  4740.1  168.75  4820.8  162.85  4868.1  160.84
  4881.7   158.7  4904.2  157.44  4910.6  155.71  4939.4  154.84  4945.8  153.59
  4968.2  152.44  4974.6  151.06  5004.6  151.02  5009.9  150.02  5026.9  152.29
  5063.3  153.94  5071.7  154.74  5113.9  155.55  5166.7  156.72  5272.9  162.46
  5323.2  166.35  5345.6  170.07  5367.5  172.24  5407.1   178.4  5443.4  181.32
#Mann= 6 ,-1 , 0
    4676      .1       0  4820.8     .12       0  4945.8     .07       0
  5063.3     .12       0  5113.9      .1       0  5367.5     .05       0
Bank Sta=4939.4,5071.7
XS Rating Curve= 0 ,0
Exp/Cntr=0.3,0.1

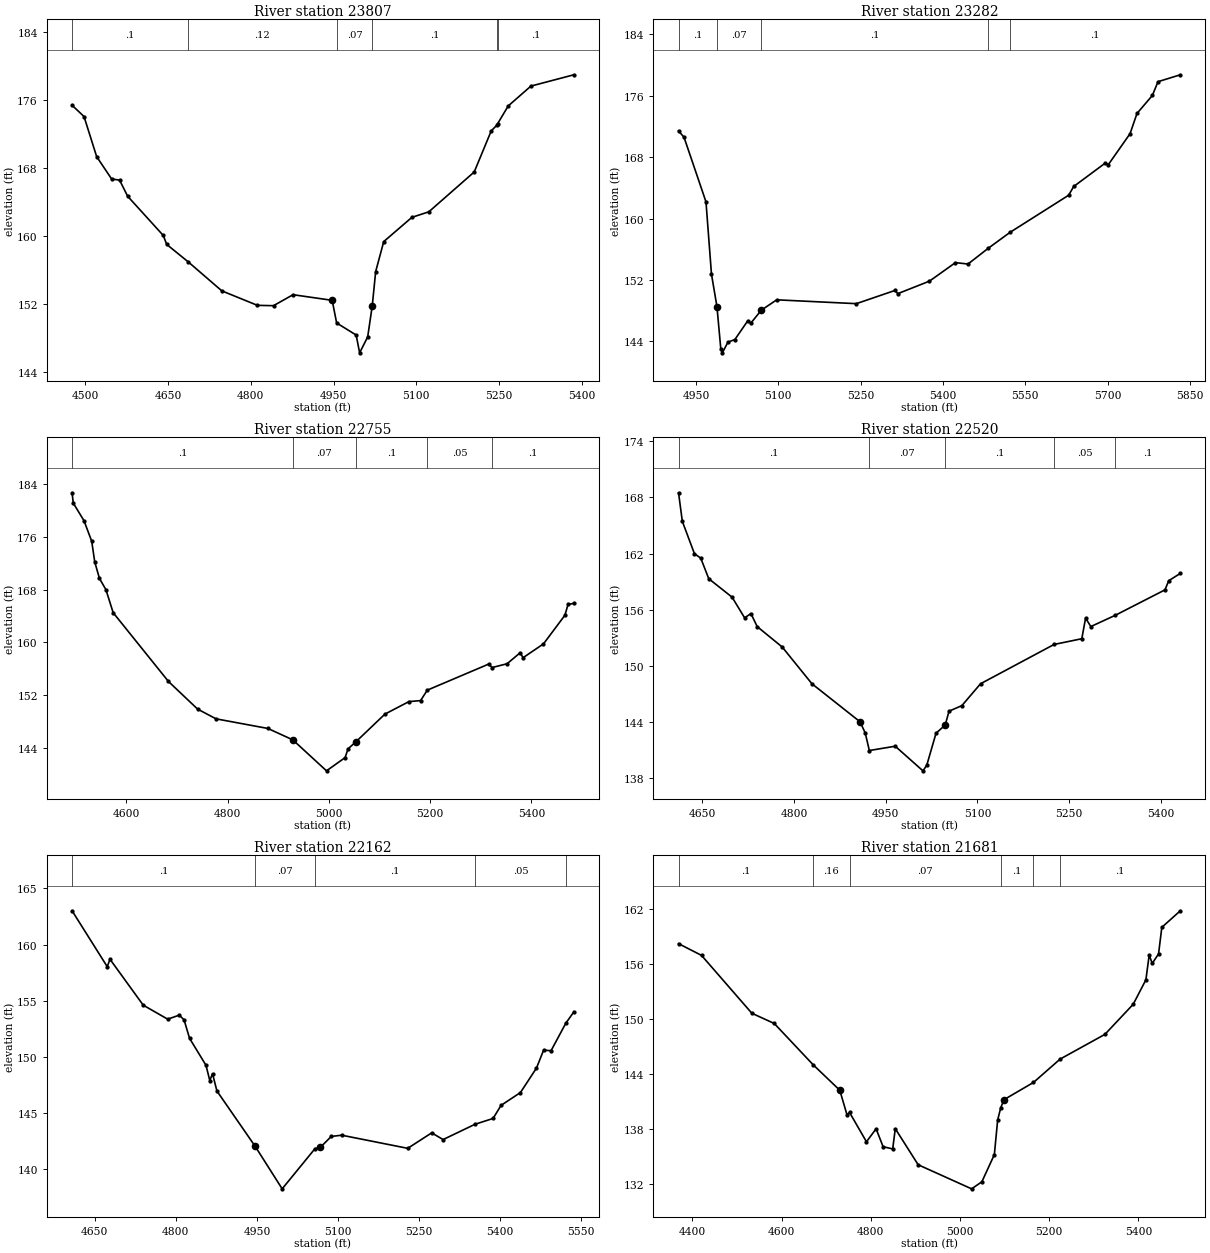
Type RM Length L Ch R = 1 ,23807   ,525,525,525
BEGIN DESCRIPTION:
UNT011 IN PECR 41.0
END DESCRIPTION:
XS GIS Cut Line= 3
      2330042.29     13263749.91      2329687.72     13264221.26
      2329612.89     13264532.57
#Sta/Elev= 30
  4475.8  175.35  4497.5  174.02  4520.4  169.31  4547.5  166.69    4562  166.55
  4576.6  164.66  4641.2  160.05  4647.4     159  4686.4  156.95  4747.4  153.54
  4811.9  151.84  4841.1   151.8  4876.5  153.09  4947.5  152.43  4955.6  149.77
    4991  148.35  4997.3  146.26  5011.9  148.13  5020.2  151.79  5026.4  155.81
    5041  159.33  5092.1  162.18  5122.8  162.83  5205.1  167.51  5235.9  172.33
  5246.4  173.03  5247.6  173.19  5266.8  175.27  5307.9   177.6  5385.8  178.93
#Mann= 6 ,-1 , 0
  4475.8      .1       0  4686.4     .12       0  4955.6     .07       0
  5020.2      .1       0  5246.4     .05       0  5247.6      .1       0
Bank Sta=4947.5,5020.2
XS Rating Curve= 0 ,0
Exp/Cntr=0.3,0.1

Type RM Length L Ch R = 1 ,23282   ,527,527,527
BEGIN DESCRIPTION:
UNT011 IN PECR 40.0
END DESCRIPTION:
XS GIS Cut Line= 3
      2329537.72     13263696.83      2329537.72     13263796.85
      2329387.71     13264596.89
#Sta/Elev= 30
  4918.3  171.41  4928.3  170.58  4968.3  162.17  4978.3  152.76  4988.3  148.52
  4995.3  143.02  4998.1  142.52  5008.3  143.91  5020.9  144.25  5044.6  146.71
  5049.7  146.36  5069.2  148.08  5097.2  149.42  5242.2  148.92  5312.5  150.64
  5317.6  150.22  5375.3  151.85  5422.7  154.26  5445.6  154.08  5482.8  156.15
  5522.3  158.21  5628.8  163.03  5638.1  164.17  5695.8  167.23  5700.8  166.98
  5740.7  171.04  5753.4  173.68  5781.4  176.02  5791.6  177.81  5832.3  178.71
#Mann= 5 ,-1 , 0
  4918.3      .1       0  4988.3     .07       0  5069.2      .1       0
  5482.8     .05       0  5522.3      .1       0
Bank Sta=4988.3,5069.2
XS Rating Curve= 0 ,0
Exp/Cntr=0.3,0.1

Type RM Length L Ch R = 1 ,22755   ,235,235,235
BEGIN DESCRIPTION:
UNT011 IN PECR 39.0
END DESCRIPTION:
XS GIS Cut Line= 3
      2329524.07     13263630.11       2328987.6     13263971.26
      2328650.92     13264085.22
#Sta/Elev= 30
  4492.6  182.74    4495  181.17  4516.2  178.49  4531.4  175.37  4537.4  172.23
  4546.7  169.72  4559.4  168.03  4573.8  164.52    4683  154.07  4740.6  149.87
    4777  148.39  4879.4  146.93  4928.6   145.2  4995.2  140.49  5031.9   142.5
  5037.8  143.84  5053.1  144.89  5110.6  149.11    5158  151.01    5181  151.16
  5194.3  152.75  5315.2   156.7  5322.3  156.19  5351.9  156.76    5378  158.45
  5383.3  157.67  5423.8  159.78  5466.1  164.13  5472.3  165.77  5483.8  165.94
#Mann= 5 ,-1 , 0
  4492.6      .1       0  4928.6     .07       0  5053.1      .1       0
  5194.3     .05       0  5322.3      .1       0
Bank Sta=4928.6,5053.1
XS Rating Curve= 0 ,0
Exp/Cntr=0.3,0.1

Type RM Length L Ch R = 1 ,22520   ,358,358,358
BEGIN DESCRIPTION:
UNT011 IN PECR 38.0
END DESCRIPTION:
XS GIS Cut Line= 4
       2329333.1     13263571.49      2329124.78     13263618.36
      2328775.82     13263842.32      2328621.13     13263955.76
#Sta/Elev= 30
  4611.5  168.49  4617.7  165.44  4637.5  161.98  4647.8  161.51  4660.9  159.31
    4699  157.34  4719.5  155.13  4729.8  155.59    4740   154.2    4781  152.01
  4829.5  148.09  4908.1  144.03  4916.6  142.83  4923.3  140.96  4965.6  141.42
  5010.9  138.79  5017.1  139.38  5032.3  142.81  5047.3  143.68  5053.5  145.16
  5074.6  145.76    5105  148.09  5225.2  152.29  5270.5   152.9  5276.7  155.11
  5285.2   154.2  5325.1   155.4  5406.4  158.12  5412.6   159.1  5431.5  159.88
#Mann= 5 ,-1 , 0
  4611.5      .1       0  4923.3     .07       0  5047.3      .1       0
  5225.2     .05       0  5325.1      .1       0
Bank Sta=4908.1,5047.3
XS Rating Curve= 0 ,0
Exp/Cntr=0.3,0.1

Type RM Length L Ch R = 1 ,22162   ,481,481,481
BEGIN DESCRIPTION:
Mapping XS 9185fbab
END DESCRIPTION:
XS GIS Cut Line= 4
      2329232.39     13263453.03      2328927.71     13263403.56
      2328745.41     13263424.39      2328496.06     13263782.84
#Sta/Elev= 30
  4607.9  163.01    4673  158.03  4678.1  158.69  4739.6   154.6  4784.9  153.35
  4806.3  153.71  4815.2  153.29  4825.4  151.64  4855.8  149.24  4862.8  147.88
  4867.9  148.49    4876  146.95  4946.8  142.02  4996.8  138.23  5057.5  141.81
  5067.5  141.93  5087.7   142.9    5107  143.01  5229.2  141.84  5273.6  143.22
  5294.6  142.62    5354  143.99  5387.1   144.5    5402  145.67  5437.8  146.81
  5467.5  148.99  5480.7  150.59  5494.5  150.54  5521.8  152.99  5536.7     154
#Mann= 5 ,-1 , 0
  4607.9      .1       0  4946.8     .07       0  5057.5      .1       0
    5354     .05       0  5521.8      .1       0
Bank Sta=4946.8,5067.5
XS Rating Curve= 0 ,0
Exp/Cntr=0.3,0.1

Type RM Length L Ch R = 1 ,21681   ,51,51,51
BEGIN DESCRIPTION:
Mapping XS 000eab33
END DESCRIPTION:
XS GIS Cut Line= 5
      2329091.77     13263364.49      2328711.56     13263156.16
      2328649.06      13263119.7      2328479.79     13263122.31
      2328149.04     13263427.01
#Sta/Elev= 30
  4369.1  158.23  4420.6  156.95  4533.4  150.63  4583.7  149.51  4670.5  145.02
  4730.6  142.22  4746.7  139.54  4752.4   139.8  4790.4  136.59    4812  138.01
  4827.7  136.05  4849.2  135.81    4855  138.02  4906.3  134.08  5026.1  131.45
  5049.1  132.22  5077.1  135.19  5084.5  138.96  5091.3  140.29  5098.7  141.19
  5164.8  143.07  5224.5  145.62  5324.9  148.32  5388.4  151.61  5416.8  154.28
  5424.2  156.99    5431  156.07  5445.2  157.11  5452.5  160.01    5494  161.82
#Mann= 6 ,-1 , 0
  4369.1      .1       0  4670.5     .16       0  4752.4     .07       0
  5091.3      .1       0  5164.8     .05       0  5224.5      .1       0
Bank Sta=4730.6,5098.7
XS Rating Curve= 0 ,0
Exp/Cntr=0.3,0.1

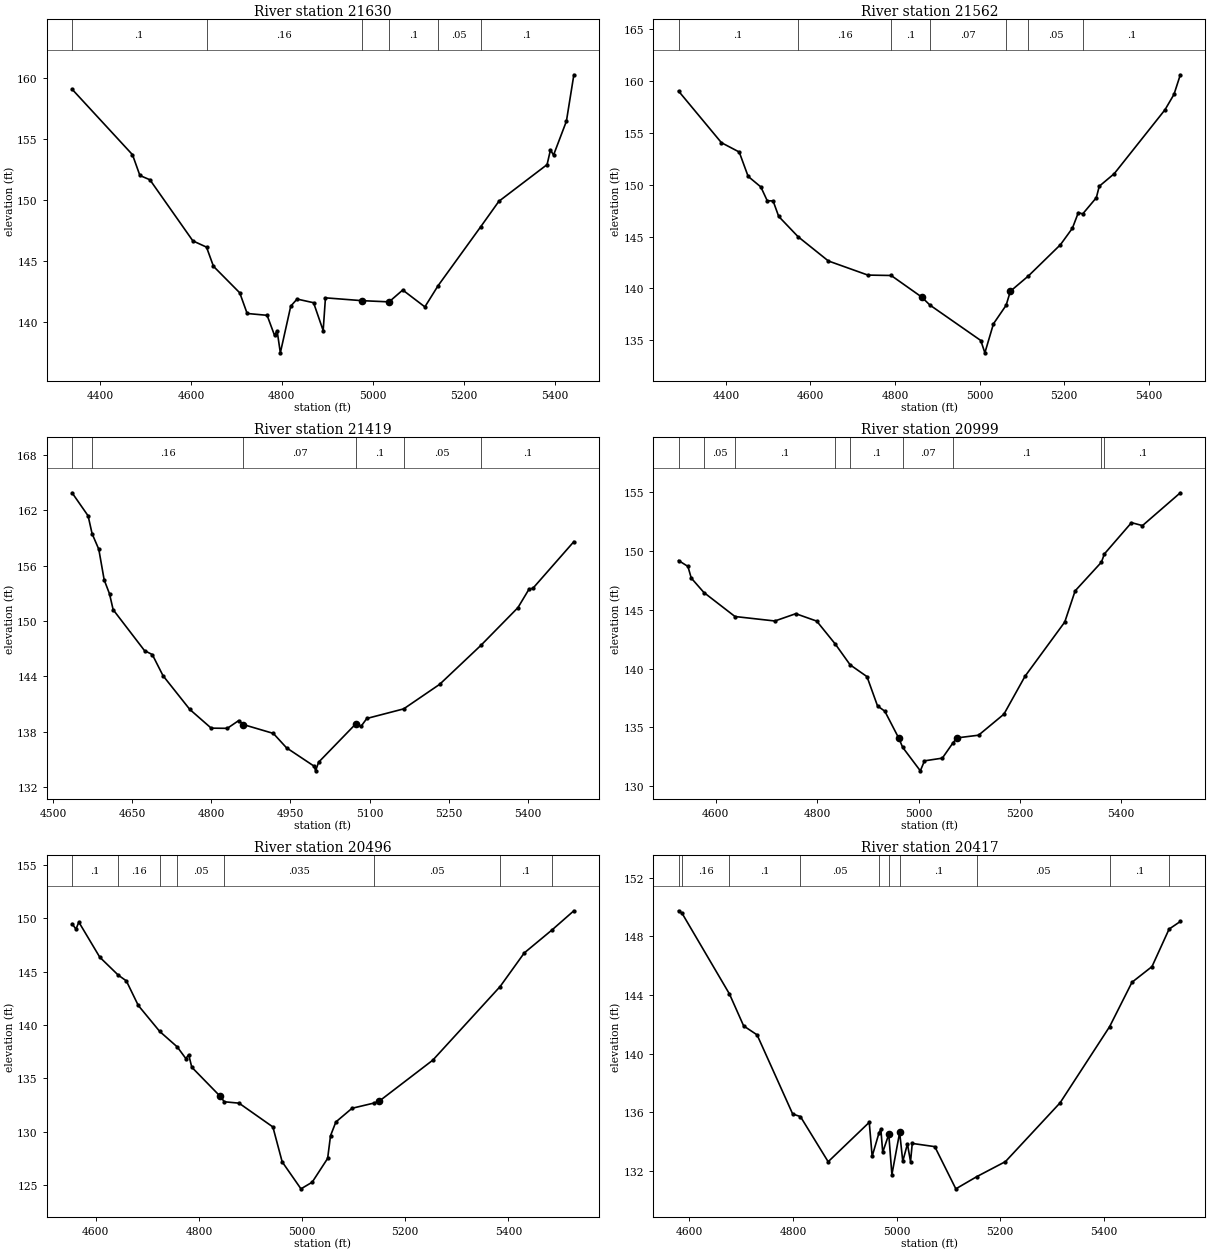
Type RM Length L Ch R = 1 ,21630   ,68,68,68
BEGIN DESCRIPTION:
Mapping XS 08fa951f
END DESCRIPTION:
XS GIS Cut Line= 4
      2329102.17     13263333.24      2328633.44     13263083.24
      2328432.91     13263070.22      2328160.02     13263322.33
#Sta/Elev= 30
  4338.6  159.08  4471.5  153.72  4487.8  152.02  4509.8  151.67  4604.3  146.67
  4634.3  146.16  4649.6  144.59  4707.4  142.42  4723.7  140.73  4767.6  140.58
  4783.9  138.94  4789.6  139.32  4796.7  137.51  4819.6  141.33  4833.5  141.91
  4869.8  141.61  4890.9  139.33  4895.9  142.01  4975.8  141.78  5035.9  141.68
  5065.9  142.65  5114.6  141.27  5143.6     143  5237.1  147.81  5277.4  149.91
  5383.4  152.91  5390.8  154.11  5397.6  153.69  5425.9  156.46  5442.3  160.26
#Mann= 6 ,-1 , 0
  4338.6      .1       0  4634.3     .16       0  4975.8     .07       0
  5035.9      .1       0  5143.6     .05       0  5237.1      .1       0
Bank Sta=4975.8,5035.9
XS Rating Curve= 0 ,0
Exp/Cntr=0.3,0.1

Type RM Length L Ch R = 1 ,21562   ,143,143,143
BEGIN DESCRIPTION:
UNT011 IN PECR 37.0
END DESCRIPTION:
XS GIS Cut Line= 4
      2329104.76     13263299.37      2328656.87     13263005.12
      2328344.37     13263015.54      2328104.79     13263255.12
#Sta/Elev= 30
  4287.8  159.03  4389.3  154.05  4431.4  153.15  4452.5   150.8  4482.6  149.78
  4497.7  148.45  4511.6  148.43  4524.8  146.94  4570.7  144.98  4642.4  142.64
  4735.8  141.28    4791  141.24  4862.9  139.17  4882.9  138.38    5003  134.97
  5012.7  133.78    5033  136.58    5063  138.37    5073  139.72  5115.8   141.2
  5191.5  144.21  5219.8   145.8  5233.9  147.31  5244.2  147.18  5276.4  148.74
  5283.4  149.85  5318.8  151.06    5439  157.23  5460.2  158.71  5475.2   160.6
#Mann= 7 ,-1 , 0
  4287.8      .1       0  4570.7     .16       0    4791      .1       0
  4882.9     .07       0    5063      .1       0  5115.8     .05       0
  5244.2      .1       0
Bank Sta=4862.9,5073
XS Rating Curve= 0 ,0
Exp/Cntr=0.3,0.1

Type RM Length L Ch R = 1 ,21419   ,420,420,420
BEGIN DESCRIPTION:
UNT011 IN PECR 36.0
END DESCRIPTION:
XS GIS Cut Line= 4
       2328927.7     13262768.14      2328599.58     13262825.43
       2328297.5     13262937.41      2328087.71     13263146.86
#Sta/Elev= 30
  4535.8   163.9  4566.2   161.4  4573.8  159.46  4586.5  157.77  4596.7  154.45
  4606.8  152.94  4613.7  151.22  4673.2  146.78    4688  146.35  4708.3  144.06
  4759.1   140.4  4799.7  138.37  4830.2  138.35  4851.8  139.19  4860.6  138.76
  4917.5   137.8  4942.5  136.24    4995  134.24  4997.7  133.74  5003.3  134.67
  5073.5  138.81  5083.8  138.56  5094.8  139.42  5164.7  140.46  5232.9  143.12
    5311  147.34  5381.4  151.44  5402.6  153.46  5409.7  153.53  5487.5   158.6
#Mann= 6 ,-1 , 0
  4535.8      .1       0  4573.8     .16       0  4860.6     .07       0
  5073.5      .1       0  5164.7     .05       0    5311      .1       0
Bank Sta=4860.6,5073.5
XS Rating Curve= 0 ,0
Exp/Cntr=0.3,0.1

Type RM Length L Ch R = 1 ,20999   ,503,503,503
BEGIN DESCRIPTION:
UNT011 IN PECR 35.0
END DESCRIPTION:
XS GIS Cut Line= 4
        2328642.     13262397.65        2328293.      13262486.2
      2328032.58     13262809.12      2328001.39     13263022.25
#Sta/Elev= 30
  4526.4  149.18  4544.9  148.68  4551.5  147.69  4576.5  146.46  4637.8  144.42
  4716.5  144.04  4757.8  144.66  4799.1  144.03  4835.9  142.07  4865.1  140.31
  4898.3  139.31  4919.1  136.82  4933.5  136.37 4961.14  134.07  4968.7   133.3
  5003.6   131.3  5011.8  132.15    5047  132.38  5067.9  133.67  5075.8   134.1
  5118.5  134.33  5168.6  136.12  5210.2  139.34  5288.6  143.95  5309.1   146.6
    5361  149.04  5366.8  149.74  5420.3   152.4    5442  152.15  5516.7  154.94
#Mann= 9 ,-1 , 0
  4526.4      .1       0  4576.5     .05       0  4637.8      .1       0
  4835.9     .05       0  4865.1      .1       0  4968.7     .07       0
  5067.9      .1       0    5361     .05       0  5366.8      .1       0
Bank Sta=4961.14,5075.8
XS Rating Curve= 0 ,0
Exp/Cntr=0.3,0.1

Type RM Length L Ch R = 1 ,20496   ,79,79,79
BEGIN DESCRIPTION:
Mapping XS 8b1ef6d1
END DESCRIPTION:
XS GIS Cut Line= 5
      2328016.23     13261895.77      2327854.79     13262249.91
      2327823.54     13262270.74       2327797.5     13262315.01
      2327656.87     13262788.97
#Sta/Elev= 30
  4554.2  149.49  4561.8  148.99  4567.3  149.65  4607.9  146.36  4643.7  144.68
  4659.4  144.14  4682.5  141.84  4724.1   139.4  4758.1  137.95  4774.7  136.86
  4780.2  137.22  4786.2  136.05  4841.1  133.33  4849.3  132.81  4877.8  132.68
  4943.4  130.45  4961.4  127.18  4997.8  124.65  5019.5  125.27  5049.5   127.5
  5055.1  129.63  5065.5  130.92  5096.8   132.2  5138.5  132.68    5149  132.85
  5253.3  136.71  5383.8  143.61  5430.6  146.76  5484.5  148.92  5526.7  150.71
#Mann= 8 ,-1 , 0
  4554.2      .1       0  4643.7     .16       0  4724.1      .1       0
  4758.1     .05       0  4849.3    .035       0  5138.5     .05       0
  5383.8      .1       0  5484.5     .05       0
Bank Sta=4841.1,5149
XS Rating Curve= 0 ,0
Exp/Cntr=0.3,0.1

Type RM Length L Ch R = 1 ,20417   ,63,63,63
BEGIN DESCRIPTION:
Mapping XS f1407562
END DESCRIPTION:
XS GIS Cut Line= 6
      2327932.92     13261893.13      2327828.75     13262203.04
      2327766.25     13262234.29      2327719.37     13262265.54
      2327714.16     13262328.04      2327586.73     13262762.35
#Sta/Elev= 30
  4579.1  149.75  4585.9  149.58  4677.4  144.07  4704.8  141.89  4730.7  141.28
  4799.4  135.88  4814.4   135.7  4867.9  132.62  4947.2  135.31  4952.8  132.99
  4966.2  134.61  4969.6  134.83  4973.2  133.27  4984.9  134.49  4990.9  131.74
  5005.9  134.62  5011.9  132.65  5020.9  133.83  5026.9  132.63  5030.2  133.87
  5073.7  133.65  5114.3  130.77  5155.1  131.61  5210.1  132.63  5315.5  136.64
  5411.1  141.84  5454.3  144.87  5492.9  145.94  5525.9   148.5  5547.6  149.02
#Mann= 10 ,-1 , 0
  4579.1      .1       0  4585.9     .16       0  4677.4      .1       0
  4814.4     .05       0  4966.2      .1       0  4984.9     .07       0
  5005.9      .1       0  5155.1     .05       0  5411.1      .1       0
  5525.9     .05       0
Bank Sta=4984.9,5005.9
XS Rating Curve= 0 ,0
Exp/Cntr=0.3,0.1