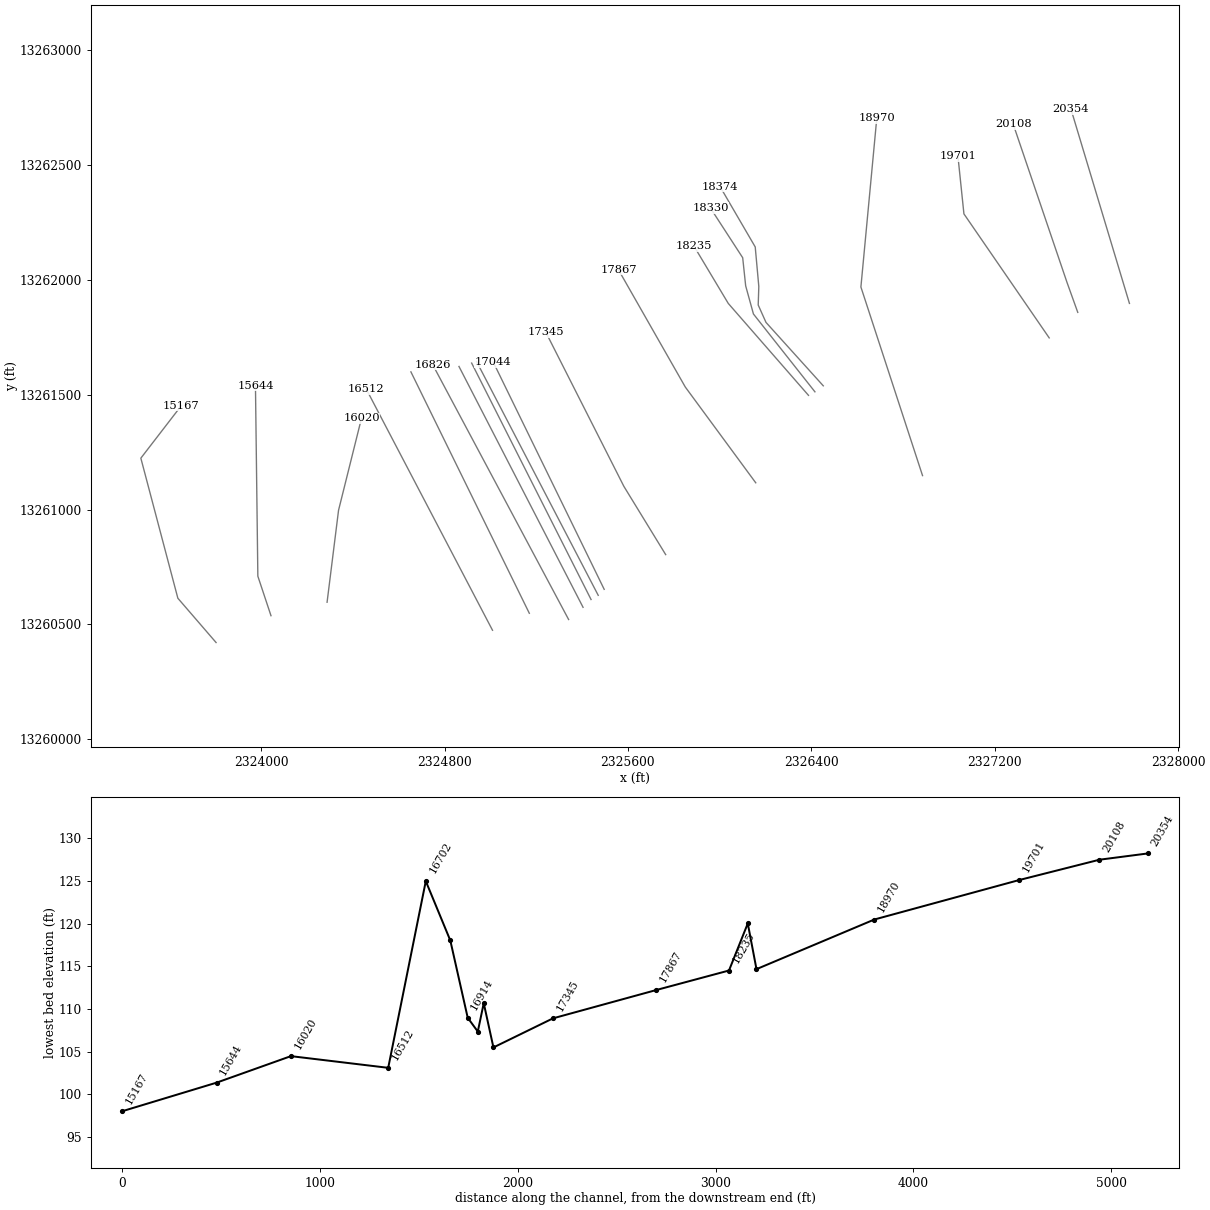
HEC-RAS study UNT011 IN PECR.prj: UNT011 IN PECR Base Level Engineering

--- UNT011 IN PECR.g01 (geometry) --- (continued)

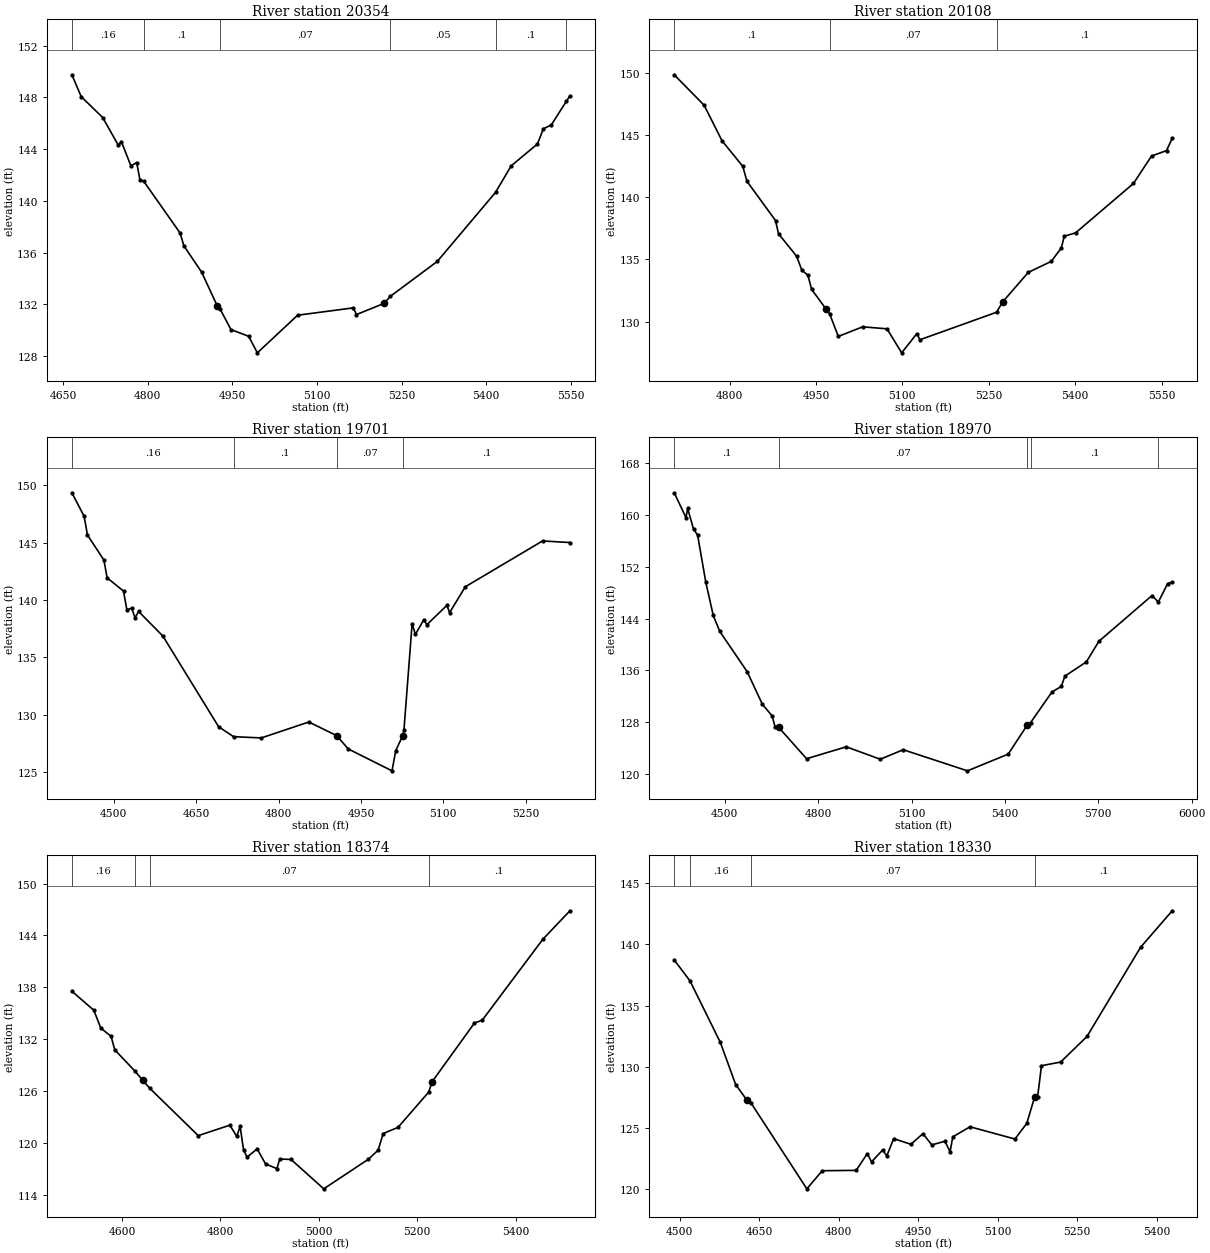
Type RM Length L Ch R = 1 ,20354   ,246,246,246
BEGIN DESCRIPTION:
UNT011 IN PECR 34.0
END DESCRIPTION:
XS GIS Cut Line= 2
      2327787.72     13261896.85      2327532.71     13262741.92
#Sta/Elev= 30
  4665.5  149.75    4682  148.06  4720.2  146.44  4747.9  144.29  4753.2  144.58
    4770  142.72  4780.4  142.95  4786.1  141.64    4793   141.5  4857.3  137.51
    4864  136.52  4895.5  134.48  4923.3  131.86  4928.5   131.6  4947.5  130.04
  4978.9  129.52  4994.2  128.24  5065.6  131.15  5164.5  131.72  5169.8   131.2
  5219.1  132.07  5229.6   132.6  5313.1  135.31  5416.5  140.66    5444   142.7
  5490.7   144.4  5501.1  145.57  5515.2  145.87  5542.1  147.71  5548.2  148.12
#Mann= 6 ,-1 , 0
  4665.5     .16       0    4793      .1       0  4928.5     .07       0
  5229.6     .05       0  5416.5      .1       0  5542.1     .05       0
Bank Sta=4923.3,5219.1
XS Rating Curve= 0 ,0
Exp/Cntr=0.3,0.1

Type RM Length L Ch R = 1 ,20108   ,407,407,407
BEGIN DESCRIPTION:
UNT011 IN PECR 33.0
END DESCRIPTION:
XS GIS Cut Line= 3
      2327562.29      13261857.9       2327515.4     13261988.15
      2327281.02     13262675.66
#Sta/Elev= 30
  4703.8  149.84  4755.8  147.39  4786.8  144.54  4822.8  142.49  4830.2  141.28
  4879.7  138.13    4885  137.06  4916.3  135.27  4925.4  134.14    4936  133.73
  4942.4   132.6  4967.6  131.01  4973.7  130.63  4988.8  128.82    5031  129.59
  5073.3  129.43  5098.8   127.5  5125.2  129.05  5130.4  128.55  5263.5  130.76
    5274  131.58  5318.5  133.96  5358.6  134.85  5375.9  135.92  5381.2  136.87
  5400.8  137.14  5501.3  141.11  5532.6  143.31  5558.7  143.75  5568.6  144.74
#Mann= 3 ,-1 , 0
  4703.8      .1       0  4973.7     .07       0  5263.5      .1       0
Bank Sta=4967.6,5274
XS Rating Curve= 0 ,0
Exp/Cntr=0.3,0.1

Type RM Length L Ch R = 1 ,19701   ,731,731,731
BEGIN DESCRIPTION:
UNT011 IN PECR 32.0
END DESCRIPTION:
XS GIS Cut Line= 3
      2327437.73     13261746.84      2327065.73     13262286.37
      2327039.69     13262536.37
#Sta/Elev= 30
  4423.7  149.36    4446  147.31  4452.1  145.67  4481.9   143.5  4487.9  141.94
  4517.7  140.79  4523.8  139.15  4532.6   139.3  4538.7  138.46  4545.2  139.01
  4589.4  136.86  4690.8  128.96    4718  128.09  4768.6  127.98  4855.1  129.37
  4905.8  128.18  4926.8  127.02  5006.5  125.11  5013.4  126.88 5026.14  128.19
  5028.2  128.64  5043.1  137.92  5049.2  137.01  5064.1  138.27  5070.1  137.86
  5106.4  139.54  5111.4  138.91  5139.9  141.16  5280.6  145.16  5330.4  145.02
#Mann= 4 ,-1 , 0
  4423.7     .16       0    4718      .1       0  4905.8     .07       0
 5026.14      .1       0
Bank Sta=4905.8,5026.14
XS Rating Curve= 0 ,0
Exp/Cntr=0.3,0.1

Type RM Length L Ch R = 1 ,18970   ,596,596,596
BEGIN DESCRIPTION:
UNT011 IN PECR 31.0
END DESCRIPTION:
XS GIS Cut Line= 3
      2326885.16     13261147.74      2326616.32     13261968.26
      2326685.51     13262701.47
#Sta/Elev= 30
  4337.7  163.41  4375.6  159.58  4380.9  161.01  4399.9  157.77  4412.7  156.92
  4439.3  149.58    4463   144.5  4484.1  142.01  4571.9  135.81  4620.9  130.77
  4652.5  128.95  4662.2  127.19  4673.5  127.19    4763  122.36  4890.4   124.2
  4999.7  122.28  5073.4  123.75  5279.8  120.49  5410.7  123.07  5470.9  127.49
  5482.8  127.95  5551.3  132.67  5581.4  133.52  5592.5   135.1  5661.8  137.31
  5701.9  140.48  5872.7  147.55  5892.9  146.54  5922.9  149.39  5937.6  149.61
#Mann= 5 ,-1 , 0
  4337.7      .1       0  4673.5     .07       0  5470.9     .16       0
  5482.8      .1       0  5892.9     .05       0
Bank Sta=4673.5,5470.9
XS Rating Curve= 0 ,0
Exp/Cntr=0.3,0.1

Type RM Length L Ch R = 1 ,18374   ,44,44,44
BEGIN DESCRIPTION:
UNT011 IN PECR 30.0
END DESCRIPTION:
XS GIS Cut Line= 6
       2326452.2     13261538.35      2326202.23     13261814.36
      2326168.37     13261889.88      2326170.98     13261970.61
      2326155.35     13262142.49      2326002.22     13262404.64
#Sta/Elev= 30
  4498.3  137.55  4542.9  135.34  4557.1  133.28    4578  132.32  4585.4  130.77
  4626.4   128.3  4642.2  127.25  4656.4  126.32  4755.1  120.83  4819.3  122.04
  4833.5  120.74  4840.2  121.92  4847.1  119.18  4854.4  118.34  4874.8   119.3
  4891.9  117.55  4915.1  117.01  4920.6  118.12  4943.7  118.07  5010.2  114.67
  5100.7  118.09  5120.6  119.14  5130.9  121.07    5161  121.78  5223.4  125.87
  5230.5  127.08  5316.5  133.87  5332.2  134.19  5455.4  143.56  5510.4  146.86
#Mann= 4 ,-1 , 0
  4498.3     .16       0  4626.4      .1       0  4656.4     .07       0
  5223.4      .1       0
Bank Sta=4642.2,5230.5
XS Rating Curve= 0 ,0
Exp/Cntr=0.3,0.1

Type RM Length L Ch R = 1 ,18330   ,95,95,95
BEGIN DESCRIPTION:
Mapping XS bc6231d3
END DESCRIPTION:
XS GIS Cut Line= 5
       2326415.8     13261512.24      2326147.54     13261850.82
      2326113.69     13261973.22      2326100.67     13262095.61
      2325960.05     13262311.75
#Sta/Elev= 30
  4489.4  138.73  4519.1  137.03  4576.5  131.99  4605.4  128.55  4626.2   127.3
  4634.3  127.05  4739.7  120.03  4768.8  121.51  4832.9  121.54  4853.8  122.91
  4861.8  122.23  4882.6   123.2  4890.7  122.73  4903.6  124.13  4936.1  123.67
  4958.8  124.54  4975.6  123.62  5000.3  123.92    5010  123.06  5015.2  124.28
  5047.7   125.1  5132.5   124.1  5154.8  125.38  5169.6  127.53  5175.2  127.53
  5182.5  130.09  5218.7  130.39  5268.4  132.48  5369.6  139.77  5429.3  142.75
#Mann= 4 ,-1 , 0
  4489.4      .1       0  4519.1     .16       0  4634.3     .07       0
  5169.6      .1       0
Bank Sta=4626.2,5169.6
XS Rating Curve= 0 ,0
Exp/Cntr=0.3,0.1

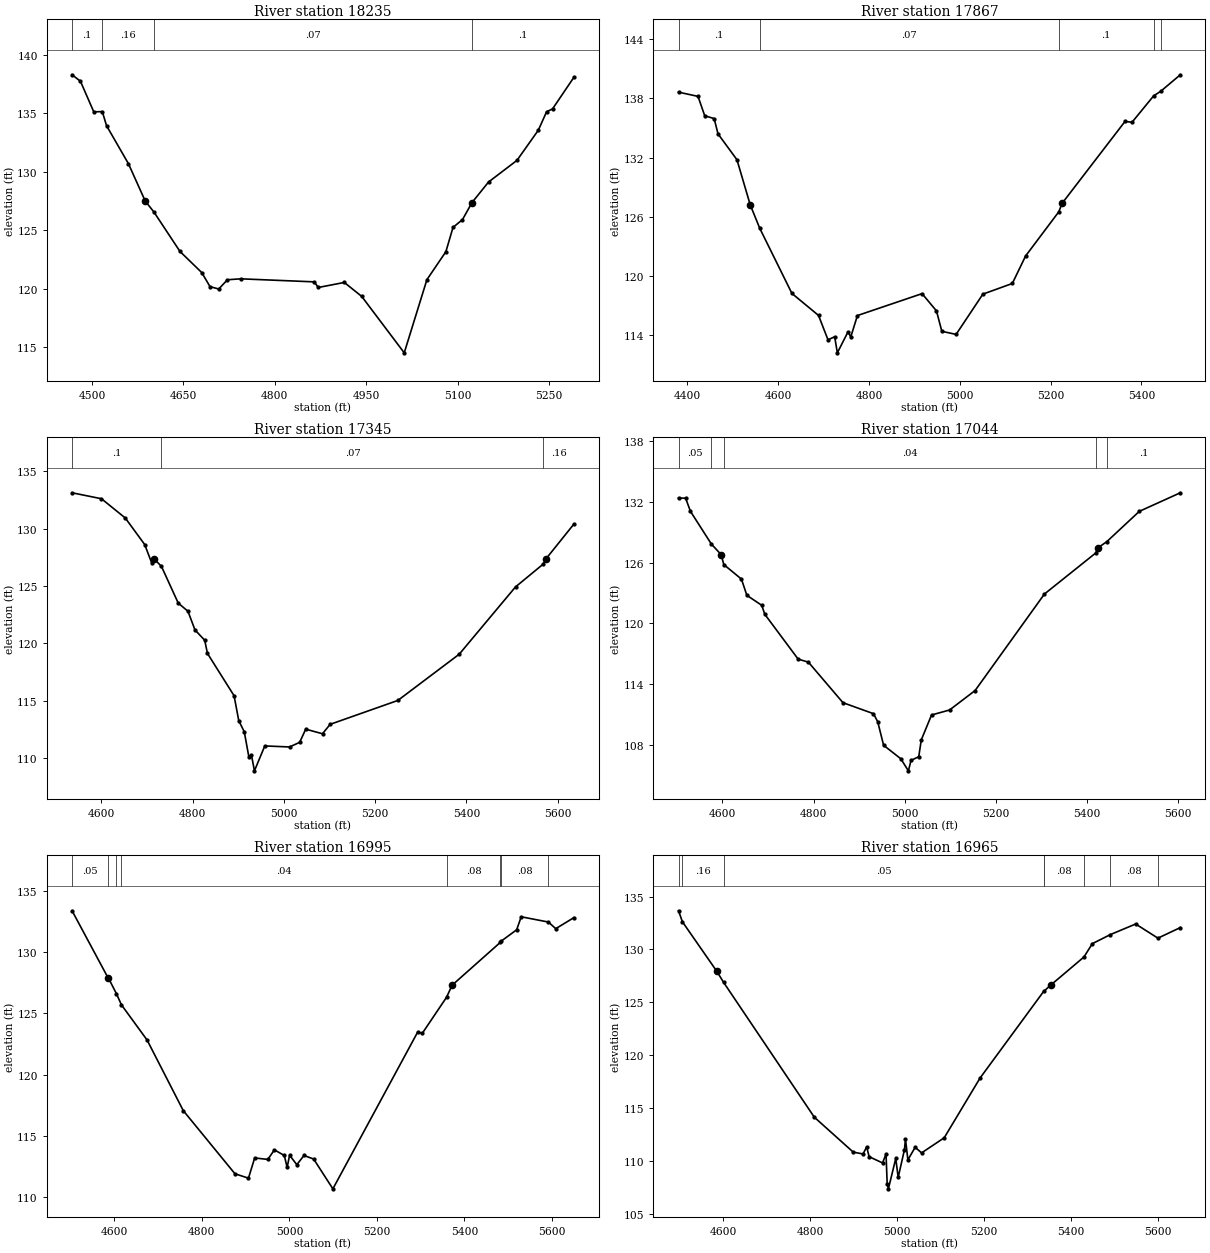
Type RM Length L Ch R = 1 ,18235   ,368,368,368
BEGIN DESCRIPTION:
UNT011 IN PECR 29.0
END DESCRIPTION:
XS GIS Cut Line= 3
      2326387.71     13261496.87      2326037.72     13261896.85
      2325887.74     13262146.82
#Sta/Elev= 30
  4467.4  138.29  4481.1  137.74    4503  135.12    4517  135.14  4523.9  133.94
  4559.9  130.68  4587.4  127.49  4601.7  126.55  4644.4  123.18    4680  121.38
  4693.7  120.17    4708  119.97  4722.2  120.76    4744  120.84  4864.6  120.58
  4871.2   120.1  4913.9  120.53  4942.4  119.34  5012.2  114.51  5049.4  120.77
  5080.5  123.16  5092.2  125.24  5107.7   125.9  5123.3  127.36  5150.5  129.12
  5197.1  130.97  5232.1  133.55  5245.7  135.13  5255.4  135.37  5290.4  138.07
#Mann= 4 ,-1 , 0
  4467.4      .1       0    4517     .16       0  4601.7     .07       0
  5123.3      .1       0
Bank Sta=4587.4,5123.3
XS Rating Curve= 0 ,0
Exp/Cntr=0.3,0.1

Type RM Length L Ch R = 1 ,17867   ,522,522,522
BEGIN DESCRIPTION:
UNT011 IN PECR 28.0
END DESCRIPTION:
XS GIS Cut Line= 3
      2326157.57     13261116.43      2325850.29     13261533.08
      2325559.11     13262042.64
#Sta/Elev= 30
    4381  138.64  4423.9  138.21  4438.6  136.25  4459.4  135.96  4467.9  134.41
  4509.6  131.79  4538.8  127.22  4559.7  124.85  4630.6  118.24  4689.2  116.01
    4710  113.54  4724.7  113.85  4730.6  112.22    4754  114.34  4760.2  113.84
  4774.8     116  4917.1  118.22  4948.8  116.47  4960.6   114.4    4992  114.09
    5051  118.17  5115.8  119.25  5144.9  122.03    5218  126.51  5225.5  127.38
  5363.8  135.67  5379.3  135.59  5426.8  138.26  5442.5  138.73  5485.6   140.4
#Mann= 5 ,-1 , 0
    4381      .1       0  4559.7     .07       0    5218      .1       0
  5426.8     .16       0  5442.5      .1       0
Bank Sta=4538.8,5225.5
XS Rating Curve= 0 ,0
Exp/Cntr=0.3,0.1

Type RM Length L Ch R = 1 ,17345   ,301,301,301
BEGIN DESCRIPTION:
Mapping XS ada930ab
END DESCRIPTION:
XS GIS Cut Line= 3
      2325764.71     13260803.98      2325582.44     13261100.82
      2325242.22     13261770.86
#Sta/Elev= 30
  4535.6  133.12  4600.1   132.6  4652.3  130.92  4694.8  128.61  4710.3  126.99
  4716.1  127.34  4731.6   126.7  4768.3  123.51  4789.6   122.8    4805  121.17
  4826.3  120.28  4832.3  119.13  4890.7  115.44  4900.9  113.28  4913.1  112.29
  4923.1  110.11  4928.7  110.29  4935.3   108.9    4958  111.07  5012.2  110.98
  5034.4  111.38  5047.7  112.53  5084.5  112.13  5101.2  112.95  5249.6  115.03
  5384.2  119.06  5507.5  124.92  5568.6  126.92  5574.8  127.39  5635.4  130.39
#Mann= 3 ,-1 , 0
  4535.6      .1       0  4731.6     .07       0  5568.6     .16       0
Bank Sta=4716.1,5574.8
XS Rating Curve= 0 ,0
Exp/Cntr=0.3,0.1

Type RM Length L Ch R = 1 ,17044   ,49,49,49
BEGIN DESCRIPTION:
UNT011 IN PECR 27.0
END DESCRIPTION:
XS GIS Cut Line= 2
       2325496.5      13260652.9       2325012.6     13261641.52
#Sta/Elev= 30
  4503.7  132.35  4519.2  132.34  4529.9  131.04  4575.9  127.81  4597.2  126.78
    4603   125.8  4641.7  124.37  4653.6  122.77  4686.2  121.79    4693   120.9
  4766.1  116.49  4788.6  116.19  4864.4   112.2  4931.2  111.12  4940.6  110.33
  4953.5  108.01  4991.2  106.68  5007.9  105.49  5013.7  106.52  5030.6  106.88
  5036.2  108.54  5058.7  110.99  5098.2  111.48  5154.3   113.4  5306.3   122.9
  5418.8  126.94  5424.4  127.47  5443.2  128.06  5514.4  131.04  5604.4  132.87
#Mann= 5 ,-1 , 0
  4503.7     .05       0  4575.9     .16       0    4603     .04       0
  5418.8     .08       0  5443.2      .1       0
Bank Sta=4597.2,5424.4
XS Rating Curve= 0 ,0
Exp/Cntr=0.3,0.1

Type RM Length L Ch R = 1 ,16995   ,30,30,30
BEGIN DESCRIPTION:
Mapping XS dbc562f6
END DESCRIPTION:
XS GIS Cut Line= 2
      2325470.45     13260626.87      2324940.03     13261643.52
#Sta/Elev= 30
  4503.4  133.36  4584.9  127.94  4586.5  127.87  4604.6  126.61  4616.2  125.69
  4674.8  122.82  4757.5  117.06  4875.6  111.91  4906.5  111.55  4920.7   113.2
  4950.7  113.08  4965.8  113.86  4988.4   113.4  4994.9  112.43  5000.5  113.42
    5017  112.65  5033.4   113.4  5055.5  113.11  5099.4  110.68  5292.8  123.44
  5304.2  123.39  5359.1   126.3  5371.9  127.29  5482.3  130.79  5484.3  130.89
  5519.4  131.81  5529.8  132.87    5592  132.44  5608.7   131.9  5650.1   132.8
#Mann= 8 ,-1 , 0
  4503.4     .05       0  4584.9     .16       0  4604.6     .05       0
  4616.2     .04       0  5359.1     .08       0  5482.3      .1       0
  5484.3     .08       0    5592     .05       0
Bank Sta=4586.5,5371.9
XS Rating Curve= 0 ,0
Exp/Cntr=0.3,0.1

Type RM Length L Ch R = 1 ,16965   ,51,51,51
BEGIN DESCRIPTION:
Mapping XS e14ea340
END DESCRIPTION:
XS GIS Cut Line= 2
      2325439.21     13260608.62      2324918.38     13261637.28
#Sta/Elev= 30
  4497.7  133.65  4506.6  132.61  4585.4  127.94  4601.4  126.87  4809.6  114.13
  4899.2  110.82  4921.7  110.65    4930  111.32  4935.6  110.39  4966.5   109.8
  4974.5  110.65  4977.1  107.85  4979.9  107.35  4996.8  110.22  5002.4  108.43
  5016.9  111.07  5019.1  112.08  5024.7  110.09  5041.4  111.28  5056.2  110.75
  5108.2  112.18  5190.7  117.84  5336.6  126.02  5353.2  126.63  5429.3  129.28
  5448.5  130.54  5490.1   131.4  5548.1   132.4  5599.2  131.06  5650.7  132.06
#Mann= 8 ,-1 , 0
  4497.7     .05       0  4506.6     .16       0  4601.4     .05       0
  5336.6     .07       0  5336.6     .08       0  5429.3      .1       0
  5490.1     .08       0  5599.2     .05       0
Bank Sta=4585.4,5353.2
XS Rating Curve= 0 ,0
Exp/Cntr=0.3,0.1

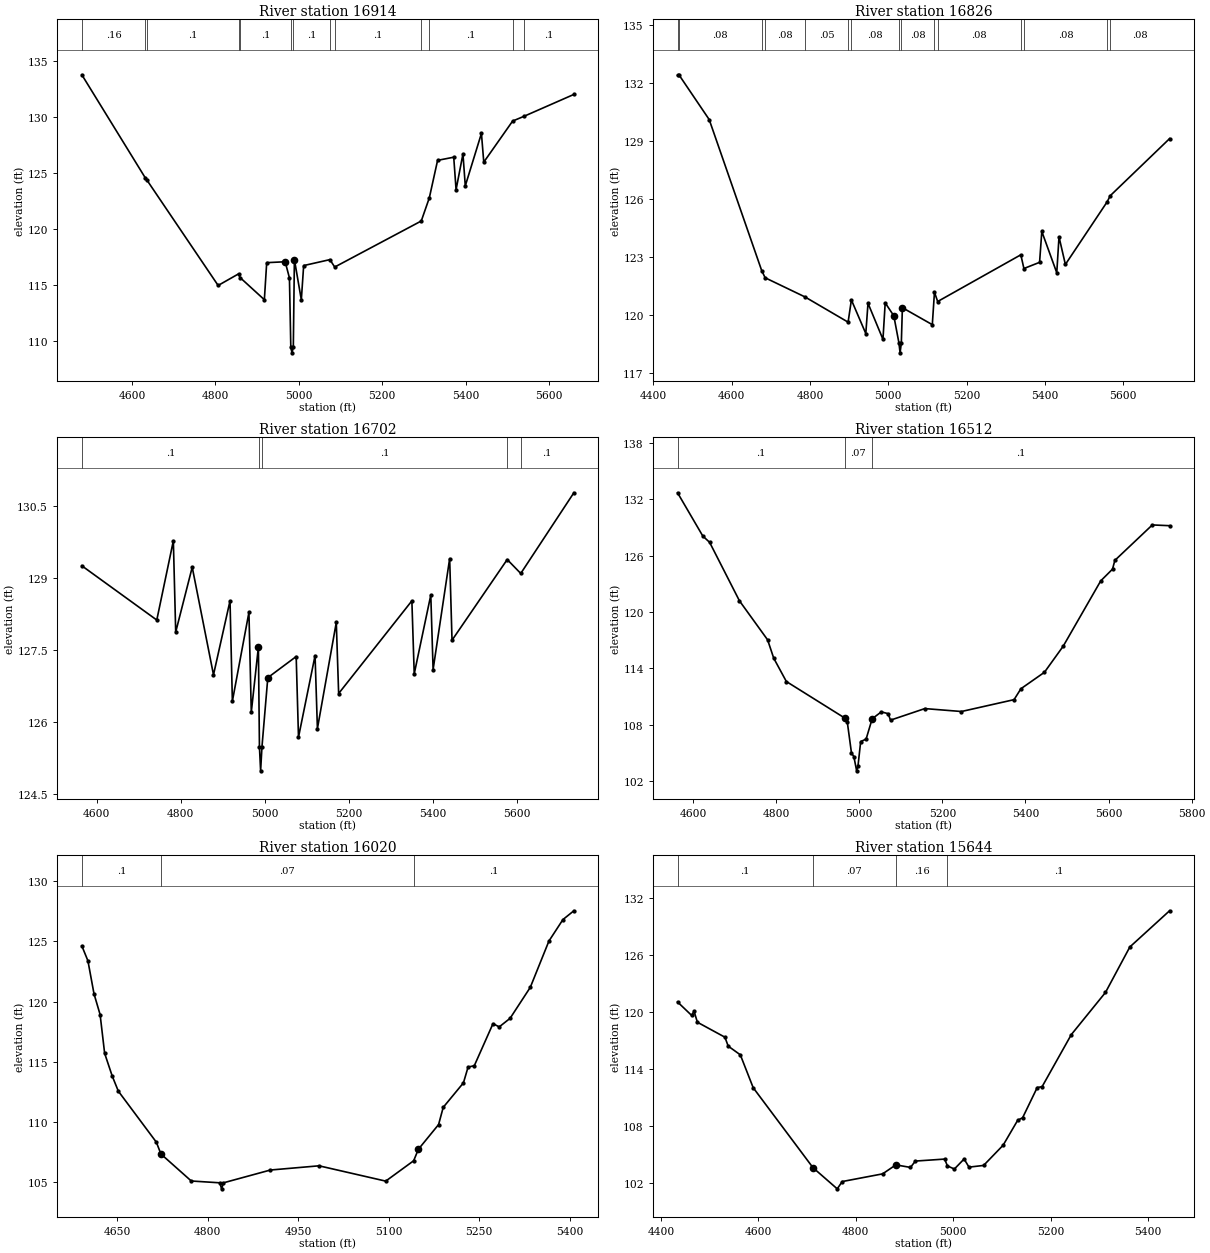
Type RM Length L Ch R = 1 ,16914   ,88,88,88
BEGIN DESCRIPTION:
UNT011 IN PECR 26.0
END DESCRIPTION:
XS GIS Cut Line= 2
      2325404.29     13260574.74      2324863.08     13261622.52
#Sta/Elev= 30
    4480  133.73  4632.6  124.52  4636.6  124.32  4806.7  114.97  4855.6     116
  4859.4  115.67  4917.5   113.7  4923.1     117  4967.4  117.08  4977.6  115.64
  4980.9  109.47  4983.7  108.97  4986.9  109.47  4989.5  117.28  5006.1  113.69
  5011.7  116.74  5074.6  117.27  5086.1  116.61  5293.6  120.71  5312.9  122.77
  5332.7  126.11  5371.4  126.39    5377   123.5  5393.5  126.68  5399.1  123.84
  5437.8  128.51  5443.4  125.95  5512.6  129.61  5539.7  130.03  5659.3  131.98
#Mann= 13 ,-1 , 0
    4480     .16       0  4632.6     .08       0  4636.6      .1       0
  4855.6     .05       0  4859.4      .1       0  4980.9     .07       0
  4986.9      .1       0  5074.6     .05       0  5086.1      .1       0
  5293.6     .08       0  5312.9      .1       0  5512.6     .08       0
  5539.7      .1       0
Bank Sta=4967.4,4989.5
XS Rating Curve= 0 ,0
Exp/Cntr=0.3,0.1

Type RM Length L Ch R = 1 ,16826   ,124,124,124
BEGIN DESCRIPTION:
Mapping XS dbdeaa2a
END DESCRIPTION:
XS GIS Cut Line= 2
      2325341.33     13260521.63      2324748.89     13261629.47
#Sta/Elev= 30
  4461.9  132.41  4465.4  132.44  4542.7  130.12  4676.8  122.29  4685.6  121.92
  4787.1  120.93  4897.4  119.62  4905.8  120.77  4942.6  119.03  4948.2   120.6
  4986.4  118.73  4992.1  120.62  5014.1  119.95  5027.3  118.53  5030.1  118.03
  5033.3  118.53    5036  120.37  5112.4  119.49  5117.9  121.17  5126.1  120.69
  5338.4  123.11  5346.3   122.4  5386.3  122.72    5392  124.32  5430.2  122.18
  5435.9  124.04  5452.2  122.61    5559  125.86  5566.6  126.17  5718.2  129.13
#Mann= 15 ,-1 , 0
  4461.9     .16       0  4465.4     .08       0  4676.8      .1       0
  4685.6     .08       0  4787.1     .05       0  4897.4      .1       0
  4905.8     .08       0  5027.3     .07       0  5033.3     .08       0
  5117.9      .1       0  5126.1     .08       0  5338.4      .1       0
  5346.3     .08       0    5559      .1       0  5566.6     .08       0
Bank Sta=5014.1,5036
XS Rating Curve= 0 ,0
Exp/Cntr=0.3,0.1

Type RM Length L Ch R = 1 ,16702   ,190,190,190
BEGIN DESCRIPTION:
Mapping XS 9117c9e5
END DESCRIPTION:
XS GIS Cut Line= 2
      2325169.88     13260548.76      2324653.42     13261599.04
#Sta/Elev= 30
    4565  129.26  4743.3  128.13  4782.7  129.78  4788.3  127.88  4827.6  129.23
  4878.2  126.99  4917.5  128.53  4923.1  126.44  4962.5  128.29  4968.1  126.21
    4985  127.57  4987.5  125.49  4990.3  124.99  4993.5  125.49  5007.4  126.93
  5074.9  127.37  5080.4  125.69  5119.8  127.39  5125.4  125.87  5170.3  128.08
  5175.9   126.6  5350.1  128.53  5355.7  127.01  5395.1  128.65  5400.6   127.1
    5440  129.41  5445.6  127.71  5576.9  129.39  5609.1   129.1  5735.4  130.78
#Mann= 5 ,-1 , 0
    4565      .1       0  4987.5     .07       0  4993.5      .1       0
  5576.9     .08       0  5609.1      .1       0
Bank Sta=4985,5007.4
XS Rating Curve= 0 ,0
Exp/Cntr=0.3,0.1

Type RM Length L Ch R = 1 ,16512   ,492,492,492
BEGIN DESCRIPTION:
UNT011 IN PECR 25.0
END DESCRIPTION:
XS GIS Cut Line= 2
      2325009.32     13260474.92      2324458.99     13261523.59
#Sta/Elev= 30
  4562.5  132.67  4623.3  128.07  4639.7   127.4  4711.5  121.18  4779.3  117.03
    4794  115.08  4824.4   112.6  4964.8  108.72  4971.2  108.26  4981.2  104.98
  4986.9  104.62  4993.6   103.1  4996.8   103.6  5003.3  106.21  5016.4  106.48
    5031  108.64    5053  109.37  5069.4  109.18  5075.1  108.49  5157.7  109.72
  5245.9  109.41  5372.5  110.67    5389  111.83  5445.6  113.58  5490.7  116.35
  5581.1   123.3  5609.5  124.55  5615.1  125.48  5705.3  129.25  5746.8  129.17
#Mann= 3 , 0 , 0
  4562.5      .1       0  4964.8     .07       0    5031      .1       0
Bank Sta=4964.8,5031
XS Rating Curve= 0 ,0
Exp/Cntr=0.3,0.1

Type RM Length L Ch R = 1 ,16020   ,376,376,376
BEGIN DESCRIPTION:
UNT011 IN PECR 24.0
END DESCRIPTION:
XS GIS Cut Line= 3
      2324287.71     13260596.81      2324337.72     13260996.85
      2324437.73     13261396.89
#Sta/Elev= 30
  4591.6  124.62  4601.7  123.38  4611.8  120.64  4621.9  118.92  4629.4  115.71
    4642  113.82  4652.1  112.57  4715.1  108.34  4722.7  107.36    4773  105.12
  4820.4  104.97  4823.2  104.47  4826.4  104.97  4904.1  106.03  4984.7  106.38
  5095.3  105.11  5141.6   106.8  5149.4  107.75  5182.9   109.8  5190.6  111.23
  5224.1  113.26  5231.8  114.57  5242.1  114.68  5273.1  118.17  5283.4   117.9
  5301.4  118.61  5334.9  121.18  5365.8  125.02    5389   126.8  5407.1  127.53
#Mann= 3 ,-1 , 0
  4591.6      .1       0  4722.7     .07       0  5141.6      .1       0
Bank Sta=4722.7,5149.4
XS Rating Curve= 0 ,0
Exp/Cntr=0.3,0.1

Type RM Length L Ch R = 1 ,15644   ,477,477,477
BEGIN DESCRIPTION:
UNT011 IN PECR 23.0
END DESCRIPTION:
XS GIS Cut Line= 3
        2324043.     13260538.28      2323985.71     13260710.16
      2323975.29     13261538.32
#Sta/Elev= 30
  4434.3  121.08    4463  119.67  4468.2  120.09    4475  118.94  4531.5  117.36
  4538.2  116.42  4563.1   115.5  4589.5  112.03  4712.2  103.59  4761.9  101.36
  4772.2  102.13    4855  102.94  4882.2  103.89  4912.2  103.62  4922.2  104.29
  4982.2   104.5    4988  103.78  5002.2  103.45  5022.2  104.51  5032.2  103.65
  5062.2  103.83  5102.2  105.96  5132.2   108.6  5142.2  108.86  5172.2  112.05
  5182.2  112.14  5242.2  117.64  5312.2  122.08  5362.2  126.88  5443.7   130.7
#Mann= 4 ,-1 , 0
  4434.3      .1       0  4712.2     .07       0  4882.2     .16       0
    4988      .1       0
Bank Sta=4712.2,4882.2
XS Rating Curve= 0 ,0
Exp/Cntr=0.3,0.1

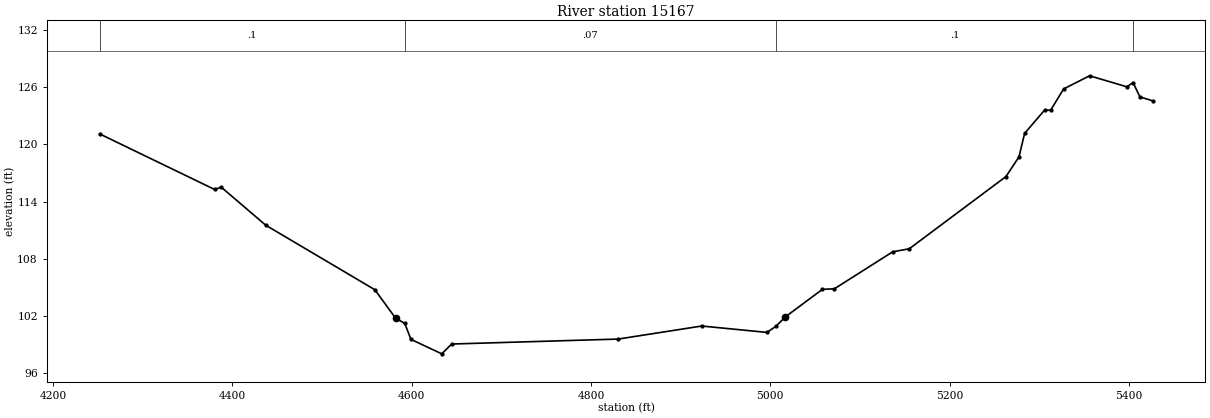
Type RM Length L Ch R = 1 ,15167   ,541,541,541
BEGIN DESCRIPTION:
UNT011 IN PECR 22.0
END DESCRIPTION:
XS GIS Cut Line= 4
      2323803.48     13260421.46      2323636.79     13260614.19
      2323475.33     13261223.57      2323652.09     13261452.32
#Sta/Elev= 30
  4252.2   121.1  4380.3  115.27  4387.9   115.5  4437.3  111.52  4559.1  104.74
  4582.2  101.75  4592.5   101.2  4599.3   99.53  4633.7   98.01  4644.7   99.04
  4830.3   99.56  4923.6  100.93  4996.3  100.26  5006.3   100.9  5016.7  101.88
  5058.1  104.78  5071.5  104.84  5136.5  108.72    5155  109.04  5262.8  116.62
  5277.3  118.68  5283.6  121.15  5305.9   123.6  5312.6  123.58  5327.1  125.82
  5356.1   127.2  5397.7  126.04  5404.5  126.49  5412.2  124.98  5426.5  124.57
#Mann= 4 ,-1 , 0
  4252.2      .1       0  4592.5     .07       0  5006.3      .1       0
  5404.5     .16       0
Bank Sta=4582.2,5016.7
XS Rating Curve= 0 ,0
Exp/Cntr=0.3,0.1