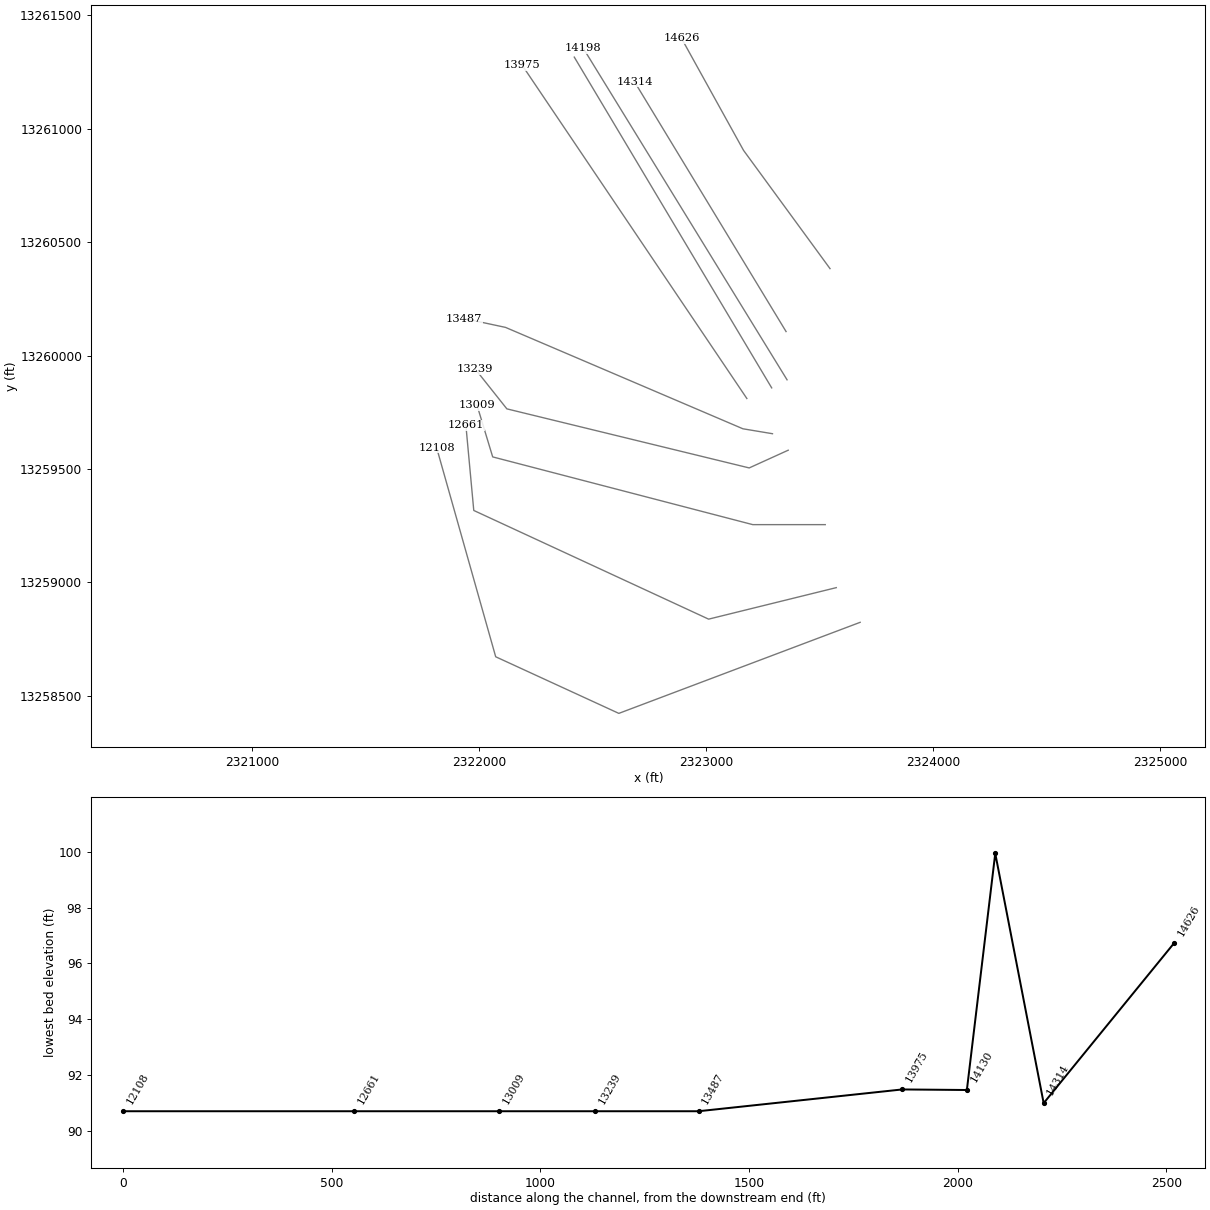
HEC-RAS study UNT011 IN PECR.prj: UNT011 IN PECR Base Level Engineering

--- UNT011 IN PECR.g01 (geometry) --- (continued)

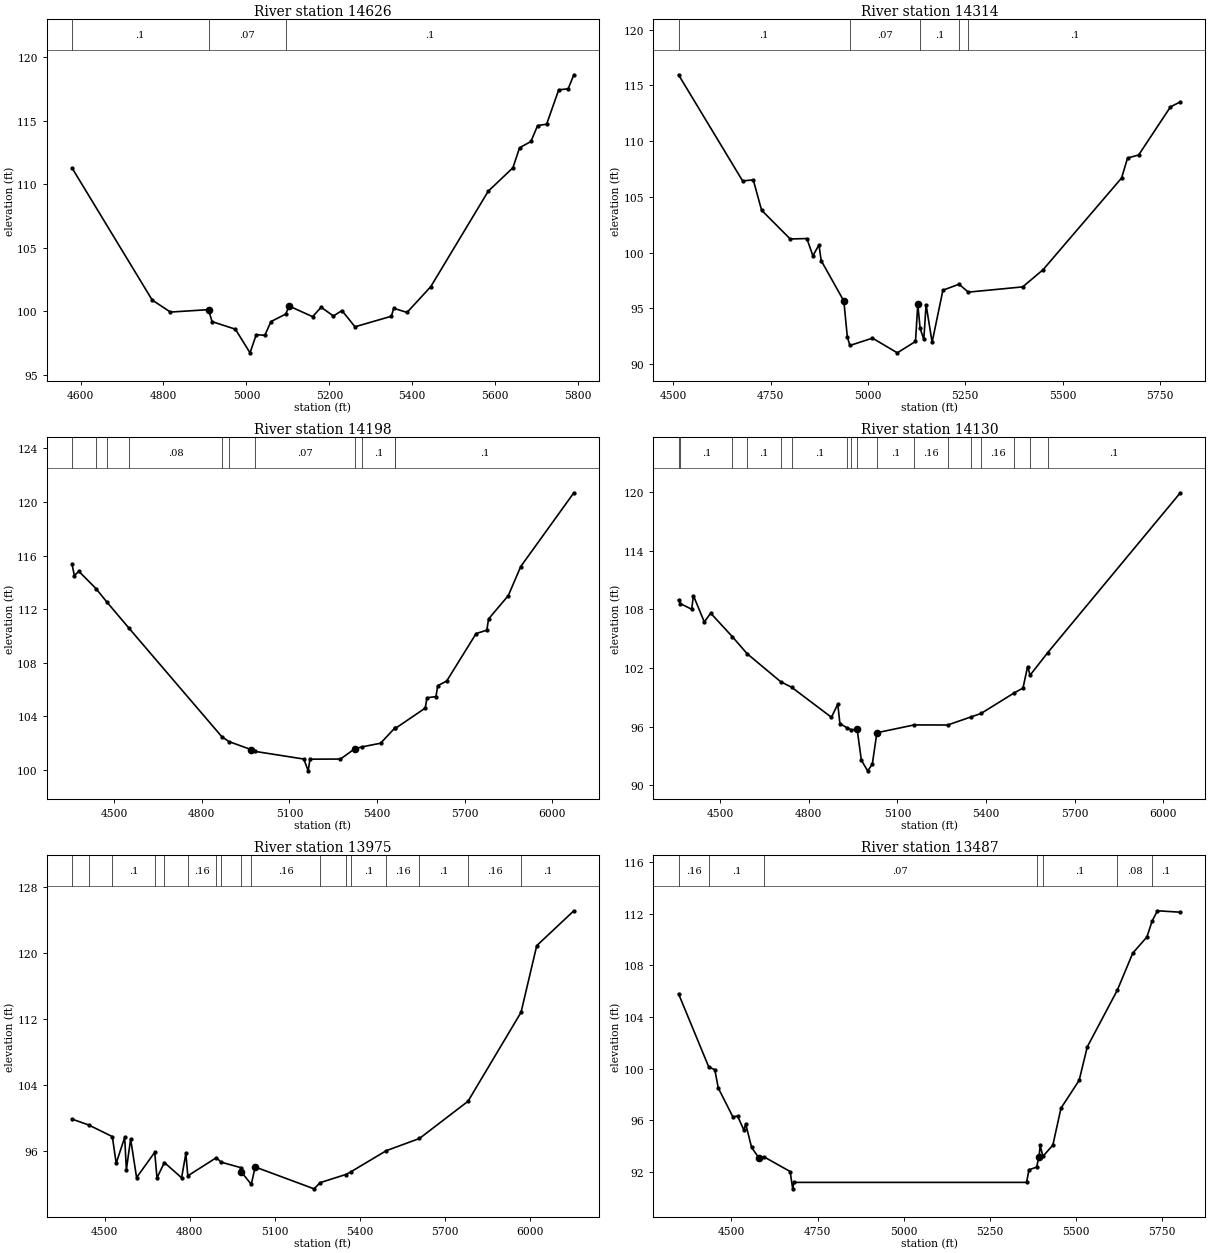
Type RM Length L Ch R = 1 ,14626   ,312,312,312
BEGIN DESCRIPTION:
Mapping XS 48ee3e83
END DESCRIPTION:
XS GIS Cut Line= 3
      2323544.98     13260383.51      2323163.91     13260904.97
      2322890.64     13261398.86
#Sta/Elev= 30
  4579.5  111.27  4772.7  100.88  4816.7   99.93  4908.6  100.12  4917.1   99.18
  4973.5   98.58  5008.7   96.72  5023.7   98.15  5044.5    98.1  5059.2   99.18
  5094.7   99.77  5103.2   100.4  5159.6   99.57  5180.4  100.31  5209.8   99.62
  5230.5  100.05  5261.8   98.77  5349.6    99.6  5355.3  100.23  5387.4    99.9
  5444.7  101.93  5583.2  109.44  5642.8  111.29  5658.8  112.86  5686.3  113.36
  5702.3  114.61  5724.1  114.72  5753.2  117.42  5776.1  117.51  5789.8  118.61
#Mann= 3 ,-1 , 0
  4579.5      .1       0  4908.6     .07       0  5094.7      .1       0
Bank Sta=4908.6,5103.2
XS Rating Curve= 0 ,0
Exp/Cntr=0.3,0.1

Type RM Length L Ch R = 1 ,14314   ,116,116,116
BEGIN DESCRIPTION:
Mapping XS 3600d7f0
END DESCRIPTION:
XS GIS Cut Line= 2
       2323351.3     13260106.06      2322682.91     13261208.47
#Sta/Elev= 30
  4513.4  115.96  4678.1  106.43  4705.4  106.53  4726.8   103.8  4800.4  101.22
  4843.1  101.26  4858.6   99.71  4874.1  100.69  4879.9   99.28  4938.1   95.65
    4947   92.45  4953.6   91.66  5011.7   92.32  5075.5      91  5122.2   92.02
  5128.1   95.35  5134.1   93.19  5143.6   92.21  5149.4   95.32  5164.9   91.95
  5192.6   96.62  5233.9   97.16    5258   96.45  5397.6   96.92  5449.9   98.46
  5651.6  106.69  5667.1  108.49  5695.5  108.76  5777.3  113.08  5802.6  113.53
#Mann= 5 ,-1 , 0
  4513.4      .1       0  4953.6     .07       0  5134.1      .1       0
  5233.9     .08       0    5258      .1       0
Bank Sta=4938.1,5128.1
XS Rating Curve= 0 ,0
Exp/Cntr=0.3,0.1

Type RM Length L Ch R = 1 ,14198   ,68,68,68
BEGIN DESCRIPTION:
Mapping XS 486720c9
END DESCRIPTION:
XS GIS Cut Line= 2
      2323355.68     13259893.33      2322457.22     13261356.03
#Sta/Elev= 30
  4356.5  115.34  4364.3  114.51  4379.7  114.82  4438.1  113.54  4475.2  112.54
    4552  110.56  4869.1  102.48  4893.5  102.12  4969.3  101.52  4982.6  101.39
  5149.2  100.82  5164.3   99.94  5170.4  100.81  5274.7  100.82  5323.2  101.58
  5348.9  101.73    5412     102    5460  103.12  5462.8  103.11  5564.7  104.62
  5570.6  105.39  5601.4  105.48  5607.3  106.29  5638.1  106.64  5738.7  110.18
  5775.4  110.43  5781.3  111.27  5848.8  113.01  5891.4  115.18  6073.1  120.68
#Mann= 11 ,-1 , 0
  4356.5      .1       0  4438.1     .08       0  4475.2      .1       0
    4552     .08       0  4869.1      .1       0  4893.5     .08       0
  4982.6     .07       0  5323.2     .08       0  5348.9      .1       0
    5460     .16       0  5462.8      .1       0
Bank Sta=4969.3,5323.2
XS Rating Curve= 0 ,0
Exp/Cntr=0.3,0.1

Type RM Length L Ch R = 1 ,14130   ,155,155,155
BEGIN DESCRIPTION:
UNT011 IN PECR 21.0
END DESCRIPTION:
XS GIS Cut Line= 2
      2323287.95     13259857.76      2322418.17     13261316.07
#Sta/Elev= 30
  4359.3  108.96  4365.7  108.58  4403.8  108.01  4409.6  109.41  4446.6   106.7
    4468  107.61  4541.1  105.21  4591.7  103.45  4704.7   100.6  4742.7  100.01
  4876.7   96.95  4898.1   98.29  4905.5   96.29  4930.8   95.86  4944.2   95.67
  4963.7   95.72  4977.9   92.57  4999.1   91.47  5014.9   92.13  5030.5   95.37
  5156.8   96.17  5269.8   96.16  5347.3   96.97  5382.8   97.34  5495.9   99.46
  5524.9   99.94  5540.5  102.14  5548.9  101.26  5608.9  103.58  6057.3  119.93
#Mann= 17 ,-1 , 0
  4359.3     .16       0  4365.7      .1       0  4541.1     .16       0
  4591.7      .1       0  4704.7     .08       0  4742.7      .1       0
  4930.8     .08       0  4944.2      .1       0  4963.7     .07       0
  5030.5      .1       0  5156.8     .16       0  5269.8     .08       0
  5347.3      .1       0  5382.8     .16       0  5495.9      .1       0
  5548.9     .16       0  5608.9      .1       0
Bank Sta=4963.7,5030.5
XS Rating Curve= 0 ,0
Exp/Cntr=0.3,0.1

Type RM Length L Ch R = 1 ,13975   ,488,488,488
BEGIN DESCRIPTION:
UNT011 IN PECR 20.0
END DESCRIPTION:
XS GIS Cut Line= 2
      2323178.55     13259810.93      2322188.97     13261279.67
#Sta/Elev= 30
  4385.2   99.91  4443.3   99.21  4527.3    97.8  4540.9   94.58  4570.9    97.7
  4576.9    93.8  4591.9   97.51  4612.9   92.85  4676.9    95.9  4684.9   92.82
    4711   94.67  4771.8   92.82  4786.8   95.76  4793.7   93.06  4894.7   95.26
  4910.5   94.72 4981.48   94.04  4981.7   93.57  5017.7   92.03  5031.4   94.13
  5239.4   91.49  5260.8   92.24  5350.4   93.21  5368.4   93.53  5494.3    96.1
  5611.1   97.57  5782.5  102.06  5969.7   112.8  6025.2  120.86  6156.2  125.07
#Mann= 17 ,-1 , 0
  4385.2      .1       0  4443.3     .16       0  4527.3      .1       0
  4676.9     .16       0    4711      .1       0  4793.7     .16       0
  4894.7     .12       0  4910.5     .16       0 4981.48     .07       0
  5017.7     .16       0  5260.8      .1       0  5350.4     .16       0
  5368.4      .1       0  5494.3     .16       0  5611.1      .1       0
  5782.5     .16       0  5969.7      .1       0
Bank Sta=4981.7,5031.4
XS Rating Curve= 0 ,0
Exp/Cntr=0.3,0.1

Type RM Length L Ch R = 1 ,13487   ,248,248,248
BEGIN DESCRIPTION:
UNT011 IN PECR 19.0
END DESCRIPTION:
XS GIS Cut Line= 4
      2323291.45     13259655.68      2323161.24     13259677.39
      2322115.23     13260124.43      2321932.92      13260163.5
#Sta/Elev= 30
  4346.4   105.8  4434.2  100.13  4451.6   99.93  4461.7   98.51    4504   96.28
  4517.8   96.34  4535.9   95.26  4541.4   95.72  4558.4   93.91  4580.1   93.09
    4594   93.19  4670.2   92.05  4677.7   90.71    4681   91.21  5356.3   91.21
  5363.1   92.18  5385.3   92.39  5392.5   93.19  5395.7   94.07  5403.6   93.22
  5432.5   94.09  5456.1   96.95  5508.8    99.1  5532.4  101.69  5619.6  106.08
  5664.5  108.95  5705.4  110.19  5720.6  111.43  5736.1  112.22  5802.4  112.11
#Mann= 7 ,-1 , 0
  4346.4     .16       0  4434.2      .1       0    4594     .07       0
  5385.3     .07       0  5403.6      .1       0  5619.6     .08       0
  5720.6      .1       0
Bank Sta=4580.1,5392.5
XS Rating Curve= 0 ,0
Exp/Cntr=0.3,0.1

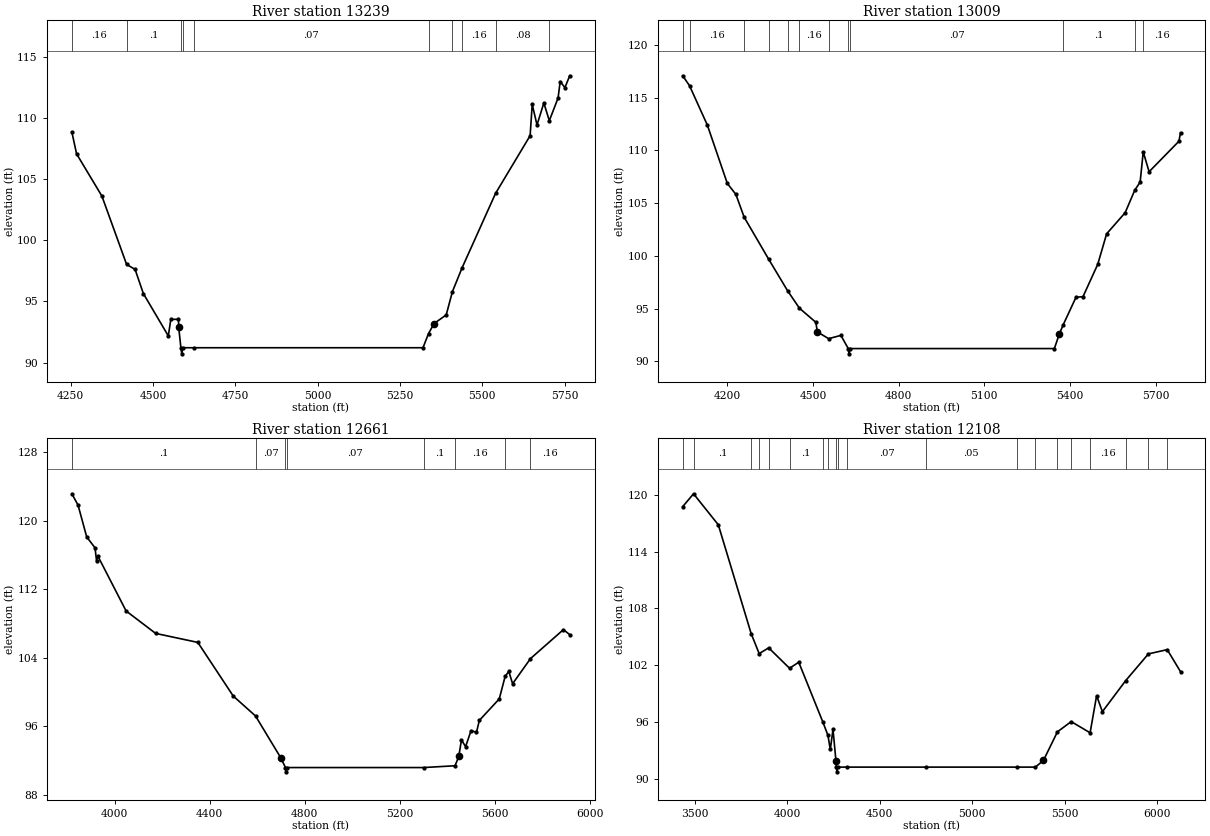
Type RM Length L Ch R = 1 ,13239   ,230,230,230
BEGIN DESCRIPTION:
UNT011 IN PECR 18.0
END DESCRIPTION:
XS GIS Cut Line= 4
      2323360.74     13259582.94      2323188.87     13259504.82
      2322121.16     13259765.24       2321981.8     13259940.74
#Sta/Elev= 30
  4253.8  108.89  4268.1   107.1    4345  103.64    4420   98.04  4445.8   97.63
  4470.9   95.65  4546.7   92.18  4554.3   93.54  4577.6   93.54 4578.18   92.91
  4584.9   91.21  4587.6   90.71  4590.9   91.21  4624.5   91.21  5320.1   91.21
    5337   92.37 5353.64   93.19  5390.7    93.9  5409.4    95.8  5438.7   97.75
  5540.5  103.86  5645.5  108.59  5651.9  111.15  5666.4  109.47  5687.2  111.27
  5703.8  109.82  5730.4  111.68  5736.8  113.03  5751.2  112.53  5765.7   113.5
#Mann= 10 ,-1 , 0
  4253.8     .16       0    4420      .1       0  4584.9     .07       0
  4590.9      .1       0  4624.5     .07       0    5337     .16       0
  5409.4      .1       0  5438.7     .16       0  5540.5     .08       0
  5703.8     .16       0
Bank Sta=4578.18,5353.64
XS Rating Curve= 0 ,0
Exp/Cntr=0.3,0.1

Type RM Length L Ch R = 1 ,13009   ,348,348,348
BEGIN DESCRIPTION:
UNT011 IN PECR 17.0
END DESCRIPTION:
XS GIS Cut Line= 4
      2323523.94     13259254.82       2323204.5     13259254.82
      2322058.66     13259553.43      2321989.34     13259782.21
#Sta/Elev= 30
  4044.3  117.08  4068.2  116.14  4130.5  112.41  4200.5  106.87  4230.5  105.83
  4259.4  103.67  4345.8   99.66  4411.5   96.69  4452.9   95.04  4510.4    93.7
  4515.6   92.79  4555.1   92.15  4598.1   92.46  4623.8   91.21  4626.5   90.71
  4629.8   91.21  5345.3   91.21  5362.8    92.6  5376.3   93.47  5421.1   96.08
  5445.5   96.13    5497   99.19  5528.2  102.09  5593.2   104.1  5626.6  106.22
  5645.5     107  5656.4  109.86  5676.9  107.98  5781.3  110.87  5786.9  111.68
#Mann= 12 ,-1 , 0
  4044.3      .1       0  4068.2     .16       0  4259.4      .1       0
  4345.8     .16       0  4411.5      .1       0  4452.9     .16       0
  4555.1     .07       0  4623.8     .07       0  4629.8     .07       0
  5376.3      .1       0  5626.6     .08       0  5656.4     .16       0
Bank Sta=4515.6,5362.8
XS Rating Curve= 0 ,0
Exp/Cntr=0.3,0.1

Type RM Length L Ch R = 1 ,12661   ,553,553,553
BEGIN DESCRIPTION:
UNT011 IN PECR 16.0
END DESCRIPTION:
XS GIS Cut Line= 4
      2323572.52     13258977.03      2323010.05     13258838.15
      2321975.33     13259317.32      2321940.63     13259692.07
#Sta/Elev= 30
  3820.4  123.15  3846.5  121.82  3882.9  118.11    3918  116.84  3924.3  115.32
  3929.5   115.9  4048.7  109.48  4173.1  106.86  4350.7  105.81  4499.9   99.55
  4593.6   97.23  4699.9   92.35  4719.7   91.21  4722.4   90.71  4725.7   91.21
  5301.2   91.21  5433.7   91.42  5449.3    92.5  5460.7   94.43  5478.1   93.65
    5501   95.51    5524   95.33    5536   96.71  5619.9   99.22  5644.7  101.86
  5660.1  102.42    5676  100.99  5751.3  103.92  5889.9   107.3  5916.4  106.72
#Mann= 8 ,-1 , 0
  3820.4      .1       0  4593.6     .07       0  4719.7     .07       0
  4725.7     .07       0  5301.2      .1       0  5433.7     .16       0
  5644.7      .1       0  5751.3     .16       0
Bank Sta=4699.9,5449.3
XS Rating Curve= 0 ,0
Exp/Cntr=0.3,0.1

Type RM Length L Ch R = 1 ,12108   ,0,0,0
BEGIN DESCRIPTION:
UNT011 IN PECR 1.0
END DESCRIPTION:
XS GIS Cut Line= 4
      2323677.78     13258824.14      2322614.44     13258422.67
      2322071.91     13258672.24      2321811.86     13259593.25
#Sta/Elev= 30
  3435.9  118.75  3494.5  120.11  3628.4  116.83  3805.9  105.33  3849.2  103.21
  3900.8  103.82  4013.4  101.66  4063.2   102.3  4193.2   95.99    4221   94.57
  4233.7   93.08  4248.3   95.19  4264.2   91.89  4266.7   91.21  4269.5   90.71
  4272.7   91.21  4324.8   91.21  4749.6   91.21  5240.5   91.21  5342.2   91.21
 5385.79   91.92  5461.4   94.94  5535.7   96.02    5638   94.84  5673.2   98.76
  5704.4   97.07  5829.3  100.33    5953  103.18  6054.8  103.63  6126.7   101.3
#Mann= 20 ,-1 , 0
  3435.9     .05       0  3494.5      .1       0  3805.9     .16       0
  3849.2      .1       0  3900.8     .16       0  4013.4      .1       0
  4193.2     .16       0    4221     .05       0  4266.7    .033       0
  4272.7     .05       0  4324.8     .07       0  4749.6     .05       0
  5240.5     .05       0  5342.2     .07       0  5461.4     .16       0
  5535.7     .07       0    5638     .16       0  5829.3      .1       0
    5953     .16       0  6054.8     .16       0
Bank Sta=4264.2,5385.79
XS Rating Curve= 0 ,0
Exp/Cntr=0.3,0.1

Chan Stop Cuts=-1
Use User Specified Reach Order=0
Composite Channel Slope=5