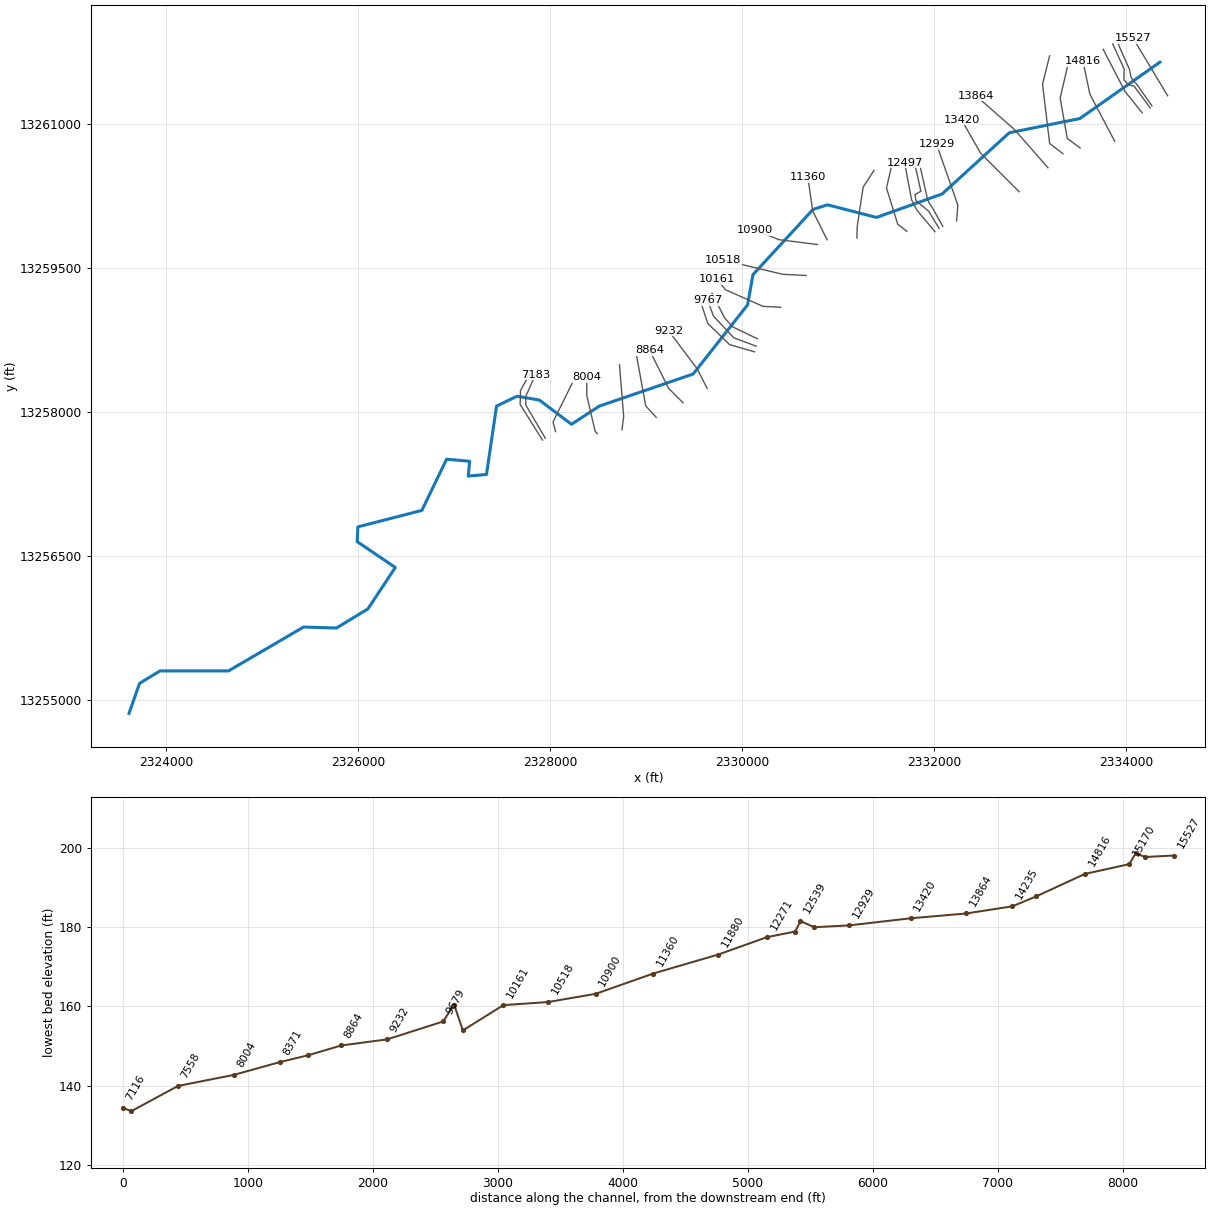
--- UNT012 IN PECR.prj (project) ---

Proj Title=UNT012 IN PECR Base Level Engineering
Current Plan=p01
Default Exp/Contr=0.3,0.1
English Units
Geom File=g01
Flow File=f01
Plan File=p01
Y Axis Title=Elevation
X Axis Title(PF)=Main Channel Distance
X Axis Title(XS)=Station
BEGIN DESCRIPTION:
UNT012 IN PECR
END DESCRIPTION:
DSS Export Rating Curves= 0
DSS Export Rating Curve Sorted= 0
DSS Export Volume Flow Curves= 0
DXF OffsetX= 0
DXF OffsetY= 0
DXF ScaleX= 1
DXF ScaleY= 10

--- UNT012 IN PECR.p01 (plan) ---

Plan Title=Multiple Run
Short Identifier=Multiple
Geom File=g01
Flow File=f01
Subcritical Flow
K Sum by GR= 0
Std Step Tol= 0.01
Critical Tol= 0.01
Num of Std Step Trials= 20
Max Error Tol= 0.3
Flow Tol Ratio= 0.001
Split Flow NTrial= 30
Split Flow Tol= 0.02
Split Flow Ratio= 0.02
Log Output Level= 0
Friction Slope Method= 1
Unsteady Friction Slope Method= 2
Unsteady Bridges Friction Slope Method= 1
Parabolic Critical Depth
Global Vel Dist=  1 , 1 , 1
Global Log Level= 0
CheckData=True
Encroach Param= -1, 0, 0, 0
BEGIN DESCRIPTION:
Multiple Run
END DESCRIPTION:

--- UNT012 IN PECR.f01 (steady flow) ---

Flow Title=Multiple
Program Version=4.10
Number of Profiles= 7
Profile Names=10-year,25-year,50-year,1pct_min,100-year,1pct_plu,500-year
River Rch & RM=UNT012 IN PECR,Reach-1         ,15527
     333     440     523     453     613     829     845
River Rch & RM=UNT012 IN PECR,Reach-1         ,15297
     666     928    1145    1029    1392    1882    2065
River Rch & RM=UNT012 IN PECR,Reach-1         ,4980
     757    1065    1321    1194    1615    2184    2425
Boundary for River Rch & Prof#=UNT012 IN PECR,Reach-1         , 1
Up Type= 0
Dn Type= 3
Dn Slope=0.005
Boundary for River Rch & Prof#=UNT012 IN PECR,Reach-1         , 2
Up Type= 0
Dn Type= 3
Dn Slope=0.005
Boundary for River Rch & Prof#=UNT012 IN PECR,Reach-1         , 3
Up Type= 0
Dn Type= 3
Dn Slope=0.005
Boundary for River Rch & Prof#=UNT012 IN PECR,Reach-1         , 4
Up Type= 0
Dn Type= 3
Dn Slope=0.005
Boundary for River Rch & Prof#=UNT012 IN PECR,Reach-1         , 5
Up Type= 0
Dn Type= 3
Dn Slope=0.005
Boundary for River Rch & Prof#=UNT012 IN PECR,Reach-1         , 6
Up Type= 0
Dn Type= 3
Dn Slope=0.005
Boundary for River Rch & Prof#=UNT012 IN PECR,Reach-1         , 7
Up Type= 0
Dn Type= 3
Dn Slope=0.005
DSS Import GetInterval= 0
DSS Import GetPeak= 0
DSS Import FillOption= 0

--- UNT012 IN PECR.g01 (geometry) ---

Geom Title=Existing Conditions

River Reach=UNT012 IN PECR,Reach-1
Reach XY= 30
      2334353.30     13261646.85      2333520.24     13261059.69
      2332785.08     13260911.47      2332086.33     13260273.85
      2331402.04     13260028.93      2330891.56     13260160.60
      2330741.53     13260112.64      2330115.79     13259432.95
      2330059.42     13259117.39      2329492.63     13258397.03
      2328514.90     13258062.28      2328225.32     13257873.01
      2327892.16     13258124.98      2327658.35     13258165.82
      2327444.67     13258062.27      2327340.15     13257349.85
      2327150.04     13257333.19      2327164.63     13257487.35
      2326924.52     13257509.23      2326667.07     13256975.46
      2326000.84     13256804.02      2325993.24     13256649.94
      2326390.38     13256380.84      2326105.01     13255948.98
      2325777.00     13255749.40      2325434.89     13255759.97
      2324653.42     13255302.68      2323939.88     13255302.68
      2323726.34     13255172.48      2323616.97     13254859.98

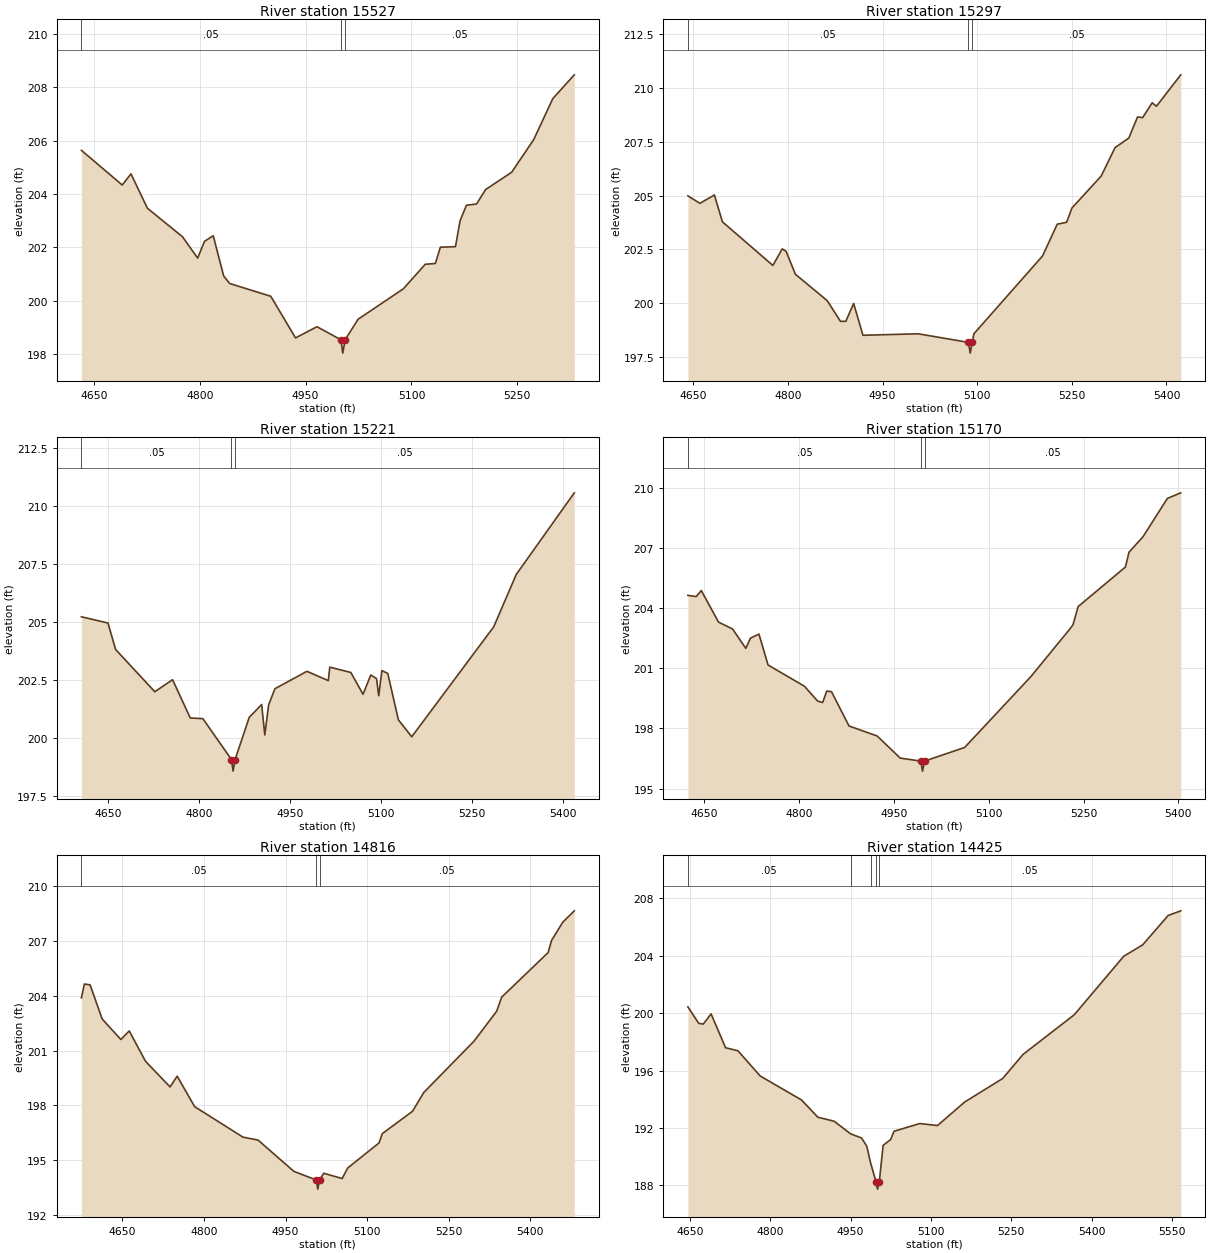
Type RM Length L Ch R = 1,15527,230,230,230
BEGIN DESCRIPTION:
UNT012 IN PECR 33.0
END DESCRIPTION:
XS GIS Cut Line= 2
      2334435.06     13261296.70      2334075.69     13261895.66
#Sta/Elev= 30
  4632.3  205.64  4690.1  204.34  4702.5  204.76  4725.8  203.47  4775.6  202.40
  4797.0  201.60  4806.7  202.23  4819.1  202.44  4833.9  200.93  4842.4  200.65
  4900.7  200.17  4935.7  198.61  4966.1  199.03  5000.0  198.54  5002.7  198.04
  5006.0  198.54  5024.4  199.31  5088.5  200.45  5119.6  201.37  5133.9  201.40
  5141.0  202.01  5162.4  202.03  5168.9  203.00  5177.9  203.58  5192.3  203.63
  5205.1  204.17  5242.1  204.82  5273.2  206.04  5300.4  207.58  5330.8  208.47
#Mann=3,-1,0
  4632.3    0.05       0  5000.0    0.03       0  5006.0    0.05       0
Bank Sta=5000,5006
Exp/Cntr=0.3,0.1

Type RM Length L Ch R = 1,15297,76,76,76
BEGIN DESCRIPTION:
Mapping XS 0e1cca04
END DESCRIPTION:
XS GIS Cut Line= 6
      2334271.00     13261192.53      2334106.93     13261424.32
      2334073.08     13261455.57      2334052.24     13261497.23
      2334036.62     13261572.75      2333903.87     13261872.09
#Sta/Elev= 30
  4641.5  204.99  4660.5  204.64  4683.5  205.03  4696.2  203.78  4776.2  201.75
  4791.0  202.52  4797.1  202.41  4811.9  201.34  4862.4  200.11  4883.3  199.15
  4891.8  199.15  4904.2  199.98  4919.0  198.50  5006.5  198.57  5086.2  198.17
  5089.0  197.67  5092.2  198.17  5094.8  198.57  5203.6  202.19  5226.9  203.67
  5241.9  203.76  5250.1  204.42  5296.6  205.91  5318.5  207.23  5340.4  207.68
  5354.2  208.66  5362.3  208.63  5377.4  209.32  5384.2  209.16  5422.7  210.62
#Mann=3,-1,0
  4641.5    0.05       0  5086.2    0.03       0  5092.2    0.05       0
Bank Sta=5086.2,5092.2
Exp/Cntr=0.3,0.1

Type RM Length L Ch R = 1,15221,51,51,51
BEGIN DESCRIPTION:
Mapping XS dcdd0059
END DESCRIPTION:
XS GIS Cut Line= 6
      2334252.75     13261171.73      2334086.10     13261395.67
      2334023.60     13261413.90      2333979.33     13261463.38
      2333981.93     13261575.36      2333862.43     13261837.75
#Sta/Elev= 30
  4605.4  205.22  4649.2  204.95  4661.8  203.81  4726.4  201.99  4755.7  202.51
  4784.9  200.86  4805.7  200.83  4852.8  199.07  4855.5  198.57  4858.8  199.07
  4882.2  200.89  4902.6  201.44  4907.8  200.13  4914.1  201.42  4924.5  202.12
  4977.3  202.87  5012.5  202.47  5015.0  203.05  5049.7  202.82  5069.8  201.88
  5082.6  202.71  5092.0  202.56  5095.7  201.82  5100.9  202.90  5110.6  202.78
  5128.1  200.78  5150.1  200.05  5285.4  204.79  5322.4  207.04  5418.2  210.56
#Mann=3,-1,0
  4605.4    0.05       0  4852.8    0.03       0  4858.8    0.05       0
Bank Sta=4852.8,4858.8
Exp/Cntr=0.3,0.1

Type RM Length L Ch R = 1,15170,354,354,354
BEGIN DESCRIPTION:
Mapping XS 8099c94e
END DESCRIPTION:
XS GIS Cut Line= 3
      2334169.45     13261119.61      2333989.74     13261343.59
      2333763.20     13261781.05
#Sta/Elev= 30
  4624.0  204.63  4637.2  204.57  4645.2  204.87  4672.4  203.30  4694.8  202.95
  4715.6  201.99  4723.0  202.50  4736.4  202.70  4750.8  201.16  4808.4  200.10
  4829.3  199.36  4837.2  199.29  4843.7  199.86  4851.2  199.83  4878.9  198.12
  4923.5  197.62  4959.9  196.52  4992.5  196.37  4995.2  195.87  4998.5  196.37
  5061.9  197.05  5166.9  200.59  5227.7  202.93  5233.3  203.16  5241.4  204.07
  5316.2  206.04  5321.9  206.78  5344.0  207.55  5382.6  209.46  5403.8  209.74
#Mann=3,-1,0
  4624.0    0.05       0  4992.5    0.03       0  4998.5    0.05       0
Bank Sta=4992.5,4998.5
Exp/Cntr=0.3,0.1

Type RM Length L Ch R = 1,14816,391,391,391
BEGIN DESCRIPTION:
UNT012 IN PECR 32.0
END DESCRIPTION:
XS GIS Cut Line= 3
      2333882.98     13260822.73      2333625.16     13261312.34
      2333552.49     13261657.53
#Sta/Elev= 30
  4574.8  203.89  4580.2  204.65  4590.8  204.60  4613.0  202.73  4647.3  201.61
  4662.7  202.08  4692.5  200.42  4737.7  199.01  4750.8  199.60  4782.9  197.93
  4871.7  196.26  4899.4  196.10  4965.5  194.38  5006.6  193.91  5009.3  193.41
  5012.6  193.91  5020.2  194.28  5054.1  193.99  5064.4  194.57  5121.9  195.94
  5127.9  196.45  5183.6  197.68  5204.3  198.71  5296.3  201.51  5338.2  203.16
  5347.4  203.93  5432.7  206.37  5439.3  207.05  5459.8  208.04  5480.9  208.66
#Mann=3,-1,0
  4574.8    0.05       0  5006.6    0.03       0  5012.6    0.05       0
Bank Sta=5006.6,5012.6
Exp/Cntr=0.3,0.1

Type RM Length L Ch R = 1,14425,190,190,190
BEGIN DESCRIPTION:
UNT012 IN PECR 31.0
END DESCRIPTION:
XS GIS Cut Line= 4
      2333523.49     13260753.03      2333388.97     13260852.84
      2333315.18     13261273.84      2333388.96     13261590.64
#Sta/Elev= 30
  4646.3  200.44  4666.6  199.29  4675.0  199.24  4689.6  199.95  4716.7  197.59
  4739.7  197.38  4781.4  195.62  4858.5  193.95  4889.0  192.75  4919.4  192.47
  4950.2  191.59  4970.6  191.30  4980.3  190.73  4987.4  189.57  4997.6  188.24
  5000.4  187.74  5003.6  188.24  5010.8  190.79  5024.9  191.20  5031.1  191.77
  5079.2  192.31  5112.3  192.17  5163.1  193.81  5234.1  195.45  5272.2  197.13
  5367.7  199.89  5459.9  203.96  5495.4  204.76  5543.1  206.81  5566.5  207.13
#Mann=5,-1,0
  4646.3    0.05       0  4950.2     0.1       0  4987.4    0.05       0
  4997.6    0.03       0  5003.6    0.05       0
Bank Sta=4997.6,5003.6
Exp/Cntr=0.3,0.1

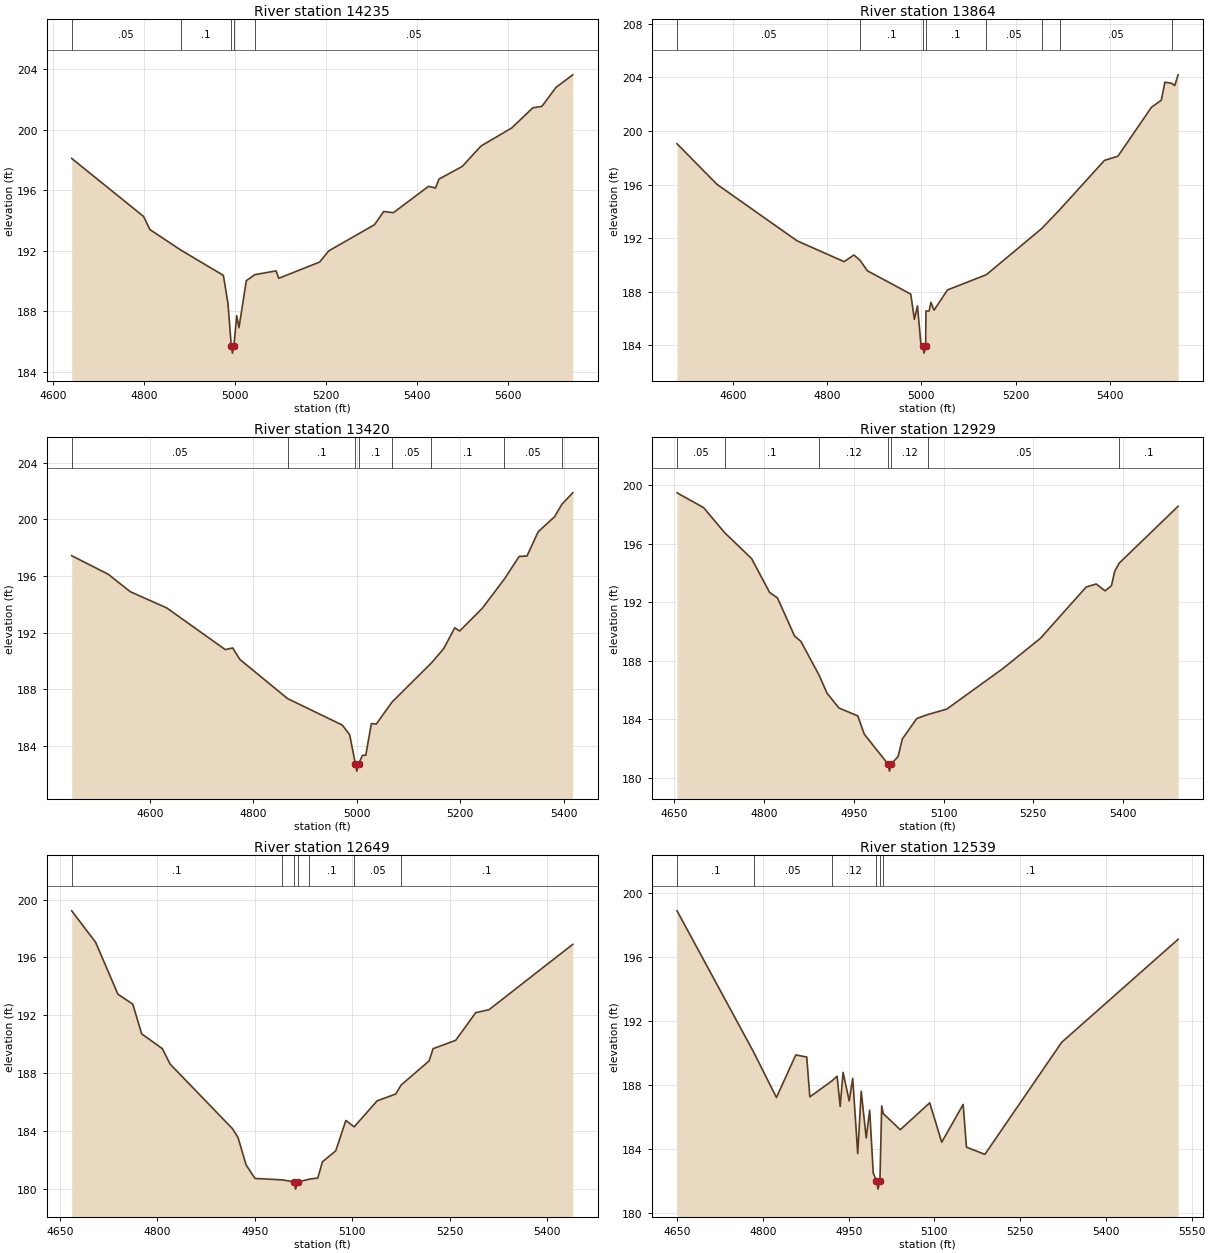
Type RM Length L Ch R = 1,14235,371,371,371
BEGIN DESCRIPTION:
Mapping XS 71eb897f
END DESCRIPTION:
XS GIS Cut Line= 4
      2333344.40     13260692.26      2333205.35     13260800.89
      2333131.48     13261417.91      2333205.17     13261712.66
#Sta/Elev= 30
  4641.6  198.09  4799.7  194.26  4813.4  193.40  4881.1  192.05  4975.1  190.37
  4985.2  188.52  4992.3  185.74  4995.0  185.24  4998.3  185.74  5004.4  187.71
  5009.4  186.92  5025.5  190.02  5044.2  190.42  5091.0  190.67  5096.8  190.18
  5186.6  191.25  5206.8  191.99  5307.5  193.72  5327.6  194.59  5348.9  194.51
  5426.2  196.25  5441.5  196.14  5449.2  196.73  5500.2  197.56  5541.5  198.91
  5609.0  200.10  5655.4  201.43  5675.5  201.53  5706.4  202.78  5743.3  203.61
#Mann=5,-1,0
  4641.6    0.05       0  4881.1     0.1       0  4992.3    0.07       0
  4998.3     0.1       0  5044.2    0.05       0
Bank Sta=4992.3,4998.3
Exp/Cntr=0.3,0.1

Type RM Length L Ch R = 1,13864,444,444,444
BEGIN DESCRIPTION:
UNT012 IN PECR 30.0
END DESCRIPTION:
XS GIS Cut Line= 3
      2333187.70     13260546.88      2332837.72     13260946.85
      2332437.70     13261296.87
#Sta/Elev= 30
  4481.9  199.04  4566.8  196.01  4736.7  191.80  4836.4  190.25  4857.2  190.75
  4870.3  190.34  4885.7  189.57  4977.8  187.83  4985.4  185.95  4992.0  186.95
  4999.6  183.97  5003.3  183.93  5006.0  183.43  5009.3  183.93  5010.0  186.57
  5016.7  186.57  5020.5  187.22  5027.1  186.63  5055.6  188.14  5138.2  189.28
  5255.3  192.71  5293.4  194.11  5388.7  197.80  5417.2  198.11  5488.4  201.76
  5509.3  202.29  5516.9  203.63  5531.0  203.55  5537.8  203.38  5544.9  204.18
#Mann=8,-1,0
  4481.9    0.05       0  4870.3     0.1       0  5003.3    0.07       0
  5009.3     0.1       0  5138.2    0.05       0  5255.3     0.1       0
  5293.4    0.05       0  5531.0     0.1       0
Bank Sta=5003.3,5009.3
Exp/Cntr=0.3,0.1

Type RM Length L Ch R = 1,13420,491,491,491
BEGIN DESCRIPTION:
UNT012 IN PECR 29.0
END DESCRIPTION:
XS GIS Cut Line= 3
      2332887.75     13260296.83      2332487.72     13260696.85
      2332287.74     13261046.82
#Sta/Elev= 30
  4448.8  197.43  4519.5  196.12  4562.0  194.89  4632.7  193.74  4745.8  190.80
  4760.0  190.92  4774.1  190.10  4866.3  187.34  4972.1  185.47  4986.2  184.79
  4997.4  182.72  5000.1  182.22  5003.4  182.72  5011.0  183.34  5017.4  183.34
  5028.2  185.58  5037.6  185.54  5068.0  187.09  5144.3  189.86  5167.9  190.86
  5189.4  192.34  5198.8  192.11  5242.7  193.72  5285.5  195.79  5314.0  197.38
  5329.1  197.41  5350.7  199.12  5382.4  200.18  5396.5  201.06  5417.6  201.87
#Mann=8,-1,0
  4448.8    0.05       0  4866.3     0.1       0  4997.4    0.07       0
  5003.4     0.1       0  5068.0    0.05       0  5144.3     0.1       0
  5285.5    0.05       0  5396.5     0.1       0
Bank Sta=4997.4,5003.4
Exp/Cntr=0.3,0.1

Type RM Length L Ch R = 1,12929,280,280,280
BEGIN DESCRIPTION:
UNT012 IN PECR 28.0
END DESCRIPTION:
XS GIS Cut Line= 3
      2332236.36     13259992.68      2332249.40     13260157.80
      2332027.86     13260791.99
#Sta/Elev= 30
  4654.6  199.49  4698.9  198.48  4734.2  196.76  4779.2  194.99  4809.3  192.67
  4822.4  192.30  4851.0  189.69  4861.6  189.32  4892.2  186.99  4905.2  185.78
  4925.2  184.76  4956.7  184.22  4967.5  182.97  5006.9  180.94  5009.6  180.44
  5012.9  180.94  5024.1  181.44  5031.1  182.64  5055.2  184.04  5073.3  184.31
  5105.2  184.68  5199.8  187.48  5261.9  189.53  5338.3  193.04  5355.1  193.25
  5370.0  192.78  5380.6  193.13  5386.1  194.12  5393.4  194.67  5492.0  198.57
#Mann=7,-1,0
  4654.6    0.05       0  4734.2     0.1       0  4892.2    0.12       0
  5006.9    0.07       0  5012.9    0.12       0  5073.3    0.05       0
  5393.4     0.1       0
Bank Sta=5006.9,5012.9
Exp/Cntr=0.3,0.1

Type RM Length L Ch R = 1,12649,110,110,110
BEGIN DESCRIPTION:
Mapping XS 80f45439
END DESCRIPTION:
XS GIS Cut Line= 5
      2332093.46     13259934.77      2331980.63     13260136.56
      2331950.25     13260179.96      2331932.89     13260223.36
      2331835.35     13260652.50
#Sta/Elev= 30
  4668.4  199.23  4705.2  197.05  4739.5  193.46  4762.4  192.77  4776.0  190.72
  4807.9  189.69  4819.7  188.63  4915.8  184.15  4924.4  183.53  4936.8  181.64
  4950.4  180.71  4992.7  180.61  5010.2  180.47  5012.9  179.97  5016.2  180.47
  5034.2  180.66  5047.1  180.74  5054.2  181.86  5074.7  182.62  5090.2  184.72
  5103.0  184.28  5138.4  186.08  5167.0  186.55  5175.0  187.16  5218.3  188.84
  5224.5  189.69  5259.3  190.27  5290.0  192.18  5310.6  192.39  5439.4  196.91
#Mann=7,-1,0
  4668.4     0.1       0  4992.7    0.12       0  5010.2    0.07       0
  5016.2    0.12       0  5034.2     0.1       0  5103.0    0.05       0
  5175.0     0.1       0
Bank Sta=5010.2,5016.2
Exp/Cntr=0.3,0.1

Type RM Length L Ch R = 1,12539,42,42,42
BEGIN DESCRIPTION:
UNT012 IN PECR 27.0
END DESCRIPTION:
XS GIS Cut Line= 6
      2332054.41     13259915.21      2331945.91     13260093.15
      2331813.53     13260203.83      2331802.68     13260266.76
      2331864.42     13260301.70      2331787.73     13260646.81
#Sta/Elev= 30
  4649.8  198.90  4783.6  190.09  4823.7  187.24  4857.5  189.90  4876.7  189.77
  4882.1  187.28  4920.3  188.27  4929.8  188.57  4935.2  186.68  4940.2  188.81
  4951.0  187.03  4957.1  188.44  4965.9  183.74  4972.0  187.63  4980.7  184.72
  4986.8  186.45  4993.0  182.53  4998.7  182.02  5001.4  181.52  5004.7  182.02
  5007.8  186.72  5010.5  186.24  5040.3  185.23  5091.8  186.91  5112.8  184.45
  5150.3  186.81  5156.1  184.14  5188.3  183.69  5322.7  190.69  5526.3  197.12
#Mann=6,-1,0
  4649.8     0.1       0  4783.6    0.05       0  4920.3    0.12       0
  4998.7    0.07       0  5004.7    0.12       0  5010.5     0.1       0
Bank Sta=4998.7,5004.7
Exp/Cntr=0.3,0.1

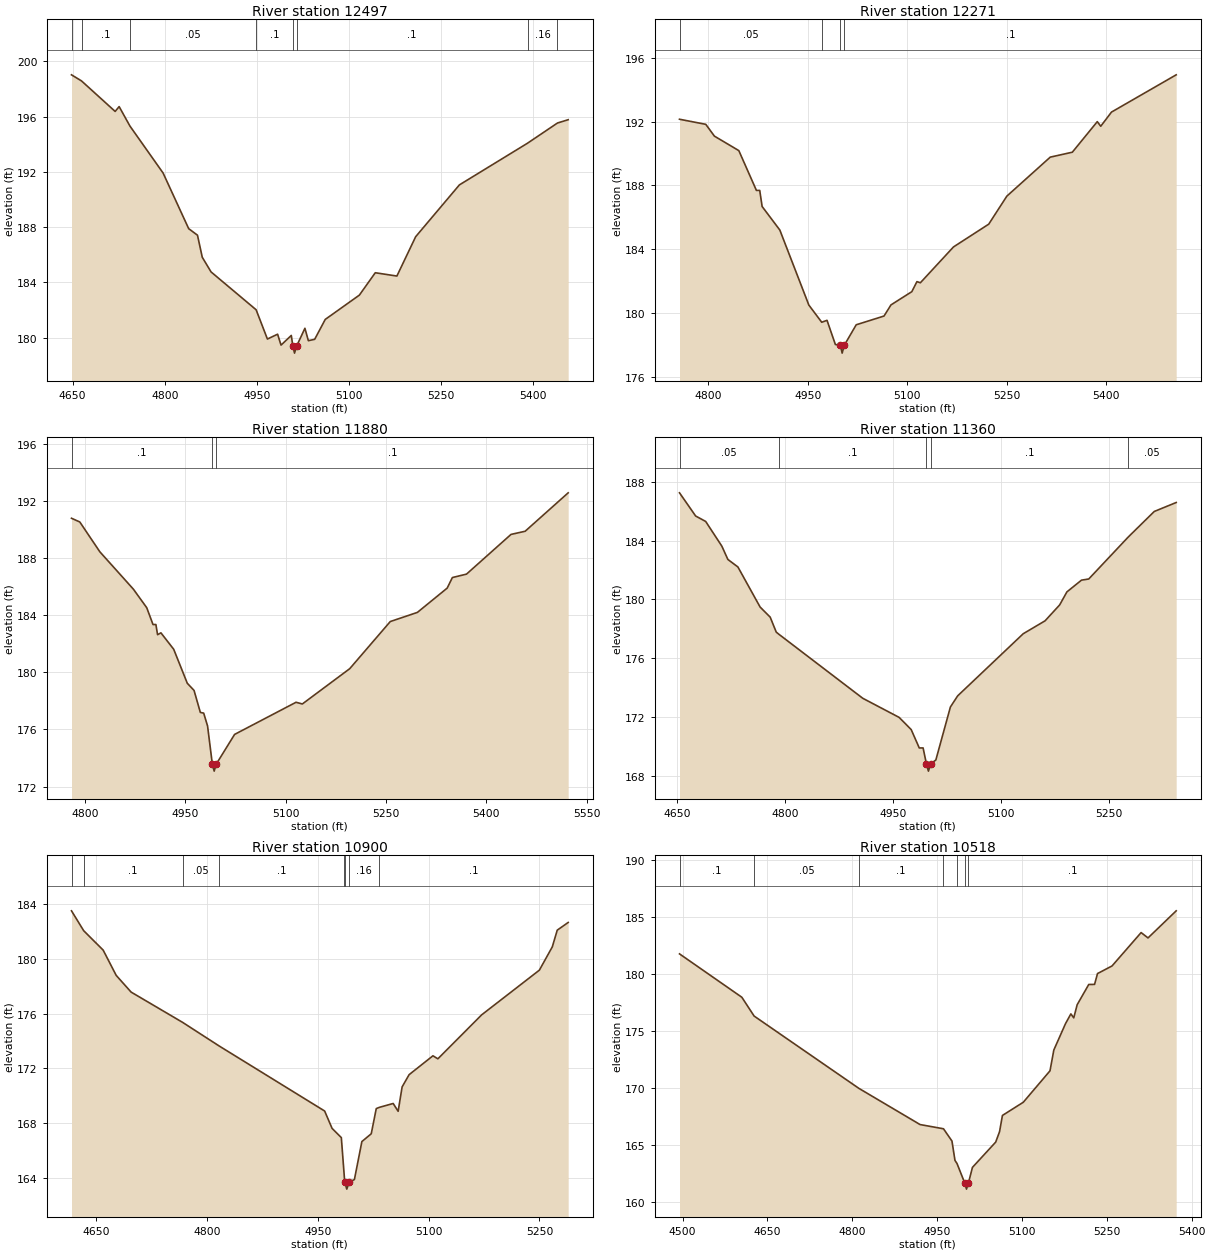
Type RM Length L Ch R = 1,12497,226,226,226
BEGIN DESCRIPTION:
Mapping XS 458e6a4d
END DESCRIPTION:
XS GIS Cut Line= 4
      2332011.01     13259880.48      2331822.21     13260106.17
      2331767.96     13260212.51      2331694.18     13260600.94
#Sta/Elev= 30
  4648.1  199.03  4664.4  198.59  4719.2  196.38  4725.7  196.73  4743.3  195.32
  4797.3  191.92  4839.0  187.89  4853.3  187.42  4861.1  185.82  4875.4  184.76
  4948.8  182.02  4967.2  179.90  4983.8  180.25  4989.4  179.46  5006.1  180.16
  5008.7  179.38  5011.4  178.88  5014.7  179.38  5028.3  180.68  5033.9  179.78
  5044.2  179.88  5061.4  181.32  5117.0  183.08  5142.9  184.70  5178.1  184.46
  5208.7  187.31  5279.9  191.06  5390.9  194.08  5439.6  195.54  5457.1  195.78
#Mann=8,-1,0
  4648.1    0.05       0  4664.4     0.1       0  4743.3    0.05       0
  4948.8     0.1       0  5008.7    0.07       0  5014.7     0.1       0
  5390.9    0.16       0  5439.6     0.1       0
Bank Sta=5008.7,5014.7
Exp/Cntr=0.3,0.1

Type RM Length L Ch R = 1,12271,391,391,391
BEGIN DESCRIPTION:
UNT012 IN PECR 26.0
END DESCRIPTION:
XS GIS Cut Line= 4
      2331719.31     13259884.02      2331623.68     13259957.91
      2331506.36     13260335.95      2331558.49     13260561.84
#Sta/Elev= 30
  4756.9  192.16  4796.5  191.84  4809.5  191.10  4846.3  190.19  4872.8  187.69
  4877.8  187.69  4881.4  186.68  4908.1  185.20  4951.8  180.49  4971.2  179.41
  4979.2  179.53  4991.8  178.01  4999.3  177.97  5002.0  177.47  5005.3  177.97
  5023.2  179.25  5065.1  179.80  5075.6  180.50  5107.0  181.33  5114.7  181.96
  5119.9  181.89  5169.8  184.14  5222.9  185.57  5250.2  187.33  5315.6  189.78
  5348.9  190.09  5386.5  192.01  5391.7  191.72  5407.9  192.61  5505.4  194.95
#Mann=4,-1,0
  4756.9    0.05       0  4971.2     0.1       0  4999.3    0.07       0
  5005.3     0.1       0
Bank Sta=4999.3,5005.3
Exp/Cntr=0.3,0.1

Type RM Length L Ch R = 1,11880,520,520,520
BEGIN DESCRIPTION:
UNT012 IN PECR 25.0
END DESCRIPTION:
XS GIS Cut Line= 4
      2331197.85     13259814.49      2331202.19     13259940.53
      2331263.03     13260344.64      2331376.02     13260518.47
#Sta/Elev= 30
  4780.2  190.78  4792.6  190.52  4822.6  188.43  4872.6  185.82  4892.6  184.52
  4902.0  183.34  4906.3  183.34  4908.8  182.63  4913.8  182.76  4932.9  181.61
  4953.2  179.23  4963.3  178.73  4972.7  177.19  4977.7  177.14  4983.5  176.24
  4990.6  173.58  4993.4  173.08  4996.6  173.58  5023.9  175.65  5115.7  177.90
  5125.1  177.78  5195.9  180.25  5256.5  183.55  5297.0  184.19  5341.5  185.89
  5349.3  186.63  5370.4  186.87  5436.9  189.65  5458.0  189.87  5522.3  192.56
#Mann=3,-1,0
  4780.2     0.1       0  4990.6    0.07       0  4996.6     0.1       0
Bank Sta=4990.6,4996.6
Exp/Cntr=0.3,0.1

Type RM Length L Ch R = 1,11360,460,460,460
BEGIN DESCRIPTION:
UNT012 IN PECR 24.0
END DESCRIPTION:
XS GIS Cut Line= 3
      2330887.72     13259796.86      2330737.72     13260096.85
      2330687.71     13260446.90
#Sta/Elev= 30
  4653.9  187.26  4676.3  185.68  4690.2  185.31  4712.6  183.63  4721.0  182.72
  4734.9  182.21  4765.7  179.48  4779.7  178.79  4788.1  177.77  4791.6  177.63
  4908.2  173.26  4958.6  171.96  4975.3  171.13  4986.5  169.88  4991.8  169.88
  4996.4  168.80  4999.2  168.30  5002.4  168.80  5009.5  169.06  5029.7  172.67
  5039.8  173.43  5130.7  177.66  5161.0  178.54  5181.2  179.62  5191.3  180.51
  5211.5  181.31  5221.6  181.39  5276.4  184.25  5312.5  185.99  5342.9  186.60
#Mann=5,-1,0
  4653.9    0.05       0  4791.6     0.1       0  4996.4    0.07       0
  5002.4     0.1       0  5276.4    0.05       0
Bank Sta=4996.4,5002.4
Exp/Cntr=0.3,0.1

Type RM Length L Ch R = 1,10900,382,382,382
BEGIN DESCRIPTION:
UNT012 IN PECR 23.0
END DESCRIPTION:
XS GIS Cut Line= 3
      2330787.75     13259746.85      2330387.72     13259796.85
      2330137.72     13259896.86
#Sta/Elev= 30
  4616.5  183.50  4633.0  182.05  4659.4  180.63  4677.0  178.79  4697.2  177.57
  4766.9  175.36  4816.3  173.64  4959.2  168.89  4969.3  167.62  4981.8  166.95
  4985.5  164.33  4986.4  163.69  4989.2  163.19  4992.4  163.69  4999.5  163.89
  5009.6  166.66  5022.3  167.23  5029.1  169.07  5033.4  169.16  5052.0  169.44
  5058.7  168.87  5064.1  170.65  5073.5  171.54  5105.8  172.92  5112.5  172.70
  5171.8  175.91  5249.9  179.17  5267.4  180.87  5274.1  182.09  5288.9  182.65
#Mann=8,-1,0
  4616.5    0.05       0  4633.0     0.1       0  4766.9    0.05       0
  4816.3     0.1       0  4985.5    0.16       0  4986.4    0.07       0
  4992.4    0.16       0  5033.4     0.1       0
Bank Sta=4986.4,4992.4
Exp/Cntr=0.3,0.1

Type RM Length L Ch R = 1,10518,357,357,357
BEGIN DESCRIPTION:
UNT012 IN PECR 22.0
END DESCRIPTION:
XS GIS Cut Line= 3
      2330667.72     13259423.45      2330424.40     13259436.49
      2329807.41     13259584.22
#Sta/Elev= 30
  4494.6  181.78  4604.8  177.97  4626.5  176.32  4811.7  169.97  4919.9  166.79
  4961.3  166.42  4976.3  165.34  4981.6  163.64  4985.1  163.38  4999.2  161.62
  5002.0  161.12  5005.2  161.62  5012.5  163.03  5053.6  165.25  5060.4  166.16
  5065.5  167.59  5102.4  168.75  5149.6  171.51  5156.4  173.34  5177.0  175.65
  5186.5  176.51  5191.6  176.16  5197.6  177.31  5218.1  179.09  5228.4  179.10
  5233.6  180.05  5259.3  180.72  5310.7  183.65  5322.9  183.18  5372.7  185.56
#Mann=7,-1,0
  4494.6     0.1       0  4626.5    0.05       0  4811.7     0.1       0
  4961.3    0.16       0  4985.1     0.1       0  4999.2    0.07       0
  5005.2     0.1       0
Bank Sta=4999.2,5005.2
Exp/Cntr=0.3,0.1

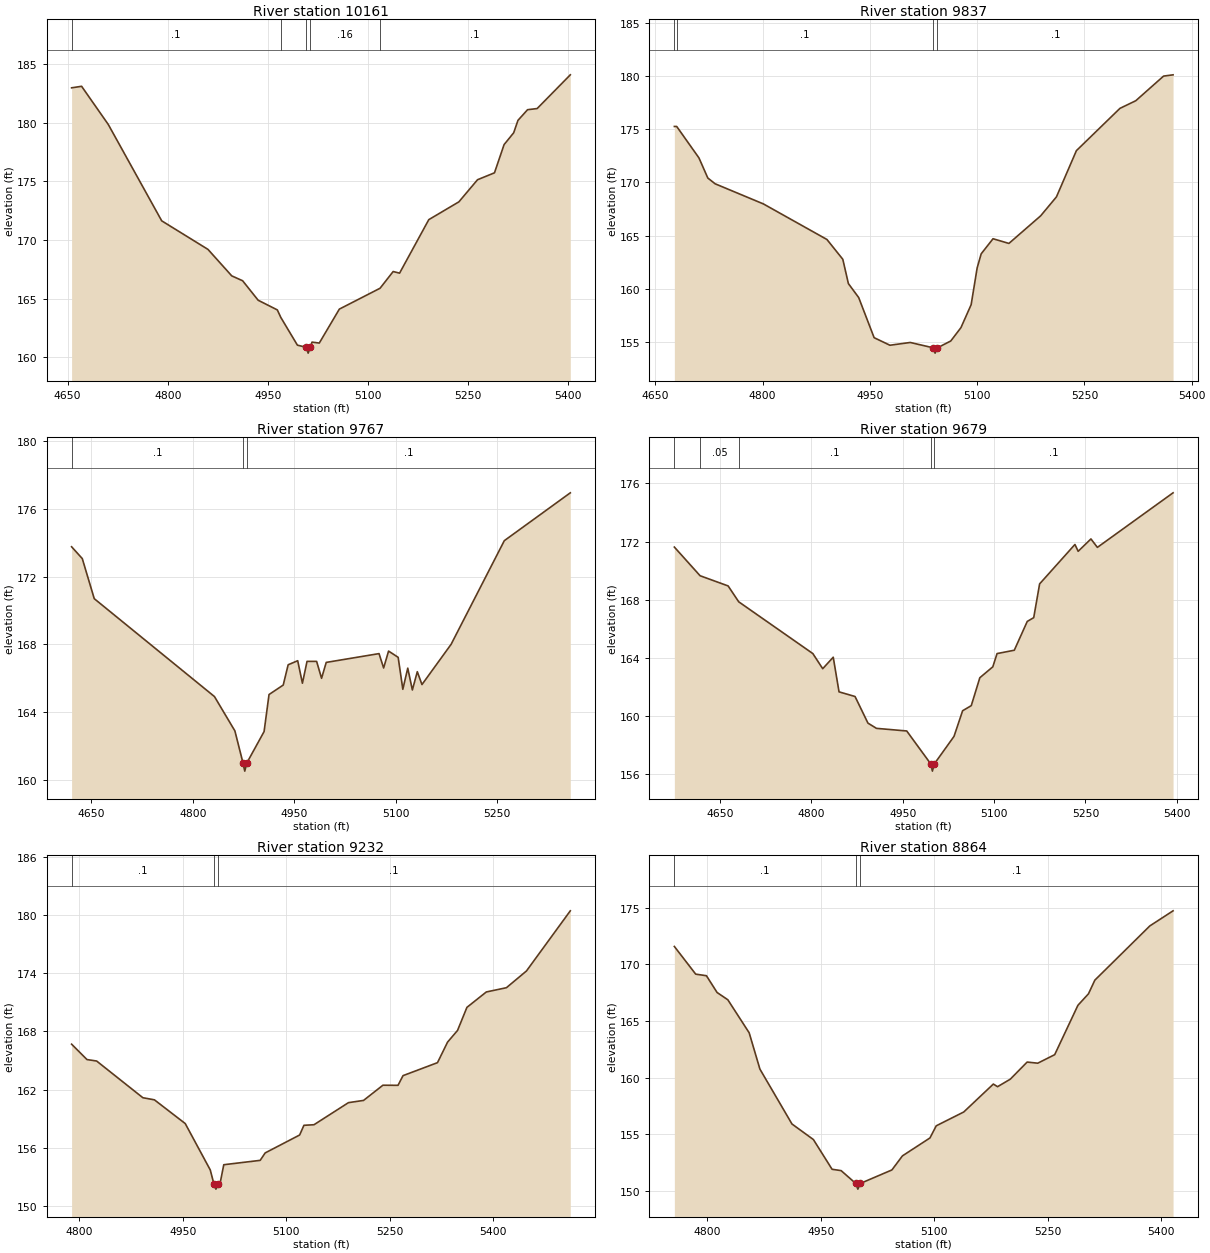
Type RM Length L Ch R = 1,10161,324,324,324
BEGIN DESCRIPTION:
UNT012 IN PECR 21.0
END DESCRIPTION:
XS GIS Cut Line= 4
      2330402.67     13259093.21      2330220.17     13259101.90
      2329829.10     13259275.71      2329743.43     13259382.80
#Sta/Elev= 30
  4655.9  183.00  4670.9  183.13  4710.9  179.87  4791.0  171.64  4860.4  169.20
  4896.0  166.94  4912.4  166.52  4935.6  164.86  4964.4  164.03  4969.6  163.39
  4994.5  161.02  5007.9  160.84  5010.6  160.34  5013.9  160.84  5016.4  161.28
  5027.3  161.20  5057.4  164.10  5118.4  165.88  5138.1  167.31  5147.7  167.17
  5191.5  171.74  5236.6  173.26  5264.6  175.15  5290.0  175.74  5304.4  178.15
  5318.8  179.16  5325.2  180.22  5339.6  181.13  5354.0  181.23  5403.7  184.11
#Mann=5,-1,0
  4655.9     0.1       0  4969.6    0.16       0  5007.9    0.07       0
  5013.9    0.16       0  5118.4     0.1       0
Bank Sta=5007.9,5013.9
Exp/Cntr=0.3,0.1

Type RM Length L Ch R = 1,9837,70,70,70
BEGIN DESCRIPTION:
Mapping XS 03f8488b
END DESCRIPTION:
XS GIS Cut Line= 4
      2330159.86     13258765.04      2329903.81     13258888.73
      2329821.34     13258979.87      2329688.95     13259238.14
#Sta/Elev= 30
  4676.5  175.25  4679.8  175.25  4710.9  172.30  4723.3  170.41  4733.5  169.87
  4801.0  167.98  4889.9  164.64  4912.1  162.78  4919.9  160.50  4934.3  159.19
  4955.9  155.42  4978.0  154.71  5006.4  154.97  5038.5  154.47  5041.2  153.97
  5044.5  154.47  5063.1  155.11  5077.3  156.36  5091.6  158.52  5100.0  161.97
  5105.6  163.29  5122.2  164.71  5144.4  164.27  5188.8  166.86  5210.9  168.64
  5238.8  172.98  5299.7  176.95  5321.9  177.67  5360.7  179.98  5374.0  180.10
#Mann=4,-1,0
  4676.5    0.05       0  4679.8     0.1       0  5038.5    0.07       0
  5044.5     0.1       0
Bank Sta=5038.5,5044.5
Exp/Cntr=0.3,0.1

Type RM Length L Ch R = 1,9767,88,88,88
BEGIN DESCRIPTION:
UNT012 IN PECR 20.0
END DESCRIPTION:
XS GIS Cut Line= 4
      2330149.07     13258686.89      2329916.12     13258774.56
      2329703.73     13259000.78      2329643.39     13259168.67
#Sta/Elev= 30
  4620.8  173.77  4636.6  173.07  4654.3  170.70  4832.1  164.91  4862.3  162.88
  4874.2  161.00  4876.9  160.50  4880.2  161.00  4905.5  162.84  4912.8  165.03
  4933.8  165.59  4941.1  166.79  4955.2  167.03  4962.2  165.70  4969.0  166.99
  4983.2  166.99  4990.5  165.99  4997.4  166.93  5075.5  167.45  5082.3  166.60
  5089.6  167.60  5103.8  167.23  5110.7  165.34  5118.0  166.59  5124.8  165.30
  5132.1  166.38  5139.0  165.62  5182.1  168.00  5260.8  174.13  5358.4  176.96
#Mann=3,-1,0
  4620.8     0.1       0  4874.2    0.07       0  4880.2     0.1       0
Bank Sta=4874.2,4880.2
Exp/Cntr=0.3,0.1

Type RM Length L Ch R = 1,9679,447,447,447
BEGIN DESCRIPTION:
Mapping XS 967822c7
END DESCRIPTION:
XS GIS Cut Line= 4
      2330131.65     13258628.32      2329871.25     13258704.26
      2329645.56     13258923.45      2329571.77     13259144.82
#Sta/Elev= 30
  4574.8  171.62  4617.1  169.65  4663.1  168.95  4680.5  167.86  4802.3  164.30
  4818.5  163.26  4835.8  164.05  4845.3  161.67  4871.6  161.35  4892.8  159.52
  4906.8  159.16  4956.5  158.98  4995.9  156.72  4998.7  156.22  5001.9  156.72
  5034.2  158.61  5048.3  160.37  5062.5  160.72  5076.6  162.64  5097.9  163.39
  5104.9  164.30  5133.2  164.53  5154.5  166.51  5165.1  166.77  5174.8  169.09
  5232.8  171.80  5238.1  171.33  5259.1  172.18  5269.7  171.60  5394.0  175.35
#Mann=5,-1,0
  4574.8     0.1       0  4617.1    0.05       0  4680.5     0.1       0
  4995.9    0.07       0  5001.9     0.1       0
Bank Sta=4995.9,5001.9
Exp/Cntr=0.3,0.1

Type RM Length L Ch R = 1,9232,368,368,368
BEGIN DESCRIPTION:
UNT012 IN PECR 19.0
END DESCRIPTION:
XS GIS Cut Line= 3
      2329637.71     13258246.88      2329537.72     13258446.85
      2329237.71     13258846.87
#Sta/Elev= 30
  4788.6  166.69  4810.9  165.10  4824.9  164.95  4892.0  161.16  4908.8  160.94
  4953.5  158.49  4989.8  153.70  4995.2  152.22  4998.0  151.72  5001.2  152.22
  5003.8  152.23  5009.4  154.24  5062.2  154.69  5069.5  155.46  5119.5  157.31
  5125.7  158.31  5140.3  158.37  5190.3  160.65  5212.2  160.88  5240.3  162.45
  5262.2  162.44  5269.5  163.44  5319.5  164.78  5334.1  166.90  5348.6  168.11
  5362.2  170.49  5390.3  172.08  5419.5  172.52  5448.6  174.25  5512.2  180.46
#Mann=3,-1,0
  4788.6     0.1       0  4995.2    0.07       0  5001.2     0.1       0
Bank Sta=4995.2,5001.2
Exp/Cntr=0.3,0.1

Type RM Length L Ch R = 1,8864,263,263,263
BEGIN DESCRIPTION:
UNT012 IN PECR 18.0
END DESCRIPTION:
XS GIS Cut Line= 3
      2329387.69     13258096.89      2329237.72     13258246.85
      2329037.72     13258646.86
#Sta/Elev= 30
  4756.4  171.57  4784.6  169.13  4798.8  168.99  4812.9  167.51  4827.1  166.87
  4855.3  163.96  4869.5  160.76  4911.9  155.92  4940.2  154.55  4964.9  151.93
  4976.9  151.81  4996.2  150.68  4999.0  150.18  5002.2  150.68  5044.0  151.87
  5057.9  153.11  5094.3  154.69  5102.6  155.76  5139.0  156.98  5178.1  159.44
  5183.7  159.21  5200.5  159.87  5222.8  161.38  5236.8  161.28  5259.2  162.03
  5289.9  166.38  5303.9  167.40  5312.3  168.60  5385.0  173.38  5415.7  174.71
#Mann=3,-1,0
  4756.4     0.1       0  4996.2    0.07       0  5002.2     0.1       0
Bank Sta=4996.2,5002.2
Exp/Cntr=0.3,0.1

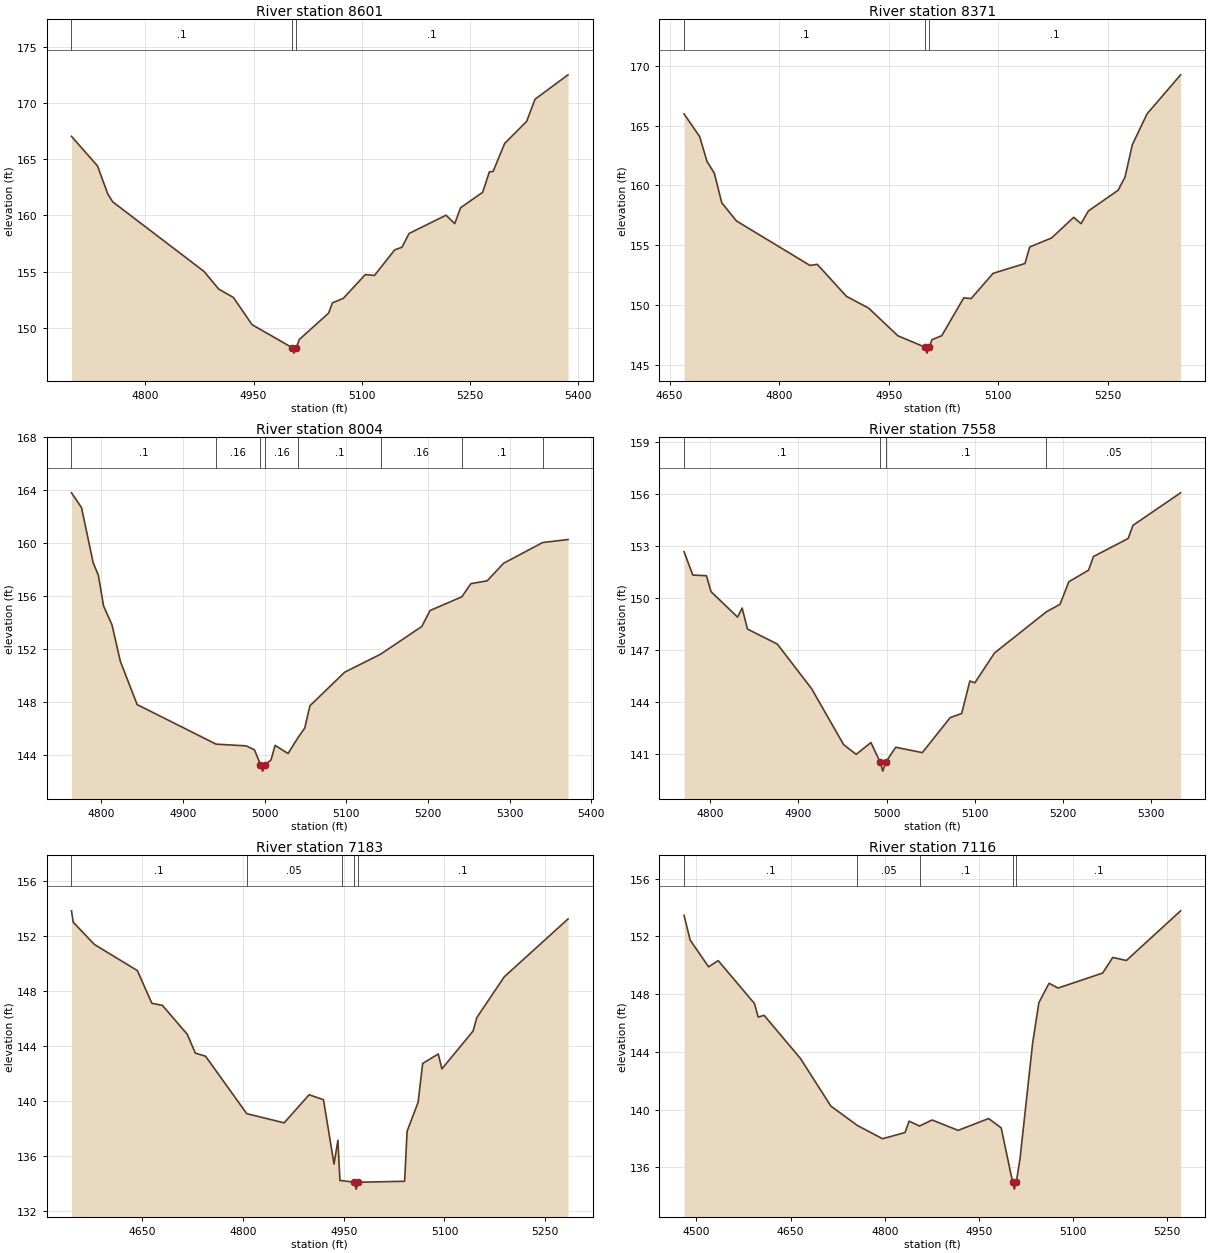
Type RM Length L Ch R = 1,8601,230,230,230
BEGIN DESCRIPTION:
Mapping XS 1ac3cb5a
END DESCRIPTION:
XS GIS Cut Line= 3
      2329107.82     13257946.04      2328999.16     13258063.39
      2328903.84     13258583.30
#Sta/Elev= 30
  4697.5  167.05  4733.6  164.41  4747.7  161.93  4754.5  161.22  4881.3  155.01
  4901.6  153.44  4922.0  152.69  4948.0  150.26  5003.2  148.23  5006.0  147.73
  5009.2  148.23  5013.5  148.95  5054.1  151.30  5059.3  152.21  5074.4  152.61
  5104.9  154.73  5117.6  154.65  5145.6  156.93  5155.8  157.17  5165.6  158.39
  5216.8  160.02  5228.9  159.27  5237.1  160.69  5267.6  162.06  5277.0  163.89
  5282.1  163.92  5298.1  166.41  5328.6  168.38  5340.3  170.36  5386.0  172.53
#Mann=3,-1,0
  4697.5     0.1       0  5003.2    0.07       0  5009.2     0.1       0
Bank Sta=5003.2,5009.2
Exp/Cntr=0.3,0.1

Type RM Length L Ch R = 1,8371,367,367,367
BEGIN DESCRIPTION:
UNT012 IN PECR 17.0
END DESCRIPTION:
XS GIS Cut Line= 3
      2328751.48     13257815.68      2328768.86     13257954.76
      2328725.47     13258492.75
#Sta/Elev= 30
  4669.8  165.97  4691.1  164.09  4701.2  162.01  4711.3  161.01  4721.4  158.55
  4741.5  157.03  4842.2  153.31  4852.2  153.40  4892.3  150.72  4922.4  149.75
  4962.6  147.43  4999.7  146.48  5002.4  145.98  5005.7  146.48  5009.2  147.10
  5022.7  147.44  5052.8  150.60  5062.9  150.54  5093.0  152.65  5136.6  153.47
  5143.1  154.85  5173.2  155.61  5203.3  157.33  5213.4  156.80  5223.4  157.86
  5264.1  159.59  5273.6  160.69  5283.6  163.39  5303.7  165.97  5349.7  169.24
#Mann=3,-1,0
  4669.8     0.1       0  4999.7    0.07       0  5005.7     0.1       0
Bank Sta=4999.7,5005.7
Exp/Cntr=0.3,0.1

Type RM Length L Ch R = 1,8004,446,446,446
BEGIN DESCRIPTION:
UNT012 IN PECR 16.0
END DESCRIPTION:
XS GIS Cut Line= 4
      2328493.16     13257775.55      2328471.43     13257801.62
      2328384.63     13258174.88      2328384.63     13258365.82
#Sta/Elev= 30
  4763.4  163.80  4775.7  162.68  4790.0  158.50  4796.3  157.57  4802.7  155.24
  4813.0  153.82  4823.2  151.07  4843.8  147.79  4940.5  144.80  4977.3  144.67
  4987.5  144.37  4994.8  143.26  4997.5  142.76  5000.8  143.26  5007.7  143.60
  5012.8  144.71  5028.6  144.09  5041.2  145.33  5049.1  146.02  5055.4  147.70
  5098.0  150.24  5142.0  151.60  5192.5  153.70  5202.5  154.90  5241.5  155.94
  5252.5  156.93  5272.5  157.15  5292.5  158.47  5340.3  160.04  5371.5  160.27
#Mann=8,-1,0
  4763.4     0.1       0  4940.5    0.16       0  4994.8    0.07       0
  5000.8    0.16       0  5041.2     0.1       0  5142.0    0.16       0
  5241.5     0.1       0  5340.3    0.05       0
Bank Sta=4994.8,5000.8
Exp/Cntr=0.3,0.1

Type RM Length L Ch R = 1,7558,375,375,375
BEGIN DESCRIPTION:
UNT012 IN PECR 15.0
END DESCRIPTION:
XS GIS Cut Line= 3
      2328059.11     13257797.25      2328033.07     13257897.11
      2328237.05     13258309.41
#Sta/Elev= 30
  4770.3  152.67  4780.2  151.32  4795.7  151.28  4800.9  150.36  4831.0  148.89
  4836.2  149.41  4842.2  148.20  4876.1  147.33  4915.0  144.75  4951.3  141.52
  4965.5  140.96  4982.3  141.64  4992.9  140.49  4995.7  139.99  4998.9  140.49
  5010.4  141.37  5040.6  141.06  5072.1  143.08  5085.2  143.32  5094.5  145.20
  5100.1  145.09  5122.5  146.82  5181.4  149.20  5196.8  149.63  5206.7  150.93
  5229.1  151.60  5234.7  152.39  5274.0  153.43  5279.5  154.19  5333.5  156.07
#Mann=4,-1,0
  4770.3     0.1       0  4992.9    0.07       0  4998.9     0.1       0
  5181.4    0.05       0
Bank Sta=4992.9,4998.9
Exp/Cntr=0.3,0.1

Type RM Length L Ch R = 1,7183,67,67,67
BEGIN DESCRIPTION:
Mapping XS ecea2e8a
END DESCRIPTION:
XS GIS Cut Line= 4
      2327952.83     13257727.73      2327749.73     13258073.19
      2327749.73     13258165.20      2327850.42     13258390.91
#Sta/Elev= 30
  4544.2  153.81  4546.7  152.99  4578.0  151.38  4642.4  149.47  4663.9  147.10
  4679.6  146.95  4716.7  144.85  4728.8  143.48  4744.0  143.26  4805.3  139.09
  4861.1  138.42  4898.3  140.46  4919.7  140.10  4935.4  135.43  4941.2  137.16
  4944.2  134.23  4946.6  134.23  4965.6  134.11  4968.4  133.61  4971.6  134.11
  5040.6  134.18  5044.3  137.81  5060.7  139.91  5067.5  142.73  5090.7  143.42
  5096.2  142.34  5142.6  145.08  5148.3  146.07  5189.1  149.02  5284.1  153.22
#Mann=5,-1,0
  4544.2     0.1       0  4805.3    0.05       0  4946.6     0.1       0
  4965.6    0.07       0  4971.6     0.1       0
Bank Sta=4965.6,4971.6
Exp/Cntr=0.3,0.1

Type RM Length L Ch R = 1,7116,44,44,44
BEGIN DESCRIPTION:
UNT012 IN PECR 14.0
END DESCRIPTION:
XS GIS Cut Line= 4
      2327923.35     13257708.58      2327690.70     13258080.13
      2327694.17     13258224.23      2327794.88     13258406.54
#Sta/Elev= 30
  4480.4  153.45  4490.2  151.74  4519.5  149.89  4534.8  150.32  4592.5  147.35
  4598.4  146.41  4607.9  146.53  4665.6  143.55  4714.3  140.24  4756.5  138.90
  4796.5  137.98  4832.3  138.41  4838.9  139.20  4855.4  138.86  4875.5  139.28
  4916.9  138.56  4965.5  139.38  4985.5  138.73  5003.6  134.99  5006.4  134.49
  5009.6  134.99  5015.5  136.61  5035.5  144.58  5045.5  147.41  5061.7  148.75
  5076.1  148.42  5147.1  149.46  5163.2  150.54  5184.9  150.33  5271.2  153.77
#Mann=5,-1,0
  4480.4     0.1       0  4756.5    0.05       0  4855.4     0.1       0
  5003.6    0.07       0  5009.6     0.1       0
Bank Sta=5003.6,5009.6
Exp/Cntr=0.3,0.1