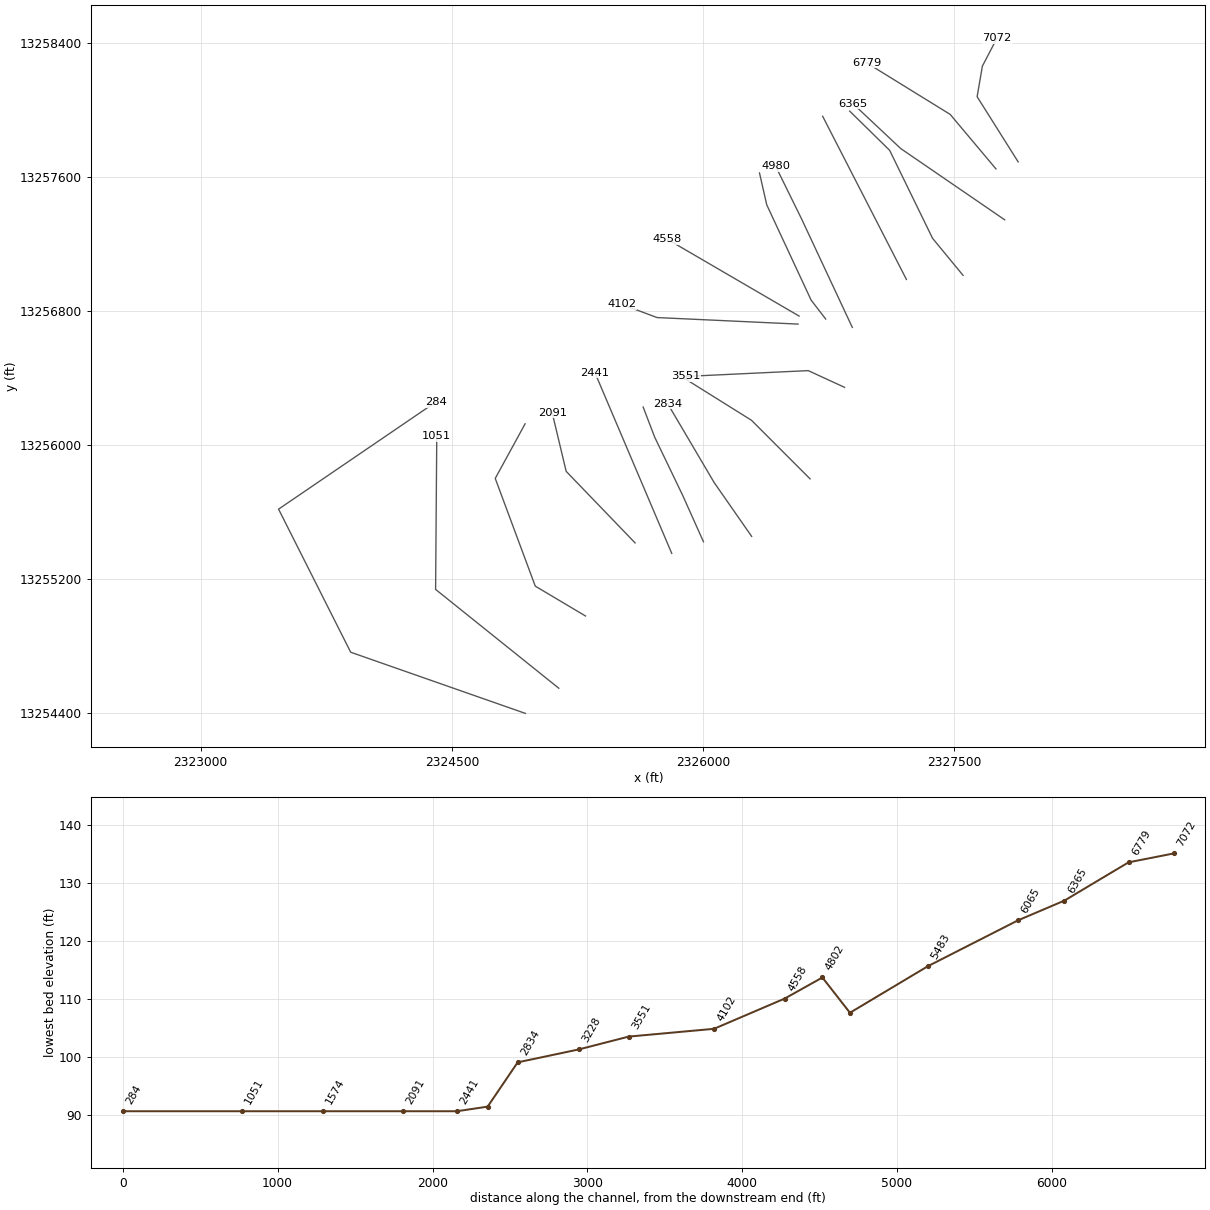
HEC-RAS study UNT012 IN PECR.prj: UNT012 IN PECR Base Level Engineering

--- UNT012 IN PECR.g01 (geometry) --- (continued)

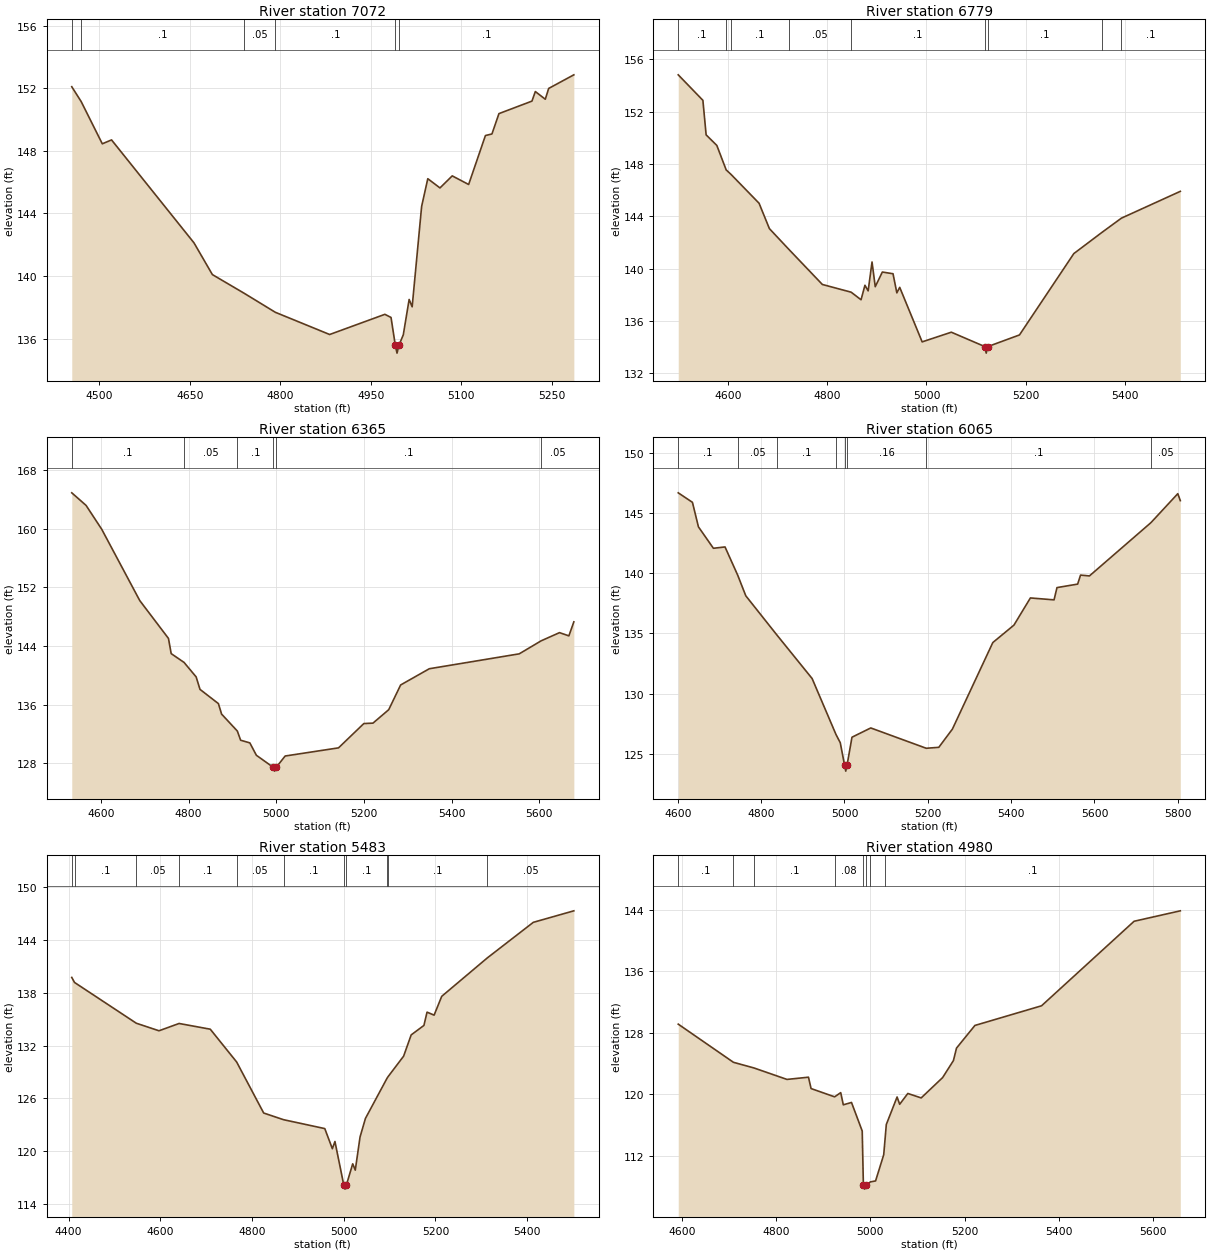
Type RM Length L Ch R = 1,7072,293,293,293
BEGIN DESCRIPTION:
Mapping XS ec266808
END DESCRIPTION:
XS GIS Cut Line= 4
      2327879.94     13257689.50      2327635.14     13258078.40
      2327666.39     13258260.69      2327752.97     13258426.92
#Sta/Elev= 30
  4454.5  152.10  4470.1  151.15  4505.1  148.45  4520.4  148.70  4657.0  142.12
  4687.5  140.09  4740.0  138.90  4791.8  137.68  4881.8  136.26  4973.3  137.55
  4983.5  137.35  4990.6  135.57  4993.4  135.07  4996.6  135.57  5003.8  136.24
  5013.5  138.50  5018.5  138.03  5034.2  144.45  5044.4  146.22  5064.6  145.63
  5084.9  146.40  5112.1  145.85  5139.9  148.98  5150.7  149.08  5162.3  150.38
  5217.0  151.18  5222.6  151.79  5239.1  151.30  5244.7  151.99  5286.4  152.86
#Mann=6,-1,0
  4454.5    0.16       0  4470.1     0.1       0  4740.0    0.05       0
  4791.8     0.1       0  4990.6    0.07       0  4996.6     0.1       0
Bank Sta=4990.6,4996.6
Exp/Cntr=0.3,0.1

Type RM Length L Ch R = 1,6779,414,414,414
BEGIN DESCRIPTION:
UNT012 IN PECR 13.0
END DESCRIPTION:
XS GIS Cut Line= 3
      2327747.65     13257647.31      2327474.21     13257972.84
      2326975.11     13258280.98
#Sta/Elev= 30
  4499.8  154.81  4549.5  152.86  4556.0  150.22  4577.6  149.41  4596.4  147.54
  4605.8  147.21  4662.7  144.99  4683.5  143.05  4722.3  141.48  4790.2  138.78
  4848.2  138.19  4868.2  137.61  4876.0  138.72  4882.5  138.29  4890.3  140.50
  4896.8  138.61  4911.1  139.73  4932.6  139.60  4940.3  138.14  4946.1  138.56
  4991.3  134.39  5050.1  135.13  5117.6  134.03  5120.4  133.53  5123.6  134.03
  5187.4  134.92  5296.9  141.14  5353.9  142.77  5392.8  143.85  5511.5  145.90
#Mann=9,-1,0
  4499.8     0.1       0  4596.4    0.16       0  4605.8     0.1       0
  4722.3    0.05       0  4848.2     0.1       0  5117.6    0.07       0
  5123.6     0.1       0  5353.9    0.05       0  5392.8     0.1       0
Bank Sta=5117.6,5123.6
Exp/Cntr=0.3,0.1

Type RM Length L Ch R = 1,6365,300,300,300
BEGIN DESCRIPTION:
UNT012 IN PECR 12.0
END DESCRIPTION:
XS GIS Cut Line= 3
      2327799.69     13257343.52      2327179.07     13257768.85
      2326892.69     13258037.87
#Sta/Elev= 30
  4533.3  164.87  4565.9  163.16  4601.7  159.90  4688.4  150.19  4753.9  145.03
  4760.1  142.96  4789.5  141.76  4817.0  139.79  4825.8  138.09  4867.8  136.15
  4875.1  134.72  4911.0  132.41  4918.5  131.16  4939.5  130.80  4954.4  129.11
  4993.4  127.45  4996.1  126.95  4999.4  127.45  5020.1  129.01  5141.8  130.12
  5199.5  133.43  5220.4  133.49  5256.3  135.32  5283.5  138.69  5348.9  140.90
  5554.0  142.93  5603.9  144.70  5645.9  145.82  5667.3  145.38  5678.6  147.29
#Mann=6,-1,0
  4533.3     0.1       0  4789.5    0.05       0  4911.0     0.1       0
  4993.4    0.07       0  4999.4     0.1       0  5603.9    0.05       0
Bank Sta=4993.4,4999.4
Exp/Cntr=0.3,0.1

Type RM Length L Ch R = 1,6065,582,582,582
BEGIN DESCRIPTION:
UNT012 IN PECR 11.0
END DESCRIPTION:
XS GIS Cut Line= 4
      2327551.27     13257011.72      2327369.00     13257233.04
      2327112.93     13257758.22      2326874.59     13257992.22
#Sta/Elev= 30
  4601.0  146.69  4635.1  145.90  4649.5  143.86  4685.4  142.08  4713.3  142.19
  4743.9  139.83  4763.1  138.13  4838.0  134.86  4922.3  131.25  4979.7  126.59
  4989.9  125.91  5000.2  124.05  5003.0  123.55  5006.2  124.05  5018.0  126.37
  5063.1  127.14  5196.3  125.45  5226.4  125.53  5259.1  127.05  5356.0  134.24
  5406.7  135.69  5446.2  137.95  5503.0  137.79  5510.0  138.81  5559.6  139.10
  5566.6  139.85  5587.9  139.78  5735.5  144.21  5800.0  146.62  5806.0  146.04
#Mann=8,-1,0
  4601.0     0.1       0  4743.9    0.05       0  4838.0     0.1       0
  4979.7    0.16       0  5000.2    0.07       0  5006.2    0.16       0
  5196.3     0.1       0  5735.5    0.05       0
Bank Sta=5000.2,5006.2
Exp/Cntr=0.3,0.1

Type RM Length L Ch R = 1,5483,503,503,503
BEGIN DESCRIPTION:
UNT012 IN PECR 10.0
END DESCRIPTION:
XS GIS Cut Line= 2
      2327212.90     13256987.63      2326712.90     13257961.59
#Sta/Elev= 30
  4406.9  139.75  4412.9  139.18  4547.6  134.54  4597.1  133.68  4640.9  134.51
  4708.9  133.86  4766.4  130.13  4825.4  124.32  4868.8  123.56  4958.6  122.55
  4975.1  120.26  4980.8  121.08  4999.9  116.16  5002.7  115.66  5005.9  116.16
  5019.5  118.54  5025.1  117.82  5035.5  121.59  5047.3  123.71  5094.5  128.29
  5096.8  128.47  5130.5  130.79  5147.0  133.21  5174.8  134.29  5181.6  135.80
  5197.0  135.46  5213.6  137.60  5313.2  141.98  5413.3  146.02  5501.7  147.33
#Mann=11,-1,0
  4406.9    0.05       0  4412.9     0.1       0  4547.6    0.05       0
  4640.9     0.1       0  4766.4    0.05       0  4868.8     0.1       0
  4999.9    0.07       0  5005.9     0.1       0  5094.5    0.05       0
  5096.8     0.1       0  5313.2    0.05       0
Bank Sta=4999.9,5005.9
Exp/Cntr=0.3,0.1

Type RM Length L Ch R = 1,4980,178,178,178
BEGIN DESCRIPTION:
Mapping XS cbbce92f
END DESCRIPTION:
XS GIS Cut Line= 3
      2326890.00     13256701.14      2326587.92     13257346.97
      2326431.69     13257664.64
#Sta/Elev= 30
  4591.6  129.14  4708.9  124.17  4752.7  123.43  4822.7  121.94  4868.4  122.23
  4873.9  120.75  4924.0  119.67  4936.9  120.22  4942.4  118.63  4959.8  118.94
  4982.6  115.22  4985.1  108.15  4987.9  107.65  4991.1  108.15  4999.9  108.59
  5011.0  108.72  5028.3  112.13  5031.6  114.49  5033.8  116.07  5056.7  119.65
  5062.2  118.70  5079.5  120.11  5107.9  119.53  5153.5  122.18  5176.4  124.39
  5183.0  126.02  5222.1  128.97  5363.7  131.53  5560.4  142.54  5658.6  143.90
#Mann=8,-1,0
  4591.6     0.1       0  4708.9    0.08       0  4752.7     0.1       0
  4924.0    0.08       0  4985.1    0.07       0  4991.1    0.08       0
  4999.9    0.16       0  5031.6     0.1       0
Bank Sta=4985.1,4991.1
Exp/Cntr=0.3,0.1

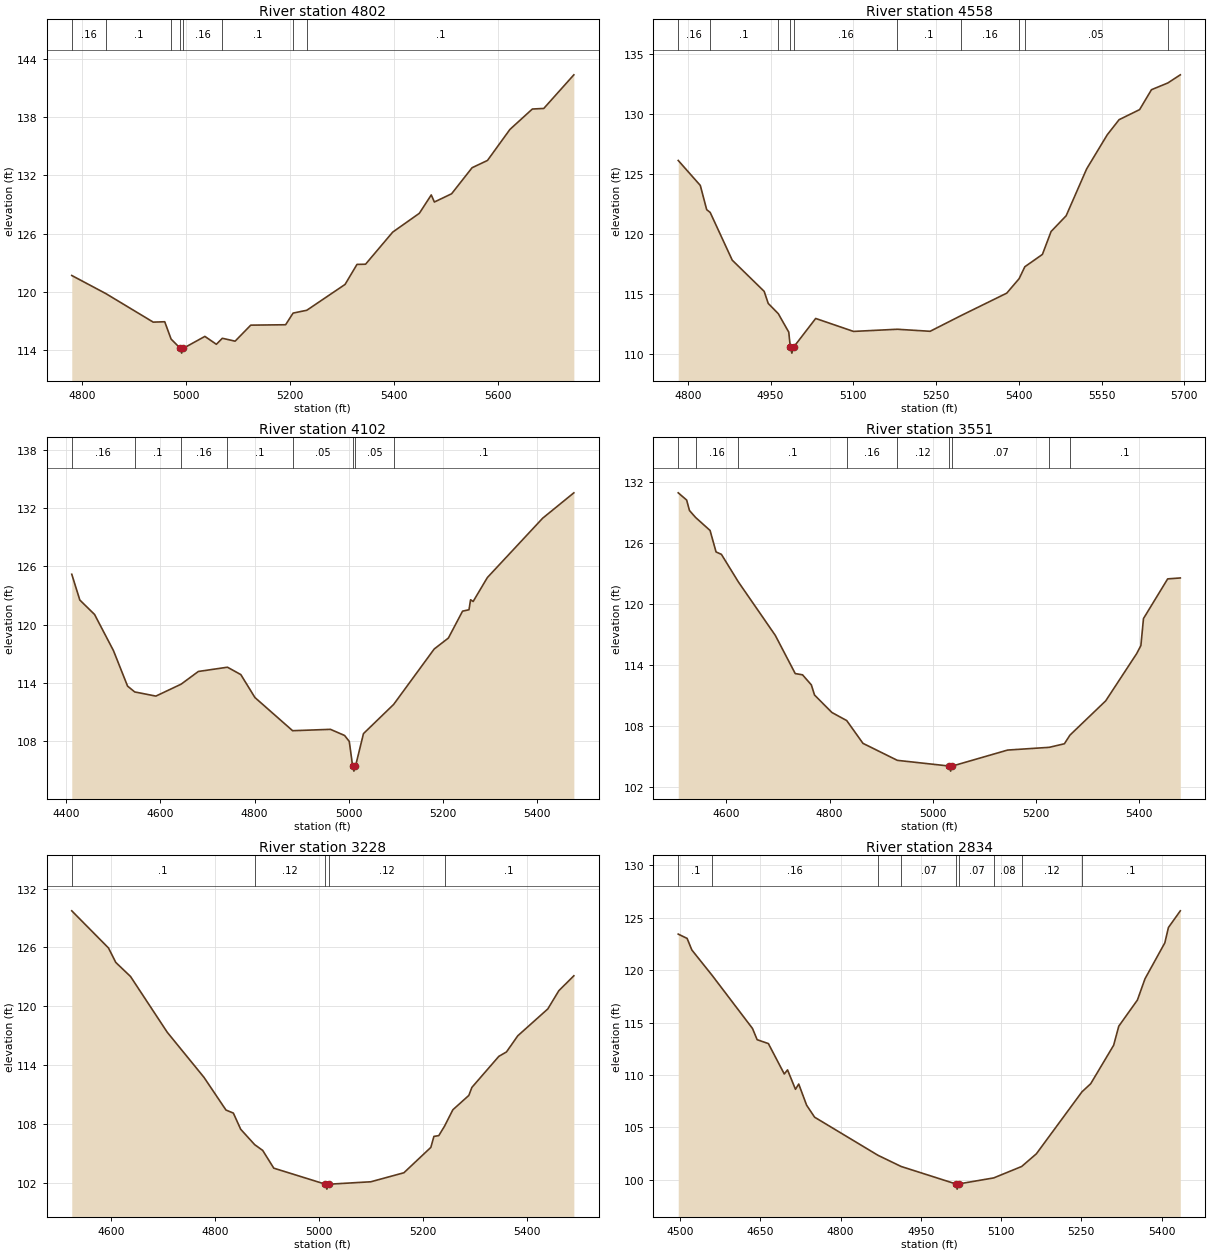
Type RM Length L Ch R = 1,4802,244,244,244
BEGIN DESCRIPTION:
Mapping XS 083c2703
END DESCRIPTION:
XS GIS Cut Line= 4
      2326730.95     13256751.12      2326644.04     13256864.11
      2326378.98     13257433.33      2326335.82     13257623.23
#Sta/Elev= 30
  4780.7  121.71  4846.1  119.85  4937.3  116.91  4959.4  116.95  4971.6  115.17
  4989.2  114.22  4991.9  113.72  4995.2  114.22  5036.6  115.44  5058.7  114.63
  5070.2  115.25  5094.7  114.95  5124.8  116.60  5191.8  116.64  5206.2  117.84
  5232.5  118.13  5306.1  120.79  5329.0  122.85  5345.5  122.87  5397.6  126.17
  5448.9  128.11  5471.8  130.00  5477.8  129.27  5510.9  130.12  5550.3  132.80
  5579.9  133.55  5623.0  136.74  5666.1  138.84  5688.1  138.90  5745.9  142.36
#Mann=8,-1,0
  4780.7    0.16       0  4846.1     0.1       0  4971.6    0.16       0
  4989.2    0.07       0  4995.2    0.16       0  5070.2     0.1       0
  5206.2    0.16       0  5232.5     0.1       0
Bank Sta=4989.2,4995.2
Exp/Cntr=0.3,0.1

Type RM Length L Ch R = 1,4558,456,456,456
BEGIN DESCRIPTION:
UNT012 IN PECR 9.0
END DESCRIPTION:
XS GIS Cut Line= 2
      2326572.30     13256768.85      2325785.81     13257227.20
#Sta/Elev= 30
  4782.5  126.15  4822.5  124.07  4834.1  122.05  4840.4  121.82  4880.4  117.84
  4938.3  115.24  4945.7  114.23  4963.9  113.38  4982.9  111.84  4985.7  110.59
  4988.5  110.09  4991.7  110.59  5031.7  112.98  5100.3  111.90  5179.7  112.08
  5239.2  111.91  5295.3  113.22  5378.1  115.09  5400.6  116.30  5410.9  117.29
  5442.8  118.32  5458.5  120.23  5485.8  121.54  5523.0  125.45  5560.3  128.29
  5581.8  129.55  5619.0  130.39  5640.5  132.05  5670.1  132.61  5692.8  133.29
#Mann=10,-1,0
  4782.5    0.16       0  4840.4     0.1       0  4963.9    0.16       0
  4985.7    0.07       0  4991.7    0.16       0  5179.7     0.1       0
  5295.3    0.16       0  5400.6     0.1       0  5410.9    0.05       0
  5670.1     0.1       0
Bank Sta=4985.7,4991.7
Exp/Cntr=0.3,0.1

Type RM Length L Ch R = 1,4102,551,551,551
BEGIN DESCRIPTION:
Mapping XS 923b8b66
END DESCRIPTION:
XS GIS Cut Line= 3
      2326566.03     13256720.89      2325724.04     13256759.95
      2325515.70     13256838.08
#Sta/Elev= 30
  4412.1  125.20  4429.2  122.54  4460.5  121.05  4500.5  117.33  4530.5  113.66
  4545.7  113.06  4590.6  112.63  4644.1  113.86  4680.7  115.17  4742.5  115.61
  4770.8  114.85  4800.8  112.48  4880.7  109.06  4961.0  109.20  4991.0  108.57
  5001.0  107.95  5008.1  105.39  5010.8  104.89  5014.1  105.39  5031.1  108.76
  5095.1  111.77  5181.2  117.49  5211.3  118.62  5241.3  121.39  5255.0  121.54
  5258.4  122.57  5263.8  122.39  5294.0  124.86  5411.3  130.98  5477.5  133.60
#Mann=8,-1,0
  4412.1    0.16       0  4545.7     0.1       0  4644.1    0.16       0
  4742.5     0.1       0  4880.7    0.05       0  5008.1   0.035       0
  5014.1    0.05       0  5095.1     0.1       0
Bank Sta=5008.1,5014.1
Exp/Cntr=0.3,0.1

Type RM Length L Ch R = 1,3551,323,323,323
BEGIN DESCRIPTION:
UNT012 IN PECR 8.0
END DESCRIPTION:
XS GIS Cut Line= 3
      2326843.81     13256343.30      2326626.82     13256443.11
      2325893.28     13256408.39
#Sta/Elev= 30
  4506.7  130.91  4523.0  130.20  4528.5  129.17  4540.5  128.48  4568.4  127.21
  4580.0  125.10  4590.4  124.86  4623.3  122.15  4694.8  116.90  4733.5  113.14
  4747.6  113.02  4764.7  112.03  4770.9  111.03  4804.7  109.31  4833.3  108.52
  4864.8  106.28  4931.4  104.61  5032.0  104.05  5034.7  103.55  5038.0  104.05
  5145.1  105.62  5225.9  105.89  5255.2  106.24  5266.0  107.09  5335.3  110.46
  5395.4  115.11  5403.5  115.90  5408.5  118.55  5455.4  122.45  5479.9  122.54
#Mann=9,-1,0
  4506.7     0.1       0  4540.5    0.16       0  4623.3     0.1       0
  4833.3    0.16       0  4931.4    0.12       0  5032.0    0.07       0
  5038.0    0.07       0  5225.9    0.05       0  5266.0     0.1       0
Bank Sta=5032,5038
Exp/Cntr=0.3,0.1

Type RM Length L Ch R = 1,3228,394,394,394
BEGIN DESCRIPTION:
UNT012 IN PECR 7.0
END DESCRIPTION:
XS GIS Cut Line= 3
      2326637.69     13255796.89      2326287.72     13256146.85
      2325887.74     13256396.84
#Sta/Elev= 30
  4523.6  129.74  4594.3  125.95  4608.4  124.47  4636.7  123.04  4707.4  117.35
  4778.1  112.75  4820.5  109.41  4834.7  109.10  4848.8  107.45  4875.7  105.88
  4891.2  105.29  4912.5  103.48  5012.0  101.84  5014.7  101.34  5018.0  101.84
  5099.3  102.09  5163.0  103.01  5214.9  105.60  5220.8  106.72  5230.2  106.80
  5241.2  107.76  5257.3  109.44  5288.0  110.90  5293.9  111.72  5345.8  114.89
  5360.5  115.34  5382.3  116.99  5440.1  119.73  5461.3  121.59  5490.2  123.11
#Mann=5,-1,0
  4523.6     0.1       0  4875.7    0.12       0  5012.0    0.07       0
  5018.0    0.12       0  5241.2     0.1       0
Bank Sta=5012,5018
Exp/Cntr=0.3,0.1

Type RM Length L Ch R = 1,2834,194,194,194
BEGIN DESCRIPTION:
Mapping XS 60e9d81a
END DESCRIPTION:
XS GIS Cut Line= 3
      2326288.95     13255453.51      2326065.18     13255774.86
      2325787.56     13256245.97
#Sta/Elev= 30
  4496.7  123.44  4513.3  123.03  4522.1  121.93  4560.6  119.47  4635.5  114.44
  4644.2  113.37  4665.2  113.00  4694.9  110.10  4701.0  110.49  4715.8  108.64
  4721.9  109.14  4736.7  107.12  4751.6  105.98  4869.9  102.35  4913.3  101.28
  5015.3   99.62  5018.0   99.12  5021.3   99.62  5086.4  100.19  5138.6  101.28
  5166.1  102.49  5251.3  108.40  5267.6  109.17  5310.5  112.84  5320.1  114.66
  5354.9  117.15  5369.1  119.18  5406.2  122.61  5412.9  124.07  5435.1  125.66
#Mann=9,-1,0
  4496.7     0.1       0  4560.6    0.16       0  4869.9    0.08       0
  4913.3    0.07       0  5015.3    0.07       0  5021.3    0.07       0
  5086.4    0.08       0  5138.6    0.12       0  5251.3     0.1       0
Bank Sta=5015.3,5021.3
Exp/Cntr=0.3,0.1

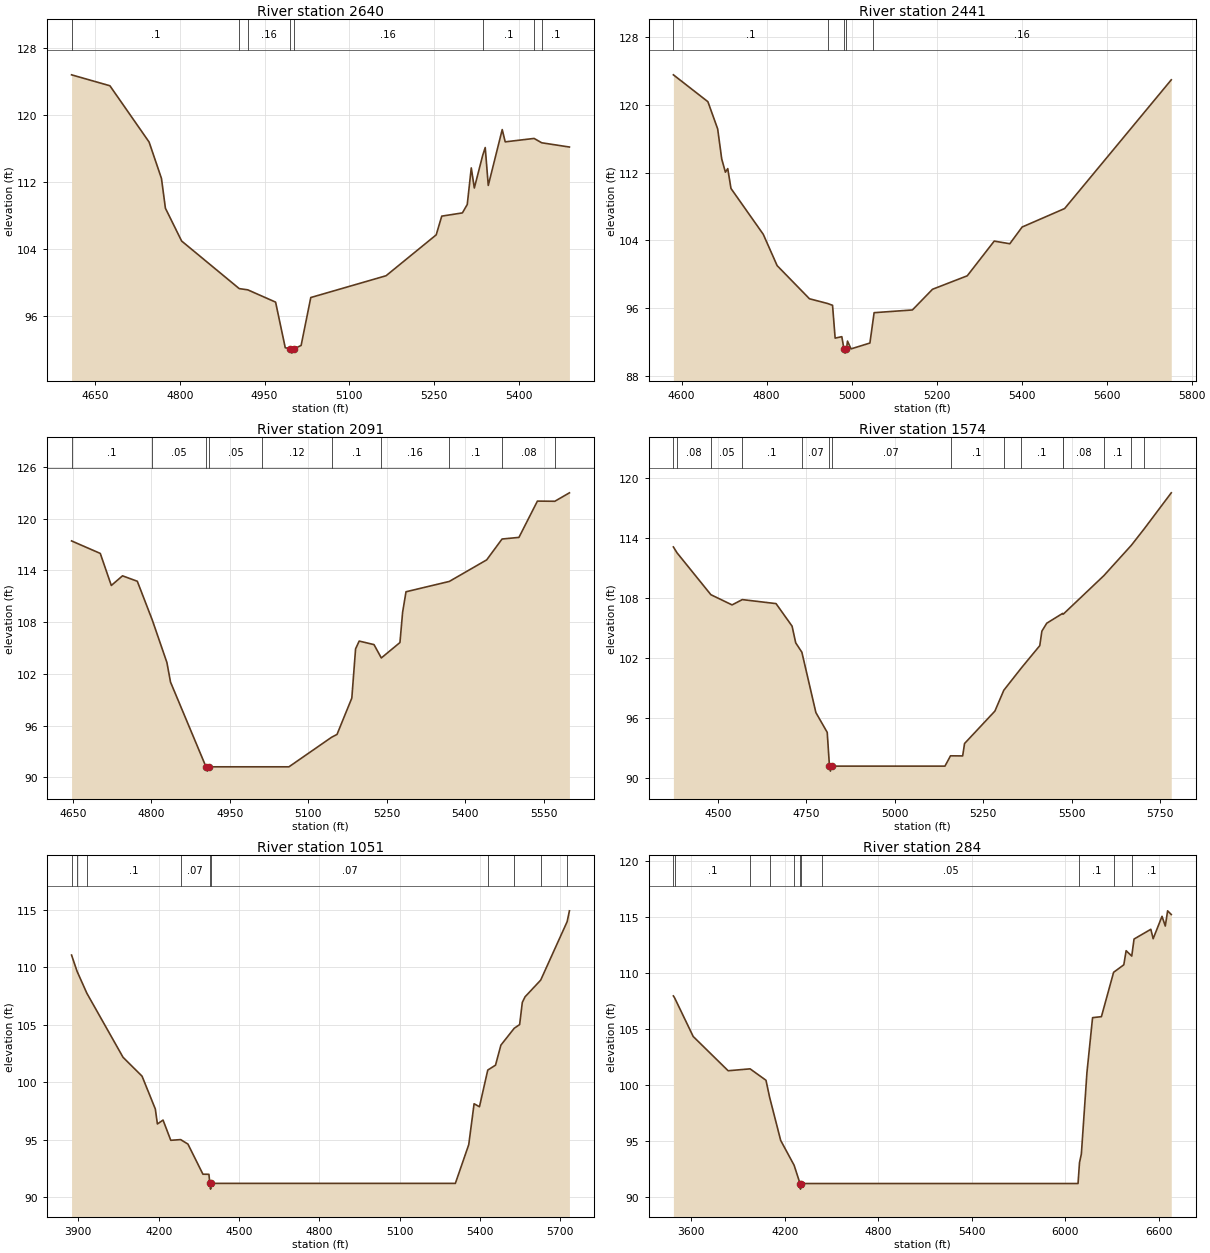
Type RM Length L Ch R = 1,2640,199,199,199
BEGIN DESCRIPTION:
UNT012 IN PECR 6.0
END DESCRIPTION:
XS GIS Cut Line= 4
      2326001.25     13255421.52      2325878.42     13255695.78
      2325710.17     13256045.74      2325641.19     13256225.77
#Sta/Elev= 30
  4608.2  124.84  4676.1  123.53  4745.5  116.79  4767.4  112.43  4774.4  108.86
  4803.1  104.93  4905.1   99.23  4920.3   99.08  4969.5   97.61  4986.6   92.15
  4995.7   92.00  4998.4   91.50  5001.7   92.00  5014.7   92.42  5031.8   98.16
  5165.1  100.77  5253.9  105.67  5263.7  107.91  5300.3  108.30  5308.9  109.31
  5316.0  113.69  5321.4  111.28  5336.1  115.16  5340.7  116.13  5346.1  111.59
  5370.8  118.28  5376.1  116.81  5427.2  117.22  5440.7  116.70  5489.8  116.19
#Mann=8,-1,0
  4608.2     0.1       0  4905.1    0.08       0  4920.3    0.16       0
  4995.7    0.07       0  5001.7    0.16       0  5336.1     0.1       0
  5427.2    0.16       0  5440.7     0.1       0
Bank Sta=4995.7,5001.7
Exp/Cntr=0.3,0.1

Type RM Length L Ch R = 1,2441,350,350,350
BEGIN DESCRIPTION:
UNT012 IN PECR 5.0
END DESCRIPTION:
XS GIS Cut Line= 2
      2325811.88     13255352.17      2325353.55     13256430.29
#Sta/Elev= 30
  4580.5  123.53  4661.7  120.36  4684.7  117.15  4694.2  113.61  4702.9  112.05
  4708.4  112.47  4716.0  110.13  4792.0  104.72  4824.6  101.03  4900.7   97.12
  4943.6   96.56  4955.0   96.35  4961.1   92.48  4976.8   92.65  4981.8   91.21
  4984.5   90.71  4987.8   91.21  4990.2   92.13  4998.5   91.21  5042.9   91.90
  5049.6   94.32  5052.8   95.48  5142.9   95.80  5190.2   98.24  5272.0   99.83
  5335.4  103.92  5372.1  103.61  5401.1  105.58  5501.1  107.76  5752.0  122.94
#Mann=5,-1,0
  4580.5     0.1       0  4943.6    0.12       0  4981.8    0.07       0
  4987.8    0.12       0  5049.6    0.16       0
Bank Sta=4981.8,4987.8
Exp/Cntr=0.3,0.1

Type RM Length L Ch R = 1,2091,517,517,517
BEGIN DESCRIPTION:
UNT012 IN PECR 4.0
END DESCRIPTION:
XS GIS Cut Line= 3
      2325593.13     13255414.68      2325181.67     13255841.76
      2325098.34     13256190.71
#Sta/Elev= 30
  4647.2  117.42  4702.1  115.97  4723.2  112.25  4744.6  113.37  4772.9  112.74
  4801.6  108.23  4829.5  103.31  4836.4  101.04  4904.2   91.21  4906.9   90.71
  4910.2   91.21  5010.9   91.21  5062.8   91.21  5144.3   94.64  5154.7   94.97
  5183.0   99.19  5190.2  104.90  5197.1  105.80  5225.4  105.39  5239.4  103.84
  5275.0  105.63  5280.1  109.14  5286.6  111.52  5369.4  112.72  5440.8  115.22
  5470.2  117.64  5502.5  117.83  5537.8  122.04  5571.1  122.02  5599.0  123.00
#Mann=10,-1,0
  4647.2     0.1       0  4801.6    0.05       0  4904.2   0.033       0
  4910.2    0.05       0  5010.9    0.12       0  5144.3     0.1       0
  5239.4    0.16       0  5369.4     0.1       0  5470.2    0.08       0
  5571.1     0.1       0
Bank Sta=4904.2,4910.2
Exp/Cntr=0.3,0.1

Type RM Length L Ch R = 1,1574,523,523,523
BEGIN DESCRIPTION:
UNT012 IN PECR 3.0
END DESCRIPTION:
XS GIS Cut Line= 4
      2325296.97     13254978.30      2324997.19     13255156.43
      2324758.21     13255799.52      2324936.37     13256125.43
#Sta/Elev= 30
  4374.5  113.11  4384.9  112.52  4480.4  108.34  4540.2  107.32  4569.1  107.85
  4664.4  107.45  4709.7  105.20  4720.0  103.53  4737.4  102.59  4777.0   96.56
  4809.0   94.58  4815.3   91.21  4818.0   90.71  4821.3   91.21  5141.5   91.21
  5157.2   92.24  5191.5   92.23  5196.9   93.47  5282.6   96.71  5307.7   98.79
  5357.3  101.02  5409.3  103.25  5415.3  104.70  5429.0  105.49  5473.8  106.47
  5475.8  106.40  5590.2  110.24  5668.0  113.28  5704.7  114.94  5780.7  118.52
#Mann=15,-1,0
  4374.5    0.05       0  4384.9    0.08       0  4480.4    0.05       0
  4569.1     0.1       0  4737.4    0.07       0  4815.3    0.07       0
  4821.3    0.07       0  5157.2     0.1       0  5307.7    0.07       0
  5357.3     0.1       0  5473.8    0.16       0  5475.8    0.08       0
  5590.2     0.1       0  5668.0    0.08       0  5704.7     0.1       0
Bank Sta=4815.3,4821.3
Exp/Cntr=0.3,0.1

Type RM Length L Ch R = 1,1051,767,767,767
BEGIN DESCRIPTION:
UNT012 IN PECR 2.0
END DESCRIPTION:
XS GIS Cut Line= 3
      2325137.71     13254546.87      2324402.16     13255136.90
      2324409.09     13256052.72
#Sta/Elev= 30
  3874.9  111.08  3895.6  109.66  3932.2  107.75  4067.2  102.18  4138.1  100.54
  4187.7   97.68  4195.4   96.38  4216.5   96.72  4245.3   94.96  4282.2   95.02
  4309.4   94.63  4365.4   92.01  4387.7   92.00  4391.2   91.21  4393.9   90.71
  4397.2   91.21  5307.8   91.21  5357.8   94.58  5377.8   98.14  5397.8   97.88
  5428.8  101.07  5457.8  101.50  5477.8  103.24  5527.6  104.71  5547.8  105.03
  5557.8  106.96  5567.8  107.44  5626.4  108.90  5725.2  113.99  5733.7  114.93
#Mann=10,-1,0
  3874.9     0.1       0  3895.6    0.05       0  3932.2     0.1       0
  4282.2    0.07       0  4391.2    0.07       0  4397.2    0.07       0
  5428.8    0.05       0  5527.6    0.08       0  5626.4    0.05       0
  5725.2    0.16       0
Bank Sta=4391.2,4397.2
Exp/Cntr=0.3,0.1

Type RM Length L Ch R = 1,284,0,0,0
BEGIN DESCRIPTION:
UNT012 IN PECR 1.0
END DESCRIPTION:
XS GIS Cut Line= 4
      2324937.70     13254396.86      2323895.21     13254761.90
      2323464.66     13255616.07      2324402.16     13256254.96
#Sta/Elev= 30
  3485.6  107.96  3493.8  107.78  3612.7  104.34  3837.0  101.28  3977.9  101.45
  4079.9  100.43  4102.9   98.93  4174.3   95.06  4260.5   92.84  4298.4   91.21
  4301.2   90.71  4304.4   91.21  4439.6   91.21  6082.9   91.21  6092.2   93.07
  6104.2   93.85  6140.1  101.14  6176.1  106.02  6232.9  106.11  6311.1  110.07
  6376.6  110.74  6391.5  112.00  6427.6  111.52  6442.3  113.04  6550.1  113.91
  6565.0  113.07  6621.9  115.07  6642.9  114.20  6657.8  115.56  6681.2  115.23
#Mann=11,-1,0
  3485.6    0.05       0  3493.8     0.1       0  3977.9    0.05       0
  4102.9     0.1       0  4260.5    0.05       0  4298.4   0.033       0
  4304.4    0.05       0  4439.6    0.05       0  6092.2     0.1       0
  6311.1    0.08       0  6427.6     0.1       0
Bank Sta=4298.4,4304.4
Exp/Cntr=0.3,0.1

Chan Stop Cuts=-1