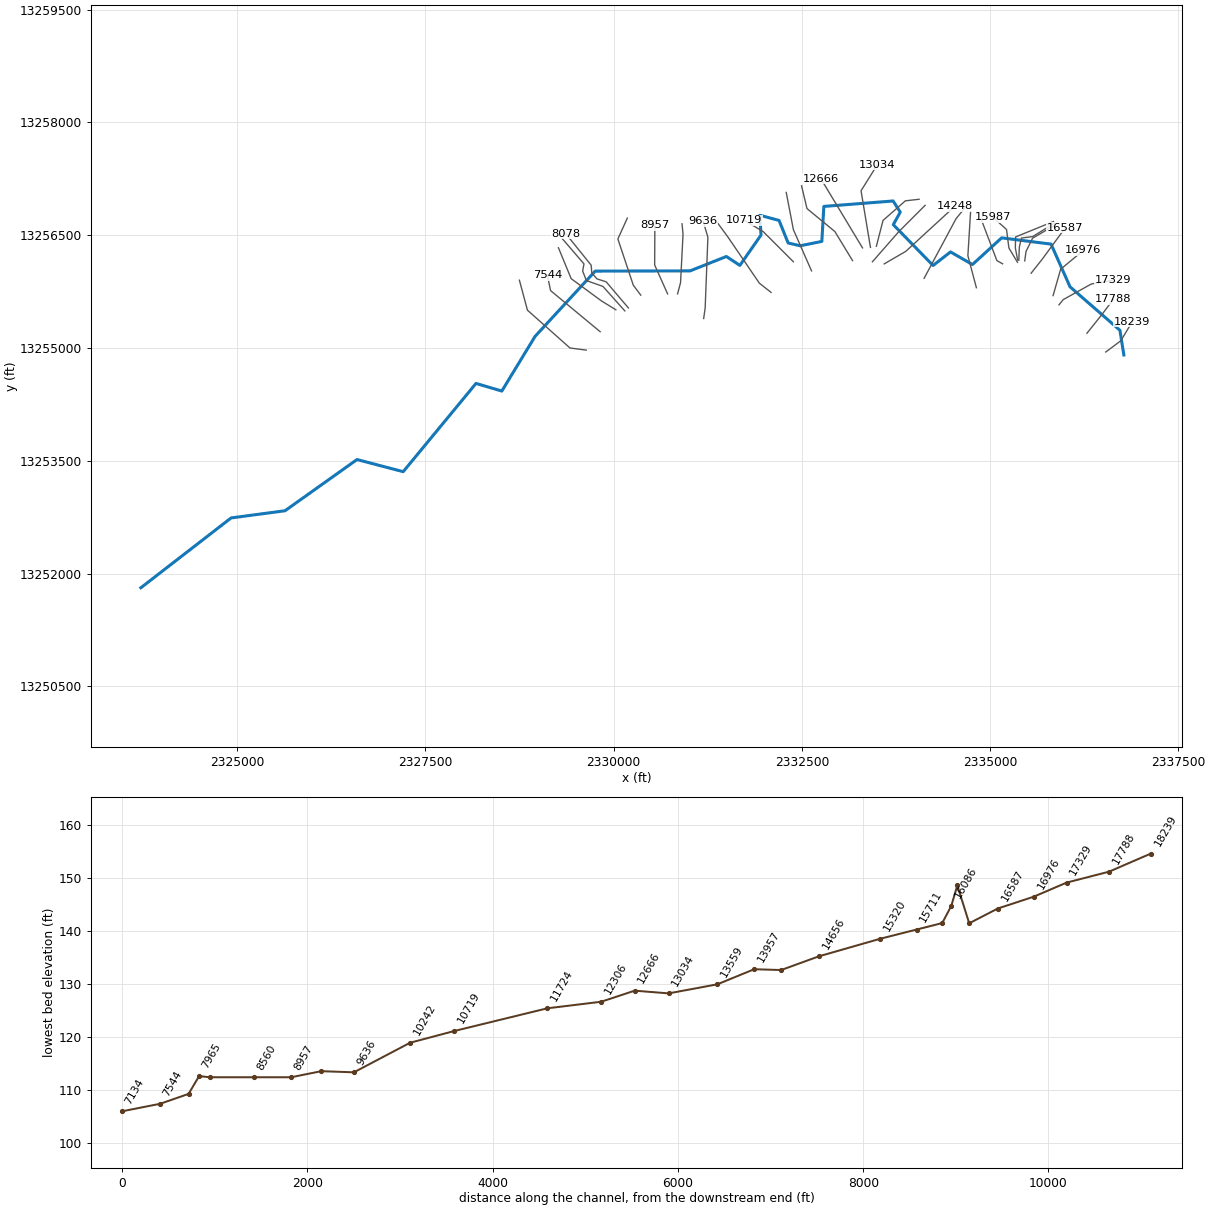
--- UNT013 IN PECR.prj (project) ---

Proj Title=UNT013 IN PECR Base Level Engineering
Current Plan=p01
Default Exp/Contr=0.3,0.1
English Units
Geom File=g01
Flow File=f01
Plan File=p01
Y Axis Title=Elevation
X Axis Title(PF)=Main Channel Distance
X Axis Title(XS)=Station
BEGIN DESCRIPTION:
UNT013 IN PECR
END DESCRIPTION:
DSS Export Rating Curves= 0
DSS Export Rating Curve Sorted= 0
DSS Export Volume Flow Curves= 0
DXF OffsetX= 0
DXF OffsetY= 0
DXF ScaleX= 1
DXF ScaleY= 10

--- UNT013 IN PECR.p01 (plan) ---

Plan Title=Multiple Run
Short Identifier=Multiple
Geom File=g01
Flow File=f01
Subcritical Flow
K Sum by GR= 0
Std Step Tol= 0.01
Critical Tol= 0.01
Num of Std Step Trials= 20
Max Error Tol= 0.3
Flow Tol Ratio= 0.001
Split Flow NTrial= 30
Split Flow Tol= 0.02
Split Flow Ratio= 0.02
Log Output Level= 0
Friction Slope Method= 1
Unsteady Friction Slope Method= 2
Unsteady Bridges Friction Slope Method= 1
Parabolic Critical Depth
Global Vel Dist=  1 , 1 , 1
Global Log Level= 0
CheckData=True
Encroach Param= -1, 0, 0, 0
BEGIN DESCRIPTION:
Multiple Run
END DESCRIPTION:

--- UNT013 IN PECR.f01 (steady flow) ---

Flow Title=Multiple
Program Version=4.10
Number of Profiles= 7
Profile Names=10-year,25-year,50-year,1pct_min,100-year,1pct_plu,500-year
River Rch & RM=UNT013 IN PECR,Reach-1         ,18239
     699     983    1219    1103    1492    2018    2244
River Rch & RM=UNT013 IN PECR,Reach-1         ,15711
    1326    1924    2437    2247    3039    4110    4747
River Rch & RM=UNT013 IN PECR,Reach-1         ,6471
    1681    2461    3136    2906    3930    5315    6200
Boundary for River Rch & Prof#=UNT013 IN PECR,Reach-1         , 1
Up Type= 0
Dn Type= 3
Dn Slope=0.0002
Boundary for River Rch & Prof#=UNT013 IN PECR,Reach-1         , 2
Up Type= 0
Dn Type= 3
Dn Slope=0.0002
Boundary for River Rch & Prof#=UNT013 IN PECR,Reach-1         , 3
Up Type= 0
Dn Type= 3
Dn Slope=0.0002
Boundary for River Rch & Prof#=UNT013 IN PECR,Reach-1         , 4
Up Type= 0
Dn Type= 3
Dn Slope=0.0002
Boundary for River Rch & Prof#=UNT013 IN PECR,Reach-1         , 5
Up Type= 0
Dn Type= 3
Dn Slope=0.0002
Boundary for River Rch & Prof#=UNT013 IN PECR,Reach-1         , 6
Up Type= 0
Dn Type= 3
Dn Slope=0.0002
Boundary for River Rch & Prof#=UNT013 IN PECR,Reach-1         , 7
Up Type= 0
Dn Type= 3
Dn Slope=0.0002
DSS Import GetInterval= 0
DSS Import GetPeak= 0
DSS Import FillOption= 0

--- UNT013 IN PECR.g01 (geometry) ---

Geom Title=Existing Conditions
Program Version=4.10

River Reach=UNT013 IN PECR  ,Reach-1
Reach XY= 30
      2336777.72     13254906.85       2336725.5     13255235.99
      2336062.67     13255813.87      2335811.06     13256381.42
      2335154.25     13256464.67       2334766.4      13256110.1
      2334475.35     13256277.53      2334243.13      13256097.1
      2333714.73     13256640.61      2333807.64      13256806.7
      2333712.21     13256954.94      2332792.49      13256882.8
      2332765.61      13256417.5      2332477.76     13256359.31
      2332318.04     13256396.69       2332197.6     13256696.23
      2331942.97      13256765.1      2331957.67     13256501.64
      2331676.86     13256098.43      2331497.92     13256217.03
      2331016.27     13256025.77      2329754.99      13256022.3
      2328955.55     13255153.56      2328514.76     13254427.58
      2328171.88     13254529.15      2327204.64     13253355.63
      2326591.24     13253517.04      2325634.76      13252836.1
      2324918.61     13252740.62       2323719.7     13251812.06

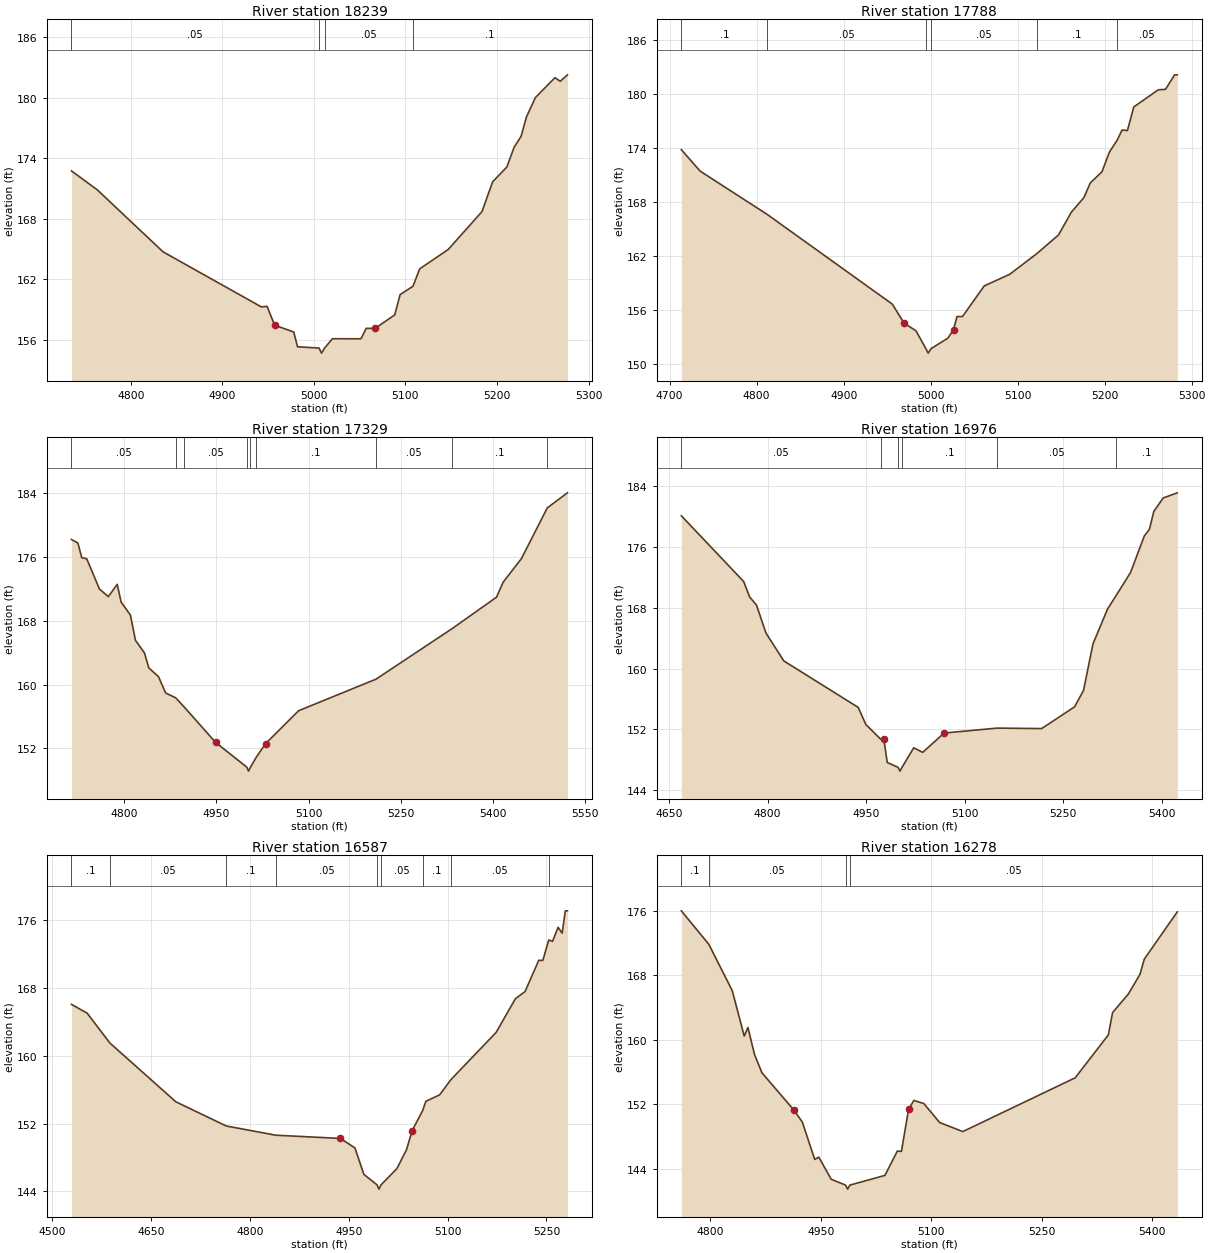
Type RM Length L Ch R = 1 ,18239   ,451,451,451
BEGIN DESCRIPTION:
UNT013 IN PECR 39.0
END DESCRIPTION:
XS GIS Cut Line= 3
       2336537.7     13254946.84      2336737.72     13255096.85
      2336887.73     13255346.88
#Sta/Elev= 30
  4735.3  172.73  4763.5  170.85  4835.3   164.7  4942.6  159.24  4948.9  159.29
  4957.2  157.42    4978  156.75  4982.2  155.28  5005.7  155.15  5008.4  154.65
  5011.7  155.15  5020.3  156.08  5051.4  156.07  5057.2  157.11    5067  157.11
  5088.3  158.44  5094.2  160.46  5108.2  161.28  5115.6  163.01  5146.7  164.93
  5183.6  168.69  5195.2  171.64  5210.8  173.12  5218.6  175.06  5226.3  176.16
  5232.2  178.09  5241.9     180  5263.3  181.98  5269.1  181.62  5276.9  182.26
#Mann= 4 ,-1 , 0
  4735.3     .05       0  5005.7     .03       0  5011.7     .05       0
  5108.2      .1       0
Bank Sta=4957.2,5067
XS Rating Curve= 0 ,0
Exp/Cntr=0.3,0.1

Type RM Length L Ch R = 1 ,17788   ,459,459,459
BEGIN DESCRIPTION:
UNT013 IN PECR 38.0
END DESCRIPTION:
XS GIS Cut Line= 3
      2336287.75     13255196.89      2336487.72     13255446.85
      2336637.72     13255646.85
#Sta/Elev= 30
  4713.4  173.85    4735  171.47  4812.3  166.64  4955.9  156.68  4969.5  154.56
  4983.1  153.72  4994.5  151.73  4997.2  151.23  5000.5  151.73  5019.9   152.9
  5026.3  153.85  5030.3   155.3  5036.6   155.3  5061.6   158.7  5090.8  159.99
  5122.2   162.3    5147  164.37  5161.6  166.88  5176.2  168.53  5183.5  170.15
    5197   171.4  5205.4  173.57  5214.3  174.89    5220  176.03  5226.2  175.98
  5233.5   178.6  5261.6   180.5    5270  180.56  5280.4  182.17  5283.5  182.17
#Mann= 6 ,-1 , 0
  4713.4      .1       0  4812.3     .05       0  4994.5     .03       0
  5000.5     .05       0  5122.2      .1       0  5214.3     .05       0
Bank Sta=4969.5,5026.3
XS Rating Curve= 0 ,0
Exp/Cntr=0.3,0.1

Type RM Length L Ch R = 1 ,17329   ,353,353,353
BEGIN DESCRIPTION:
UNT013 IN PECR 37.0
END DESCRIPTION:
XS GIS Cut Line= 4
      2335916.11     13255573.87      2335971.64     13255643.29
      2336346.64     13255851.62      2336631.34     13255900.23
#Sta/Elev= 30
  4714.3  178.15  4724.7  177.72  4731.1  175.87  4739.1  175.74  4759.9  171.94
  4774.3     171  4788.7  172.53  4795.1  170.32  4810.2  168.69  4818.4  165.53
    4833  163.96  4840.1  162.08  4855.9  160.98  4867.5  158.94  4883.7  158.34
  4897.6  157.19  4948.8  152.75  4999.5  149.66  5002.3  149.16  5005.5  149.66
  5014.8  150.89    5030   152.6  5083.8  156.72  5209.7  160.67    5333  166.97
  5405.7  170.93  5416.4   172.8  5446.3  175.77  5488.2   182.1    5521  183.99
#Mann= 9 ,-1 , 0
  4714.3     .05       0  4883.7      .1       0  4897.6     .05       0
  4999.5     .03       0  5005.5     .05       0  5014.8      .1       0
  5209.7     .05       0    5333      .1       0  5488.2     .05       0
Bank Sta=4948.8,5030
XS Rating Curve= 0 ,0
Exp/Cntr=0.3,0.1

Type RM Length L Ch R = 1 ,16976   ,389,389,389
BEGIN DESCRIPTION:
UNT013 IN PECR 36.0
END DESCRIPTION:
XS GIS Cut Line= 3
      2335837.71     13255696.81      2335937.72     13256046.85
      2336237.75     13256296.88
#Sta/Elev= 30
  4668.8  180.11  4763.7  171.46  4772.8  169.42  4783.2  168.36  4797.5  164.69
  4824.8  161.01  4937.9   154.9  4949.6  152.64  4972.2  150.71  4976.9  150.76
  4982.1  147.65  4998.6  147.01  5001.4  146.51  5004.6  147.01  5022.4  149.58
  5036.1  148.98  5068.6  151.52  5149.2  152.17    5217  152.11  5267.2  154.97
  5280.8  157.14  5295.1  163.25  5317.3  167.84  5329.8  169.54  5352.4  172.66
  5373.2  177.45  5381.1  178.34  5387.6  180.66  5401.9  182.45  5423.4  183.13
#Mann= 6 ,-1 , 0
  4668.8     .05       0  4972.2      .1       0  4998.6     .07       0
  5004.6      .1       0  5149.2     .05       0  5329.8      .1       0
Bank Sta=4976.9,5068.6
XS Rating Curve= 0 ,0
Exp/Cntr=0.3,0.1

Type RM Length L Ch R = 1 ,16587   ,309,309,309
BEGIN DESCRIPTION:
Mapping XS 80fba3f0
END DESCRIPTION:
XS GIS Cut Line= 3
      2335546.45     13255995.06      2335696.47     13256184.96
      2335998.37     13256596.98
#Sta/Elev= 30
  4529.1  166.03  4552.9     165  4587.4  161.48  4687.5  154.56  4763.9  151.71
  4839.3  150.62  4937.4  150.24  4959.4  149.12  4972.9  146.01    4993  144.77
  4995.8  144.27    4999  144.77  5023.1  146.69  5037.7  148.92  5046.2  151.16
  5062.1  153.51  5067.1  154.62  5087.9  155.37  5105.1  157.17  5173.6  162.72
  5202.9  166.69  5217.6  167.54  5238.4  171.22  5244.6  171.21  5253.6  173.62
  5259.3  173.45  5267.7   175.1  5273.9  174.42  5278.7  177.05  5281.9  177.05
#Mann= 9 ,-1 , 0
  4529.1      .1       0  4587.4     .05       0  4763.9      .1       0
  4839.3     .05       0    4993     .03       0    4999     .05       0
  5062.1      .1       0  5105.1     .05       0  5253.6      .1       0
Bank Sta=4937.4,5046.2
XS Rating Curve= 0 ,0
Exp/Cntr=0.3,0.1

Type RM Length L Ch R = 1 ,16278   ,128,128,128
BEGIN DESCRIPTION:
UNT013 IN PECR 35.0
END DESCRIPTION:
XS GIS Cut Line= 4
      2335461.03     13256158.42      2335478.11      13256283.7
      2335565.46     13256460.29      2335867.36     13256636.87
#Sta/Elev= 30
  4760.7  175.96    4798  171.82  4829.8  166.08  4846.1  160.44  4851.1  161.51
    4860  158.18  4870.1   155.9    4913  151.33  4924.9   149.8  4941.8  145.16
  4947.3  145.44  4964.2   142.7  4983.6  141.98  4986.4  141.48  4989.6  141.98
  5037.1  143.18  5053.9  146.19  5059.5  146.16  5069.2  151.38  5076.4  152.47
  5089.9  152.08  5111.4  149.73  5142.8  148.61  5295.3  155.27  5340.3  160.58
  5346.1  163.35  5367.6  165.67  5383.3   168.1  5389.1  169.97  5433.9  175.83
#Mann= 4 ,-1 , 0
  4760.7      .1       0    4798     .05       0  4983.6     .03       0
  4989.6     .05       0
Bank Sta=4913,5069.2
XS Rating Curve= 0 ,0
Exp/Cntr=0.3,0.1

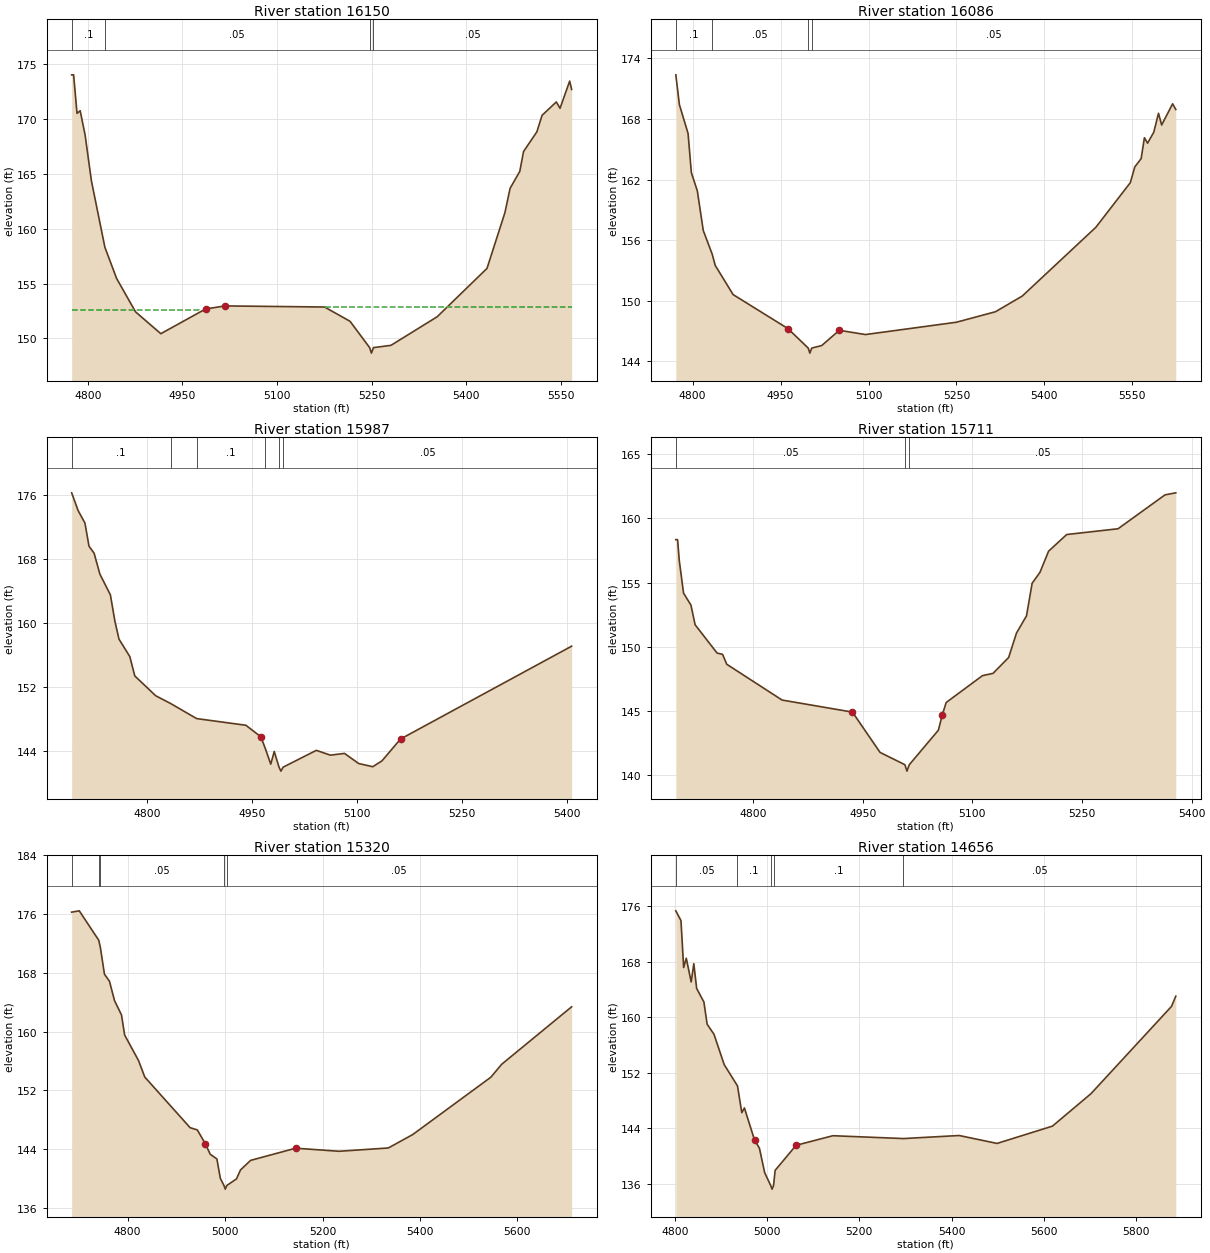
Type RM Length L Ch R = 1 ,16150   ,64,64,64
BEGIN DESCRIPTION:
Mapping XS 72ed15cb
END DESCRIPTION:
XS GIS Cut Line= 5
       2335382.3     13256165.59      2335389.32     13256342.84
       2335417.4     13256462.17      2335566.56     13256481.48
       2335857.6     13256662.06
#Sta/Elev= 30
  4774.3  174.01  4777.4  174.01  4782.8   170.5  4787.8  170.74  4795.6  168.54
  4805.6  164.36    4827   158.3  4845.6  155.46  4875.6  152.42  4915.7  150.43
  4986.6  152.68  5017.5  152.96  5175.4  152.86  5215.8  151.56  5246.9  149.16
  5249.7  148.66  5252.9  149.16  5280.7  149.37  5353.9  151.97    5433  156.38
  5461.4  161.46  5469.6  163.67    5485  165.22  5490.9  167.02  5512.1  168.82
  5520.3  170.32  5542.9  171.54  5548.8  170.96  5564.1  173.44  5567.2  172.68
#Mann= 4 ,-1 , 0
  4774.3      .1       0    4827     .05       0  5246.9     .03       0
  5252.9     .05       0
#XS Ineff= 2 , 0
       0  4976.7  152.57  5175.8       0  152.87
Permanent Ineff=
       T       T
Bank Sta=4986.6,5017.5
XS Rating Curve= 0 ,0
Exp/Cntr=0.3,0.1

Type RM Length L Ch R = 1 ,16086   ,99,99,99
BEGIN DESCRIPTION:
Mapping XS 0cadd873
END DESCRIPTION:
XS GIS Cut Line= 4
      2335366.51     13256170.82      2335336.67      13256328.8
      2335338.43     13256476.21      2335842.44       13256682.
#Sta/Elev= 30
  4771.4  172.38  4777.5  169.43  4792.3  166.57  4797.9  162.69  4808.1  160.88
  4818.2  156.96  4833.6  154.59  4838.6   153.5  4869.1  150.61 4962.58  147.24
  4997.2  145.31    5000  144.81  5003.2  145.31  5020.2  145.56  5050.2  147.07
  5094.8  146.65  5249.8  147.87  5316.5  148.91  5362.1  150.46  5487.6  157.27
  5546.5   161.7  5554.1  163.26  5564.9  164.08  5570.5  166.15  5575.9  165.61
  5586.5   166.7  5594.5  168.57  5599.9  167.41  5618.6  169.51    5624  168.95
#Mann= 4 ,-1 , 0
  4771.4      .1       0  4833.6     .05       0  4997.2     .03       0
  5003.2     .05       0
Bank Sta=4962.58,5050.2
XS Rating Curve= 0 ,0
Exp/Cntr=0.3,0.1

Type RM Length L Ch R = 1 ,15987   ,276,276,276
BEGIN DESCRIPTION:
UNT013 IN PECR 34.0
END DESCRIPTION:
XS GIS Cut Line= 4
      2335364.72     13256139.31      2335250.68     13256330.55
      2335219.09     13256576.24      2335036.59     13256739.44
#Sta/Elev= 30
  4691.7  176.22    4701     174  4710.7  172.45  4716.5  169.57  4723.8  168.69
  4732.1  166.08  4747.1   163.5  4753.5  160.24  4759.4  157.98  4774.9   155.8
    4782  153.39  4811.9  150.92  4833.5  149.94  4870.5  148.07  4940.9  147.24
 4962.24  145.81  4968.9   144.3  4976.5  142.39  4981.5  143.97  4988.3  142.02
    4991  141.52  4994.3  142.02  5041.7  144.11  5061.9  143.51    5082  143.73
  5102.2  142.47  5122.4  142.07  5135.6   142.8  5162.1  145.52  5406.9   157.1
#Mann= 6 ,-1 , 0
  4691.7      .1       0  4833.5     .05       0  4870.5      .1       0
  4968.9     .05       0  4988.3     .03       0  4994.3     .05       0
Bank Sta=4962.24,5162.1
XS Rating Curve= 0 ,0
Exp/Cntr=0.3,0.1

Type RM Length L Ch R = 1 ,15711   ,391,391,391
BEGIN DESCRIPTION:
UNT013 IN PECR 33.0
END DESCRIPTION:
XS GIS Cut Line= 3
      2335166.93     13256119.52      2335090.98     13256162.44
      2334879.57     13256720.72
#Sta/Elev= 30
  4694.1  158.34  4696.5  158.34  4698.9  156.68  4704.7  154.17  4714.8  153.24
  4720.5  151.71  4750.6   149.5  4758.1   149.4  4763.8  148.63  4839.5  145.84
  4935.8   144.9  4973.6  141.76  5007.6   140.8  5010.4   140.3  5013.6   140.8
  5053.4  143.49  5058.8  144.69  5064.1  145.65  5113.7  147.74  5128.2  147.92
  5149.6  149.16  5160.3  151.06    5174   152.4  5181.7  154.94  5192.4  155.79
  5204.2  157.44    5229  158.74  5299.3  159.19  5363.5  161.83  5378.3  161.99
#Mann= 3 ,-1 , 0
  4694.1     .05       0  5007.6     .03       0  5013.6     .05       0
Bank Sta=4935.8,5058.8
XS Rating Curve= 0 ,0
Exp/Cntr=0.3,0.1

Type RM Length L Ch R = 1 ,15320   ,664,664,664
BEGIN DESCRIPTION:
UNT013 IN PECR 32.0
END DESCRIPTION:
XS GIS Cut Line= 3
      2334818.65     13255801.82       2334705.8     13256227.18
      2334741.68     13256812.31
#Sta/Elev= 30
  4685.1  176.26  4700.7  176.44  4740.7  172.44  4744.1  171.43  4752.4  167.82
  4762.7  166.86  4773.1  164.22  4787.4  162.27  4793.8  159.55  4822.4  156.06
  4835.2  153.82  4928.3  146.93    4943  146.63  4959.3  144.77  4969.6  143.31
  4983.2  142.68  4990.3  140.03  4997.7  139.07  5000.4  138.57  5003.7  139.07
  5023.4  139.96  5031.7  141.18  5052.4  142.48  5144.9  144.14  5234.1  143.72
  5335.2  144.17  5385.3     146  5545.6   153.8  5567.8  155.56  5711.4  163.38
#Mann= 5 ,-1 , 0
  4685.1     .05       0  4740.7      .1       0  4744.1     .05       0
  4997.7     .03       0  5003.7     .05       0
Bank Sta=4959.3,5144.9
XS Rating Curve= 0 ,0
Exp/Cntr=0.3,0.1

Type RM Length L Ch R = 1 ,14656   ,408,408,408
BEGIN DESCRIPTION:
UNT013 IN PECR 31.0
END DESCRIPTION:
XS GIS Cut Line= 3
      2334124.61     13255926.99      2334548.22     13256718.65
      2334665.21     13256863.17
#Sta/Elev= 30
  4802.2  175.31  4813.4   173.9  4819.2  167.15  4824.9  168.48  4835.5  165.07
  4841.2   167.7  4847.4  164.13  4863.1  162.18  4870.1  158.99    4885  157.53
    4907  153.18  4935.9   150.1  4945.2  146.25  4950.9  146.93  4972.8  142.32
  4983.4  141.14  4994.9   137.6    5008  135.74  5010.8  135.24    5014  135.74
  5017.5  137.94  5062.9  141.55  5142.6  142.93  5295.5  142.52  5416.5  142.96
  5498.6  141.82  5618.6  144.31  5702.1  148.98  5876.7  161.55    5886  163.02
#Mann= 5 ,-1 , 0
  4802.2     .05       0  4935.9      .1       0    5008     .07       0
    5014      .1       0  5295.5     .05       0
Bank Sta=4972.8,5062.9
XS Rating Curve= 0 ,0
Exp/Cntr=0.3,0.1

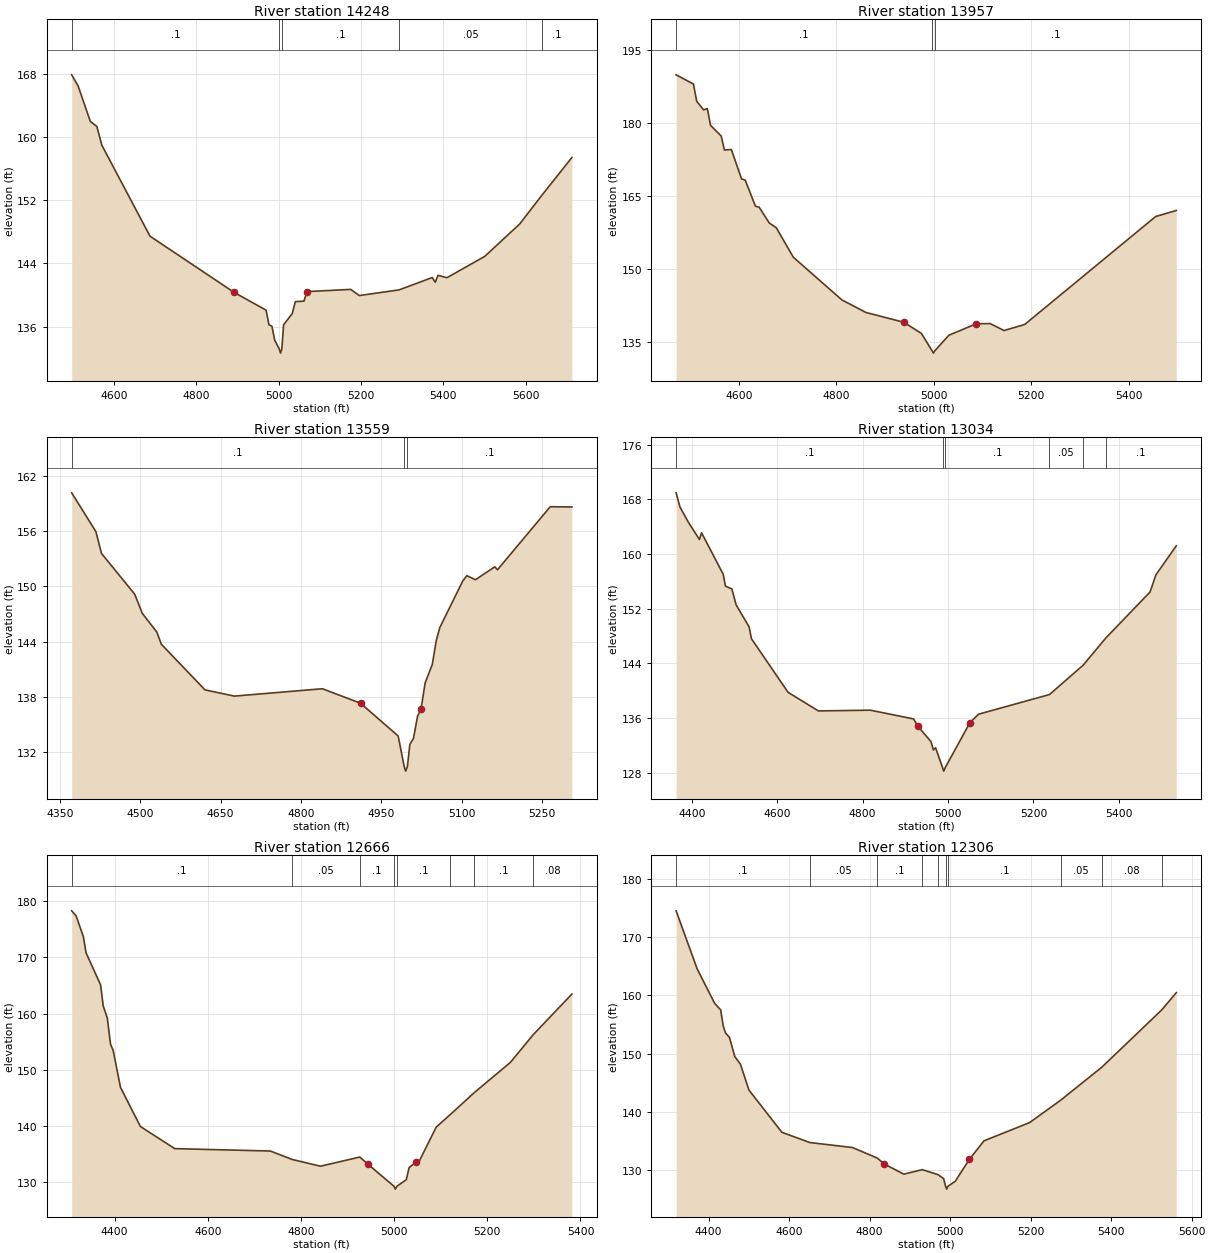
Type RM Length L Ch R = 1 ,14248   ,291,291,291
BEGIN DESCRIPTION:
UNT013 IN PECR 30.0
END DESCRIPTION:
XS GIS Cut Line= 3
      2333594.36     13256118.57      2333880.81     13256285.23
      2334530.56     13256883.01
#Sta/Elev= 30
  4497.6  167.89  4513.1   166.5  4542.9  161.99  4558.7  161.35  4570.9  158.97
  4687.7  147.46  4891.9  140.34  4969.6  138.09  4976.4  136.25  4983.8  136.04
  4990.6  134.28  5001.7  133.15  5004.5  132.65  5007.7  133.15  5012.1  136.24
  5033.1  137.66  5040.5  139.17  5061.5  139.23  5068.8  140.44  5174.9  140.72
  5195.9  139.94  5292.6  140.66  5372.8  142.22  5380.2  141.63    5387   142.5
  5408.6   142.2  5500.4   144.9  5585.5  149.02  5639.5  152.67  5711.9  157.42
#Mann= 5 ,-1 , 0
  4497.6      .1       0  5001.7     .07       0  5007.7      .1       0
  5292.6     .05       0  5639.5      .1       0
Bank Sta=4891.9,5068.8
XS Rating Curve= 0 ,0
Exp/Cntr=0.3,0.1

Type RM Length L Ch R = 1 ,13957   ,398,398,398
BEGIN DESCRIPTION:
UNT013 IN PECR 29.0
END DESCRIPTION:
XS GIS Cut Line= 3
       2333437.7     13256146.84      2333787.72     13256546.85
      2334137.72     13256896.85
#Sta/Elev= 30
  4471.2  189.83  4506.8  187.95  4513.5  184.41  4527.7  182.64  4535.3  182.91
  4541.9  179.48  4563.8  177.28  4570.4  174.42  4584.6  174.52  4605.5  168.51
  4613.1  168.25    4634  162.91  4641.6  162.71  4662.5  159.46  4676.7  158.51
  4711.8  152.45  4811.5   143.7  4860.8  141.13  4938.7  139.12  4974.7  136.83
  4996.4   133.3  4999.2   132.8  5002.4   133.3    5031  136.47  5087.6  138.83
  5115.9  138.85  5144.2  137.43  5186.6  138.67  5455.3  160.79  5497.7  162.03
#Mann= 3 ,-1 , 0
  4471.2      .1       0  4996.4     .07       0  5002.4      .1       0
Bank Sta=4938.7,5087.6
XS Rating Curve= 0 ,0
Exp/Cntr=0.3,0.1

Type RM Length L Ch R = 1 ,13559   ,525,525,525
BEGIN DESCRIPTION:
UNT013 IN PECR 28.0
END DESCRIPTION:
XS GIS Cut Line= 4
      2333490.19     13256352.98      2333578.72     13256696.69
       2333875.6     13256957.11      2334057.88     13256977.94
#Sta/Elev= 30
  4372.2  160.15  4417.4  155.94  4427.8  153.58  4489.8  149.15  4503.9  147.08
  4531.1  145.04  4539.5  143.72  4620.9  138.77  4675.7  138.09    4840  138.89
  4911.1  137.32  4981.4  133.76  4992.6  130.45  4995.4  129.95  4998.6  130.45
  5003.2  132.86  5009.9  133.49  5017.4  135.87  5024.1  136.72  5031.7  139.52
    5045  141.52  5052.6  144.15  5059.2  145.55  5101.9  150.58  5109.5  151.16
  5125.6  150.72  5161.6  152.12  5166.7   151.8  5265.1  158.64  5305.5  158.62
#Mann= 3 ,-1 , 0
  4372.2      .1       0  4992.6     .07       0  4998.6      .1       0
Bank Sta=4911.1,5024.1
XS Rating Curve= 0 ,0
Exp/Cntr=0.3,0.1

Type RM Length L Ch R = 1 ,13034   ,368,368,368
BEGIN DESCRIPTION:
UNT013 IN PECR 27.0
END DESCRIPTION:
XS GIS Cut Line= 3
      2333411.69     13256337.97      2333286.53      13257090.9
      2333503.11     13257437.43
#Sta/Elev= 30
  4362.9  168.97  4371.9  166.91  4392.2  164.61  4417.6  162.14  4422.6  163.12
  4473.3  157.05  4478.5  155.32  4493.6  154.89  4503.7  152.56  4534.1  149.34
  4539.4  147.62  4625.3  139.77  4696.3  137.05  4817.9  137.16  4919.3  135.88
  4929.5  134.79  4959.9  132.58  4965.7  131.34  4970.8  131.66  4987.3  128.74
    4990  128.24  4993.3  128.74  5051.1  135.31  5071.4  136.57  5237.7  139.45
  5316.5  143.74  5369.9  147.74  5473.4  154.46    5487  156.97  5534.8  161.22
#Mann= 6 ,-1 , 0
  4362.9      .1       0  4987.3     .07       0  4993.3      .1       0
  5237.7     .05       0  5316.5     .08       0  5369.9      .1       0
Bank Sta=4929.5,5051.1
XS Rating Curve= 0 ,0
Exp/Cntr=0.3,0.1

Type RM Length L Ch R = 1 ,12666   ,360,360,360
BEGIN DESCRIPTION:
UNT013 IN PECR 26.0
END DESCRIPTION:
XS GIS Cut Line= 2
       2333306.2     13256331.23      2332752.68     13257251.49
#Sta/Elev= 30
  4307.7  178.29  4317.3  177.38  4332.8  173.69  4338.6  170.81  4369.7  165.13
  4375.5  161.35  4384.3  159.17  4391.1  154.56  4396.9  153.41  4412.5  146.86
  4455.2   139.9    4529  135.96  4734.4  135.53  4781.2  134.03  4841.8  132.83
  4926.3  134.46  4944.4  133.14  4999.8  129.25  5002.5  128.75  5005.8  129.25
  5026.1  130.43  5032.1  132.57  5047.6  133.61  5053.5  133.66  5090.4   139.8
  5120.5  142.02  5172.2  145.94  5249.7  151.32  5298.8  156.26  5381.6  163.47
#Mann= 8 ,-1 , 0
  4307.7      .1       0  4781.2     .05       0  4926.3      .1       0
  4999.8     .07       0  5005.8      .1       0  5120.5     .05       0
  5172.2      .1       0  5298.8     .08       0
Bank Sta=4944.4,5047.6
XS Rating Curve= 0 ,0
Exp/Cntr=0.3,0.1

Type RM Length L Ch R = 1 ,12306   ,582,582,582
BEGIN DESCRIPTION:
UNT013 IN PECR 25.0
END DESCRIPTION:
XS GIS Cut Line= 4
      2333173.67      13256162.1      2332939.31     13256548.36
      2332568.42     13256854.13      2332496.59     13257156.03
#Sta/Elev= 30
  4319.1  174.56  4371.4  164.58  4414.8  158.65  4429.9  157.51  4436.2  154.74
    4442  153.53  4451.7  152.77    4465  149.47  4478.9  148.17  4500.2   143.7
    4582  136.44  4651.3  134.68  4757.4  133.82  4819.1     132  4835.3  131.03
  4884.8  129.24  4930.7  130.01  4969.7  129.16  4983.8  128.47  4988.6  127.16
  4991.4  126.66  4994.6  127.16  5012.5  127.99  5047.6  131.76    5084  134.97
  5197.5  138.11  5275.4  142.01  5376.3  147.61  5525.5  157.49  5561.9  160.48
#Mann= 10 ,-1 , 0
  4319.1      .1       0  4651.3     .05       0  4819.1      .1       0
  4930.7     .05       0  4969.7      .1       0  4988.6     .07       0
  4994.6      .1       0  5275.4     .05       0  5376.3     .08       0
  5525.5      .1       0
Bank Sta=4835.3,5047.6
XS Rating Curve= 0 ,0
Exp/Cntr=0.3,0.1

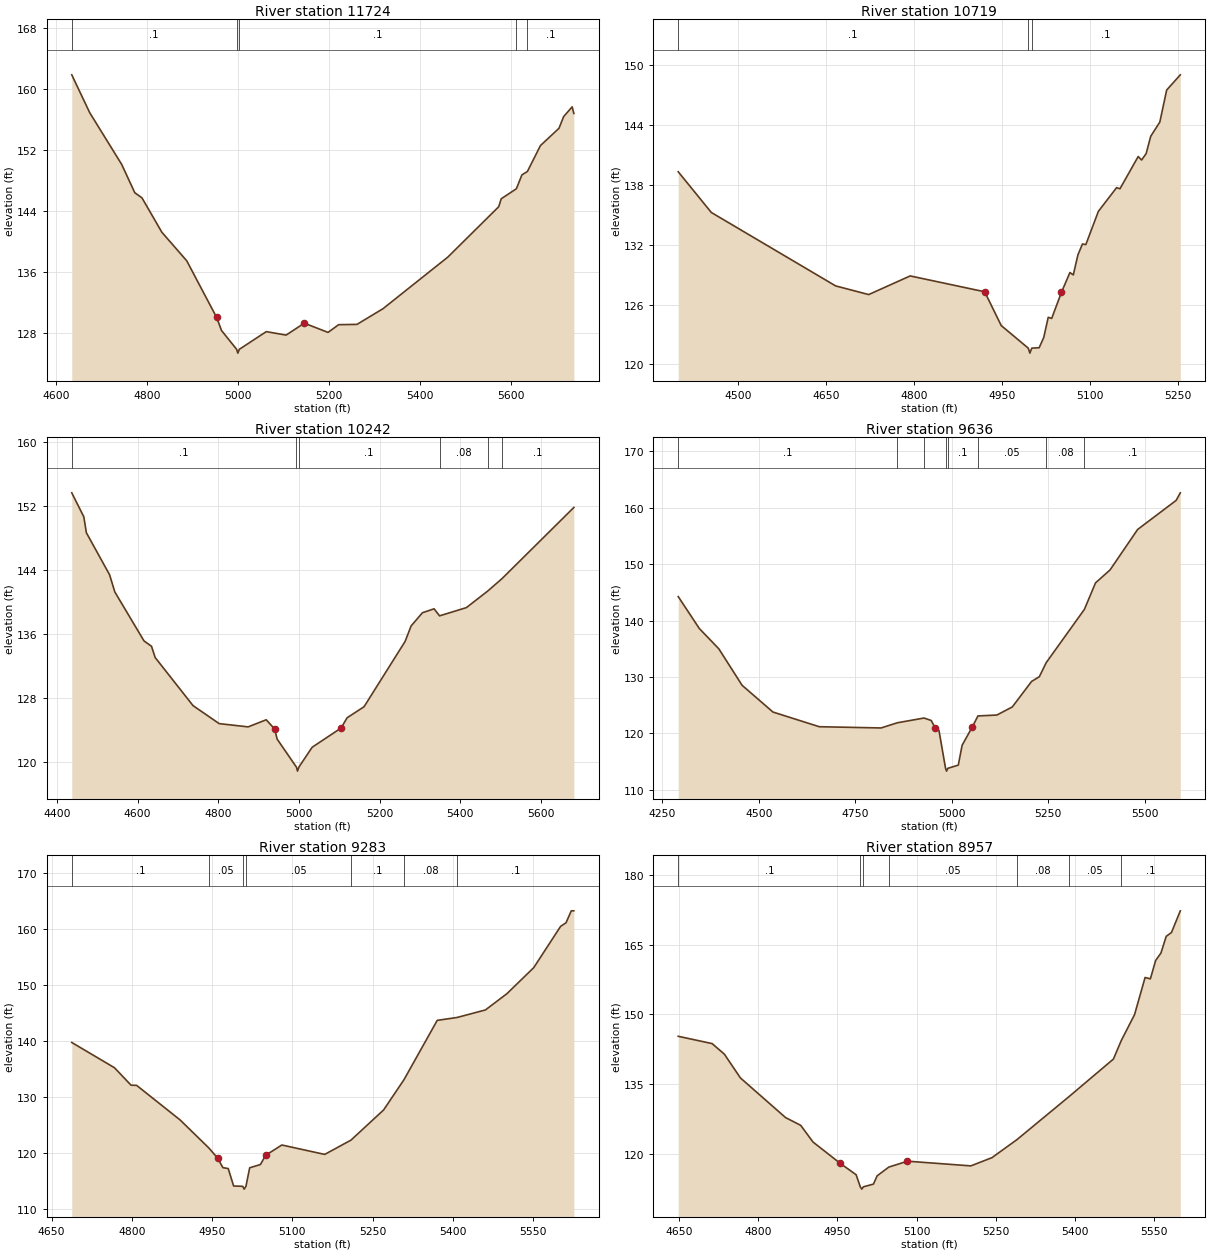
Type RM Length L Ch R = 1 ,11724   ,1005,1005,1005
BEGIN DESCRIPTION:
UNT013 IN PECR 24.0
END DESCRIPTION:
XS GIS Cut Line= 3
      2332628.62     13256025.66      2332387.72      13256574.4
      2332292.67     13257068.85
#Sta/Elev= 30
  4634.3  161.82  4673.8  156.86  4743.9  150.11  4772.7   146.4  4788.5  145.73
  4832.2  141.23  4886.8   137.5  4952.6  130.08  4963.2  128.38  4996.4  125.92
  4999.1  125.42  5002.4  125.92  5061.5  128.23  5105.2  127.78    5145  129.34
  5197.2  128.13  5220.5  129.14  5260.8  129.18  5317.9  131.23  5460.1  137.97
  5572.1  144.57  5577.6  145.61  5610.9  146.92    5623  148.73  5635.1  149.18
  5663.8  152.57  5704.5  154.83  5714.7  156.36  5733.4  157.63  5737.1  156.77
#Mann= 5 ,-1 , 0
  4634.3      .1       0  4996.4     .07       0  5002.4      .1       0
  5610.9     .08       0  5635.1      .1       0
Bank Sta=4952.6,5145
XS Rating Curve= 0 ,0
Exp/Cntr=0.3,0.1

Type RM Length L Ch R = 1 ,10719   ,477,477,477
BEGIN DESCRIPTION:
UNT013 IN PECR 23.0
END DESCRIPTION:
XS GIS Cut Line= 3
       2332387.7     13256146.87      2331987.72     13256546.85
      2331737.72     13256696.85
#Sta/Elev= 30
  4397.4  139.31  4453.9  135.23  4666.1  127.87  4722.6     127  4793.4  128.87
  4920.6  127.28  4948.9  123.89    4995  121.63  4997.8  121.13    5001  121.63
  5013.6  121.67  5021.4  122.69  5029.1  124.72    5035  124.61 5051.59  127.21
  5066.1  129.21  5071.9  128.97  5079.7  130.96  5087.5  132.07  5093.3  132.01
  5114.7  135.34  5145.8  137.72  5151.6  137.61  5182.7  140.84  5188.5  140.49
  5196.3  141.14  5204.1  142.87  5219.6  144.29  5231.3   147.5  5254.6  149.03
#Mann= 3 ,-1 , 0
  4397.4      .1       0    4995     .07       0    5001      .1       0
Bank Sta=4920.6,5051.59
XS Rating Curve= 0 ,0
Exp/Cntr=0.3,0.1

Type RM Length L Ch R = 1 ,10242   ,606,606,606
BEGIN DESCRIPTION:
UNT013 IN PECR 22.0
END DESCRIPTION:
XS GIS Cut Line= 4
      2332091.35     13255739.58      2331936.07     13255861.82
      2331513.22     13256482.89      2331338.14     13256720.73
#Sta/Elev= 30
  4436.8   153.7  4466.7   150.7    4473  148.71  4530.5  143.46  4543.5  141.31
  4615.8  135.19  4634.4  134.52  4643.5  133.11  4737.3   127.1  4802.1  124.85
  4873.9  124.44  4918.7  125.33  4939.7  124.17  4945.7  122.92  4993.6  119.41
  4996.3  118.91  4999.6  119.41  5032.5  121.89  5104.3   124.3  5119.2  125.58
  5161.2  126.96  5262.9  135.12  5277.8  137.06  5305.9  138.71  5334.7   139.2
  5348.3  138.32  5414.8  139.35  5467.4  141.41    5503  142.97  5681.1  151.87
#Mann= 6 ,-1 , 0
  4436.8      .1       0  4993.6     .07       0  4999.6      .1       0
  5348.3     .08       0  5467.4     .05       0    5503      .1       0
Bank Sta=4939.7,5104.3
XS Rating Curve= 0 ,0
Exp/Cntr=0.3,0.1

Type RM Length L Ch R = 1 ,9636    ,353,353,353
BEGIN DESCRIPTION:
UNT013 IN PECR 21.0
END DESCRIPTION:
XS GIS Cut Line= 4
      2331196.07     13255392.71      2331215.89     13255531.46
      2331252.23     13256472.98      2331189.84     13256683.14
#Sta/Elev= 30
  4291.1  144.26  4345.8   138.6  4396.3  135.01  4456.7  128.54  4536.7   123.8
  4656.8   121.2  4816.9  120.98  4859.3   121.9  4928.4  122.74    4947   122.3
    4957  120.99  4967.1  120.52  4984.1  113.83  4986.8  113.33  4990.1  113.83
  5017.1  114.39  5027.1  117.92 5053.73  121.19  5068.1  123.11  5117.2  123.27
  5157.2  124.71  5207.2  129.23  5227.2  130.06  5245.1  132.56  5344.1     142
  5372.9  146.69  5410.5  148.98  5482.1  156.16  5581.8   161.3  5592.7  162.65
#Mann= 8 ,-1 , 0
  4291.1      .1       0  4859.3     .05       0  4928.4      .1       0
  4984.1     .07       0  4990.1      .1       0  5068.1     .05       0
  5245.1     .08       0  5344.1      .1       0
Bank Sta=4957,5053.73
XS Rating Curve= 0 ,0
Exp/Cntr=0.3,0.1

Type RM Length L Ch R = 1 ,9283    ,326,326,326
BEGIN DESCRIPTION:
UNT013 IN PECR 20.0
END DESCRIPTION:
XS GIS Cut Line= 4
       2330849.2     13255719.78      2330888.84     13255868.43
      2330921.88     13256512.62      2330908.66     13256651.41
#Sta/Elev= 30
  4687.8  139.73  4767.6  135.22  4798.6   132.1    4809  132.07  4890.1  125.91
  4943.9   120.9  4960.2   119.1  4970.2  117.38  4980.2  117.21  4990.3   114.1
  5007.3  114.04    5010  113.54  5013.3  114.04  5020.3  117.35  5040.3  117.93
  5050.3  119.59  5080.4  121.42  5160.5  119.74  5209.6  122.29  5270.6  127.68
  5308.7  133.09  5370.8  143.68  5407.7  144.19  5460.9  145.54    5501  148.44
  5551.2   153.1  5601.4  160.47  5611.5  161.11  5621.3  163.24  5626.1  163.24
#Mann= 7 ,-1 , 0
  4687.8      .1       0  4943.9     .05       0  5007.3     .03       0
  5013.3     .05       0  5209.6      .1       0  5308.7     .08       0
  5407.7      .1       0
Bank Sta=4960.2,5050.3
XS Rating Curve= 0 ,0
Exp/Cntr=0.3,0.1

Type RM Length L Ch R = 1 ,8957    ,397,397,397
BEGIN DESCRIPTION:
UNT013 IN PECR 19.0
END DESCRIPTION:
XS GIS Cut Line= 3
      2330717.09     13255719.35        2330545.     13256104.13
      2330547.81     13256633.51
#Sta/Elev= 30
  4648.4  145.27  4712.5   143.7  4735.7  141.44  4766.2  136.31  4851.7  127.78
  4880.4  126.11  4903.6  122.53  4955.4  117.92  4985.3  115.49  4993.2  112.89
    4996  112.39  4999.2  112.89  5018.1  113.47  5025.1  115.25  5047.2  117.13
  5082.6   118.4  5202.6  117.39  5242.6  119.16  5289.8  123.03  5388.6   132.3
  5472.6  140.37  5487.4  144.33  5512.6  149.92  5532.6  157.92  5542.6  157.63
  5552.6  161.58  5562.6  163.17  5572.6  166.77  5582.6   167.6  5599.3  172.26
#Mann= 7 ,-1 , 0
  4648.4      .1       0  4993.2     .07       0  4999.2      .1       0
  5047.2     .05       0  5289.8     .08       0  5388.6     .05       0
  5487.4      .1       0
Bank Sta=4955.4,5082.6
XS Rating Curve= 0 ,0
Exp/Cntr=0.3,0.1

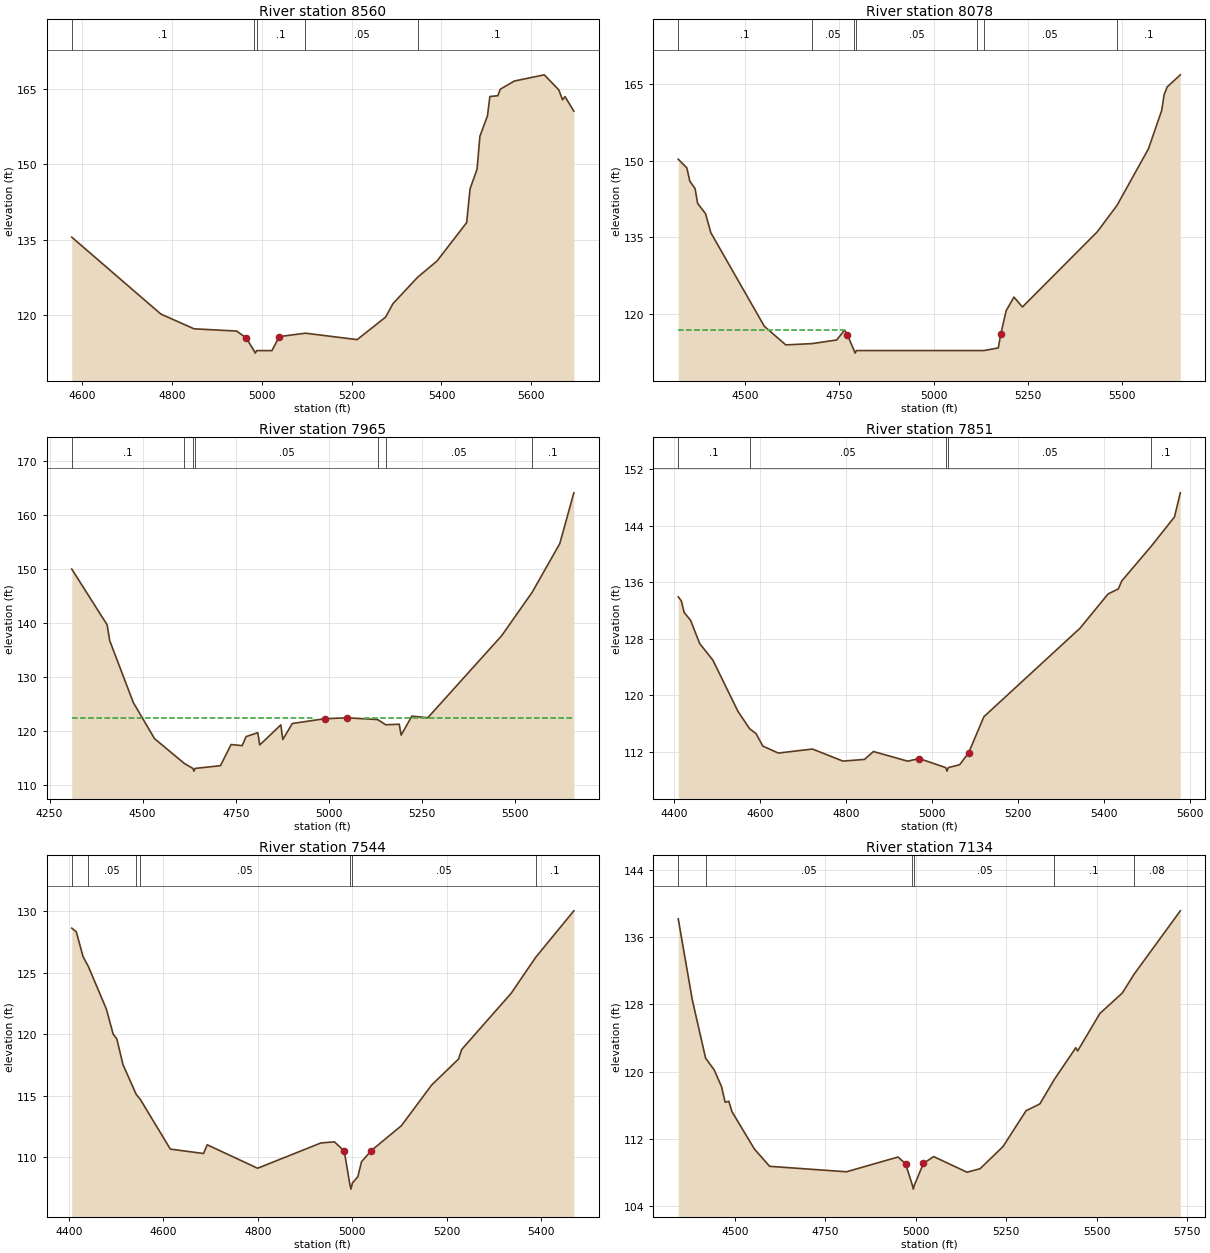
Type RM Length L Ch R = 1 ,8560    ,482,482,482
BEGIN DESCRIPTION:
UNT013 IN PECR 18.0
END DESCRIPTION:
XS GIS Cut Line= 4
      2330360.29     13255703.22      2330261.16     13255835.39
      2330056.34     13256449.85      2330181.88     13256727.36
#Sta/Elev= 30
  4577.2  135.47  4775.6  120.16  4849.4  117.23  4944.2  116.78  4965.3  115.43
  4982.8  112.89  4985.6  112.39  4988.8  112.89  5022.7  112.89  5039.1  115.68
  5097.3  116.36  5212.4  115.08  5275.7  119.56  5292.1  122.24  5346.8  127.48
  5390.1  130.72  5456.1  138.37  5463.7   145.1  5479.3  149.01  5485.6  155.57
  5502.4  159.59  5507.8  163.47  5525.5  163.63    5531  164.93  5562.4  166.56
  5628.9  167.79  5661.2   164.8  5669.6  162.82  5675.1  163.45  5694.7  160.55
#Mann= 5 ,-1 , 0
  4577.2      .1       0  4982.8     .07       0  4988.8      .1       0
  5097.3     .05       0  5346.8      .1       0
Bank Sta=4965.3,5039.1
XS Rating Curve= 0 ,0
Exp/Cntr=0.3,0.1

Type RM Length L Ch R = 1 ,8078    ,113,113,113
BEGIN DESCRIPTION:
Mapping XS e9152c8a
END DESCRIPTION:
XS GIS Cut Line= 6
      2330196.22     13255532.77      2329901.11     13255879.96
      2329779.59     13255919.02      2329710.14     13255997.15
      2329701.46     13256101.31      2329363.11     13256522.08
#Sta/Elev= 30
  4322.1  150.25    4345  148.56  4352.8  145.98  4366.8  144.51  4373.6  141.62
  4394.5  139.63  4408.7  135.89  4550.6  117.63  4607.5     114  4677.4  114.25
  4742.6  114.96  4763.5  116.89  4771.2  115.93  4788.8  112.89  4791.6  112.39
  4794.8  112.89  5114.8  112.89  5132.6  112.89  5171.4   113.4  5177.8  116.04
  5192.2  120.66    5213  123.33  5235.4   121.4  5433.8  136.06  5486.2  141.21
  5569.8  152.28    5605  159.76  5611.4  162.84  5619.4  164.35  5654.4  166.73
#Mann= 7 ,-1 , 0
  4322.1      .1       0  4677.4     .05       0  4788.8    .033       0
  4794.8     .05       0  5114.8     .07       0  5132.6     .05       0
  5486.2      .1       0
#XS Ineff= 2 , 0
         4763.49  116.89
Permanent Ineff=
       F       F
Bank Sta=4771.2,5177.8
XS Rating Curve= 0 ,0
Exp/Cntr=0.3,0.1

Type RM Length L Ch R = 1 ,7965    ,114,114,114
BEGIN DESCRIPTION:
UNT013 IN PECR 17.0
END DESCRIPTION:
XS GIS Cut Line= 6
      2330148.54     13255493.64      2329857.71      13255819.2
      2329637.72     13255896.85      2329588.61     13256023.19
      2329605.98     13256118.67      2329315.19      13256457.2
#Sta/Elev= 30
  4309.6  150.06  4404.7  139.72  4411.4  136.82    4475  125.32  4531.8  118.65
  4611.8  114.05    4635  113.12  4637.7  112.62    4641  113.12    4709  113.63
  4737.5  117.55  4767.3  117.34  4777.9  119.02  4809.3  119.74  4814.6  117.47
  4871.2  121.19  4876.5  118.48  4902.1  121.45    4989  122.33  5048.8   122.5
  5131.2  122.18    5153  121.21  5189.3  121.31  5194.4   119.3  5223.2  122.81
    5266  122.51  5464.6  137.73  5546.4  145.77  5620.5  154.78  5658.3  164.19
#Mann= 7 ,-1 , 0
  4309.6      .1       0  4611.8     .05       0    4635     .03       0
    4641     .05       0  5131.2     .07       0    5153     .05       0
  5546.4      .1       0
#XS Ineff= 2 , 0
       0 4959.81  122.47 5098.24       0  122.45
Permanent Ineff=
       T       T
Bank Sta=4989,5048.8
XS Rating Curve= 0 ,0
Exp/Cntr=0.3,0.1

Type RM Length L Ch R = 1 ,7851    ,307,307,307
BEGIN DESCRIPTION:
Mapping XS 248130e4
END DESCRIPTION:
XS GIS Cut Line= 4
      2330029.47     13255508.31      2329839.39     13255625.49
      2329435.75     13255922.36      2329266.88     13256332.82
#Sta/Elev= 30
  4410.2  133.94  4417.5  133.36    4424  131.73  4438.8  130.63  4460.1  127.33
  4490.9  124.97  4548.9  117.75  4576.1  115.27  4591.4  114.56  4606.8  112.81
    4643  111.81  4722.4  112.38  4793.4  110.67  4843.6  110.91  4864.4  112.03
  4943.9  110.66  4970.9  111.03  5032.7  109.75  5035.5  109.25  5038.7  109.75
    5065  110.16  5085.9  111.85  5121.4  116.96  5344.9  129.49  5410.3  134.35
  5434.2  135.07  5442.2   136.2  5509.9  141.05  5564.8  145.26  5578.4  148.68
#Mann= 5 ,-1 , 0
  4410.2      .1       0  4576.1     .05       0  5032.7     .03       0
  5038.7     .05       0  5509.9      .1       0
Bank Sta=4970.9,5085.9
XS Rating Curve= 0 ,0
Exp/Cntr=0.3,0.1

Type RM Length L Ch R = 1 ,7544    ,410,410,410
BEGIN DESCRIPTION:
UNT013 IN PECR 16.0
END DESCRIPTION:
XS GIS Cut Line= 3
      2329821.16     13255216.63      2329162.31     13255763.51
      2329120.64     13255966.63
#Sta/Elev= 30
  4405.7  128.63  4415.3  128.33  4429.6  126.31  4440.6  125.53  4479.1  122.03
  4493.4     120  4501.1  119.62  4514.2  117.52  4542.3  115.09    4551  114.68
  4614.5  110.64  4684.8  110.28  4692.6  110.99  4799.4  109.08  4933.5  111.14
  4962.2  111.23    4983  110.47  4994.3  107.88  4997.1  107.38  5000.3  107.88
  5011.7  108.39  5019.5  109.61  5040.3  110.52  5104.1  112.55  5167.9  115.85
  5225.2  117.98  5231.7  118.75  5336.8  123.34  5388.4  126.25  5469.3  130.04
#Mann= 7 ,-1 , 0
  4405.7      .1       0  4440.6     .05       0  4542.3      .1       0
    4551     .05       0  4994.3     .03       0  5000.3     .05       0
  5388.4      .1       0
Bank Sta=4983,5040.3
XS Rating Curve= 0 ,0
Exp/Cntr=0.3,0.1

Type RM Length L Ch R = 1 ,7134    ,418,418,418
BEGIN DESCRIPTION:
UNT013 IN PECR 15.0
END DESCRIPTION:
XS GIS Cut Line= 4
      2329636.24     13254971.84      2329420.12     13255000.49
      2328855.02     13255503.09      2328748.24     13255901.55
#Sta/Elev= 30
  4343.8  138.22  4382.7  128.54  4419.4   121.6  4443.2  120.19  4463.4  118.19
  4473.4  116.33  4483.5  116.46  4492.3  115.21  4554.1  110.76  4596.2  108.69
  4808.6  108.04  4950.8   109.8  4971.7     109  4990.3  106.47    4993  105.97
  4996.3  106.47    5021  109.04  5049.4  109.85  5141.4  107.99  5177.4   108.4
  5240.9  111.05  5304.5  115.32  5342.7  116.14  5382.4  119.04    5442  122.84
  5447.1  122.46  5508.3  126.92  5570.5  129.37  5602.8   131.6  5730.6  139.17
#Mann= 6 ,-1 , 0
  4343.8      .1       0  4419.4     .05       0  4990.3     .03       0
  4996.3     .05       0  5382.4      .1       0  5602.8     .08       0
Bank Sta=4971.7,5021
XS Rating Curve= 0 ,0
Exp/Cntr=0.3,0.1