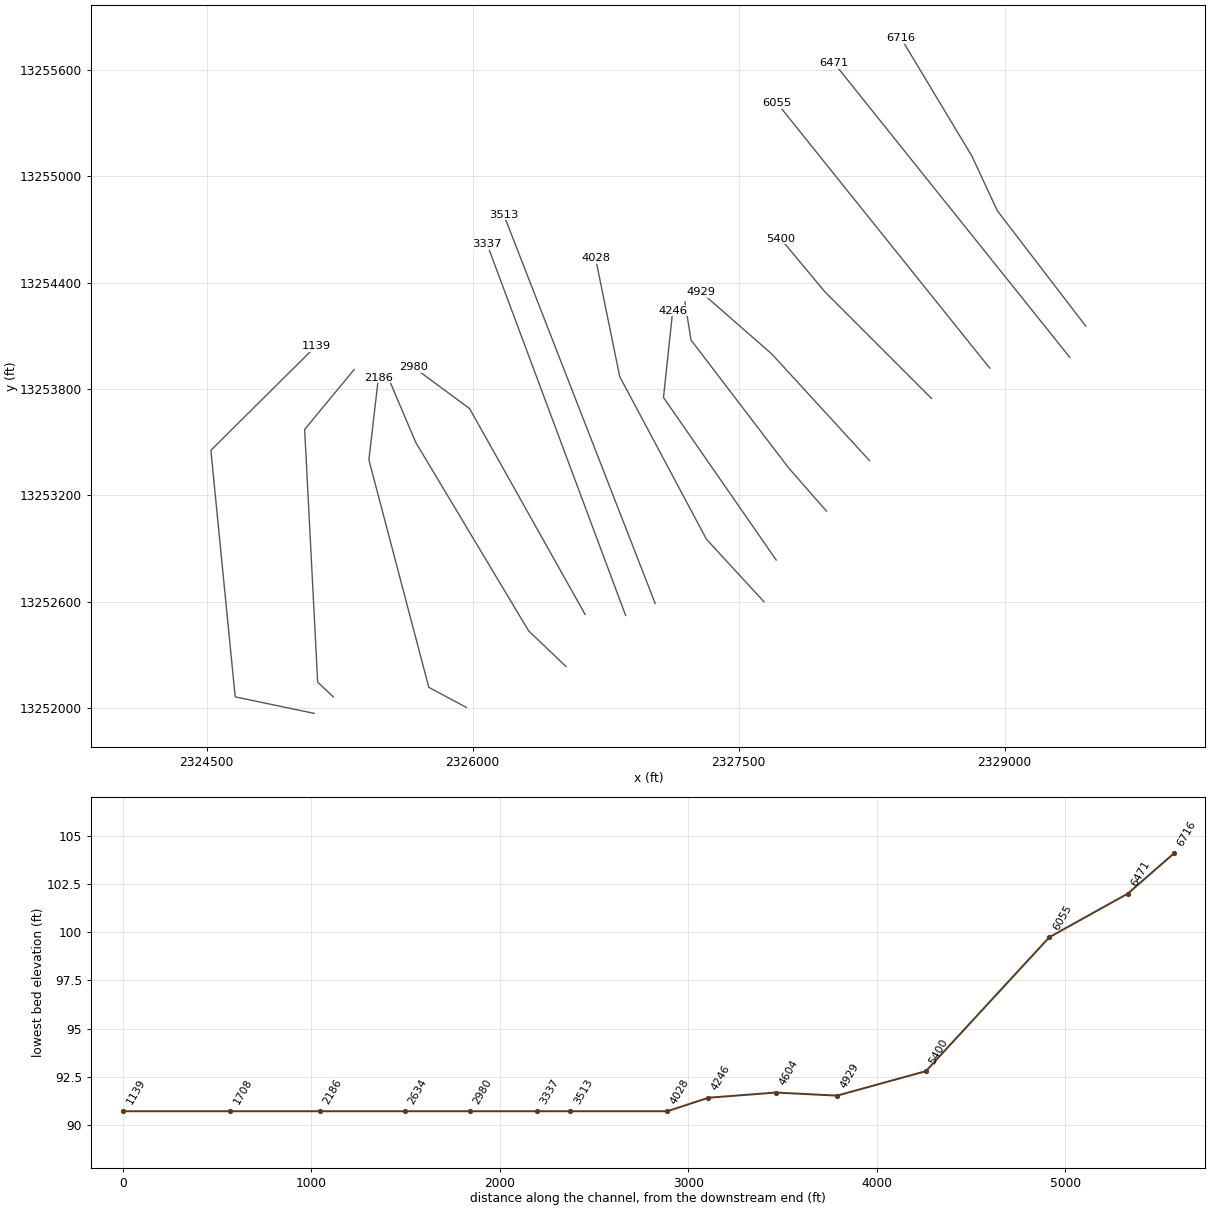
HEC-RAS study UNT013 IN PECR.prj: UNT013 IN PECR Base Level Engineering

--- UNT013 IN PECR.g01 (geometry) --- (continued)

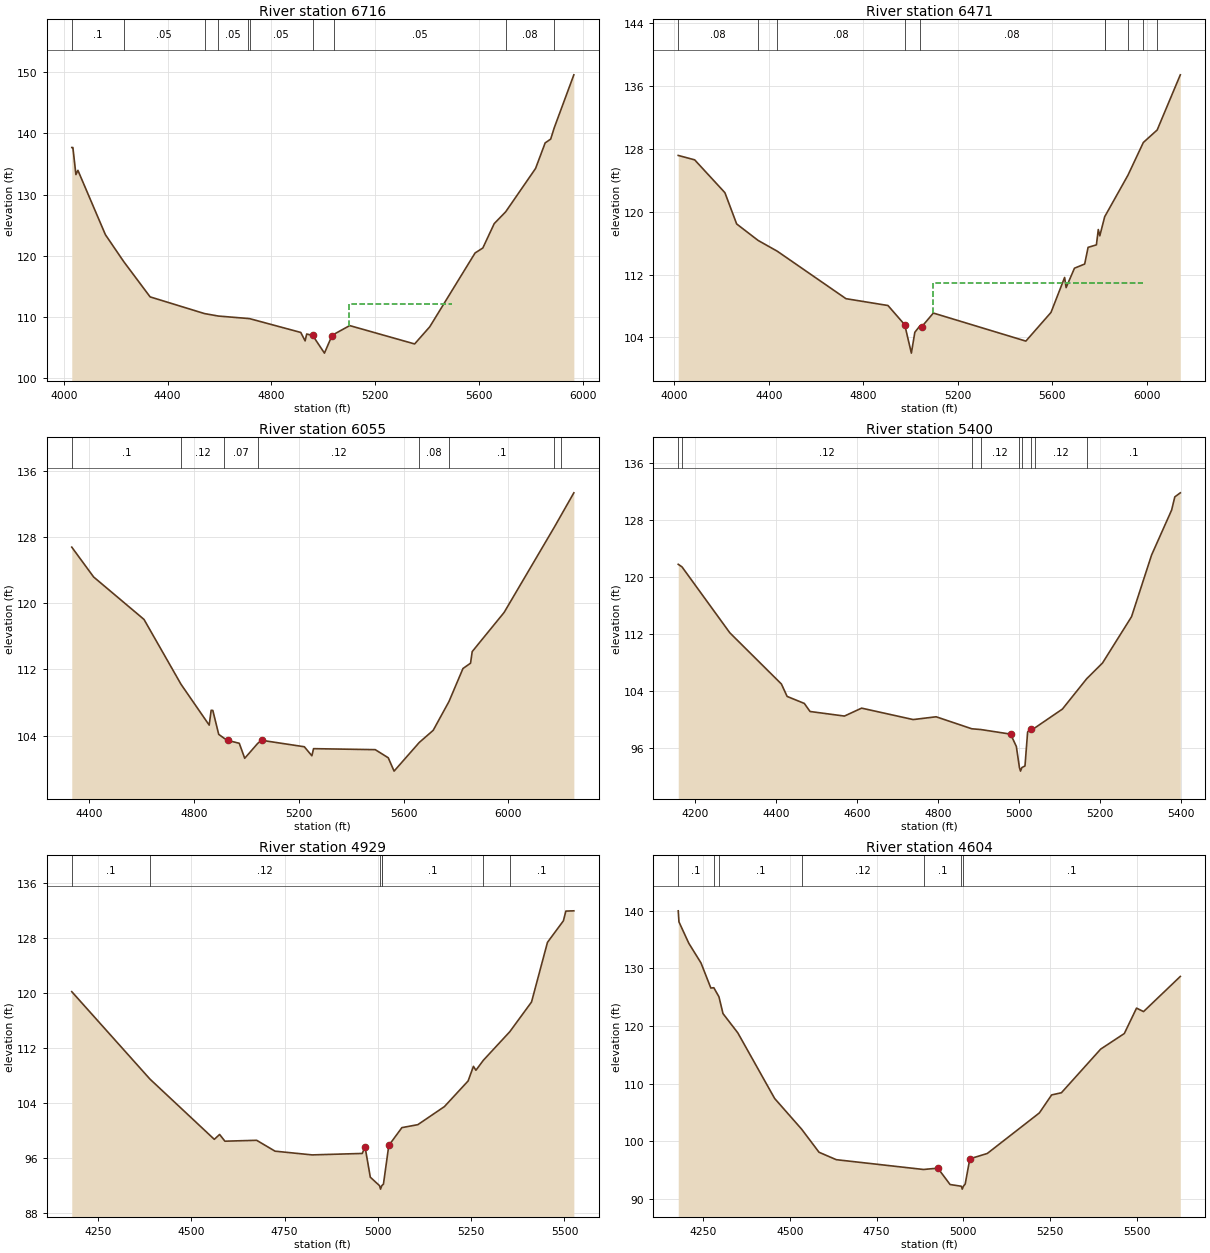
Type RM Length L Ch R = 1 ,6716    ,245,245,245
BEGIN DESCRIPTION:
UNT013 IN PECR 14.0
END DESCRIPTION:
XS GIS Cut Line= 4
      2329457.95     13254154.17      2328958.82     13254805.22
      2328815.59     13255113.38      2328416.26     13255777.48
#Sta/Elev= 30
  4030.8  137.69  4035.1  137.69  4046.8  133.27  4054.5  133.96  4160.5  123.44
  4230.7  119.07  4332.8  113.28  4542.6  110.55  4595.8  110.15  4710.3  109.75
  4717.6  109.71  4913.4  107.47  4930.2  106.09  4936.2  107.21  4959.1  106.99
  5004.7  104.09  5033.3  106.91  5040.4  107.15    5102  108.59  5352.2  105.59
  5410.5  108.39  5585.3  120.46  5615.1  121.27  5659.1  125.26  5703.1  127.18
  5818.4  134.27  5855.3  138.44  5876.7  139.07  5890.4  140.92  5965.9  149.57
#Mann= 10 ,-1 , 0
  4030.8      .1       0  4230.7     .05       0  4542.6      .1       0
  4595.8     .05       0  4710.3      .1       0  4717.6     .05       0
  4959.1     .03       0  5040.4     .05       0  5703.1     .08       0
  5890.4      .1       0
#XS Ineff= 1 ,-1
 5099.88 5495.12112.0701
Permanent Ineff=
       F
Bank Sta=4959.1,5033.3
XS Rating Curve= 0 ,0
Exp/Cntr=0.3,0.1

Type RM Length L Ch R = 1 ,6471    ,416,416,416
BEGIN DESCRIPTION:
UNT013 IN PECR 13.0
END DESCRIPTION:
XS GIS Cut Line= 2
      2329367.24     13253978.95      2328039.14      13255636.9
#Sta/Elev= 30
  4016.9  127.16  4086.4   126.6  4214.4  122.42  4264.1  118.44    4355  116.34
    4436  114.97  4726.6  108.93  4904.3  108.06  4975.2  105.61  5003.3     102
  5017.9  104.65  5039.2  105.46  5046.7  105.34  5096.3   107.1  5487.7  103.53
  5594.1  107.18  5651.7  111.63  5658.1  110.34  5693.4  112.81  5736.6  113.34
    5751  115.46  5786.2  115.78  5794.2  117.73  5800.6  116.93  5821.4  119.38
  5821.8  119.39  5919.6  124.64  5984.8  128.81  6043.3   130.4  6141.2  137.42
#Mann= 10 ,-1 , 0
  4016.9     .08       0    4355      .1       0    4436     .08       0
  4975.2     .05       0  5039.2     .08       0  5821.4     .08       0
  5821.8      .1       0  5919.6     .08       0  5984.8      .1       0
  6043.3     .08       0
#XS Ineff= 1 ,-1
 5096.59 5981.53  110.91
Permanent Ineff=
       F
Bank Sta=4975.2,5046.7
XS Rating Curve= 0 ,0
Exp/Cntr=0.3,0.1

Type RM Length L Ch R = 1 ,6055    ,655,655,655
BEGIN DESCRIPTION:
UNT013 IN PECR 12.0
END DESCRIPTION:
XS GIS Cut Line= 2
       2328915.9     13253918.12      2327717.93     13255411.24
#Sta/Elev= 30
    4335  126.76  4418.3  123.16  4610.4  118.04  4751.7  110.21    4859  105.29
  4866.4  107.08  4872.8  107.06  4895.2  104.18    4916   103.7  4930.4  103.44
  4973.6   103.1  4994.4  101.29  5044.1  103.09  5058.5  103.46  5221.7  102.68
  5250.5  101.59  5256.9  102.45  5492.1  102.33  5541.7  101.35  5563.9   99.74
    5660   103.2    5713  104.66  5773.4  108.15  5826.6  112.12  5855.4  112.76
  5861.8  114.16  5983.4  118.88  6174.7  129.16  6200.6   130.6  6249.3  133.31
#Mann= 8 ,-1 , 0
    4335      .1       0  4751.7     .12       0    4916     .07       0
  5044.1     .12       0    5660     .08       0  5773.4      .1       0
  6174.7     .08       0  6200.6      .1       0
Bank Sta=4930.4,5058.5
XS Rating Curve= 0 ,0
Exp/Cntr=0.3,0.1

Type RM Length L Ch R = 1 ,5400    ,471,471,471
BEGIN DESCRIPTION:
UNT013 IN PECR 11.0
END DESCRIPTION:
XS GIS Cut Line= 3
      2328587.72     13253746.85      2327987.72     13254346.85
      2327737.75     13254646.82
#Sta/Elev= 30
  4159.3  121.75  4168.6  121.39  4286.6  112.16  4413.9  104.99    4428  103.25
  4470.4  102.27  4484.6  101.14  4569.4   100.5  4611.8  101.61  4739.1  100.01
  4795.7   100.4  4883.7   98.72  4906.4   98.61  4979.5   97.97  4993.7   96.24
  5001.3   93.29    5004   92.79  5007.3   93.29    5015   93.51  5021.5   98.27
  5028.8   98.74  5039.5   98.85  5107.4  101.48  5167.3  105.73  5206.3  107.93
  5277.9  114.41  5327.4  123.05  5376.9  129.35  5384.7  131.19  5398.3  131.76
#Mann= 9 ,-1 , 0
  4159.3     .16       0  4168.6     .12       0  4883.7      .1       0
  4906.4     .12       0  5001.3     .07       0  5007.3     .12       0
  5028.8      .1       0  5039.5     .12       0  5167.3      .1       0
Bank Sta=4979.5,5028.8
XS Rating Curve= 0 ,0
Exp/Cntr=0.3,0.1

Type RM Length L Ch R = 1 ,4929    ,325,325,325
BEGIN DESCRIPTION:
UNT013 IN PECR 10.0
END DESCRIPTION:
XS GIS Cut Line= 3
      2328237.75     13253396.82      2327687.72     13253996.85
      2327287.72     13254346.86
#Sta/Elev= 30
  4179.7  120.19  4389.2   107.5  4561.7   98.75  4575.9   99.46  4590.1   98.48
  4675.2   98.61  4724.5   97.03  4823.8   96.49  4958.2    96.7  4965.6   97.67
  4979.8   93.25  5004.5   92.02  5007.2   91.52  5010.5   92.02  5011.9   92.09
    5015   92.26  5029.3   97.86  5064.4  100.45  5107.1  100.88  5178.3   103.5
  5241.9  107.23  5256.1  109.35  5262.8  108.78  5282.7  110.23  5353.6  114.38
  5411.8  118.69  5454.5  127.35  5497.2  130.48  5503.8  131.89  5525.2  131.93
#Mann= 7 ,-1 , 0
  4179.7      .1       0  4389.2     .12       0  5004.5     .07       0
  5010.5     .12       0  5011.9      .1       0  5282.7     .16       0
  5353.6      .1       0
Bank Sta=4965.6,5029.3
XS Rating Curve= 0 ,0
Exp/Cntr=0.3,0.1

Type RM Length L Ch R = 1 ,4604    ,358,358,358
BEGIN DESCRIPTION:
UNT013 IN PECR 9.0
END DESCRIPTION:
XS GIS Cut Line= 4
      2327995.38     13253111.77      2327784.86     13253351.67
      2327231.63     13254076.26      2327197.36     13254291.63
#Sta/Elev= 30
  4177.4  139.99  4179.5  138.07  4207.9  134.36  4243.1  130.94  4271.5  126.59
  4280.1  126.64  4294.9  125.07  4306.6  122.15  4349.3  118.81  4455.6  107.42
  4533.6  102.08  4583.7   98.08  4633.6   96.79  4885.2   95.09  4926.6   95.32
  4961.9   92.48  4994.3   92.18    4997   91.68  5000.3   92.18  5005.5   92.56
  5018.9   96.94  5069.3   97.87  5219.6  104.91  5254.9  108.03  5283.2  108.41
  5396.4  115.98  5464.7  118.69    5500   123.1  5520.2   122.5  5626.3   128.6
#Mann= 7 ,-1 , 0
  4177.4      .1       0  4280.1     .08       0  4294.9      .1       0
  4533.6     .12       0  4885.2      .1       0  4994.3     .07       0
  5000.3      .1       0
Bank Sta=4926.6,5018.9
XS Rating Curve= 0 ,0
Exp/Cntr=0.3,0.1

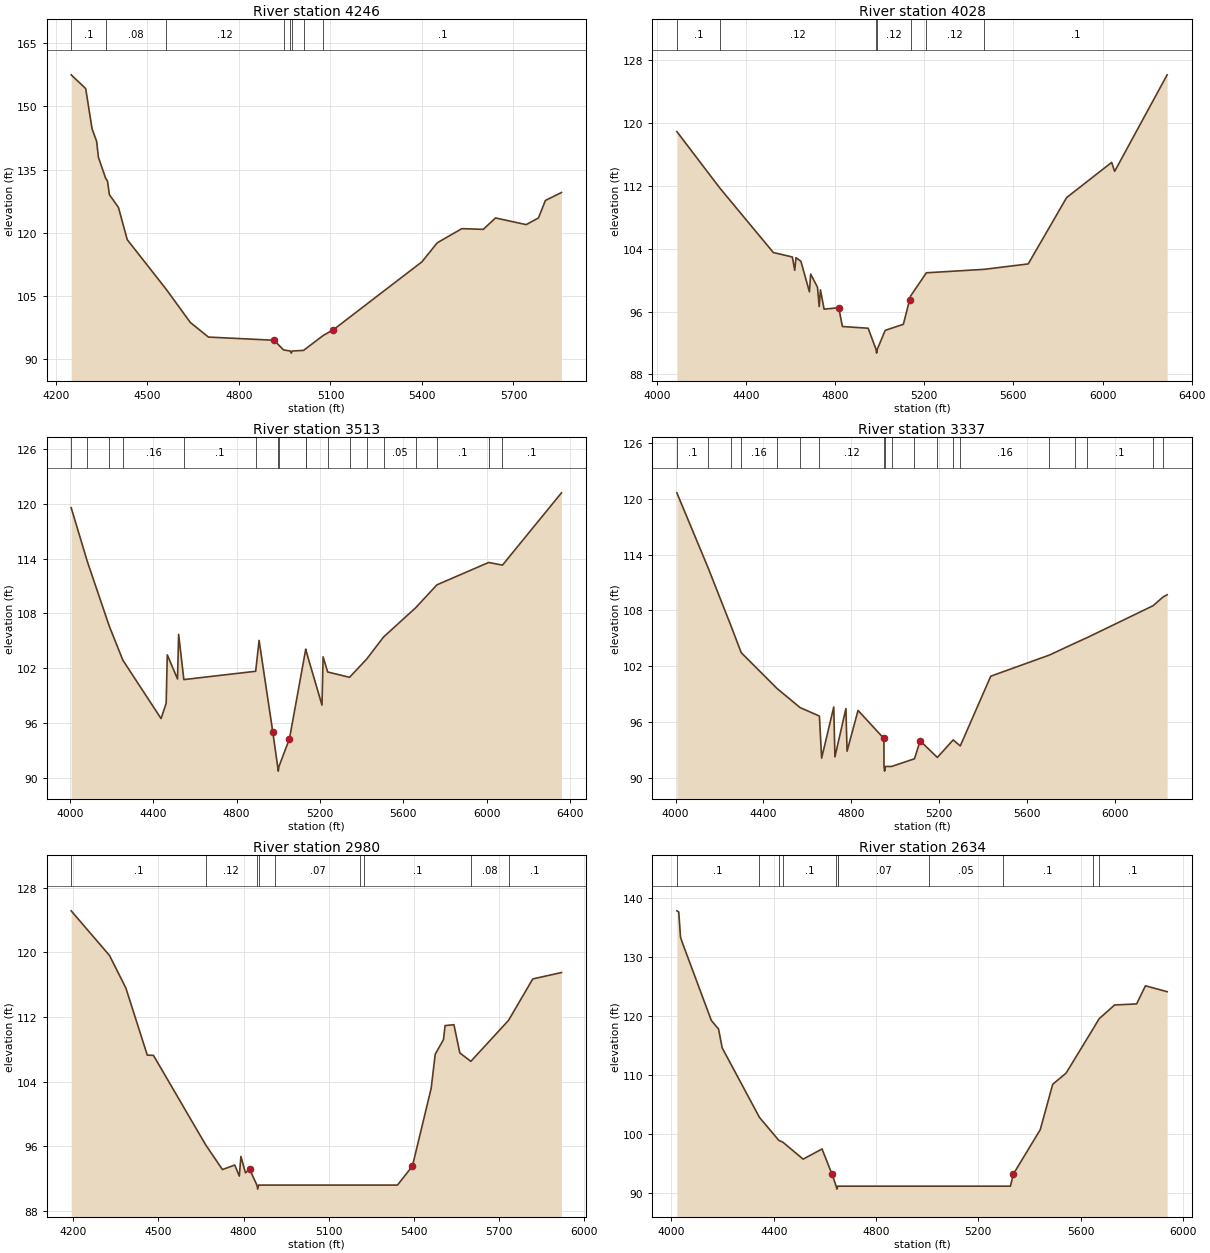
Type RM Length L Ch R = 1 ,4246    ,218,218,218
BEGIN DESCRIPTION:
UNT013 IN PECR 8.0
END DESCRIPTION:
XS GIS Cut Line= 3
      2327711.86     13252835.72      2327076.46     13253752.36
      2327128.54     13254241.87
#Sta/Elev= 30
  4249.8   157.5  4297.4  154.24  4318.3  144.68  4333.2  141.72  4339.2  137.89
  4362.6  132.98    4369  132.25  4375.1  129.04  4404.8  126.01  4433.7  118.35
    4561  106.61  4640.5   98.69    4700   95.22  4914.8   94.47  4946.3   92.17
  4968.6   91.91  4971.3   91.41  4974.6   91.91  5011.7   92.06  5076.6   95.62
  5108.7   96.92  5399.8  113.09  5450.1  117.61  5530.6  120.97  5600.9   120.8
  5641.2  123.51  5741.7  121.93    5782  123.51  5804.8  127.67  5857.4  129.55
#Mann= 8 ,-1 , 0
  4249.8      .1       0  4362.6     .08       0    4561     .12       0
  4946.3      .1       0  4968.6     .07       0  4974.6      .1       0
  5011.7     .12       0  5076.6      .1       0
Bank Sta=4914.8,5108.7
XS Rating Curve= 0 ,0
Exp/Cntr=0.3,0.1

Type RM Length L Ch R = 1 ,4028    ,515,515,515
BEGIN DESCRIPTION:
Mapping XS e58f43b3
END DESCRIPTION:
XS GIS Cut Line= 4
      2327643.17     13252600.26      2327318.68     13252952.97
      2326829.63     13253869.93      2326693.27     13254537.66
#Sta/Elev= 30
    4090  118.92  4283.7   111.7    4523  103.52  4608.3  102.95  4618.9  101.25
  4624.5  102.86  4646.5  102.41  4684.8   98.52  4690.4  100.78    4721    99.1
  4728.7   96.64  4734.3   98.77  4750.6   96.31  4816.5   96.49  4832.8    94.1
  4948.3   93.88  4983.5   91.21  4986.3   90.71  4989.5   91.21  5024.8   93.61
  5106.3   94.38  5134.5   97.51  5138.4   97.97  5209.7  100.94  5469.1  101.38
  5666.6  102.07    5839  110.52    6041     115  6054.4  113.86    6290  126.15
#Mann= 7 ,-1 , 0
    4090      .1       0  4283.7     .12       0  4983.5     .07       0
  4989.5     .12       0  5138.4     .08       0  5209.7     .12       0
  5469.1      .1       0
Bank Sta=4816.5,5134.5
XS Rating Curve= 0 ,0
Exp/Cntr=0.3,0.1

Type RM Length L Ch R = 1 ,3513    ,176,176,176
BEGIN DESCRIPTION:
UNT013 IN PECR 7.0
END DESCRIPTION:
XS GIS Cut Line= 2
      2327029.58     13252590.92      2326175.78     13254782.69
#Sta/Elev= 30
    4006  119.57  4083.9  113.65  4188.7   106.6  4254.1  102.86  4437.2   96.47
  4461.7   98.14  4467.1  103.45  4516.1  100.81  4521.5  105.69  4546.6  100.74
  4891.1  101.65  4907.5  105.03 4973.01   95.04  4996.7   91.21  4999.5   90.71
  5002.7   91.21  5053.4   94.27  5131.4  104.08  5131.9  103.97  5209.3   97.94
  5214.6  103.23  5236.7  101.57  5341.5  100.99  5423.8  102.99  5504.5   105.4
  5658.8  108.61  5760.7  111.12  6008.7  113.57  6075.2  113.28  6358.2   121.2
#Mann= 18 ,-1 , 0
    4006      .1       0  4083.9     .16       0  4188.7     .12       0
  4254.1     .16       0  4546.6      .1       0  4891.1     .12       0
  4996.7     .07       0  5002.7     .12       0  5131.4     .16       0
  5131.9      .1       0  5236.7     .16       0  5341.5     .12       0
  5423.8     .16       0  5504.5     .05       0  5658.8     .16       0
  5760.7      .1       0  6008.7     .16       0  6075.2      .1       0
Bank Sta=4973.01,5053.4
XS Rating Curve= 0 ,0
Exp/Cntr=0.3,0.1

Type RM Length L Ch R = 1 ,3337    ,357,357,357
BEGIN DESCRIPTION:
UNT013 IN PECR 6.0
END DESCRIPTION:
XS GIS Cut Line= 2
      2326862.92     13252523.18      2326082.18     13254615.56
#Sta/Elev= 30
  4005.5  120.64  4149.3  112.49  4253.6  106.24  4298.7  103.45  4462.2   99.59
  4566.5   97.55  4654.8   96.63  4664.9   92.11  4720.2   97.61  4725.5   92.24
  4775.5   97.44  4780.8   92.85  4830.8   97.24 4948.64   94.22    4949   91.21
  4951.8   90.71    4955   91.21  4983.6   91.21  5087.9   92.04 5113.58   93.97
  5192.1   92.18  5264.2   94.07  5296.4   93.42  5435.3  100.92    5702  103.19
  5817.8  104.46  5873.6  105.06  6174.8   108.5  6220.7  109.45  6238.8  109.68
#Mann= 19 ,-1 , 0
  4005.5      .1       0  4149.3     .16       0  4253.6      .1       0
  4298.7     .16       0  4462.2      .1       0  4566.5     .16       0
  4654.8     .12       0    4949    .033       0    4955     .12       0
  4983.6     .05       0  5087.9      .1       0  5192.1     .16       0
  5264.2      .1       0  5296.4     .16       0    5702      .1       0
  5817.8     .16       0  5873.6      .1       0  6174.8     .16       0
  6220.7      .1       0
Bank Sta=4948.64,5113.58
XS Rating Curve= 0 ,0
Exp/Cntr=0.3,0.1

Type RM Length L Ch R = 1 ,2980    ,346,346,346
BEGIN DESCRIPTION:
UNT013 IN PECR 5.0
END DESCRIPTION:
XS GIS Cut Line= 3
      2326634.34     13252529.17      2325983.19     13253689.49
      2325664.99     13253924.47
#Sta/Elev= 30
  4193.1  125.12  4328.1   119.6  4385.7  115.57    4461  107.28  4482.7  107.25
  4666.7   96.18  4725.7   93.13    4769   93.69    4785   92.32  4790.7   94.75
  4806.7   92.72  4821.1   93.17    4847   91.21  4849.8   90.71    4853   91.21
  4912.4   91.21  5209.8   91.21  5223.8   91.21  5341.8   91.21  5394.5   93.56
  5460.4  103.16  5474.8  107.39  5503.8   109.2  5509.5  110.93  5540.6  111.04
  5561.4  107.55  5600.2  106.51  5732.9  111.58  5818.2   116.7  5919.2  117.49
#Mann= 9 ,-1 , 0
  4193.1      .1       0  4666.7     .12       0    4847     .07       0
    4853     .12       0  4912.4     .07       0  5209.8     .05       0
  5223.8      .1       0  5600.2     .08       0  5732.9      .1       0
Bank Sta=4821.1,5394.5
XS Rating Curve= 0 ,0
Exp/Cntr=0.3,0.1

Type RM Length L Ch R = 1 ,2634    ,448,448,448
BEGIN DESCRIPTION:
UNT013 IN PECR 4.0
END DESCRIPTION:
XS GIS Cut Line= 4
      2326526.65      13252235.4      2326316.11     13252436.15
      2325679.65     13253498.55      2325527.86     13253855.99
#Sta/Elev= 30
  4021.2  137.86  4028.6  137.67  4035.5  133.41  4042.7  132.46    4156  119.29
  4184.3  117.83  4198.4  114.65  4344.2  102.87  4419.5   98.99  4436.2   98.65
  4515.1   95.79    4589   97.51 4628.16   93.23  4644.3   91.21  4647.1   90.71
  4650.3   91.21  4653.2   91.21  5008.5   91.21    5296   91.21  5325.9   91.21
 5337.79   93.29  5442.6  100.79  5491.2  108.47  5543.7  110.37  5649.9  117.91
  5672.6  119.57  5733.4  121.91  5819.5  122.09    5854  125.16  5938.9  124.16
#Mann= 11 ,-1 , 0
  4021.2      .1       0  4344.2     .05       0  4419.5     .16       0
  4436.2      .1       0  4644.3     .07       0  4650.3      .1       0
  4653.2     .07       0  5008.5     .05       0    5296      .1       0
  5649.9     .08       0  5672.6      .1       0
Bank Sta=4628.16,5337.79
XS Rating Curve= 0 ,0
Exp/Cntr=0.3,0.1

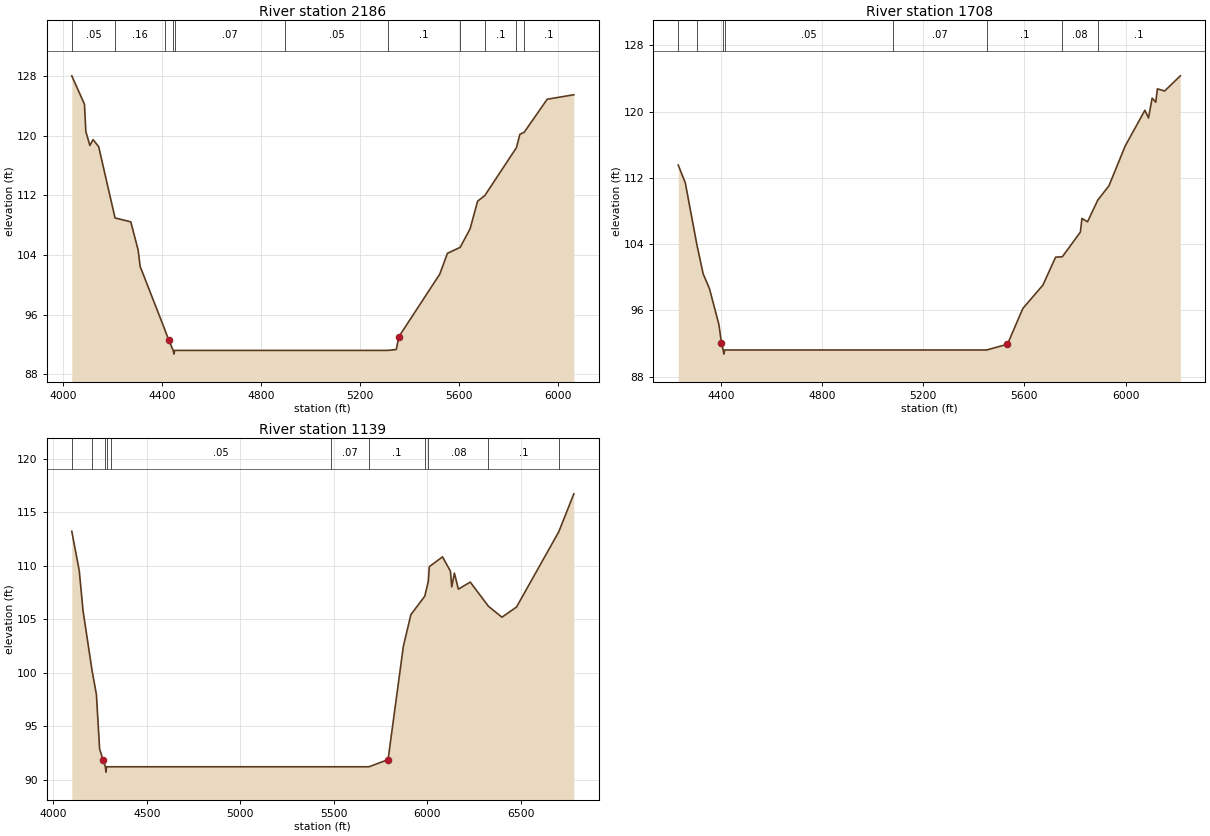
Type RM Length L Ch R = 1 ,2186    ,478,478,478
BEGIN DESCRIPTION:
UNT013 IN PECR 3.0
END DESCRIPTION:
XS GIS Cut Line= 4
      2325963.64      13252005.3      2325753.09     13252117.92
      2325415.27     13253400.63       2325468.9     13253863.81
#Sta/Elev= 30
    4034  128.06  4085.4  124.25    4091  120.58  4107.3  118.71  4120.1   119.5
  4142.8  118.56  4209.1  108.99  4272.8  108.46  4302.7  104.66  4310.7  102.48
  4409.3   94.11  4426.5   92.57  4444.5   91.21  4447.2   90.71  4450.5   91.21
  4897.4   91.21  5312.2   91.21  5347.1   91.33  5357.5   93.05  5522.9  101.44
    5554  104.24  5605.6  105.04  5645.8  107.54    5676  111.23  5705.4     112
  5833.4  118.43  5847.1  120.21  5864.7  120.49  5957.8  124.92  6065.5  125.52
#Mann= 11 ,-1 , 0
    4034     .05       0  4209.1     .16       0  4409.3     .07       0
  4444.5    .033       0  4450.5     .07       0  4897.4     .05       0
  5312.2      .1       0  5605.6     .08       0  5705.4      .1       0
  5833.4     .08       0  5864.7      .1       0
Bank Sta=4426.5,5357.5
XS Rating Curve= 0 ,0
Exp/Cntr=0.3,0.1

Type RM Length L Ch R = 1 ,1708    ,569,569,569
BEGIN DESCRIPTION:
UNT013 IN PECR 2.0
END DESCRIPTION:
XS GIS Cut Line= 4
      2325214.53     13252064.08      2325126.42      13252147.3
      2325052.98     13253571.99      2325332.02     13253909.77
#Sta/Elev= 30
  4230.9  113.54  4258.8  111.41  4305.4  103.81  4329.6   100.4  4354.4   98.62
  4391.7    94.3  4401.7   92.08  4408.7   91.21  4411.5   90.71  4414.7   91.21
  5079.6   91.21  5450.7   91.21  5533.2   91.91  5593.9   96.22  5673.4   99.05
  5723.5  102.42  5750.2  102.47  5821.4  105.45  5827.9   107.1  5849.8  106.69
  5890.3  109.31  5934.7  111.05  5998.5  115.83  6076.7  120.16    6091  119.23
  6105.4  121.63  6119.7  121.14  6126.2  122.75  6154.9  122.49  6216.8  124.32
#Mann= 8 ,-1 , 0
  4230.9     .16       0  4305.4     .05       0  4408.7    .033       0
  4414.7     .05       0  5079.6     .07       0  5450.7      .1       0
  5750.2     .08       0  5890.3      .1       0
Bank Sta=4401.7,5533.2
XS Rating Curve= 0 ,0
Exp/Cntr=0.3,0.1

Type RM Length L Ch R = 1 ,1139    ,0,0,0
BEGIN DESCRIPTION:
UNT013 IN PECR 1.0
END DESCRIPTION:
XS GIS Cut Line= 4
      2325106.85     13251971.04      2324661.31     13252064.07
      2324524.23     13253454.49      2325116.54      13254041.9
#Sta/Elev= 30
  4098.1  113.22  4138.1  109.55  4158.5  105.79  4206.9  100.18    4230   97.96
  4247.1   92.88 4265.17   91.86  4278.1   91.21  4280.8   90.71  4284.1   91.21
  4307.8   91.21  5485.4   91.21  5688.1   91.21 5790.55   91.88  5872.4  102.47
  5912.6  105.43  5986.9  107.15  6006.1  108.55  6011.1  109.91  6081.9  110.83
  6124.3  109.49  6131.3  108.02  6145.5  109.31  6166.7  107.81  6230.3  108.47
  6327.7  106.21    6400  105.19  6477.8  106.14  6703.9  113.17  6784.6  116.72
#Mann= 11 ,-1 , 0
  4098.1     .16       0  4206.9      .1       0  4278.1    .033       0
  4284.1      .1       0  4307.8     .05       0  5485.4     .07       0
  5688.1      .1       0  5986.9     .05       0  6006.1     .08       0
  6327.7      .1       0  6703.9     .08       0
Bank Sta=4265.17,5790.55
XS Rating Curve= 0 ,0
Exp/Cntr=0.3,0.1

Chan Stop Cuts=-1
Use User Specified Reach Order=0
Composite Channel Slope=5