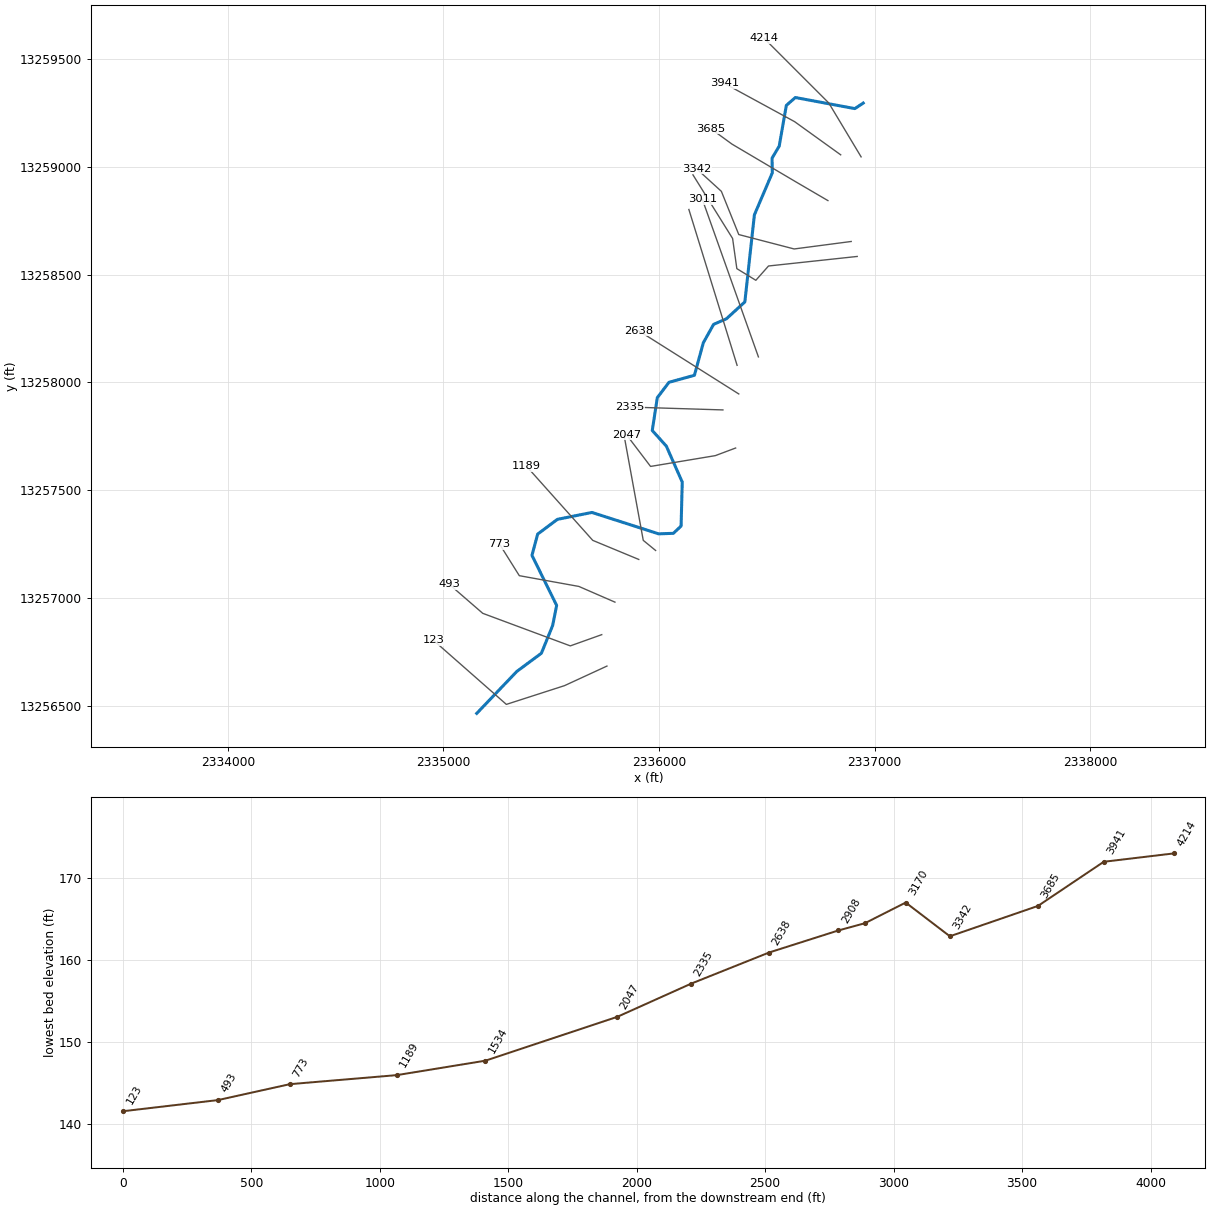
--- UNT014 IN PECR.prj (project) ---

Proj Title=UNT014 IN PECR Base Level Engineering
Current Plan=p01
Default Exp/Contr=0.3,0.1
English Units
Geom File=g01
Flow File=f01
Plan File=p01
Y Axis Title=Elevation
X Axis Title(PF)=Main Channel Distance
X Axis Title(XS)=Station
BEGIN DESCRIPTION:
UNT014 IN PECR
END DESCRIPTION:
DSS Export Rating Curves= 0
DSS Export Rating Curve Sorted= 0
DSS Export Volume Flow Curves= 0
DXF OffsetX= 0
DXF OffsetY= 0
DXF ScaleX= 1
DXF ScaleY= 10

--- UNT014 IN PECR.p01 (plan) ---

Plan Title=Multiple Run
Short Identifier=Multiple
Geom File=g01
Flow File=f01
Subcritical Flow
K Sum by GR= 0
Std Step Tol= 0.01
Critical Tol= 0.01
Num of Std Step Trials= 20
Max Error Tol= 0.3
Flow Tol Ratio= 0.001
Split Flow NTrial= 30
Split Flow Tol= 0.02
Split Flow Ratio= 0.02
Log Output Level= 0
Friction Slope Method= 1
Unsteady Friction Slope Method= 2
Unsteady Bridges Friction Slope Method= 1
Parabolic Critical Depth
Global Vel Dist=  1 , 1 , 1
Global Log Level= 0
CheckData=True
Encroach Param= -1, 0, 0, 0
BEGIN DESCRIPTION:
Multiple Run
END DESCRIPTION:

--- UNT014 IN PECR.f01 (steady flow) ---

Flow Title=Multiple
Program Version=4.10
Number of Profiles= 7
Profile Names=10-year,25-year,50-year,1pct_min,100-year,1pct_plu,500-year
River Rch & RM=UNT014 IN PECR,Reach-1         ,4214
     503     692     847     757    1023    1384    1498
River Rch & RM=UNT014 IN PECR,Reach-1         ,3011
     694     976    1211    1096    1482    2004    2229
Boundary for River Rch & Prof#=UNT014 IN PECR,Reach-1         , 1
Up Type= 0
Dn Type= 3
Dn Slope=0.005
Boundary for River Rch & Prof#=UNT014 IN PECR,Reach-1         , 2
Up Type= 0
Dn Type= 3
Dn Slope=0.005
Boundary for River Rch & Prof#=UNT014 IN PECR,Reach-1         , 3
Up Type= 0
Dn Type= 3
Dn Slope=0.005
Boundary for River Rch & Prof#=UNT014 IN PECR,Reach-1         , 4
Up Type= 0
Dn Type= 3
Dn Slope=0.005
Boundary for River Rch & Prof#=UNT014 IN PECR,Reach-1         , 5
Up Type= 0
Dn Type= 3
Dn Slope=0.005
Boundary for River Rch & Prof#=UNT014 IN PECR,Reach-1         , 6
Up Type= 0
Dn Type= 3
Dn Slope=0.005
Boundary for River Rch & Prof#=UNT014 IN PECR,Reach-1         , 7
Up Type= 0
Dn Type= 3
Dn Slope=0.005
DSS Import GetInterval= 0
DSS Import GetPeak= 0
DSS Import FillOption= 0

--- UNT014 IN PECR.g01 (geometry) ---

Geom Title=Existing Conditions

River Reach=UNT014 IN PECR,Reach-1
Reach XY= 30
      2336947.48     13259296.42      2336908.58     13259270.81
      2336632.84     13259322.19      2336590.69     13259285.69
      2336557.72     13259096.86      2336524.37     13259040.58
      2336525.68     13258972.81      2336442.51     13258777.60
      2336398.24     13258373.95      2336312.83     13258295.52
      2336253.25     13258269.64      2336205.51     13258184.11
      2336164.29     13258033.41      2336046.34     13258000.85
      2335992.18     13257929.78      2335968.67     13257777.31
      2336034.02     13257704.71      2336107.82     13257537.87
      2336102.44     13257333.96      2336066.59     13257300.12
      2335998.32     13257297.73      2335688.71     13257396.95
      2335528.71     13257364.97      2335437.05     13257296.74
      2335410.49     13257197.94      2335524.95     13256965.65
      2335506.50     13256872.40      2335454.16     13256743.55
      2335340.21     13256659.23      2335154.25     13256464.67

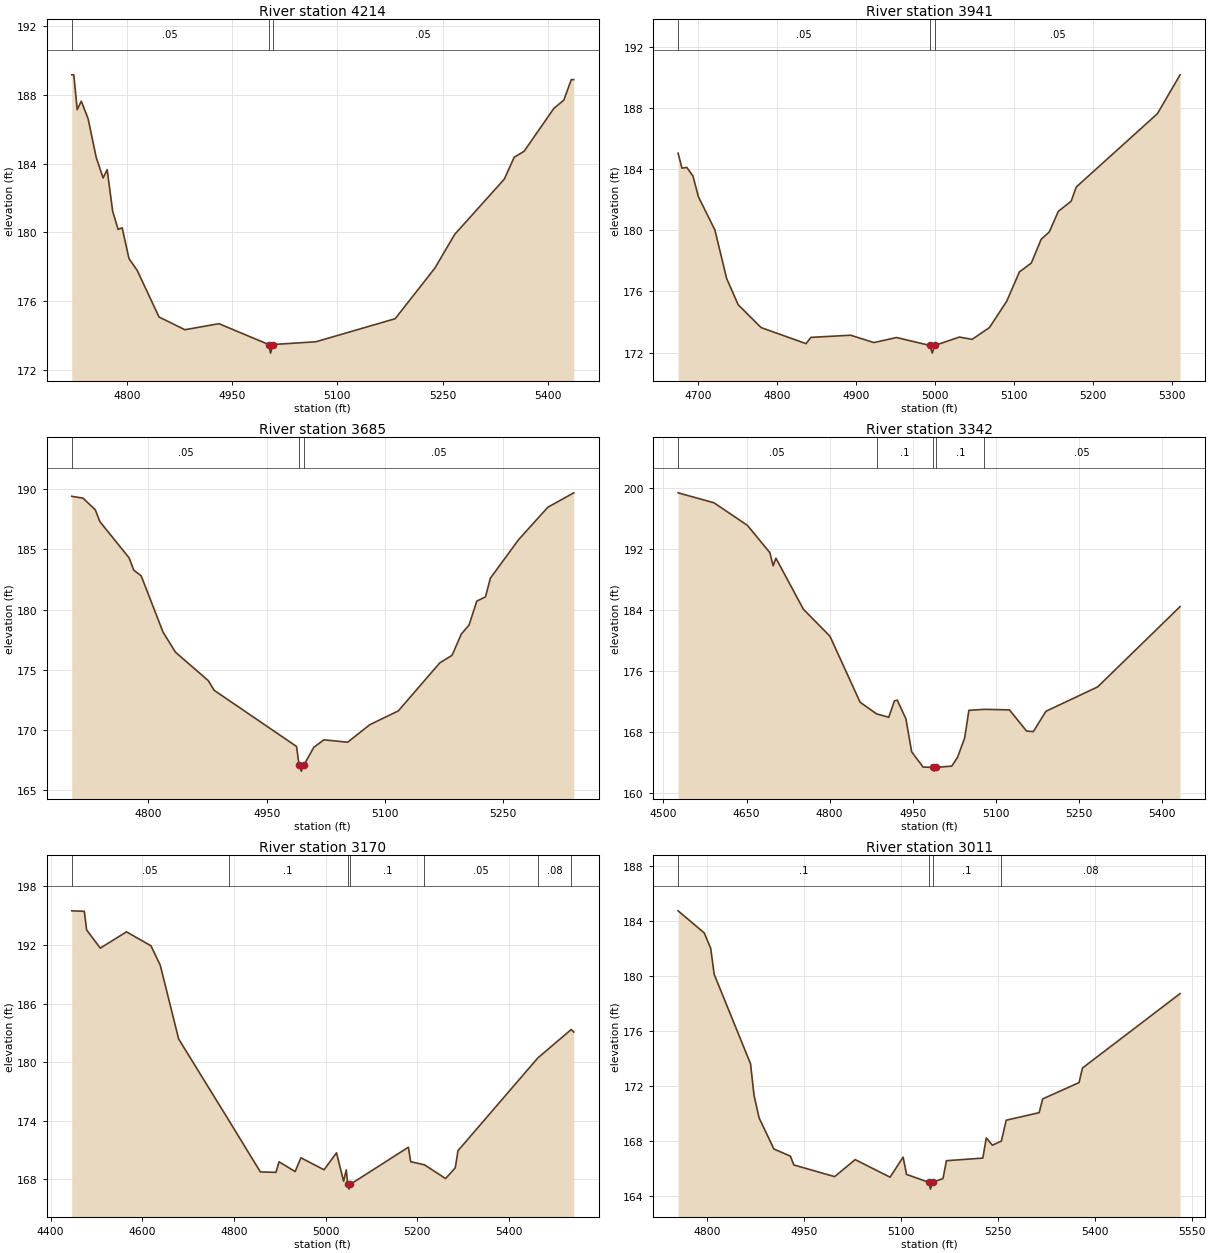
Type RM Length L Ch R = 1,4214,273,273,273
BEGIN DESCRIPTION:
UNT014 IN PECR 9.0
END DESCRIPTION:
XS GIS Cut Line= 3
      2336937.71     13259046.87      2336787.72     13259296.85
      2336487.72     13259596.86
#Sta/Elev= 30
  4721.2  189.16  4724.1  189.16  4729.0  187.14  4734.8  187.63  4744.5  186.61
  4756.2  184.34  4765.9  183.17  4771.7  183.65  4779.5  181.24  4787.3  180.18
  4793.1  180.27  4802.8  178.48  4814.5  177.80  4845.6  175.09  4882.5  174.35
  4931.1  174.70  5002.0  173.49  5004.7  172.99  5008.0  173.49  5069.3  173.65
  5182.4  174.99  5239.0  177.93  5267.3  179.89  5338.0  183.10  5352.1  184.37
  5366.3  184.72  5408.7  187.21  5422.9  187.69  5433.5  188.88  5437.0  188.88
#Mann=3,-1,0
  4721.2    0.05       0  5002.0    0.03       0  5008.0    0.05       0
Bank Sta=5002,5008
Exp/Cntr=0.3,0.1

Type RM Length L Ch R = 1,3941,256,256,256
BEGIN DESCRIPTION:
Mapping XS 9afa9608
END DESCRIPTION:
XS GIS Cut Line= 3
      2336842.99     13259056.35      2336628.97     13259210.37
      2336302.31     13259388.19
#Sta/Elev= 30
  4675.1  185.04  4680.0  184.06  4686.1  184.11  4693.9  183.55  4700.9  182.18
  4721.7  180.02  4736.5  176.86  4751.2  175.13  4780.2  173.64  4837.1  172.59
  4843.3  173.00  4893.6  173.14  4923.0  172.66  4951.6  172.99  4994.1  172.47
  4996.9  171.97  5000.1  172.47  5031.3  173.02  5047.4  172.87  5069.3  173.64
  5091.1  175.35  5107.3  177.28  5122.4  177.86  5134.8  179.41  5145.1  179.89
  5156.6  181.24  5172.8  181.90  5179.3  182.83  5282.0  187.62  5310.7  190.16
#Mann=3,-1,0
  4675.1    0.05       0  4994.1    0.03       0  5000.1    0.05       0
Bank Sta=4994.1,5000.1
Exp/Cntr=0.3,0.1

Type RM Length L Ch R = 1,3685,343,343,343
BEGIN DESCRIPTION:
UNT014 IN PECR 8.0
END DESCRIPTION:
XS GIS Cut Line= 4
      2336783.77     13258843.96      2336634.26     13258931.32
      2336338.63     13259106.01      2336241.13     13259177.07
#Sta/Elev= 30
  4702.6  189.41  4716.8  189.26  4732.5  188.29  4738.3  187.31  4775.5  184.29
  4781.3  183.28  4790.7  182.81  4818.5  178.13  4834.2  176.47  4875.8  174.11
  4883.4  173.30  4987.9  168.64  4991.2  167.09  4994.0  166.59  4997.2  167.09
  5009.9  168.57  5022.7  169.19  5052.8  168.99  5080.8  170.44  5117.1  171.59
  5169.8  175.58  5185.4  176.21  5197.1  177.97  5206.9  178.72  5216.8  180.71
  5227.8  181.06  5234.0  182.61  5269.8  185.81  5306.9  188.50  5339.8  189.70
#Mann=3,-1,0
  4702.6    0.05       0  4991.2    0.03       0  4997.2    0.05       0
Bank Sta=4991.2,4997.2
Exp/Cntr=0.3,0.1

Type RM Length L Ch R = 1,3342,172,172,172
BEGIN DESCRIPTION:
Mapping XS b14feb79
END DESCRIPTION:
XS GIS Cut Line= 5
      2336891.79     13258654.27      2336627.03     13258619.54
      2336370.08     13258686.38      2336289.35     13258886.90
      2336173.44     13258992.51
#Sta/Elev= 30
  4526.6  199.33  4591.2  198.03  4651.7  195.07  4692.1  191.50  4698.0  189.78
  4703.1  190.77  4752.6  184.09  4800.5  180.56  4854.9  171.91  4884.5  170.39
  4906.6  169.94  4916.9  172.09  4922.0  172.18  4937.6  169.73  4947.9  165.42
  4968.6  163.42  4986.2  163.39  4989.0  162.89  4992.2  163.39  5020.2  163.54
  5030.6  164.68  5043.6  167.25  5051.2  170.85  5079.1  170.98  5124.3  170.91
  5155.2  168.14  5167.4  168.06  5190.2  170.73  5283.5  173.92  5432.1  184.43
#Mann=5,-1,0
  4526.6    0.05       0  4884.5     0.1       0  4986.2    0.07       0
  4992.2     0.1       0  5079.1    0.05       0
Bank Sta=4986.2,4992.2
Exp/Cntr=0.3,0.1

Type RM Length L Ch R = 1,3170,159,159,159
BEGIN DESCRIPTION:
UNT014 IN PECR 7.0
END DESCRIPTION:
XS GIS Cut Line= 6
      2336919.57     13258584.82      2336508.10     13258540.55
      2336449.27     13258474.19      2336361.12     13258528.26
      2336341.44     13258668.15      2336157.52     13258963.45
#Sta/Elev= 30
  4446.2  195.49  4473.6  195.44  4478.6  193.54  4508.4  191.67  4565.6  193.34
  4619.0  191.91  4639.2  189.93  4679.4  182.37  4788.6  174.06  4857.7  168.76
  4891.7  168.72  4898.4  169.80  4933.5  168.80  4946.1  170.21  4996.6  168.98
  5023.8  170.72  5039.2  167.81  5045.1  168.97  5048.2  167.50  5051.0  167.00
  5054.2  167.50  5180.6  171.29  5185.6  169.81  5215.7  169.49  5261.7  168.08
  5282.9  169.18  5288.8  170.93  5462.8  180.42  5535.8  183.34  5541.3  183.08
#Mann=7,-1,0
  4446.2    0.05       0  4788.6     0.1       0  5048.2    0.07       0
  5054.2     0.1       0  5215.7    0.05       0  5462.8    0.08       0
  5535.8    0.05       0
Bank Sta=5048.2,5054.2
Exp/Cntr=0.3,0.1

Type RM Length L Ch R = 1,3011,103,103,103
BEGIN DESCRIPTION:
Mapping XS 4b55bdc5
END DESCRIPTION:
XS GIS Cut Line= 2
      2336461.21     13258118.71      2336200.81     13258850.46
#Sta/Elev= 30
  4755.4  184.75  4795.9  183.14  4805.9  182.01  4811.2  180.13  4867.5  173.61
  4872.9  171.31  4880.8  169.66  4903.7  167.40  4929.2  166.88  4934.5  166.24
  4997.6  165.39  5029.4  166.63  5083.4  165.35  5103.6  166.81  5108.9  165.55
  5143.2  164.98  5145.9  164.48  5149.2  164.98  5165.3  165.25  5170.6  166.55
  5226.9  166.74  5232.3  168.21  5241.7  167.68  5255.6  167.98  5263.1  169.50
  5314.1  170.05  5319.5  171.05  5375.8  172.24  5381.1  173.30  5532.1  178.72
#Mann=4,-1,0
  4755.4     0.1       0  5143.2    0.07       0  5149.2     0.1       0
  5255.6    0.08       0
Bank Sta=5143.2,5149.2
Exp/Cntr=0.3,0.1

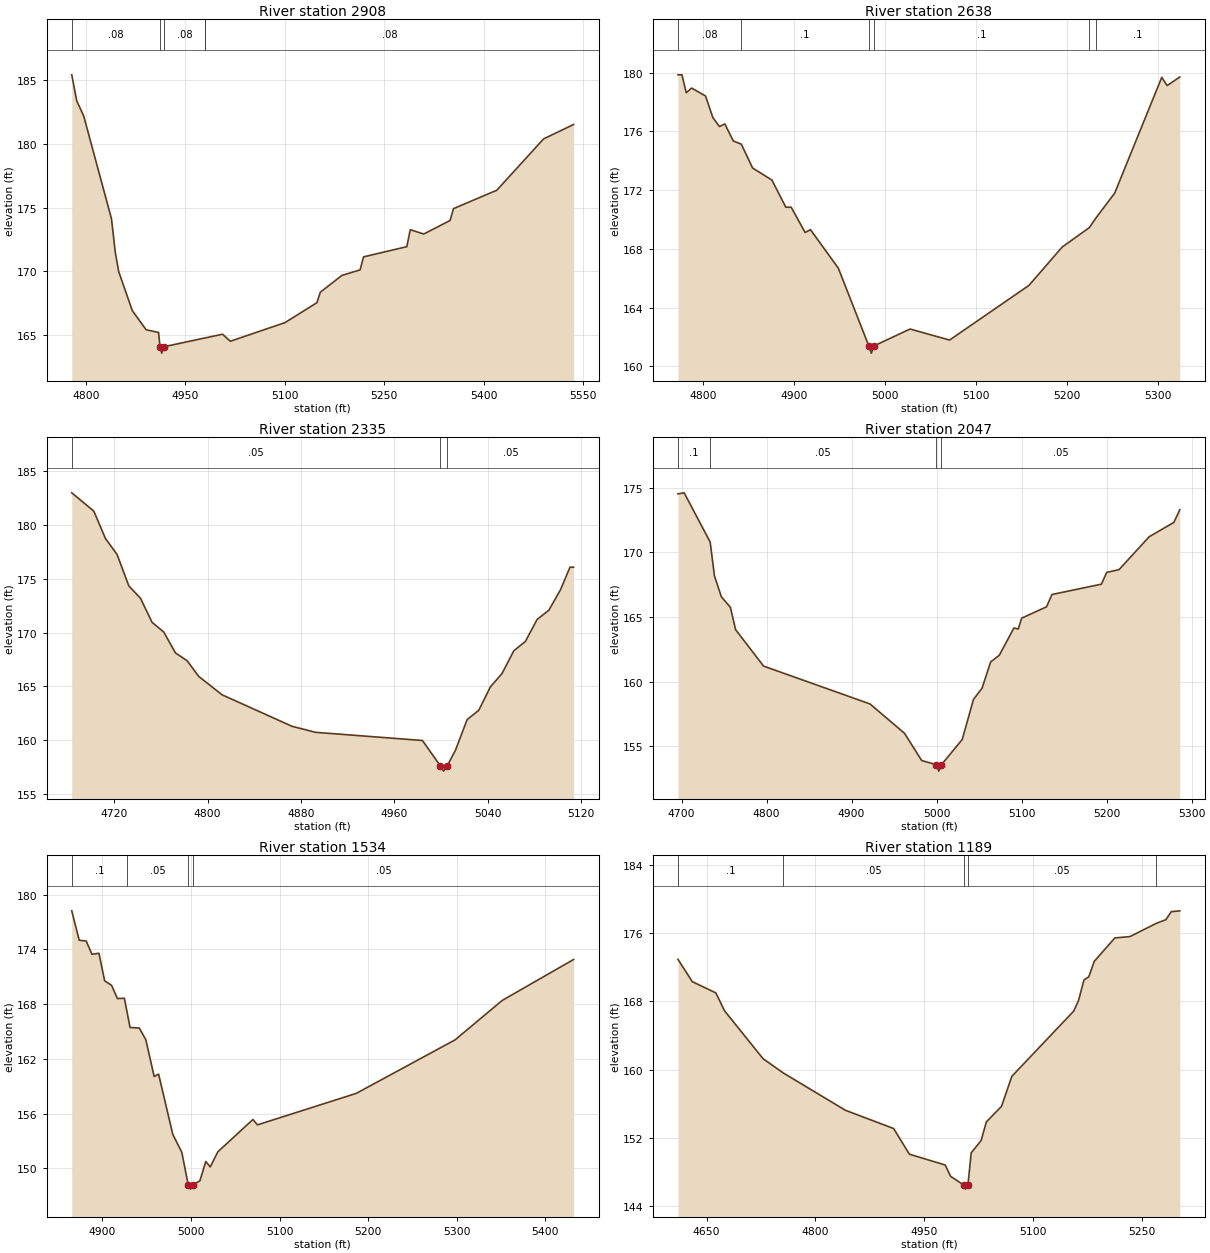
Type RM Length L Ch R = 1,2908,270,270,270
BEGIN DESCRIPTION:
UNT014 IN PECR 6.0
END DESCRIPTION:
XS GIS Cut Line= 2
      2336362.26     13258079.65      2336138.57     13258802.74
#Sta/Elev= 30
  4778.6  185.40  4786.1  183.36  4796.6  182.18  4838.5  174.13  4844.2  171.52
  4849.4  169.99  4869.9  166.93  4890.8  165.43  4909.5  165.22  4911.7  164.10
  4914.4  163.60  4917.7  164.10  4979.5  164.79  4979.8  164.79  5006.0  165.08
  5017.8  164.53  5100.2  165.99  5148.3  167.55  5153.5  168.37  5186.1  169.69
  5213.5  170.12  5218.7  171.14  5284.0  171.94  5289.2  173.27  5309.5  172.93
  5349.2  173.99  5354.4  174.92  5419.7  176.36  5490.2  180.38  5535.5  181.51
#Mann=5,-1,0
  4778.6    0.08       0  4911.7    0.07       0  4917.7    0.08       0
  4979.5     0.1       0  4979.8    0.08       0
Bank Sta=4911.7,4917.7
Exp/Cntr=0.3,0.1

Type RM Length L Ch R = 1,2638,303,303,303
BEGIN DESCRIPTION:
Mapping XS 984cd704
END DESCRIPTION:
XS GIS Cut Line= 2
      2336370.08     13257946.80      2335903.90     13258241.09
#Sta/Elev= 30
  4772.3  179.85  4776.7  179.85  4781.4  178.63  4787.3  178.95  4802.6  178.41
  4810.6  176.95  4817.9  176.33  4823.8  176.51  4833.1  175.35  4841.9  175.13
  4854.3  173.51  4875.5  172.69  4890.8  170.84  4896.7  170.84  4912.0  169.12
  4917.9  169.31  4948.5  166.69  4981.9  161.41  4984.7  160.91  4987.9  161.41
  5027.3  162.55  5070.7  161.80  5157.9  165.52  5194.4  168.13  5224.2  169.45
  5231.5  170.11  5252.1  171.80  5303.8  179.68  5309.7  179.12  5323.6  179.70
#Mann=6,-1,0
  4772.3    0.08       0  4841.9     0.1       0  4981.9    0.07       0
  4987.9     0.1       0  5224.2    0.05       0  5231.5     0.1       0
Bank Sta=4981.9,4987.9
Exp/Cntr=0.3,0.1

Type RM Length L Ch R = 1,2335,288,288,288
BEGIN DESCRIPTION:
UNT014 IN PECR 5.0
END DESCRIPTION:
XS GIS Cut Line= 2
      2336296.58     13257872.70      2335866.48     13257885.95
#Sta/Elev= 30
  4683.5  183.01  4702.4  181.31  4712.4  178.76  4722.4  177.27  4732.4  174.36
  4742.4  173.21  4752.4  170.96  4762.4  170.06  4772.4  168.12  4782.4  167.39
  4792.4  165.93  4812.4  164.22  4872.4  161.29  4892.5  160.73  4984.2  159.97
  4999.5  157.62  5002.3  157.12  5005.5  157.62  5012.5  159.06  5022.5  161.91
  5032.5  162.78  5042.5  164.96  5052.5  166.21  5062.5  168.31  5072.5  169.19
  5082.5  171.23  5092.6  172.09  5102.6  174.00  5110.7  176.09  5113.8  176.09
#Mann=3,-1,0
  4683.5    0.05       0  4999.5   0.035       0  5005.5    0.05       0
Bank Sta=4999.5,5005.5
Exp/Cntr=0.3,0.1

Type RM Length L Ch R = 1,2047,513,513,513
BEGIN DESCRIPTION:
Mapping XS 7b6b03e3
END DESCRIPTION:
XS GIS Cut Line= 4
      2336355.52     13257695.95      2336261.26     13257660.60
      2335960.79     13257610.52      2335848.84     13257757.83
#Sta/Elev= 30
  4695.8  174.53  4703.1  174.61  4733.7  170.80  4738.7  168.19  4746.9  166.56
  4757.5  165.75  4763.6  164.02  4796.5  161.20  4921.7  158.27  4962.3  156.00
  4982.5  153.89  4999.8  153.57  5002.6  153.07  5005.8  153.57  5030.2  155.52
  5043.4  158.62  5053.5  159.49  5063.6  161.52  5073.8  162.04  5091.0  164.15
  5096.1  164.07  5100.1  164.91  5129.4  165.79  5135.7  166.74  5193.9  167.54
  5200.1  168.45  5214.7  168.67  5250.1  171.21  5279.1  172.32  5286.1  173.30
#Mann=4,-1,0
  4695.8     0.1       0  4733.7    0.05       0  4999.8   0.035       0
  5005.8    0.05       0
Bank Sta=4999.8,5005.8
Exp/Cntr=0.3,0.1

Type RM Length L Ch R = 1,1534,345,345,345
BEGIN DESCRIPTION:
UNT014 IN PECR 4.0
END DESCRIPTION:
XS GIS Cut Line= 3
      2335984.17     13257220.58      2335926.91     13257267.43
      2335838.37     13257751.82
#Sta/Elev= 30
  4865.5  178.22  4873.9  175.00  4881.8  174.91  4888.3  173.46  4896.2  173.57
  4902.6  170.56  4910.5  170.05  4917.0  168.61  4924.9  168.64  4928.0  167.09
  4931.3  165.44  4941.7  165.38  4949.1  164.10  4958.5  160.07  4963.5  160.33
  4979.6  153.71  4989.7  151.77  4996.9  148.23  4999.6  147.73  5002.9  148.23
  5010.1  148.64  5016.8  150.76  5021.8  150.16  5030.4  151.82  5070.0  155.36
  5075.1  154.77  5186.6  158.22  5298.1  164.08  5351.3  168.40  5431.9  172.89
#Mann=4,-1,0
  4865.5     0.1       0  4928.0    0.05       0  4996.9    0.03       0
  5002.9    0.05       0
Bank Sta=4996.9,5002.9
Exp/Cntr=0.3,0.1

Type RM Length L Ch R = 1,1189,416,416,416
BEGIN DESCRIPTION:
UNT014 IN PECR 3.0
END DESCRIPTION:
XS GIS Cut Line= 3
      2335906.04     13257178.90      2335692.54     13257267.43
      2335385.25     13257611.17
#Sta/Elev= 30
  4610.6  172.93  4630.4  170.31  4662.9  168.99  4674.8  166.90  4728.0  161.27
  4756.1  159.59  4841.6  155.22  4908.1  153.08  4929.8  150.07  4979.2  148.80
  4986.7  147.47  5004.6  146.47  5007.3  145.97  5010.6  146.47  5015.1  150.23
  5028.8  151.67  5036.0  153.86  5056.9  155.68  5071.1  159.20  5156.4  166.85
  5163.1  168.09  5170.6  170.51  5177.3  170.88  5184.8  172.69  5213.2  175.44
  5234.1  175.60  5270.6  177.16  5283.6  177.58  5291.0  178.52  5302.8  178.62
#Mann=5,-1,0
  4610.6     0.1       0  4756.1    0.05       0  5004.6    0.03       0
  5010.6    0.05       0  5270.6     0.1       0
Bank Sta=5004.6,5010.6
Exp/Cntr=0.3,0.1

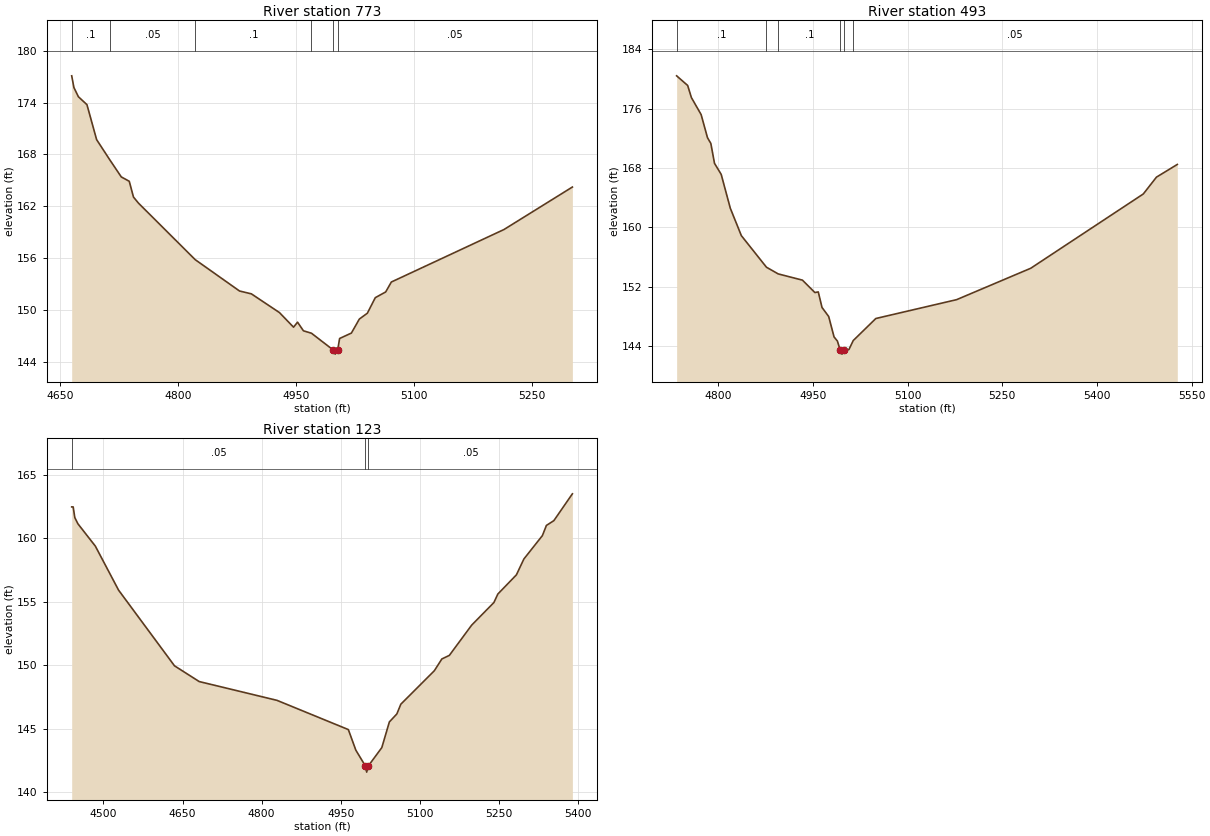
Type RM Length L Ch R = 1,773,280,280,280
BEGIN DESCRIPTION:
UNT014 IN PECR 2.0
END DESCRIPTION:
XS GIS Cut Line= 4
      2335795.55     13256980.81      2335627.99     13257053.72
      2335351.76     13257103.59      2335259.70     13257250.63
#Sta/Elev= 30
  4664.7  177.10  4667.5  175.75  4673.2  174.68  4684.1  173.76  4696.4  169.71
  4713.4  167.34  4727.8  165.39  4737.9  164.89  4743.3  163.06  4749.6  162.36
  4821.8  155.81  4878.2  152.18  4893.3  151.85  4929.0  149.68  4946.9  147.99
  4952.0  148.57  4959.5  147.57  4969.7  147.29  4997.1  145.37  4999.9  144.87
  5003.1  145.37  5005.5  146.68  5020.5  147.31  5030.6  148.93  5040.8  149.61
  5050.9  151.41  5064.1  152.07  5071.3  153.22  5214.6  159.30  5301.6  164.22
#Mann=6,-1,0
  4664.7     0.1       0  4713.4    0.05       0  4821.8     0.1       0
  4969.7    0.05       0  4997.1    0.03       0  5003.1    0.05       0
Bank Sta=4997.1,5003.1
Exp/Cntr=0.3,0.1

Type RM Length L Ch R = 1,493,370,370,370
BEGIN DESCRIPTION:
Mapping XS 584beeeb
END DESCRIPTION:
XS GIS Cut Line= 4
      2335734.24     13256829.94      2335588.37     13256777.84
      2335182.12     13256928.88      2335027.29     13257063.07
#Sta/Elev= 30
  4734.1  180.43  4751.6  179.13  4757.5  177.50  4772.9  175.21  4783.0  172.09
  4788.3  171.32  4794.1  168.64  4804.7  167.15  4819.1  162.60  4836.6  158.90
  4876.4  154.64  4895.0  153.74  4933.4  152.90  4953.1  151.23  4958.5  151.31
  4964.4  149.22  4975.0  148.00  4983.5  145.25  4988.8  144.69  4993.4  143.43
  4996.1  142.93  4999.4  143.43  5007.0  143.54  5013.9  144.76  5049.7  147.73
  5177.7  150.27  5295.1  154.50  5473.4  164.51  5494.3  166.78  5527.3  168.49
#Mann=6,-1,0
  4734.1     0.1       0  4876.4    0.05       0  4895.0     0.1       0
  4993.4    0.07       0  4999.4     0.1       0  5013.9    0.05       0
Bank Sta=4993.4,4999.4
Exp/Cntr=0.3,0.1

Type RM Length L Ch R = 1,123,0,0,0
BEGIN DESCRIPTION:
UNT014 IN PECR 1.0
END DESCRIPTION:
XS GIS Cut Line= 4
      2335758.48     13256684.15      2335561.49     13256593.33
      2335291.65     13256506.36      2334954.17     13256803.09
#Sta/Elev= 30
  4439.7  162.45  4442.5  162.45  4445.6  161.61  4451.5  161.12  4484.6  159.36
  4528.6  155.90  4634.7  149.94  4681.6  148.70  4829.2  147.22  4964.5  144.92
  4978.7  143.30  4996.6  142.07  4999.3  141.57  5002.6  142.07  5028.0  143.50
  5042.3  145.52  5056.5  146.15  5064.1  146.92  5127.6  149.55  5141.9  150.48
  5156.1  150.76  5198.4  153.14  5240.6  154.92  5248.1  155.59  5283.3  157.10
  5297.5  158.35  5332.6  160.19  5340.2  160.99  5354.4  161.37  5389.5  163.48
#Mann=3,-1,0
  4439.7    0.05       0  4996.6    0.03       0  5002.6    0.05       0
Bank Sta=4996.6,5002.6
Exp/Cntr=0.3,0.1

Chan Stop Cuts=-1