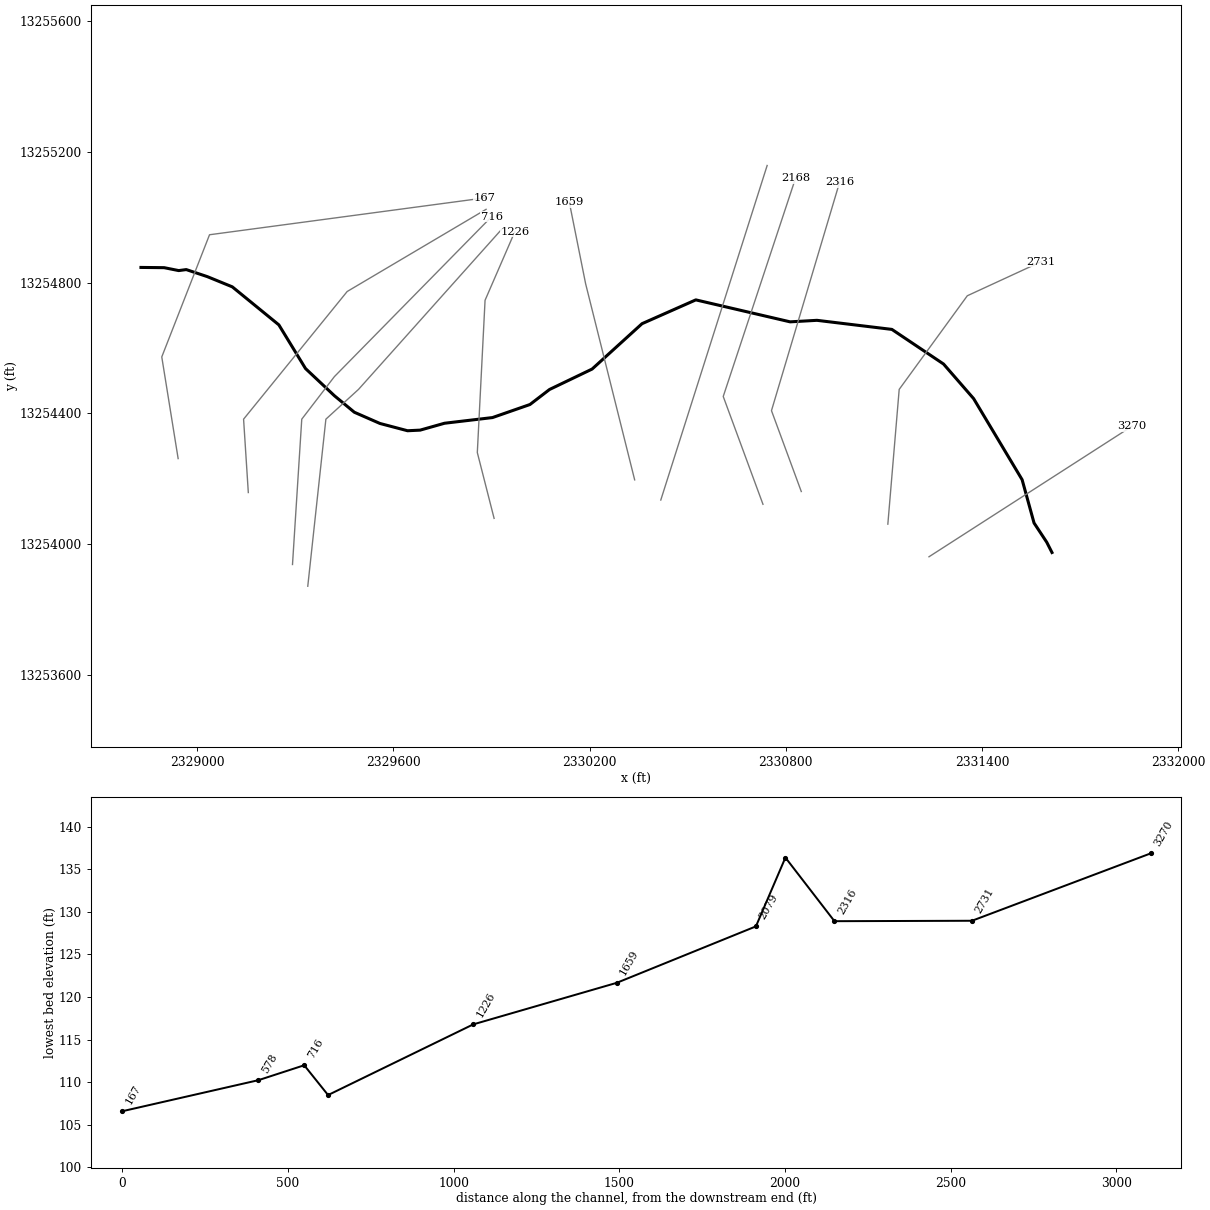
--- UNT015 IN PECR.prj (project) ---

Proj Title=UNT015 IN PECR Base Level Engineering
Current Plan=p01
Default Exp/Contr=0.3,0.1
English Units
Geom File=g01
Flow File=f01
Plan File=p01
Y Axis Title=Elevation
X Axis Title(PF)=Main Channel Distance
X Axis Title(XS)=Station
BEGIN DESCRIPTION:
UNT015 IN PECR
END DESCRIPTION:
DSS Export Rating Curves= 0
DSS Export Rating Curve Sorted= 0
DSS Export Volume Flow Curves= 0
DXF OffsetX= 0
DXF OffsetY= 0
DXF ScaleX= 1
DXF ScaleY= 10

--- UNT015 IN PECR.p01 (plan) ---

Plan Title=Multiple Run
Short Identifier=Multiple
Geom File=g01
Flow File=f01
Subcritical Flow
K Sum by GR= 0
Std Step Tol= 0.01
Critical Tol= 0.01
Num of Std Step Trials= 20
Max Error Tol= 0.3
Flow Tol Ratio= 0.001
Split Flow NTrial= 30
Split Flow Tol= 0.02
Split Flow Ratio= 0.02
Log Output Level= 0
Friction Slope Method= 1
Unsteady Friction Slope Method= 2
Unsteady Bridges Friction Slope Method= 1
Parabolic Critical Depth
Global Vel Dist=  1 , 1 , 1
Global Log Level= 0
CheckData=True
Encroach Param= -1, 0, 0, 0
BEGIN DESCRIPTION:
Multiple Run
END DESCRIPTION:

--- UNT015 IN PECR.f01 (steady flow) ---

Flow Title=Multiple
Program Version=4.10
Number of Profiles= 7
Profile Names=10-year,25-year,50-year,1pct_min,100-year,1pct_plu,500-year
River Rch & RM=UNT015 IN PECR,Reach-1         ,3270
     557     780     965     873    1180    1596    1772
Boundary for River Rch & Prof#=UNT015 IN PECR,Reach-1         , 1
Up Type= 0
Dn Type= 3
Dn Slope=0.0088
Boundary for River Rch & Prof#=UNT015 IN PECR,Reach-1         , 2
Up Type= 0
Dn Type= 3
Dn Slope=0.0088
Boundary for River Rch & Prof#=UNT015 IN PECR,Reach-1         , 3
Up Type= 0
Dn Type= 3
Dn Slope=0.0088
Boundary for River Rch & Prof#=UNT015 IN PECR,Reach-1         , 4
Up Type= 0
Dn Type= 3
Dn Slope=0.0088
Boundary for River Rch & Prof#=UNT015 IN PECR,Reach-1         , 5
Up Type= 0
Dn Type= 3
Dn Slope=0.0088
Boundary for River Rch & Prof#=UNT015 IN PECR,Reach-1         , 6
Up Type= 0
Dn Type= 3
Dn Slope=0.0088
Boundary for River Rch & Prof#=UNT015 IN PECR,Reach-1         , 7
Up Type= 0
Dn Type= 3
Dn Slope=0.0088
DSS Import GetInterval= 0
DSS Import GetPeak= 0
DSS Import FillOption= 0

--- UNT015 IN PECR.g01 (geometry) ---

Geom Title=Existing Conditions
Program Version=4.10

River Reach=UNT015 IN PECR  ,Reach-1
Reach XY= 29
      2331614.04     13253974.57       2331598.1     13254005.92
      2331559.21     13254064.95      2331522.73     13254197.39
      2331374.42     13254445.43       2331282.4     13254551.33
      2331124.42     13254657.23      2330895.25     13254685.01
      2330813.12     13254680.36      2330524.75     13254747.58
       2330360.3     13254674.78      2330207.52     13254535.89
      2330077.31     13254473.39      2330017.42     13254427.38
      2329902.83     13254387.45      2329756.13     13254370.09
      2329681.64     13254349.04      2329643.07     13254347.15
      2329558.65     13254369.41      2329480.32     13254403.76
      2329419.56     13254454.11      2329331.02     13254537.44
      2329249.42     13254671.12      2329107.06     13254787.44
      2329030.67     13254818.69      2328966.22     13254840.26
      2328943.19     13254837.21      2328898.72     13254846.11
      2328827.72     13254846.85

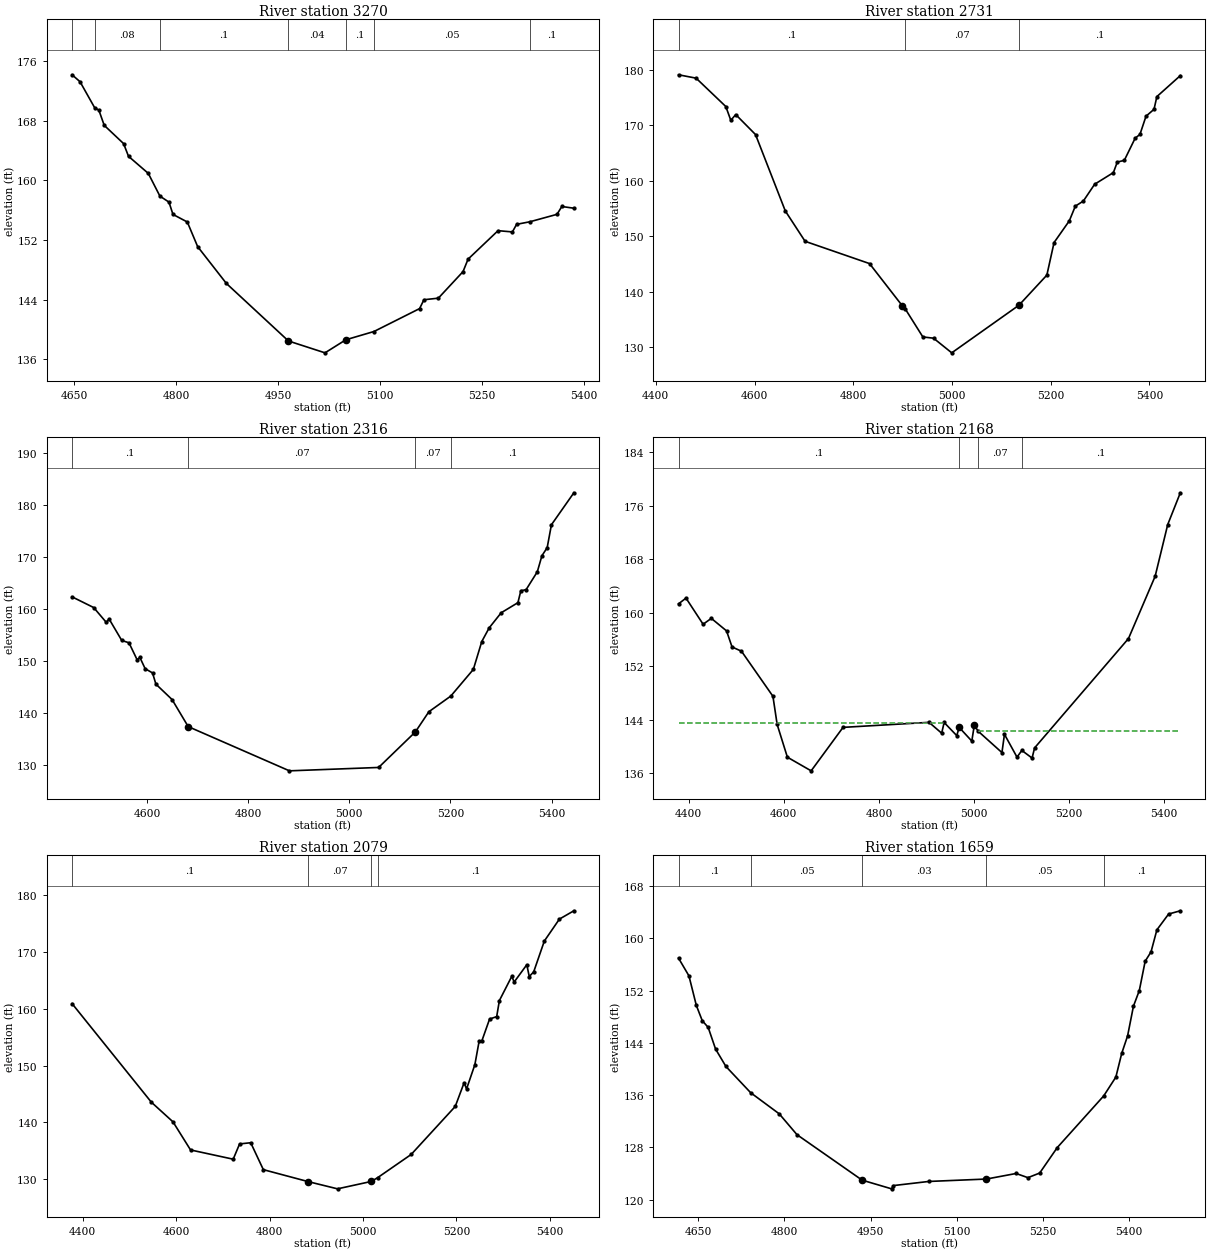
Type RM Length L Ch R = 1 ,3270    ,539,539,539
BEGIN DESCRIPTION:
UNT015 IN PECR 4.0
END DESCRIPTION:
XS GIS Cut Line= 2
      2331237.92     13253961.56      2331858.57     13254360.85
#Sta/Elev= 30
  4646.7  174.15  4658.4  173.22    4680  169.72  4686.1  169.41    4694  167.37
  4722.5  164.92  4729.7  163.22  4758.8  160.93  4775.9  157.88  4789.2  157.08
  4795.1  155.43  4816.2  154.41  4831.4  151.11  4873.7  146.17 4964.92  138.46
  5018.7  136.87  5049.3  138.62  5090.7  139.73  5157.8   142.8  5164.2  143.99
  5185.4   144.2  5221.7  147.76  5229.1  149.43  5273.2  153.25  5294.3  153.08
  5300.5   154.1  5319.9  154.44  5359.9  155.44    5367  156.49  5384.7  156.26
#Mann= 7 ,-1 , 0
  4646.7      .1       0    4680     .08       0  4775.9      .1       0
 4964.92     .04       0  5049.3      .1       0  5090.7     .05       0
  5319.9      .1       0
Bank Sta=4964.92,5049.3
XS Rating Curve= 0 ,0
Exp/Cntr=0.3,0.1

Type RM Length L Ch R = 1 ,2731    ,415,415,415
BEGIN DESCRIPTION:
Mapping XS 9a983f17
END DESCRIPTION:
XS GIS Cut Line= 4
      2331112.05     13254061.36      2331146.77     13254473.71
      2331355.11     13254760.17      2331580.82     13254864.34
#Sta/Elev= 30
  4446.1  179.05  4481.7  178.44  4541.9  173.33    4552  170.85    4562  171.88
  4602.1  168.28  4662.4  154.52  4702.5  149.05    4833  145.04  4899.4  137.44
  4905.5  136.86  4941.1  131.82  4962.7   131.6  4999.6  128.96  5135.8  137.54
  5192.3  142.96  5206.9  148.83  5237.8  152.74    5250  155.39  5266.2   156.3
  5289.1  159.33  5327.1  161.43    5335  163.33  5349.2  163.63  5371.2  167.63
  5380.9  168.31  5393.2  171.59  5409.4  172.83  5415.2  175.12  5462.7   178.9
#Mann= 3 ,-1 , 0
  4446.1      .1       0  4905.5     .07       0  5135.8      .1       0
Bank Sta=4899.4,5135.8
XS Rating Curve= 0 ,0
Exp/Cntr=0.3,0.1

Type RM Length L Ch R = 1 ,2316    ,148,148,148
BEGIN DESCRIPTION:
Mapping XS ad51ea5d
END DESCRIPTION:
XS GIS Cut Line= 3
       2330847.3     13254161.18      2330756.15     13254408.61
      2330964.49     13255107.43
#Sta/Elev= 30
  4451.3  162.35  4494.1  160.29  4519.2  157.42  4524.5  158.11  4549.6  153.97
  4563.9  153.52  4580.1  150.24  4585.4  150.72  4595.9  148.54  4610.5  147.73
  4617.2  145.57  4649.2  142.61  4681.1  137.41  4881.4  128.91  5057.9  129.56
  5130.6  136.39  5157.3  140.27  5200.7  143.28  5245.3   148.4    5262  153.76
  5276.6  156.38  5300.4  159.29  5333.5  161.23  5339.3  163.52  5349.7  163.73
  5371.9  167.17    5381  170.25  5391.4   171.8  5399.8   176.2  5444.2  182.35
#Mann= 4 ,-1 , 0
  4451.3      .1       0  4681.1     .07       0  5130.6     .07       0
  5200.7      .1       0
Bank Sta=4681.1,5130.6
XS Rating Curve= 0 ,0
Exp/Cntr=0.3,0.1

Type RM Length L Ch R = 1 ,2168    ,89,89,89
BEGIN DESCRIPTION:
Mapping XS 15770efd
END DESCRIPTION:
XS GIS Cut Line= 3
      2330730.12     13254122.12      2330608.58     13254452.01
      2330829.94     13255120.44
#Sta/Elev= 30
  4378.5  161.35  4394.2  162.21  4430.2   158.3  4447.5  159.18  4479.5  157.31
  4491.1   154.9  4510.9  154.27  4577.1  147.53    4586  143.31  4607.5  138.42
  4657.5  136.38  4724.6  142.88  4905.6  143.63  4932.1  142.01  4937.3  143.61
  4963.8  141.65    4969  142.87  4995.5  140.83  5000.7  143.18  5009.1  142.29
  5058.9  139.11  5064.2  141.84  5090.6  138.43  5100.8  139.43  5122.3  138.29
  5127.6  139.81  5325.1  156.16  5381.2  165.47  5407.7  173.21  5434.2  177.96
#Mann= 4 ,-1 , 0
  4378.5      .1       0    4969     .07       0  5009.1     .07       0
  5100.8      .1       0
#XS Ineff= 2 , 0
       0 4936.85  143.56 5010.05       0  142.29
Permanent Ineff=
       T       T
Bank Sta=4969,5000.7
XS Rating Curve= 0 ,0
Exp/Cntr=0.3,0.1

Type RM Length L Ch R = 1 ,2079    ,420,420,420
BEGIN DESCRIPTION:
Mapping XS 2eb35413
END DESCRIPTION:
XS GIS Cut Line= 2
       2330417.6     13254135.14      2330742.91     13255158.79
#Sta/Elev= 30
  4377.3  160.92    4547  143.56  4593.3   140.1  4630.9  135.15  4722.2  133.52
  4735.9  136.21  4759.7  136.42  4786.7  131.68  4882.8  129.57  4945.5   128.3
  5017.7   129.6  5031.6  130.28  5103.1  134.35  5197.5  142.81  5216.5  146.99
  5221.7  145.89  5239.5  150.17  5248.7  154.34    5254  154.25    5271   158.2
  5286.2  158.63    5292  161.46  5318.5  165.72  5323.7  164.73  5350.7  167.77
  5355.9  165.69  5365.4  166.51  5388.2  171.94  5420.4   175.8  5451.4  177.27
#Mann= 4 ,-1 , 0
  4377.3      .1       0  4882.8     .07       0  5017.7     .07       0
  5031.6      .1       0
Bank Sta=4882.8,5017.7
XS Rating Curve= 0 ,0
Exp/Cntr=0.3,0.1

Type RM Length L Ch R = 1 ,1659    ,433,433,433
BEGIN DESCRIPTION:
UNT015 IN PECR 3.0
END DESCRIPTION:
XS GIS Cut Line= 3
      2330337.73     13254196.82      2330187.72     13254796.85
      2330137.71      13255046.9
#Sta/Elev= 30
  4615.8  156.98  4633.9  154.27  4646.8  149.74  4657.1  147.41  4667.4  146.38
  4680.3  143.06  4698.3   140.4  4741.4  136.38  4791.1  133.15    4822  129.96
  4935.4     123  4986.7  121.67  4989.9  122.17  5051.3   122.8  5151.8  123.17
  5203.4  124.02    5224  123.38  5244.5  124.09  5275.1  127.99  5355.9  135.89
  5377.1  138.78  5387.3  142.41  5397.5  145.08  5407.7  149.63  5417.9  152.02
  5428.1  156.51  5438.3  157.94  5448.5  161.31  5468.9  163.73  5489.3  164.23
#Mann= 5 ,-1 , 0
  4615.8      .1       0  4741.4     .05       0  4935.4     .03       0
  5151.8     .05       0  5355.9      .1       0
Bank Sta=4935.4,5151.8
XS Rating Curve= 0 ,0
Exp/Cntr=0.3,0.1

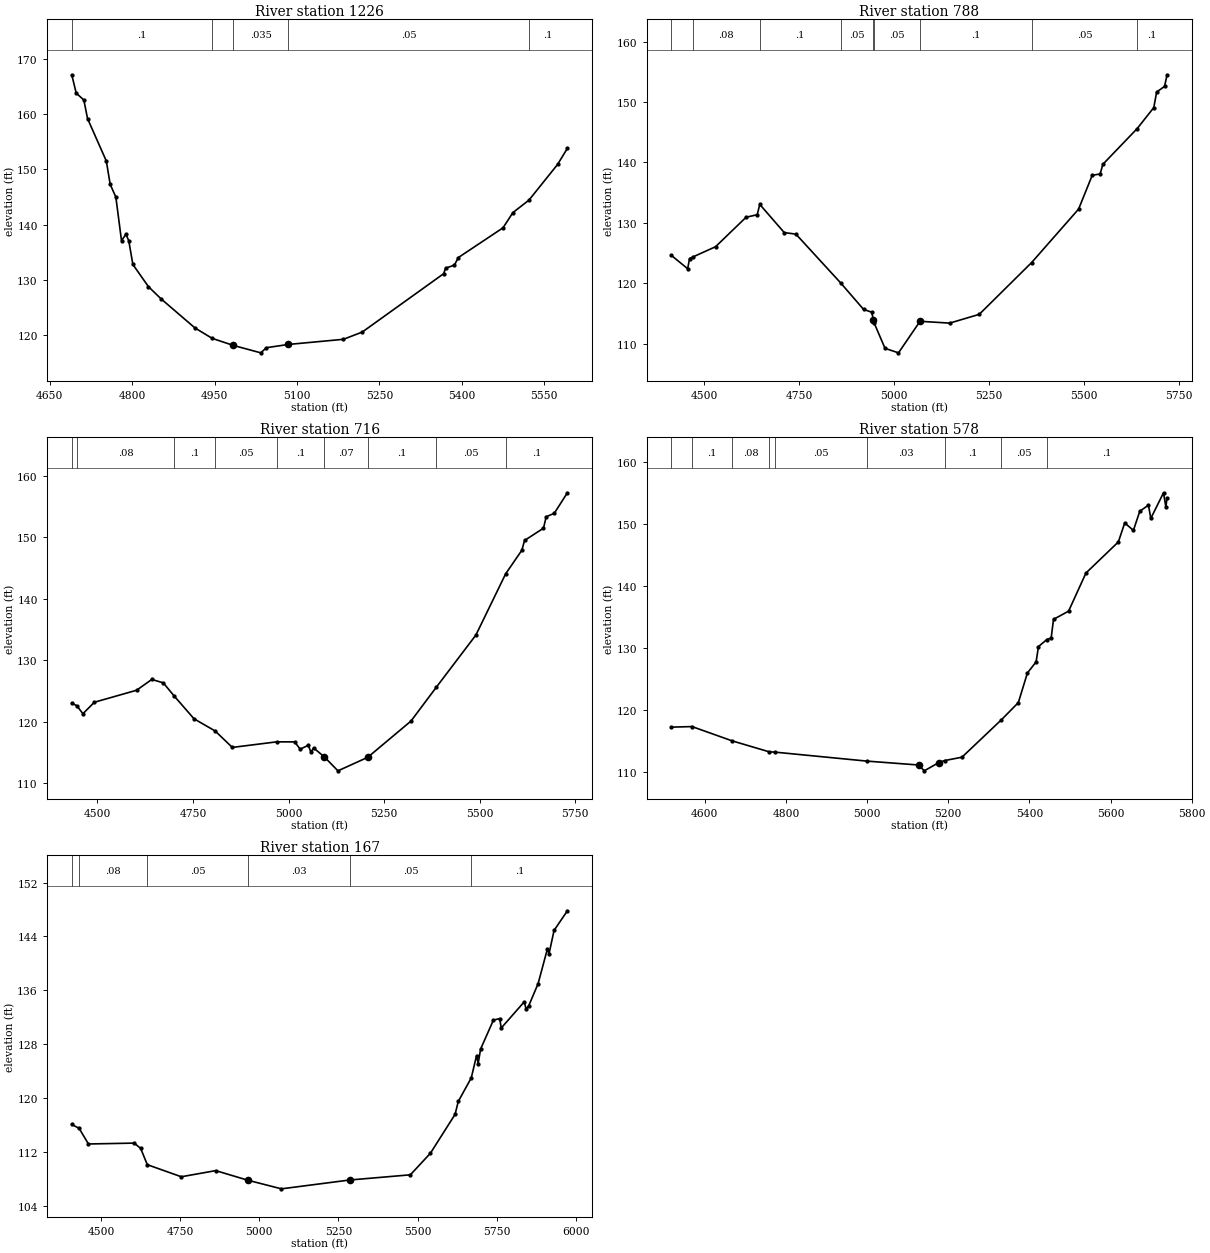
Type RM Length L Ch R = 1 ,1226    ,438,438,438
BEGIN DESCRIPTION:
UNT015 IN PECR 2.0
END DESCRIPTION:
XS GIS Cut Line= 4
      2329907.78     13254079.05      2329856.45     13254280.42
      2329880.14     13254746.33      2329970.98     13254955.65
#Sta/Elev= 30
  4689.9  167.14    4698  163.82  4711.9  162.57  4718.6  159.22  4752.8  151.53
  4759.9  147.29  4770.2  144.99  4780.5  137.09  4788.5  138.27  4793.7  137.09
  4801.2  132.79  4829.4  128.79  4852.8  126.54  4914.2   121.3  4945.6  119.41
  4984.3  118.13  5034.1  116.79  5044.3  117.72  5084.4  118.31  5184.5  119.24
  5218.8  120.55  5367.2  131.13  5370.5  132.12  5386.6  132.67  5393.9  134.05
  5475.2  139.43  5493.2  142.19  5522.4  144.44  5574.5   150.9  5592.4  153.82
#Mann= 5 ,-1 , 0
  4689.9      .1       0  4945.6     .05       0  4984.3    .035       0
  5084.4     .05       0  5522.4      .1       0
Bank Sta=4984.3,5084.4
XS Rating Curve= 0 ,0
Exp/Cntr=0.3,0.1

Type RM Length L Ch R = 1 ,788     ,72,72,72
BEGIN DESCRIPTION:
Mapping XS 13d66562
END DESCRIPTION:
XS GIS Cut Line= 4
       2329337.9      13253871.4       2329393.3     13254382.56
      2329493.13     13254473.71      2329930.47     13254963.01
#Sta/Elev= 30
  4413.3  124.61    4456  122.41    4461  124.09  4469.1  124.34  4529.4  126.05
  4609.9  130.93  4639.3  131.35  4645.9  133.06  4710.5  128.39  4741.1  128.14
  4858.8  120.08  4919.4  115.68  4940.7  115.22  4945.4  113.96  4947.5   113.4
  4975.9  109.23  5011.4  108.49  5068.1  113.71  5146.3  113.41  5224.1  114.86
  5362.2  123.44  5485.8  132.28  5521.7  137.87  5542.6   138.1  5549.7  139.69
  5639.9  145.59  5683.9  149.08  5691.4  151.65  5712.3  152.59  5718.9  154.51
#Mann= 9 ,-1 , 0
  4413.3      .1       0  4469.1     .08       0  4645.9      .1       0
  4858.8     .05       0  4945.4      .1       0  4947.5     .05       0
  5068.1      .1       0  5362.2     .05       0  5639.9      .1       0
Bank Sta=4945.4,5068.1
XS Rating Curve= 0 ,0
Exp/Cntr=0.3,0.1

Type RM Length L Ch R = 1 ,716     ,138,138,138
BEGIN DESCRIPTION:
Mapping XS f4973c83
END DESCRIPTION:
XS GIS Cut Line= 4
      2329291.18     13253937.85      2329319.52     13254382.56
      2329419.34     13254512.77      2329900.42     13255002.52
#Sta/Elev= 30
  4433.1  123.01  4446.6  122.57  4462.3  121.28  4492.2  123.15  4602.5   125.1
  4642.5  126.86  4672.6   126.3    4701  124.16  4752.8  120.46  4808.2  118.47
    4853   115.8  4969.4  116.71    5016   116.7  5030.5  115.52  5051.6  116.14
  5058.7  115.04  5065.7  115.71    5094  114.24  5129.2  111.99  5207.1  114.19
  5320.3  120.09  5386.7  125.61    5490  134.08  5567.9  144.05  5610.2  147.88
  5617.3  149.47  5666.8  151.47  5673.9  153.33    5695  153.89  5729.3  157.23
#Mann= 9 ,-1 , 0
  4433.1      .1       0  4446.6     .08       0    4701      .1       0
  4808.2     .05       0  4969.4      .1       0    5094     .07       0
  5207.1      .1       0  5386.7     .05       0  5567.9      .1       0
Bank Sta=5094,5207.1
XS Rating Curve= 0 ,0
Exp/Cntr=0.3,0.1

Type RM Length L Ch R = 1 ,578     ,411,411,411
BEGIN DESCRIPTION:
Mapping XS 1e2a0196
END DESCRIPTION:
XS GIS Cut Line= 4
      2329156.05     13254158.06      2329141.57     13254382.56
      2329458.41     13254773.19      2329883.24     13255024.62
#Sta/Elev= 30
  4517.8  117.28  4568.5  117.37  4667.3  115.07  4758.4  113.31  4773.5  113.25
    4999  111.81  5126.9  111.18    5141  110.24  5176.4  111.56  5190.8  111.89
  5233.9  112.44    5331  118.46  5372.8  121.23  5395.2  126.01  5416.6  127.79
  5422.4  130.26  5443.1  131.39  5453.7  131.64  5459.5  134.64  5496.6  135.96
  5539.4   142.1  5619.4  147.12    5635  150.18  5656.4  148.97  5672.1  152.05
  5693.5  153.04  5699.3   150.9  5730.6  155.03  5736.4  152.75  5739.4  154.22
#Mann= 9 ,-1 , 0
  4517.8     .08       0  4568.5      .1       0  4667.3     .08       0
  4758.4      .1       0  4773.5     .05       0    4999     .03       0
  5190.8      .1       0    5331     .05       0  5443.1      .1       0
Bank Sta=5126.9,5176.4
XS Rating Curve= 0 ,0
Exp/Cntr=0.3,0.1

Type RM Length L Ch R = 1 ,167     ,0,0,0
BEGIN DESCRIPTION:
UNT015 IN PECR 1.0
END DESCRIPTION:
XS GIS Cut Line= 4
      2328941.42     13254261.94      2328891.36     13254573.01
       2329037.4     13254946.85      2329879.45     13255059.65
#Sta/Elev= 30
  4407.4  116.13  4430.5  115.57  4460.1  113.24  4604.8  113.37  4625.1  112.58
  4646.1  110.17  4753.6  108.38  4862.2  109.29 4964.24  107.86  5069.9  106.59
  5285.6   107.9  5477.3  108.67  5540.5  111.86  5618.5  117.63  5628.6  119.54
  5669.8  123.05  5686.4  126.35  5691.5  125.17  5699.2  127.31  5739.6   131.6
  5759.4  131.83  5764.4  130.43  5837.4  134.33  5842.4   133.3  5850.6  133.65
  5880.8     137  5910.4  142.18  5915.4  141.44  5931.3   144.9  5973.4  147.81
#Mann= 6 ,-1 , 0
  4407.4      .1       0  4430.5     .08       0  4646.1     .05       0
 4964.24     .03       0  5285.6     .05       0  5669.8      .1       0
Bank Sta=4964.24,5285.6
XS Rating Curve= 0 ,0
Exp/Cntr=0.3,0.1

Chan Stop Cuts=-1
Use User Specified Reach Order=0
Composite Channel Slope=5