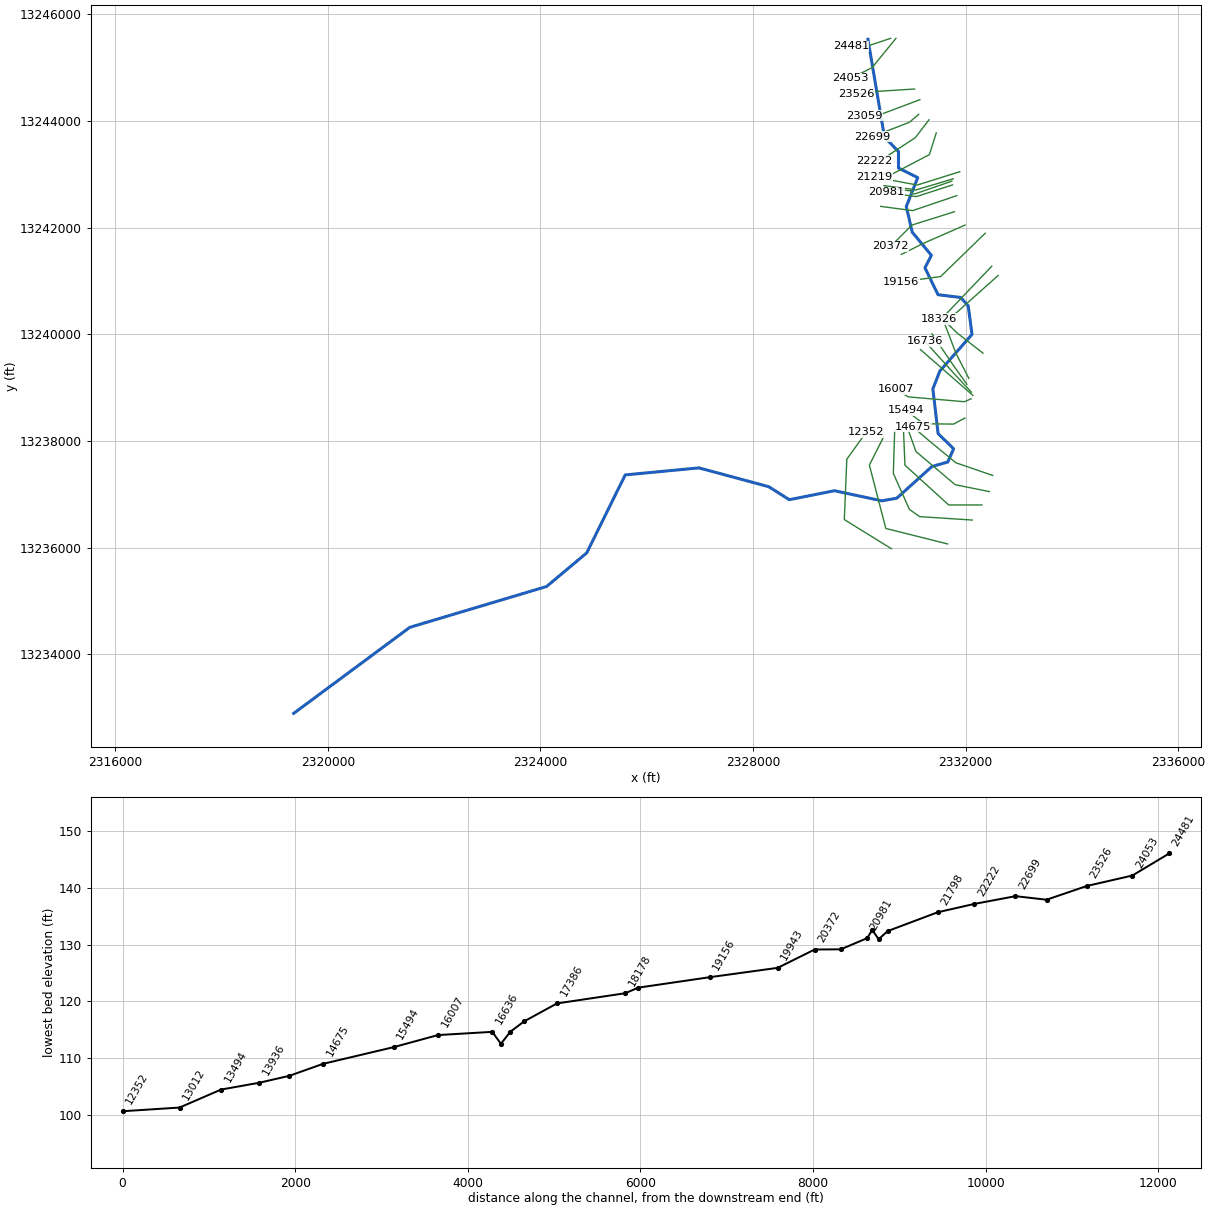
--- UNT016 IN PECR.prj (project) ---

Proj Title=UNT016 IN PECR Base Level Engineering
Current Plan=p01
Default Exp/Contr=0.3,0.1
English Units
Geom File=g01
Flow File=f01
Plan File=p01
Y Axis Title=Elevation
X Axis Title(PF)=Main Channel Distance
X Axis Title(XS)=Station
BEGIN DESCRIPTION:
UNT016 IN PECR
END DESCRIPTION:
DSS Export Rating Curves= 0
DSS Export Rating Curve Sorted= 0
DSS Export Volume Flow Curves= 0
DXF OffsetX= 0
DXF OffsetY= 0
DXF ScaleX= 1
DXF ScaleY= 10

--- UNT016 IN PECR.p01 (plan) ---

Plan Title=Multiple Run
Short Identifier=Multiple
Geom File=g01
Flow File=f01
Subcritical Flow
K Sum by GR= 0
Std Step Tol= 0.01
Critical Tol= 0.01
Num of Std Step Trials= 20
Max Error Tol= 0.3
Flow Tol Ratio= 0.001
Split Flow NTrial= 30
Split Flow Tol= 0.02
Split Flow Ratio= 0.02
Log Output Level= 0
Friction Slope Method= 1
Unsteady Friction Slope Method= 2
Unsteady Bridges Friction Slope Method= 1
Parabolic Critical Depth
Global Vel Dist=  1 , 1 , 1
Global Log Level= 0
CheckData=True
Encroach Param= -1, 0, 0, 0
BEGIN DESCRIPTION:
Multiple Run
END DESCRIPTION:

--- UNT016 IN PECR.f01 (steady flow) ---

Flow Title=Multiple
Program Version=4.10
Number of Profiles= 7
Profile Names=10-year,25-year,50-year,1pct_min,100-year,1pct_plu,500-year
River Rch & RM=UNT016 IN PECR,Reach-1         ,24481
     539     753     931     841    1137    1538    1701
River Rch & RM=UNT016 IN PECR,Reach-1         ,24053
     920    1320    1659    1520    2056    2781    3172
River Rch & RM=UNT016 IN PECR,Reach-1         ,17386
    1299    1893    2405    2225    3009    4069    4731
River Rch & RM=UNT016 IN PECR,Reach-1         ,16636
    1840    2713    3474    3234    4374    5915    6967
Boundary for River Rch & Prof#=UNT016 IN PECR,Reach-1         , 1
Up Type= 0
Dn Type= 3
Dn Slope=0.005
Boundary for River Rch & Prof#=UNT016 IN PECR,Reach-1         , 2
Up Type= 0
Dn Type= 3
Dn Slope=0.005
Boundary for River Rch & Prof#=UNT016 IN PECR,Reach-1         , 3
Up Type= 0
Dn Type= 3
Dn Slope=0.005
Boundary for River Rch & Prof#=UNT016 IN PECR,Reach-1         , 4
Up Type= 0
Dn Type= 3
Dn Slope=0.005
Boundary for River Rch & Prof#=UNT016 IN PECR,Reach-1         , 5
Up Type= 0
Dn Type= 3
Dn Slope=0.005
Boundary for River Rch & Prof#=UNT016 IN PECR,Reach-1         , 6
Up Type= 0
Dn Type= 3
Dn Slope=0.005
Boundary for River Rch & Prof#=UNT016 IN PECR,Reach-1         , 7
Up Type= 0
Dn Type= 3
Dn Slope=0.005
DSS Import GetInterval= 0
DSS Import GetPeak= 0
DSS Import FillOption= 0

--- UNT016 IN PECR.g01 (geometry) ---

Geom Title=Existing Conditions

River Reach=UNT016 IN PECR,Reach-1
Reach XY= 30
      2330160.38     13245529.77      2330471.96     13243694.15
      2330734.62     13243425.77      2330735.09     13243115.56
      2331097.01     13242935.39      2330881.90     13242393.69
      2330992.99     13241914.37      2331353.65     13241479.53
      2331232.87     13241244.55      2331479.25     13240741.17
      2331904.77     13240689.61      2332047.30     13240532.08
      2332117.72     13239996.85      2331512.57     13239309.55
      2331381.98     13238976.17      2331480.42     13238137.77
      2331772.78     13237853.29      2331661.91     13237604.42
      2331364.19     13237521.12      2330702.69     13236926.93
      2330423.14     13236877.56      2329531.06     13237067.06
      2328680.42     13236899.33      2328295.00     13237142.39
      2326981.31     13237495.36      2325594.85     13237363.58
      2324870.81     13235902.24      2324115.60     13235272.03
      2321542.69     13234506.41      2319358.04     13232893.78

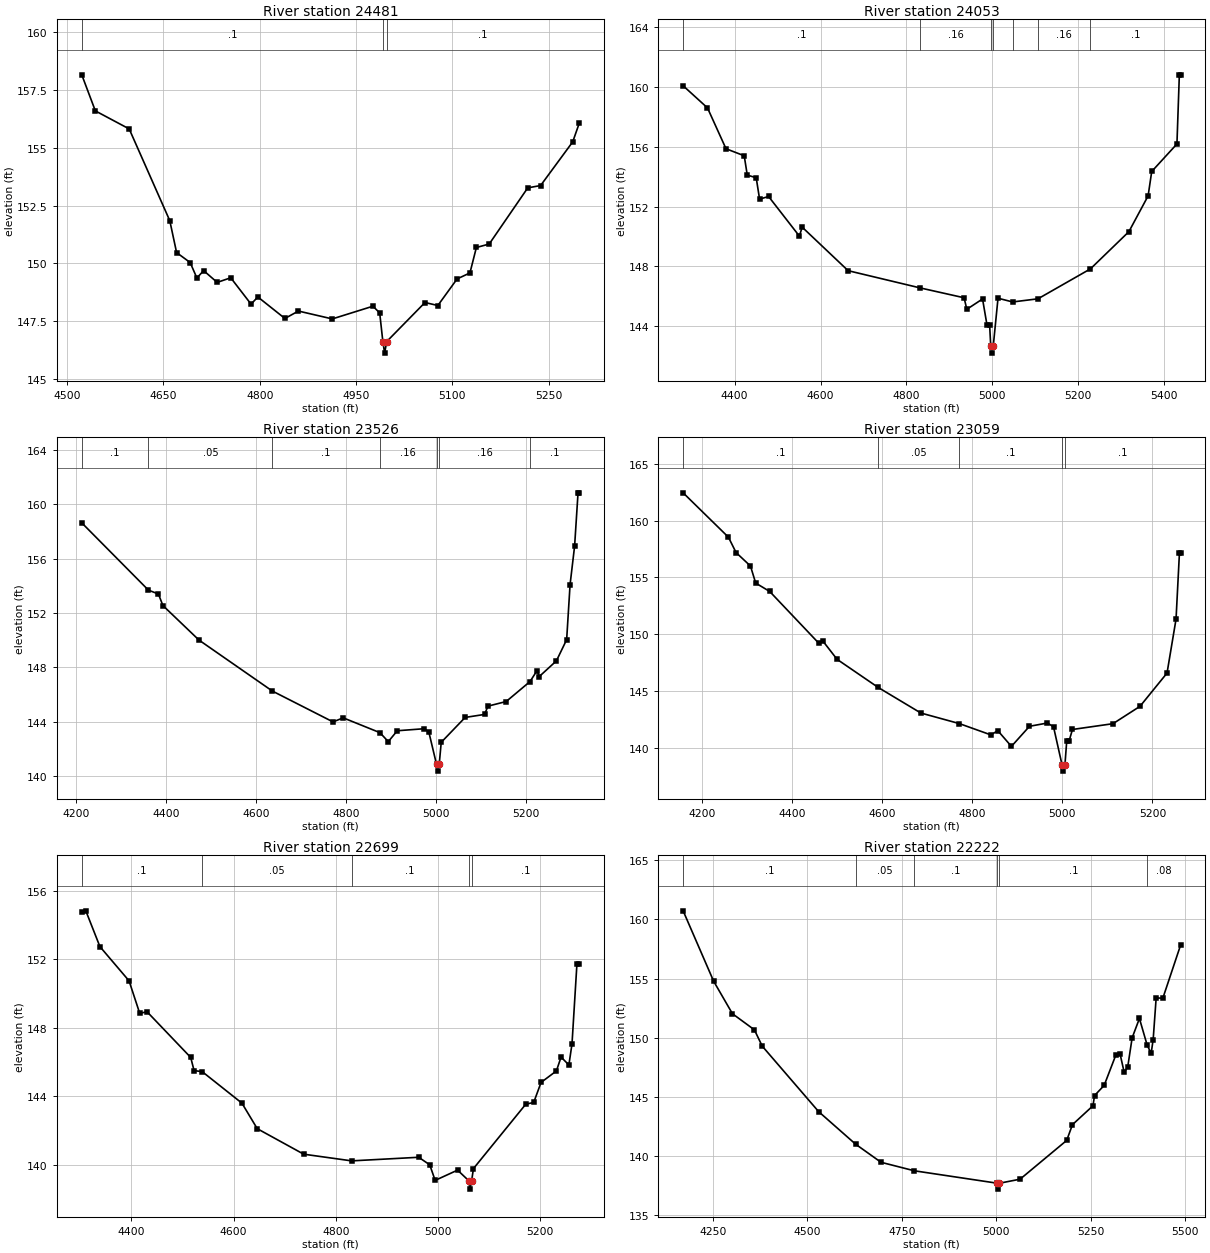
Type RM Length L Ch R = 1,24481,428,428,428
BEGIN DESCRIPTION:
UNT016 IN PECR 45.0
END DESCRIPTION:
XS GIS Cut Line= 3
      2330587.73     13245546.86      2330137.72     13245396.85
      2329837.67     13245396.85
#Sta/Elev= 30
  4523.0  158.16  4544.1  156.60  4596.8  155.82  4660.0  151.85  4670.6  150.47
  4691.7  150.04  4702.2  149.37  4712.7  149.69  4733.8  149.18  4754.9  149.38
  4786.5  148.24  4797.1  148.55  4839.2  147.62  4860.3  147.94  4913.0  147.60
  4976.3  148.15  4986.8  147.86  4991.7  146.62  4994.5  146.12  4997.7  146.62
  5057.3  148.31  5077.3  148.18  5107.3  149.33  5127.3  149.59  5137.3  150.69
  5157.3  150.84  5217.3  153.27  5237.3  153.37  5287.3  155.26  5297.4  156.06
#Mann=3,-1,0
  4523.0     0.1       0  4991.7    0.07       0  4997.7     0.1       0
Bank Sta=4991.7,4997.7
Exp/Cntr=0.3,0.1

Type RM Length L Ch R = 1,24053,527,527,527
BEGIN DESCRIPTION:
UNT016 IN PECR 44.0
END DESCRIPTION:
XS GIS Cut Line= 3
      2330687.74     13245546.87      2330237.72     13244996.85
      2329837.69     13244796.84
#Sta/Elev= 30
  4280.2  160.08  4336.9  158.60  4380.0  155.87  4422.4  155.40  4429.5  154.11
  4450.3  153.93  4458.2  152.50  4479.1  152.68  4550.8  150.03  4557.3  150.63
  4664.3  147.72  4831.7  146.57  4934.2  145.91  4940.6  145.14  4977.2  145.83
  4987.6  144.08  4993.7  144.08  4996.2  142.71  4999.0  142.21  5002.2  142.71
  5013.2  145.88  5047.2  145.63  5106.2  145.84  5228.3  147.84  5317.9  150.33
  5362.6  152.72  5371.0  154.35  5429.7  156.19  5435.3  160.81  5438.1  160.81
#Mann=7,-1,0
  4280.2     0.1       0  4831.7    0.16       0  4996.2    0.07       0
  5002.2    0.16       0  5047.2     0.1       0  5106.2    0.16       0
  5228.3     0.1       0
Bank Sta=4996.2,5002.2
Exp/Cntr=0.3,0.1

Type RM Length L Ch R = 1,23526,467,467,467
BEGIN DESCRIPTION:
UNT016 IN PECR 43.0
END DESCRIPTION:
XS GIS Cut Line= 3
      2331037.68     13244596.85      2330237.72     13244546.85
      2329937.68     13244496.85
#Sta/Elev= 30
  4212.5  158.63  4360.7  153.68  4382.8  153.40  4392.8  152.55  4473.0  150.01
  4636.1  146.26  4771.0  143.99  4793.6  144.29  4875.2  143.20  4893.8  142.54
  4913.8  143.34  4973.9  143.49  4984.0  143.24  5001.0  140.87  5003.7  140.37
  5007.0  140.87  5011.5  142.49  5064.7  144.32  5107.8  144.54  5115.4  145.15
  5155.9  145.49  5208.9  146.96  5224.4  147.76  5229.5  147.33  5267.5  148.48
  5290.3  150.04  5297.9  154.09  5308.0  156.93  5315.6  160.84  5318.2  160.84
#Mann=7,-1,0
  4212.5     0.1       0  4360.7    0.05       0  4636.1     0.1       0
  4875.2    0.16       0  5001.0    0.07       0  5007.0    0.16       0
  5208.9     0.1       0
Bank Sta=5001,5007
Exp/Cntr=0.3,0.1

Type RM Length L Ch R = 1,23059,360,360,360
BEGIN DESCRIPTION:
UNT016 IN PECR 42.0
END DESCRIPTION:
XS GIS Cut Line= 3
      2331137.71     13244396.85      2330337.72     13244096.85
      2330087.71     13244096.85
#Sta/Elev= 30
  4158.1  162.46  4258.7  158.55  4275.6  157.20  4307.6  156.01  4319.2  154.51
  4350.3  153.77  4459.8  149.19  4467.8  149.43  4499.9  147.79  4591.3  145.31
  4685.9  143.06  4771.2  142.13  4841.6  141.13  4856.7  141.51  4887.0  140.12
  4927.1  141.89  4967.1  142.18  4980.5  141.84  4999.7  138.44  5002.5  137.94
  5005.7  138.44  5009.8  140.59  5015.0  140.59  5022.5  141.61  5112.5  142.12
  5172.5  143.65  5232.5  146.58  5252.5  151.33  5260.0  157.13  5262.5  157.13
#Mann=5,-1,0
  4158.1     0.1       0  4591.3    0.05       0  4771.2     0.1       0
  4999.7    0.07       0  5005.7     0.1       0
Bank Sta=4999.7,5005.7
Exp/Cntr=0.3,0.1

Type RM Length L Ch R = 1,22699,477,477,477
BEGIN DESCRIPTION:
UNT016 IN PECR 41.0
END DESCRIPTION:
XS GIS Cut Line= 3
      2331113.75     13244121.51      2330942.58     13243974.41
      2330244.61     13243704.32
#Sta/Elev= 30
  4302.7  154.77  4310.6  154.82  4338.2  152.73  4395.3  150.73  4416.2  148.83
  4430.4  148.93  4516.0  146.26  4522.6  145.49  4538.5  145.43  4616.3  143.59
  4646.3  142.10  4737.3  140.61  4831.2  140.22  4962.5  140.43  4984.1  139.99
  4994.7  139.08  5038.6  139.68  5060.2  139.07  5062.9  138.57  5066.2  139.07
  5069.7  139.77  5172.2  143.53  5187.7  143.63  5202.1  144.80  5232.1  145.47
  5241.3  146.28  5256.6  145.82  5262.7  147.05  5272.4  151.74  5276.8  151.74
#Mann=5,-1,0
  4302.7     0.1       0  4538.5    0.05       0  4831.2     0.1       0
  5060.2    0.07       0  5066.2     0.1       0
Bank Sta=5060.2,5066.2
Exp/Cntr=0.3,0.1

Type RM Length L Ch R = 1,22222,424,424,424
BEGIN DESCRIPTION:
UNT016 IN PECR 40.0
END DESCRIPTION:
XS GIS Cut Line= 4
      2331308.92     13244019.85      2331052.22     13243685.60
      2330498.67     13243324.59      2330276.74     13243247.05
#Sta/Elev= 30
  4170.9  160.73  4251.7  154.78  4301.5  152.03  4359.6  150.67  4380.4  149.29
  4529.9  143.75  4627.7  141.00  4695.0  139.47  4783.3  138.75  5002.8  137.70
  5005.5  137.20  5008.8  137.70  5063.3  138.04  5186.8  141.32  5202.0  142.65
  5256.4  144.25  5260.5  145.11  5286.0  145.97  5317.3  148.57  5328.4  148.59
  5339.0  147.08  5348.4  147.53  5360.1  149.99  5379.4  151.63  5400.1  149.35
  5410.5  148.69  5415.8  149.85  5423.7  153.36  5441.5  153.35  5488.3  157.82
#Mann=6,-1,0
  4170.9     0.1       0  4627.7    0.05       0  4783.3     0.1       0
  5002.8    0.07       0  5008.8     0.1       0  5400.1    0.08       0
Bank Sta=5002.8,5008.8
Exp/Cntr=0.3,0.1

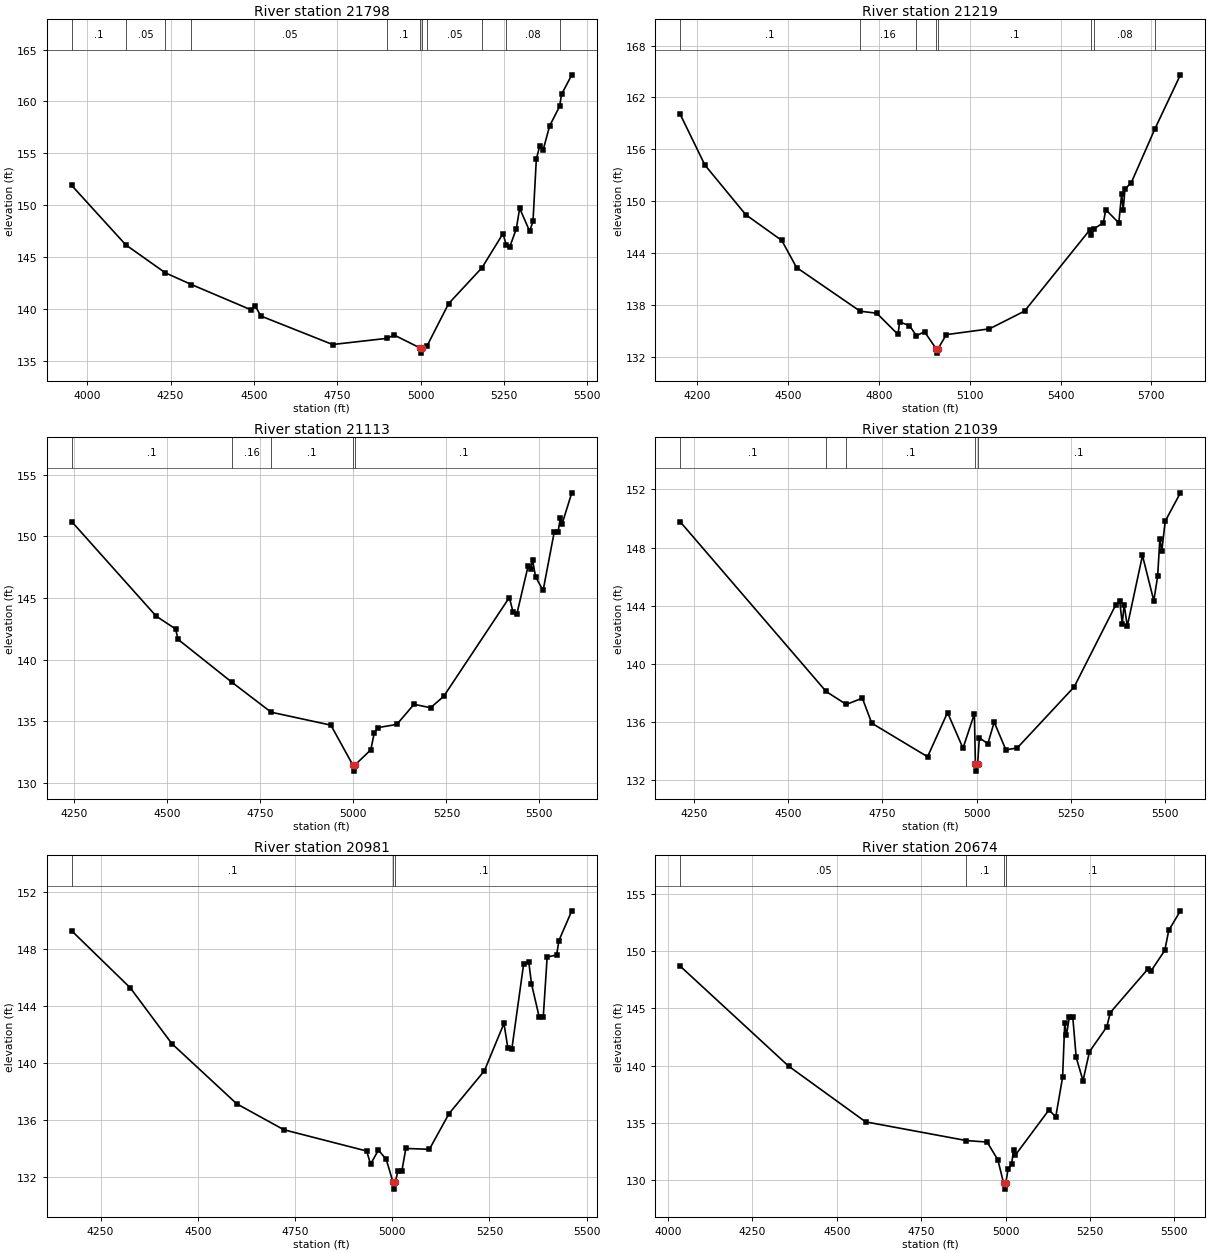
Type RM Length L Ch R = 1,21798,579,579,579
BEGIN DESCRIPTION:
UNT016 IN PECR 39.0
END DESCRIPTION:
XS GIS Cut Line= 4
      2331445.33     13243773.88      2331316.96     13243367.38
      2330629.70     13243009.04      2330331.46     13243001.05
#Sta/Elev= 30
  3953.6  151.90  4115.5  146.18  4234.0  143.48  4312.9  142.34  4491.8  139.90
  4504.4  140.26  4520.8  139.31  4736.1  136.56  4900.6  137.16  4920.4  137.48
  4998.2  136.23  5001.0  135.73  5004.2  136.23  5019.8  136.46  5083.9  140.50
  5184.2  143.97  5247.0  147.25  5256.8  146.16  5267.0  145.94  5287.0  147.72
  5297.0  149.70  5327.0  147.48  5337.0  148.43  5347.0  154.44  5357.0  155.67
  5367.0  155.27  5387.0  157.64  5416.7  159.51  5422.7  160.68  5453.3  162.56
#Mann=11,-1,0
  3953.6     0.1       0  4115.5    0.05       0  4234.0     0.1       0
  4312.9    0.05       0  4900.6     0.1       0  4998.2    0.07       0
  5004.2     0.1       0  5019.8    0.05       0  5184.2     0.1       0
  5256.8    0.08       0  5416.7     0.1       0
Bank Sta=4998.2,5004.2
Exp/Cntr=0.3,0.1

Type RM Length L Ch R = 1,21219,106,106,106
BEGIN DESCRIPTION:
UNT016 IN PECR 38.0
END DESCRIPTION:
XS GIS Cut Line= 3
      2331887.72     13243046.85      2331087.72     13242796.85
      2330287.71     13242946.86
#Sta/Elev= 30
  4143.7  160.03  4224.9  154.18  4360.0  148.43  4479.0  145.45  4527.7  142.32
  4737.9  137.26  4792.7  137.03  4862.9  134.57  4868.2  136.01  4900.7  135.60
  4923.7  134.42  4950.4  134.89  4989.0  132.91  4991.8  132.41  4995.0  132.91
  5022.5  134.55  5165.0  135.22  5281.1  137.28  5496.5  146.67  5501.4  146.09
  5511.1  146.82  5541.4  147.50  5549.1  149.02  5592.3  147.48  5601.6  150.84
  5606.7  148.98  5612.7  151.42  5633.0  152.10  5712.0  158.40  5795.8  164.62
#Mann=8,-1,0
  4143.7     0.1       0  4737.9    0.16       0  4923.7     0.1       0
  4989.0    0.07       0  4995.0     0.1       0  5501.4    0.05       0
  5511.1    0.08       0  5712.0    0.05       0
Bank Sta=4989,4995
Exp/Cntr=0.3,0.1

Type RM Length L Ch R = 1,21113,74,74,74
BEGIN DESCRIPTION:
Mapping XS d6047972
END DESCRIPTION:
XS GIS Cut Line= 5
      2331765.34     13242914.31      2331091.78     13242712.93
      2331029.28     13242699.04      2331001.50     13242716.40
      2330461.23     13242785.67
#Sta/Elev= 30
  4242.6  151.21  4469.7  143.54  4521.9  142.50  4528.8  141.65  4673.3  138.18
  4778.8  135.75  4939.4  134.70  4998.4  131.47  5001.2  130.97  5004.4  131.47
  5046.8  132.70  5056.3  134.10  5066.4  134.50  5116.8  134.76  5163.0  136.39
  5207.5  136.11  5242.7  137.03  5419.2  145.05  5429.3  143.87  5439.4  143.71
  5469.7  147.60  5476.6  147.35  5481.6  148.09  5489.8  146.73  5510.0  145.62
  5540.2  150.40  5550.3  150.38  5556.2  151.47  5561.3  151.04  5587.1  153.54
#Mann=5,-1,0
  4242.6     0.1       0  4673.3    0.16       0  4778.8     0.1       0
  4998.4    0.07       0  5004.4     0.1       0
Bank Sta=4998.4,5004.4
Exp/Cntr=0.3,0.1

Type RM Length L Ch R = 1,21039,58,58,58
BEGIN DESCRIPTION:
Mapping XS 8785bf8b
END DESCRIPTION:
XS GIS Cut Line= 6
      2331737.57     13242869.17      2331050.11     13242633.07
      2331011.92     13242633.07      2330973.72     13242653.90
      2330966.78     13242688.63      2330487.62     13242737.24
#Sta/Elev= 30
  4214.3  149.77  4600.8  138.10  4654.3  137.21  4696.9  137.64  4721.7  135.92
  4869.7  133.61  4922.6  136.65  4963.6  134.20  4993.8  136.56  4996.5  133.12
  4999.2  132.62  5002.5  133.12  5006.9  134.91  5029.5  134.51  5046.3  135.99
  5077.4  134.08  5107.6  134.22  5258.4  138.42  5368.9  144.08  5379.0  144.32
  5385.8  142.76  5390.8  144.08  5399.1  142.59  5439.3  147.46  5469.4  144.34
  5479.5  146.02  5485.5  148.62  5490.6  147.77  5499.6  149.82  5539.9  151.77
#Mann=5,-1,0
  4214.3     0.1       0  4600.8    0.16       0  4654.3     0.1       0
  4996.5    0.07       0  5002.5     0.1       0
Bank Sta=4996.5,5002.5
Exp/Cntr=0.3,0.1

Type RM Length L Ch R = 1,20981,307,307,307
BEGIN DESCRIPTION:
UNT016 IN PECR 37.0
END DESCRIPTION:
XS GIS Cut Line= 4
      2331751.54     13242799.75      2331074.42     13242580.99
      2330904.28     13242601.82      2330505.02     13242657.37
#Sta/Elev= 30
  4175.8  149.26  4326.6  145.26  4433.2  141.36  4600.2  137.14  4721.5  135.32
  4934.4  133.83  4944.5  132.91  4964.7  133.90  4984.8  133.24  5002.0  131.66
  5004.7  131.16  5008.0  131.66  5015.0  132.44  5025.1  132.46  5035.2  134.01
  5095.7  133.95  5146.2  136.45  5237.1  139.45  5287.5  142.77  5297.6  141.04
  5307.7  140.97  5338.0  146.91  5351.2  147.10  5358.2  145.56  5378.4  143.19
  5388.5  143.19  5398.6  147.43  5422.9  147.56  5428.9  148.58  5461.9  150.66
#Mann=3,-1,0
  4175.8     0.1       0  5002.0    0.07       0  5008.0     0.1       0
Bank Sta=5002,5008
Exp/Cntr=0.3,0.1

Type RM Length L Ch R = 1,20674,302,302,302
BEGIN DESCRIPTION:
Mapping XS c3d9332c
END DESCRIPTION:
XS GIS Cut Line= 3
      2331831.40     13242598.36      2331001.50     13242317.10
      2330401.74     13242396.83
#Sta/Elev= 30
  4036.7  148.69  4357.3  139.95  4585.5  135.07  4884.1  133.43  4945.5  133.30
  4977.3  131.74  4994.5  129.68  4997.2  129.18  5000.5  129.68  5007.6  130.93
  5017.7  131.34  5023.8  132.57  5028.9  132.15  5128.6  136.11  5148.8  135.51
  5169.0  138.97  5175.4  143.71  5180.4  142.63  5189.2  144.29  5199.2  144.24
  5209.3  140.71  5229.5  138.67  5248.6  141.21  5300.1  143.39  5310.2  144.63
  5421.2  148.43  5431.3  148.29  5471.6  150.07  5483.5  151.83  5518.0  153.54
#Mann=4,-1,0
  4036.7    0.05       0  4884.1     0.1       0  4994.5    0.07       0
  5000.5     0.1       0
Bank Sta=4994.5,5000.5
Exp/Cntr=0.3,0.1

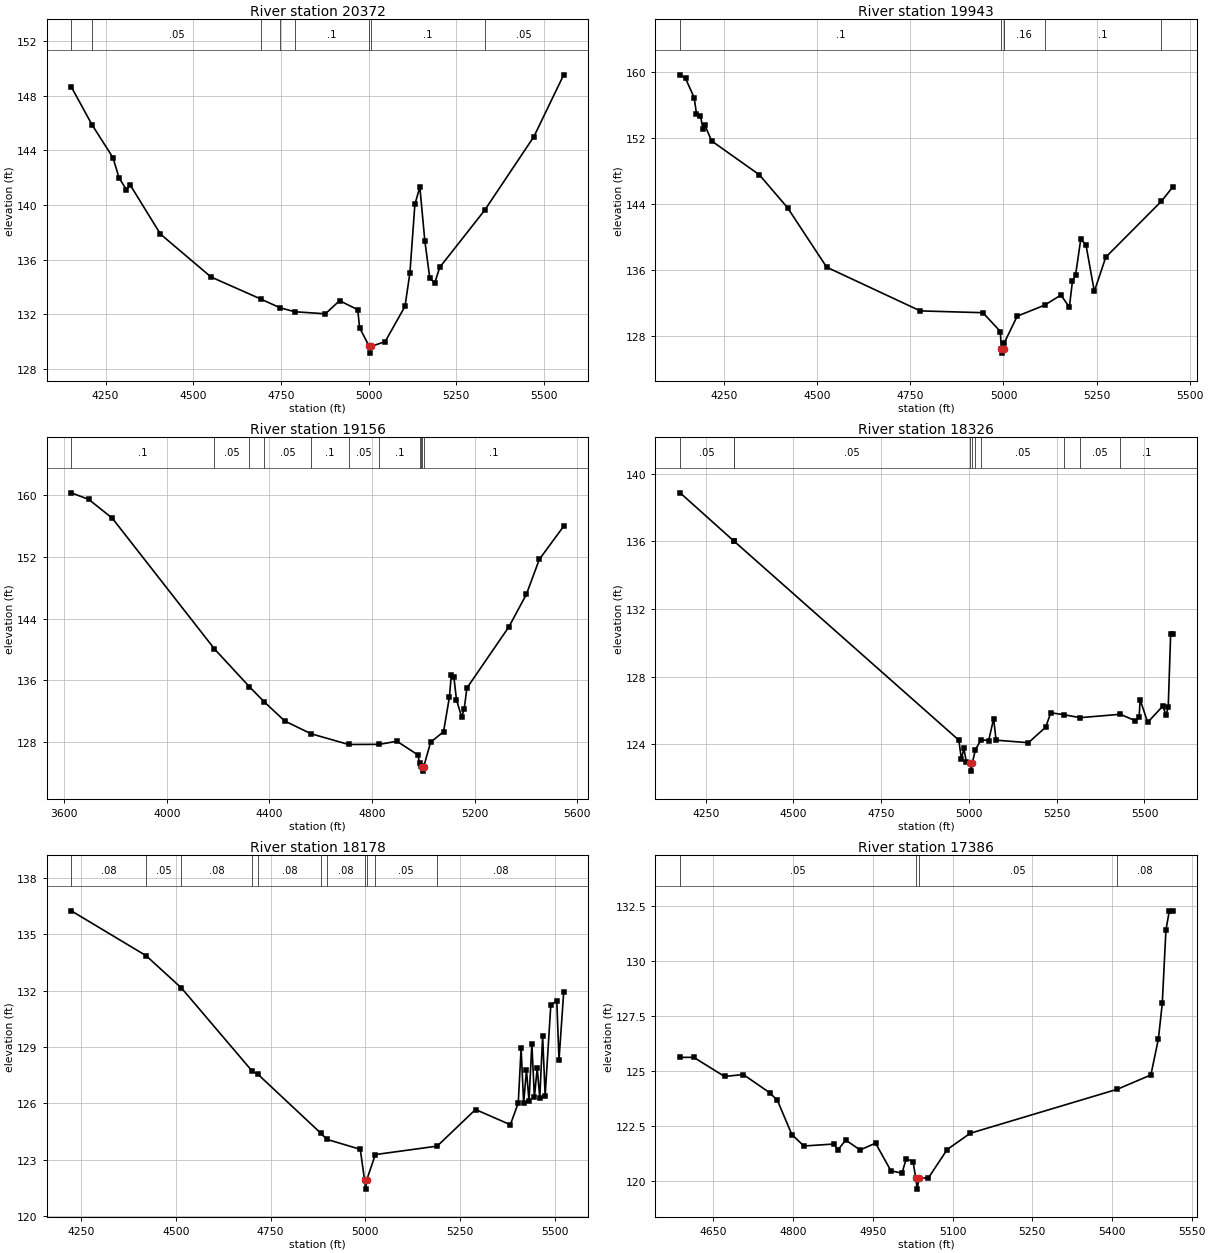
Type RM Length L Ch R = 1,20372,429,429,429
BEGIN DESCRIPTION:
UNT016 IN PECR 36.0
END DESCRIPTION:
XS GIS Cut Line= 3
      2331787.73     13242296.86      2330987.72     13242046.85
      2330587.75     13241646.89
#Sta/Elev= 30
  4152.4  148.65  4211.8  145.86  4271.3  143.46  4288.6  141.98  4309.6  141.12
  4320.0  141.48  4406.5  137.87  4550.5  134.73  4693.6  133.10  4747.6  132.47
  4789.6  132.18  4876.9  132.03  4917.2  132.99  4969.1  132.33  4974.3  131.01
  5001.7  129.65  5004.5  129.15  5007.7  129.65  5047.1  129.99  5103.7  132.57
  5117.8  135.03  5132.0  140.05  5146.1  141.31  5160.3  137.38  5174.4  134.65
  5188.5  134.28  5202.7  135.43  5330.8  139.61  5471.4  145.01  5556.2  149.53
#Mann=8,-1,0
  4152.4     0.1       0  4211.8    0.05       0  4693.6     0.1       0
  4747.6    0.05       0  4789.6     0.1       0  5001.7    0.07       0
  5007.7     0.1       0  5330.8    0.05       0
Bank Sta=5001.7,5007.7
Exp/Cntr=0.3,0.1

Type RM Length L Ch R = 1,19943,787,787,787
BEGIN DESCRIPTION:
UNT016 IN PECR 35.0
END DESCRIPTION:
XS GIS Cut Line= 3
      2331987.76     13242046.87      2331187.72     13241696.85
      2330787.69     13241496.84
#Sta/Elev= 30
  4132.9  159.65  4147.4  159.21  4170.8  156.87  4176.6  154.96  4187.5  154.69
  4194.1  153.06  4199.6  153.51  4217.5  151.63  4345.4  147.53  4421.0  143.54
  4525.9  136.33  4776.9  131.03  4945.0  130.81  4991.7  128.53  4994.2  126.41
  4996.9  125.91  5000.2  126.41  5002.1  127.15  5036.9  130.39  5110.1  131.72
  5154.3  132.95  5176.7  131.47  5185.0  134.61  5193.4  135.38  5207.4  139.74
  5221.4  139.00  5243.7  133.40  5274.5  137.55  5423.6  144.32  5453.4  146.02
#Mann=6,-1,0
  4132.9     0.1       0  4994.2    0.07       0  5000.2     0.1       0
  5002.1    0.16       0  5110.1     0.1       0  5423.6    0.05       0
Bank Sta=4994.2,5000.2
Exp/Cntr=0.3,0.1

Type RM Length L Ch R = 1,19156,830,830,830
BEGIN DESCRIPTION:
Mapping XS a4d248cc
END DESCRIPTION:
XS GIS Cut Line= 3
      2332366.97     13241893.51      2331526.68     13241080.99
      2330783.59     13240983.76
#Sta/Elev= 30
  3628.3  160.31  3696.2  159.46  3788.1  157.02  4185.8  140.10  4321.6  135.21
  4380.3  133.22  4460.0  130.75  4562.3  129.10  4708.9  127.71  4828.7  127.73
  4897.0  128.13  4977.7  126.38  4985.6  125.34  4989.7  124.98  4994.8  124.76
  4997.6  124.26  5000.8  124.76  5028.1  128.01  5078.5  129.36  5101.3  133.83
  5108.8  136.73  5118.9  136.42  5128.9  133.51  5149.1  131.27  5159.2  132.33
  5169.3  135.01  5332.9  142.94  5401.2  147.16  5451.7  151.69  5546.6  155.99
#Mann=11,-1,0
  3628.3     0.1       0  4185.8    0.05       0  4321.6     0.1       0
  4380.3    0.05       0  4562.3     0.1       0  4708.9    0.05       0
  4828.7     0.1       0  4985.6    0.05       0  4989.7     0.1       0
  4994.8    0.07       0  5000.8     0.1       0
Bank Sta=4994.8,5000.8
Exp/Cntr=0.3,0.1

Type RM Length L Ch R = 1,18326,148,148,148
BEGIN DESCRIPTION:
UNT016 IN PECR 34.0
END DESCRIPTION:
XS GIS Cut Line= 3
      2332490.96     13241276.49      2331587.66     13240334.37
      2331503.53     13240284.90
#Sta/Elev= 30
  4177.1  138.86  4330.2  136.01  4330.4  136.01  4971.2  124.24  4978.5  123.10
  4985.4  123.77  4992.6  122.94  5003.8  122.91  5006.5  122.41  5009.8  122.91
  5018.4  123.68  5034.7  124.27  5056.1  124.21  5070.3  125.51  5077.2  124.24
  5169.4  124.09  5218.7  125.01  5232.9  125.86  5272.1  125.74  5316.4  125.57
  5431.3  125.77  5473.5  125.39  5484.8  125.58  5487.6  126.64  5509.1  125.29
  5552.0  126.25  5561.9  125.73  5567.7  126.20  5574.6  130.53  5579.9  130.53
#Mann=10,-1,0
  4177.1    0.05       0  4330.2     0.1       0  4330.4    0.05       0
  5003.8    0.04       0  5009.8    0.05       0  5018.4     0.1       0
  5034.7    0.05       0  5272.1     0.1       0  5316.4    0.05       0
  5431.3     0.1       0
Bank Sta=5003.8,5009.8
Exp/Cntr=0.3,0.1

Type RM Length L Ch R = 1,18178,792,792,792
BEGIN DESCRIPTION:
UNT016 IN PECR 33.0
END DESCRIPTION:
XS GIS Cut Line= 3
      2332610.02     13241101.83      2331672.22     13240268.02
      2331632.50     13240245.35
#Sta/Elev= 30
  4223.5  136.25  4421.2  133.86  4514.5  132.14  4701.4  127.71  4716.7  127.54
  4882.5  124.41  4898.6  124.08  4986.8  123.55  4998.0  121.93  5000.8  121.43
  5004.0  121.93  5026.6  123.27  5190.0  123.72  5291.2  125.67  5383.2  124.86
  5404.1  126.02  5411.6  128.94  5418.3  126.01  5425.8  127.77  5432.5  126.12
  5440.0  129.17  5446.7  126.33  5454.2  127.88  5460.9  126.28  5468.5  129.59
  5475.1  126.40  5490.1  131.25  5505.9  131.45  5511.7  128.31  5524.1  131.91
#Mann=11,-1,0
  4223.5    0.08       0  4421.2    0.05       0  4514.5    0.08       0
  4701.4     0.1       0  4716.7    0.08       0  4882.5     0.1       0
  4898.6    0.08       0  4998.0    0.07       0  5004.0    0.08       0
  5026.6    0.05       0  5190.0    0.08       0
Bank Sta=4998,5004
Exp/Cntr=0.3,0.1

Type RM Length L Ch R = 1,17386,383,383,383
BEGIN DESCRIPTION:
Mapping XS 3ec79690
END DESCRIPTION:
XS GIS Cut Line= 3
      2332323.71     13239646.57      2331835.46     13240026.33
      2331614.04     13240240.64
#Sta/Elev= 30
  4587.3  125.62  4613.0  125.62  4670.9  124.75  4706.2  124.84  4756.0  124.01
  4770.5  123.66  4797.6  122.11  4820.3  121.59  4876.4  121.68  4884.5  121.42
  4898.9  121.86  4926.1  121.41  4955.1  121.72  4984.1  120.46  5004.9  120.36
  5013.0  121.02  5025.7  120.87  5030.8  120.13  5033.6  119.63  5036.8  120.13
  5054.6  120.14  5089.9  121.43  5133.4  122.17  5410.1  124.17  5473.3  124.82
  5487.5  126.47  5494.7  128.07  5501.6  131.41  5508.0  132.28  5514.0  132.28
#Mann=4,-1,0
  4587.3    0.05       0  5030.8    0.03       0  5036.8    0.05       0
  5410.1    0.08       0
Bank Sta=5030.8,5036.8
Exp/Cntr=0.3,0.1

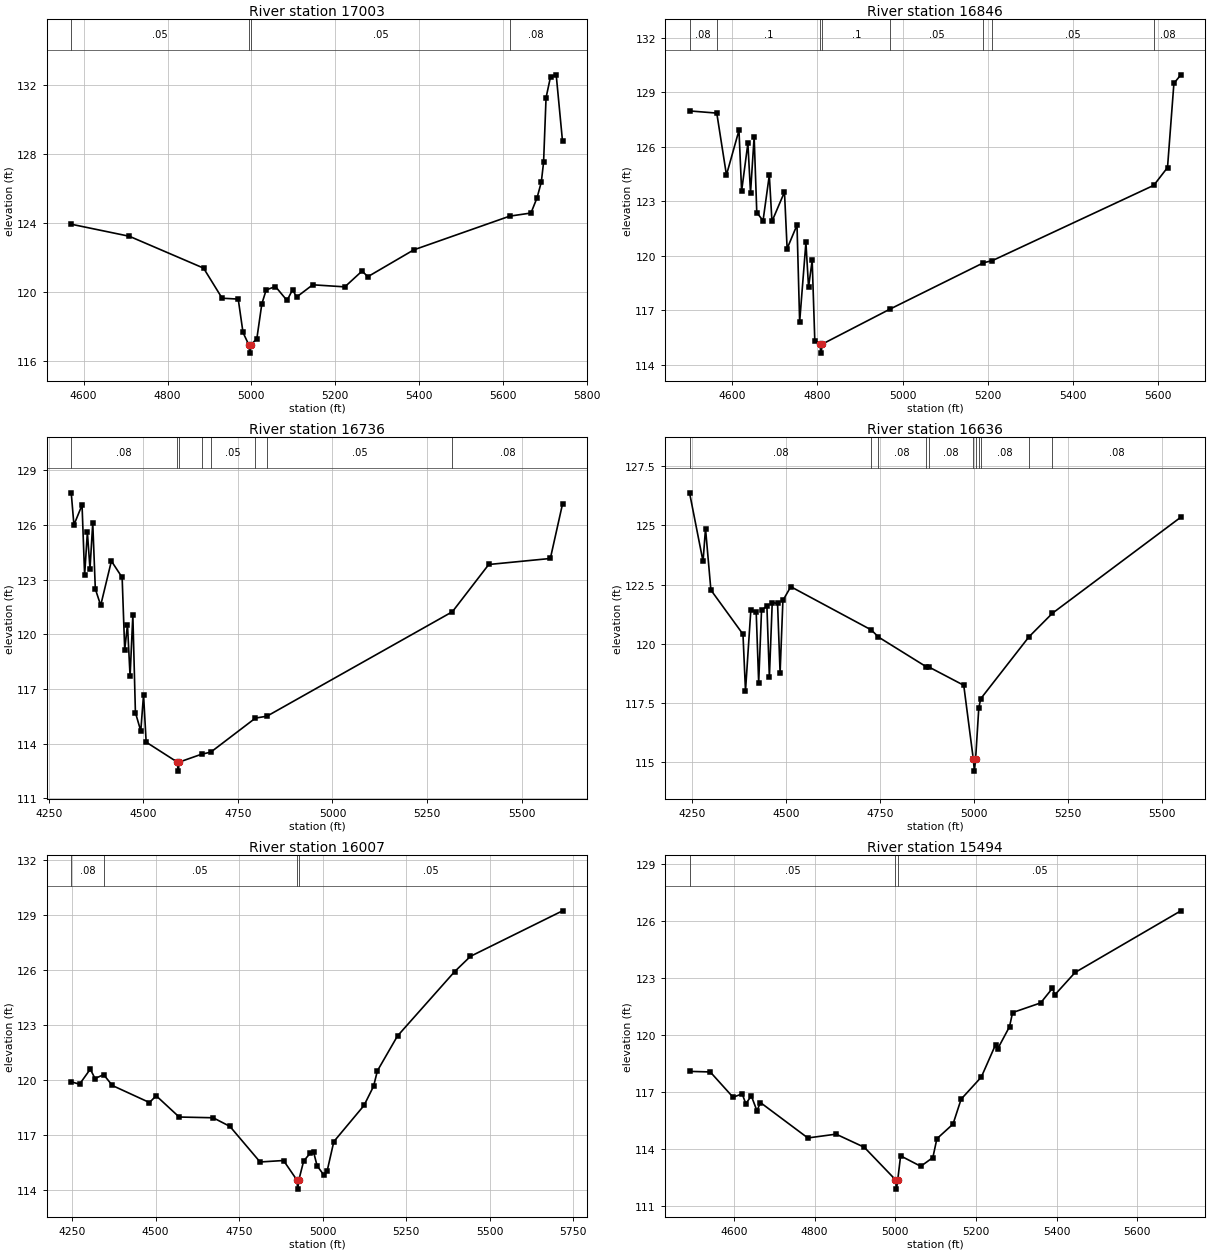
Type RM Length L Ch R = 1,17003,157,157,157
BEGIN DESCRIPTION:
UNT016 IN PECR 32.0
END DESCRIPTION:
XS GIS Cut Line= 3
      2332058.83     13239173.27      2331815.76     13239642.05
      2331586.41     13240243.56
#Sta/Elev= 30
  4570.3  123.93  4708.9  123.23  4885.9  121.38  4930.2  119.63  4968.6  119.58
  4980.0  117.64  4993.5  116.94  4996.3  116.44  4999.5  116.94  5013.0  117.28
  5024.9  119.30  5035.2  120.11  5057.3  120.31  5085.0  119.50  5098.2  120.12
  5107.9  119.70  5146.3  120.41  5222.9  120.29  5264.0  121.21  5277.7  120.88
  5387.3  122.44  5616.2  124.40  5666.8  124.58  5681.4  125.47  5691.5  126.38
  5696.9  127.53  5702.8  131.28  5713.5  132.50  5727.0  132.61  5742.1  128.74
#Mann=4,-1,0
  4570.3    0.05       0  4993.5    0.03       0  4999.5    0.05       0
  5616.2    0.08       0
Bank Sta=4993.5,4999.5
Exp/Cntr=0.3,0.1

Type RM Length L Ch R = 1,16846,110,110,110
BEGIN DESCRIPTION:
Mapping XS d9a01cd7
END DESCRIPTION:
XS GIS Cut Line= 3
      2332023.05     13239061.17      2331767.82     13239415.36
      2331365.57     13240008.33
#Sta/Elev= 30
  4500.2  127.98  4564.1  127.86  4586.8  124.45  4616.2  126.91  4622.4  123.56
  4637.1  126.20  4643.3  123.46  4651.8  126.56  4658.0  122.38  4672.7  121.93
  4687.4  124.44  4693.6  121.89  4723.0  123.51  4729.2  120.39  4752.4  121.69
  4758.6  116.35  4773.3  120.73  4779.5  118.27  4788.0  119.74  4794.2  115.29
  4805.9  115.13  4808.7  114.63  4811.9  115.13  4971.8  117.07  5190.0  119.61
  5211.0  119.73  5589.8  123.88  5622.0  124.86  5637.0  129.50  5653.3  129.97
#Mann=8,-1,0
  4500.2    0.08       0  4564.1     0.1       0  4805.9    0.03       0
  4811.9     0.1       0  4971.8    0.05       0  5190.0     0.1       0
  5211.0    0.05       0  5589.8    0.08       0
Bank Sta=4805.9,4811.9
Exp/Cntr=0.3,0.1

Type RM Length L Ch R = 1,16736,100,100,100
BEGIN DESCRIPTION:
UNT016 IN PECR 31.0
END DESCRIPTION:
XS GIS Cut Line= 3
      2332105.92     13238914.94      2331751.13     13239294.35
      2331227.70     13239872.04
#Sta/Elev= 30
  4309.3  127.76  4316.4  126.00  4337.9  127.09  4344.7  123.24  4352.0  125.60
  4358.9  123.59  4366.2  126.11  4373.0  122.49  4387.2  121.59  4415.5  124.02
  4443.9  123.12  4450.7  119.15  4458.0  120.53  4464.9  117.70  4472.2  121.06
  4479.0  115.71  4493.2  114.70  4500.5  116.69  4507.4  114.09  4589.4  113.00
  4592.1  112.50  4595.4  113.00  4654.2  113.43  4678.2  113.54  4796.5  115.41
  4826.6  115.51  5317.1  121.24  5413.2  123.83  5576.1  124.16  5608.3  127.15
#Mann=8,-1,0
  4309.3    0.08       0  4589.4    0.04       0  4595.4    0.08       0
  4654.2     0.1       0  4678.2    0.05       0  4796.5     0.1       0
  4826.6    0.05       0  5317.1    0.08       0
Bank Sta=4589.4,4595.4
Exp/Cntr=0.3,0.1

Type RM Length L Ch R = 1,16636,629,629,629
BEGIN DESCRIPTION:
UNT016 IN PECR 30.0
END DESCRIPTION:
XS GIS Cut Line= 2
      2332135.15     13238854.23      2331148.58     13239712.73
#Sta/Elev= 30
  4242.7  126.38  4278.6  123.48  4285.2  124.87  4299.5  122.27  4384.9  120.40
  4391.6  118.00  4405.8  121.42  4420.1  121.34  4426.7  118.35  4434.3  121.41
  4448.6  121.59  4455.2  118.58  4462.8  121.74  4477.0  121.70  4483.7  118.76
  4491.2  121.83  4512.2  122.41  4726.6  120.58  4745.6  120.28  4872.2  119.03
  4879.1  119.02  4972.6  118.24  4998.1  115.11  5000.9  114.61  5004.1  115.11
  5012.6  117.27  5017.7  117.67  5146.2  120.29  5208.8  121.29  5550.5  125.35
#Mann=11,-1,0
  4242.7    0.08       0  4726.6    0.05       0  4745.6    0.08       0
  4872.2    0.05       0  4879.1    0.08       0  4998.1    0.07       0
  5004.1    0.08       0  5012.6    0.05       0  5017.7    0.08       0
  5146.2    0.05       0  5208.8    0.08       0
Bank Sta=4998.1,5004.1
Exp/Cntr=0.3,0.1

Type RM Length L Ch R = 1,16007,513,513,513
BEGIN DESCRIPTION:
UNT016 IN PECR 29.0
END DESCRIPTION:
XS GIS Cut Line= 4
      2332099.76     13238790.10      2331977.89     13238735.26
      2330917.32     13238826.69      2330686.62     13238972.39
#Sta/Elev= 30
  4247.6  119.89  4272.5  119.76  4304.7  120.58  4318.8  120.07  4344.8  120.28
  4370.6  119.69  4481.8  118.76  4501.9  119.13  4570.8  117.97  4672.5  117.93
  4722.7  117.46  4813.0  115.52  4883.3  115.60  4923.1  114.54  4925.8  114.04
  4929.1  114.54  4943.5  115.57  4963.6  116.01  4973.6  116.04  4983.6  115.32
  5003.7  114.81  5013.7  115.02  5033.8  116.63  5124.2  118.60  5152.9  119.65
  5164.3  120.49  5224.5  122.39  5395.2  125.89  5443.0  126.73  5718.6  129.21
#Mann=4,-1,0
  4247.6    0.08       0  4344.8    0.05       0  4923.1    0.03       0
  4929.1    0.05       0
Bank Sta=4923.1,4929.1
Exp/Cntr=0.3,0.1

Type RM Length L Ch R = 1,15494,819,819,819
BEGIN DESCRIPTION:
UNT016 IN PECR 28.0
END DESCRIPTION:
XS GIS Cut Line= 4
      2331983.09     13238428.65      2331770.47     13238316.09
      2331207.61     13238322.34      2330876.58     13238572.18
#Sta/Elev= 30
  4490.1  118.10  4541.4  118.07  4598.0  116.74  4620.6  116.92  4629.6  116.40
  4643.3  116.81  4657.2  116.03  4665.9  116.46  4783.4  114.60  4853.4  114.80
  4923.4  114.11  5000.4  112.41  5003.2  111.91  5006.4  112.41  5013.4  113.66
  5063.4  113.11  5093.4  113.57  5103.4  114.56  5143.4  115.33  5163.5  116.64
  5213.5  117.80  5249.0  119.51  5254.0  119.28  5283.5  120.45  5291.0  121.19
  5360.7  121.70  5389.9  122.47  5396.1  122.13  5446.1  123.30  5708.3  126.54
#Mann=3,-1,0
  4490.1    0.05       0  5000.4    0.03       0  5006.4    0.05       0
Bank Sta=5000.4,5006.4
Exp/Cntr=0.3,0.1

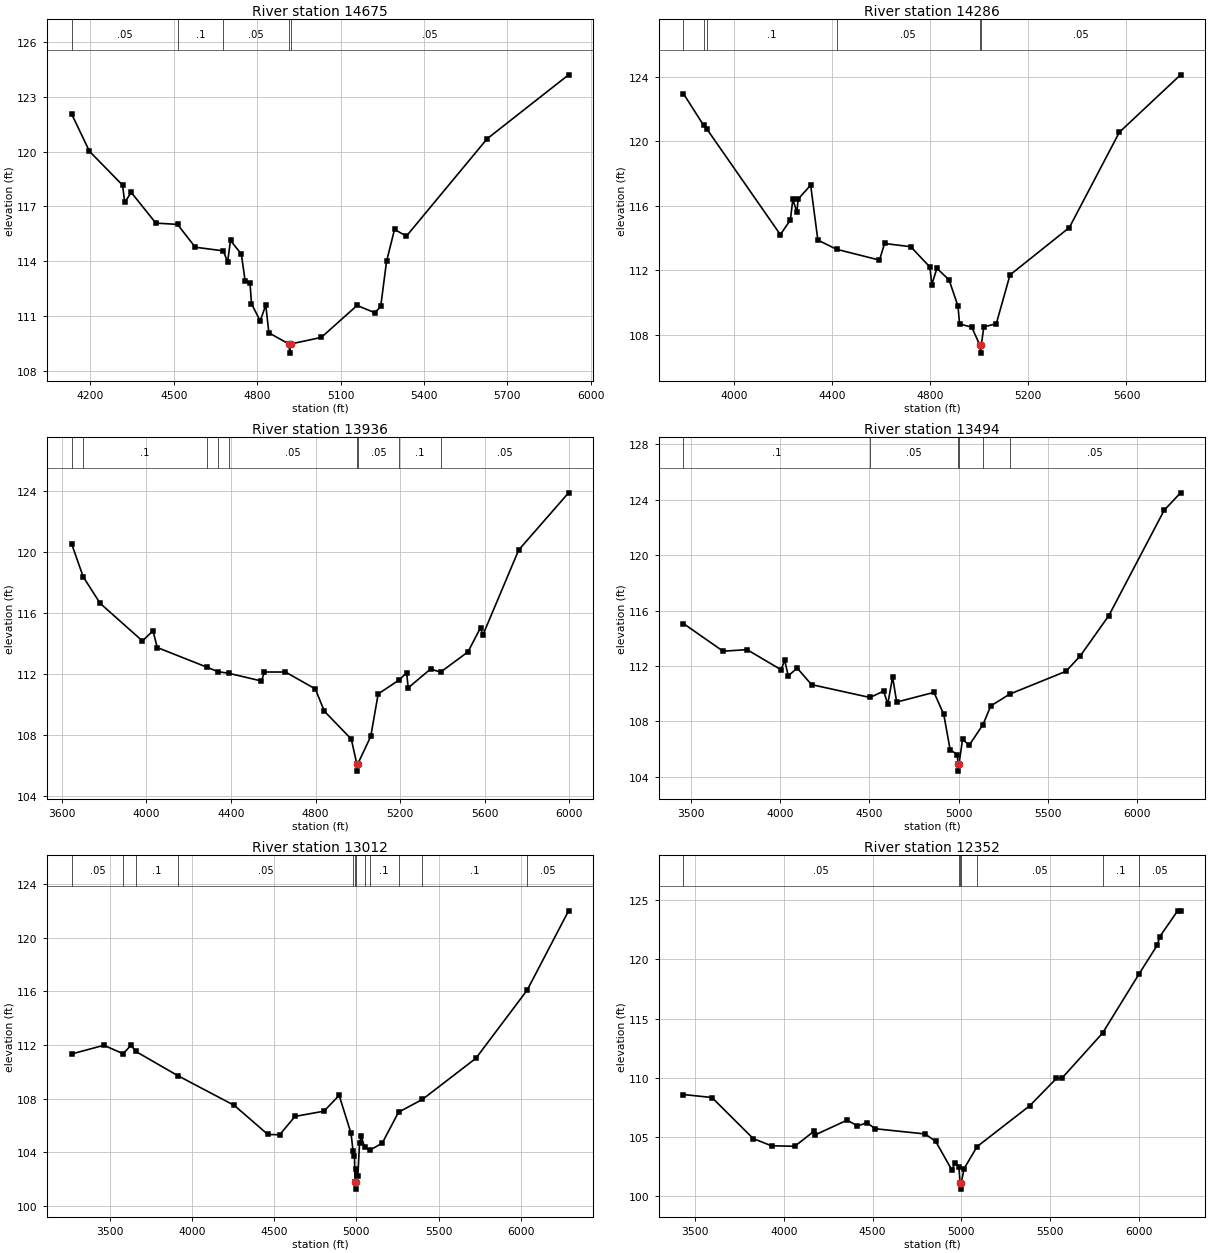
Type RM Length L Ch R = 1,14675,389,389,389
BEGIN DESCRIPTION:
UNT016 IN PECR 27.0
END DESCRIPTION:
XS GIS Cut Line= 4
      2332508.83     13237353.20      2331814.57     13237591.04
      2331313.14     13238002.47      2331004.57     13238266.04
#Sta/Elev= 30
  4132.1  122.07  4196.7  120.01  4315.7  118.16  4323.5  117.22  4347.0  117.76
  4435.5  116.08  4513.4  116.01  4577.2  114.76  4678.4  114.56  4693.5  113.95
  4704.1  115.13  4743.1  114.38  4756.9  112.89  4774.3  112.80  4779.6  111.67
  4810.9  110.72  4830.9  111.59  4842.2  110.07  4914.3  109.46  4917.1  108.96
  4920.3  109.46  5030.7  109.82  5159.4  111.57  5223.7  111.17  5244.5  111.52
  5265.4  113.98  5294.1  115.73  5337.1  115.37  5627.5  120.70  5920.4  124.20
#Mann=5,-1,0
  4132.1    0.05       0  4513.4     0.1       0  4678.4    0.05       0
  4914.3    0.03       0  4920.3    0.05       0
Bank Sta=4914.3,4920.3
Exp/Cntr=0.3,0.1

Type RM Length L Ch R = 1,14286,350,350,350
BEGIN DESCRIPTION:
UNT016 IN PECR 26.0
END DESCRIPTION:
XS GIS Cut Line= 4
      2332444.52     13237051.05      2331801.71     13237179.62
      2331062.42     13237803.19      2330927.52     13238182.20
#Sta/Elev= 30
  3795.5  122.94  3877.6  120.97  3890.2  120.76  4190.0  114.20  4230.8  115.10
  4241.0  116.39  4257.4  115.59  4262.5  116.40  4313.5  117.27  4342.9  113.86
  4419.2  113.29  4593.9  112.62  4614.7  113.65  4721.3  113.45  4799.3  112.19
  4807.1  111.10  4827.9  112.11  4877.4  111.39  4913.7  109.77  4920.2  108.66
  4969.7  108.46  5002.7  107.35  5005.5  106.85  5008.7  107.35  5019.1  108.48
  5069.7  108.67  5125.7  111.70  5367.5  114.64  5571.2  120.55  5820.5  124.11
#Mann=6,-1,0
  3795.5     0.1       0  3877.6    0.05       0  3890.2     0.1       0
  4419.2    0.05       0  5002.7    0.03       0  5008.7    0.05       0
Bank Sta=5002.7,5008.7
Exp/Cntr=0.3,0.1

Type RM Length L Ch R = 1,13936,442,442,442
BEGIN DESCRIPTION:
UNT016 IN PECR 25.0
END DESCRIPTION:
XS GIS Cut Line= 4
      2332303.11     13236800.33      2331679.57     13236800.33
      2330856.71     13237546.04      2330831.02     13238162.47
#Sta/Elev= 30
  3645.8  120.57  3700.9  118.39  3781.2  116.64  3981.2  114.17  4031.2  114.84
  4051.2  113.74  4287.5  112.44  4339.3  112.15  4388.6  112.05  4544.1  111.54
  4558.3  112.13  4657.6  112.13  4798.9  111.02  4841.4  109.56  4969.2  107.72
  4994.6  106.12  4997.3  105.62  5000.6  106.12  5061.1  107.90  5096.2  110.69
  5195.8  111.61  5230.7  112.09  5238.2  111.09  5344.3  112.33  5391.0  112.12
  5520.8  113.45  5580.8  115.05  5590.8  114.54  5761.0  120.15  5996.8  123.90
#Mann=9,-1,0
  3645.8    0.05       0  3700.9     0.1       0  4287.5    0.05       0
  4339.3     0.1       0  4388.6    0.05       0  4994.6    0.03       0
  5000.6    0.05       0  5195.8     0.1       0  5391.0    0.05       0
Bank Sta=4994.6,5000.6
Exp/Cntr=0.3,0.1

Type RM Length L Ch R = 1,13494,482,482,482
BEGIN DESCRIPTION:
UNT016 IN PECR 24.0
END DESCRIPTION:
XS GIS Cut Line= 5
      2332123.16     13236517.47      2331133.14     13236581.76
      2330940.28     13236716.76      2330638.14     13237391.76
      2330663.85     13238208.19
#Sta/Elev= 30
  3459.5  115.06  3680.9  113.07  3815.7  113.18  4006.1  111.73  4026.1  112.42
  4046.2  111.29  4096.3  111.85  4176.5  110.66  4504.2  109.73  4580.3  110.19
  4603.7  109.26  4630.7  111.20  4653.5  109.40  4862.4  110.10  4917.2  108.51
  4952.9  105.96  4993.8  105.61  4996.3  104.92  4999.1  104.42  5002.3  104.92
  5022.5  106.71  5059.6  106.29  5137.2  107.78  5180.2  109.12  5285.7  109.97
  5601.7  111.62  5681.8  112.73  5841.9  115.64  6152.0  123.24  6243.4  124.49
#Mann=6,-1,0
  3459.5     0.1       0  4504.2    0.05       0  4996.3    0.03       0
  5002.3    0.05       0  5137.2     0.1       0  5285.7    0.05       0
Bank Sta=4996.3,5002.3
Exp/Cntr=0.3,0.1

Type RM Length L Ch R = 1,13012,660,660,660
BEGIN DESCRIPTION:
UNT016 IN PECR 23.0
END DESCRIPTION:
XS GIS Cut Line= 4
      2331658.52     13236069.74      2330496.79     13236360.17
      2330187.72     13237546.85      2330457.67     13238082.64
#Sta/Elev= 30
  3267.2  111.33  3463.9  111.98  3581.3  111.35  3628.8  111.98  3658.3  111.52
  3914.1  109.71  4257.6  107.49  4461.6  105.32  4533.6  105.30  4626.6  106.67
  4802.8  107.06  4895.3  108.24  4967.6  105.40  4979.5  104.12  4988.3  103.72
  4992.0  101.74  4994.8  101.24  4998.0  101.74  5000.2  102.78  5008.9  102.20
  5019.3  104.68  5029.6  105.18  5049.6  104.39  5080.8  104.14  5157.0  104.67
  5256.8  106.99  5401.9  107.94  5727.2  111.01  6039.0  116.10  6290.9  122.02
#Mann=12,-1,0
  3267.2    0.05       0  3581.3    0.08       0  3658.3     0.1       0
  3914.1    0.05       0  4979.5     0.1       0  4992.0    0.07       0
  4998.0     0.1       0  5049.6    0.16       0  5080.8     0.1       0
  5256.8    0.05       0  5401.9     0.1       0  6039.0    0.05       0
Bank Sta=4992,4998
Exp/Cntr=0.3,0.1

Type RM Length L Ch R = 1,12352,688,688,688
BEGIN DESCRIPTION:
UNT016 IN PECR 22.0
END DESCRIPTION:
XS GIS Cut Line= 4
      2330602.30     13235979.66      2329715.85     13236526.62
      2329763.00     13237658.23      2330130.80     13238167.50
#Sta/Elev= 30
  3434.3  108.58  3594.6  108.33  3827.4  104.86  3930.5  104.25  4061.7  104.21
  4168.2  105.46  4177.6  105.18  4357.3  106.42  4415.3  105.92  4467.3  106.20
  4516.2  105.69  4796.4  105.25  4856.5  104.62  4946.6  102.22  4966.6  102.80
  4987.1  102.47  4993.6  101.09  4996.3  100.59  4999.6  101.09  5016.6  102.33
  5089.3  104.18  5386.9  107.64  5537.1  109.95  5567.1  109.95  5796.9  113.77
  6002.9  118.77  6104.9  121.19  6119.6  121.92  6220.2  124.10  6236.7  124.08
#Mann=7,-1,0
  3434.3    0.05       0  4987.1     0.1       0  4993.6    0.07       0
  4999.6     0.1       0  5089.3    0.05       0  5796.9     0.1       0
  6002.9    0.05       0
Bank Sta=4993.6,4999.6
Exp/Cntr=0.3,0.1