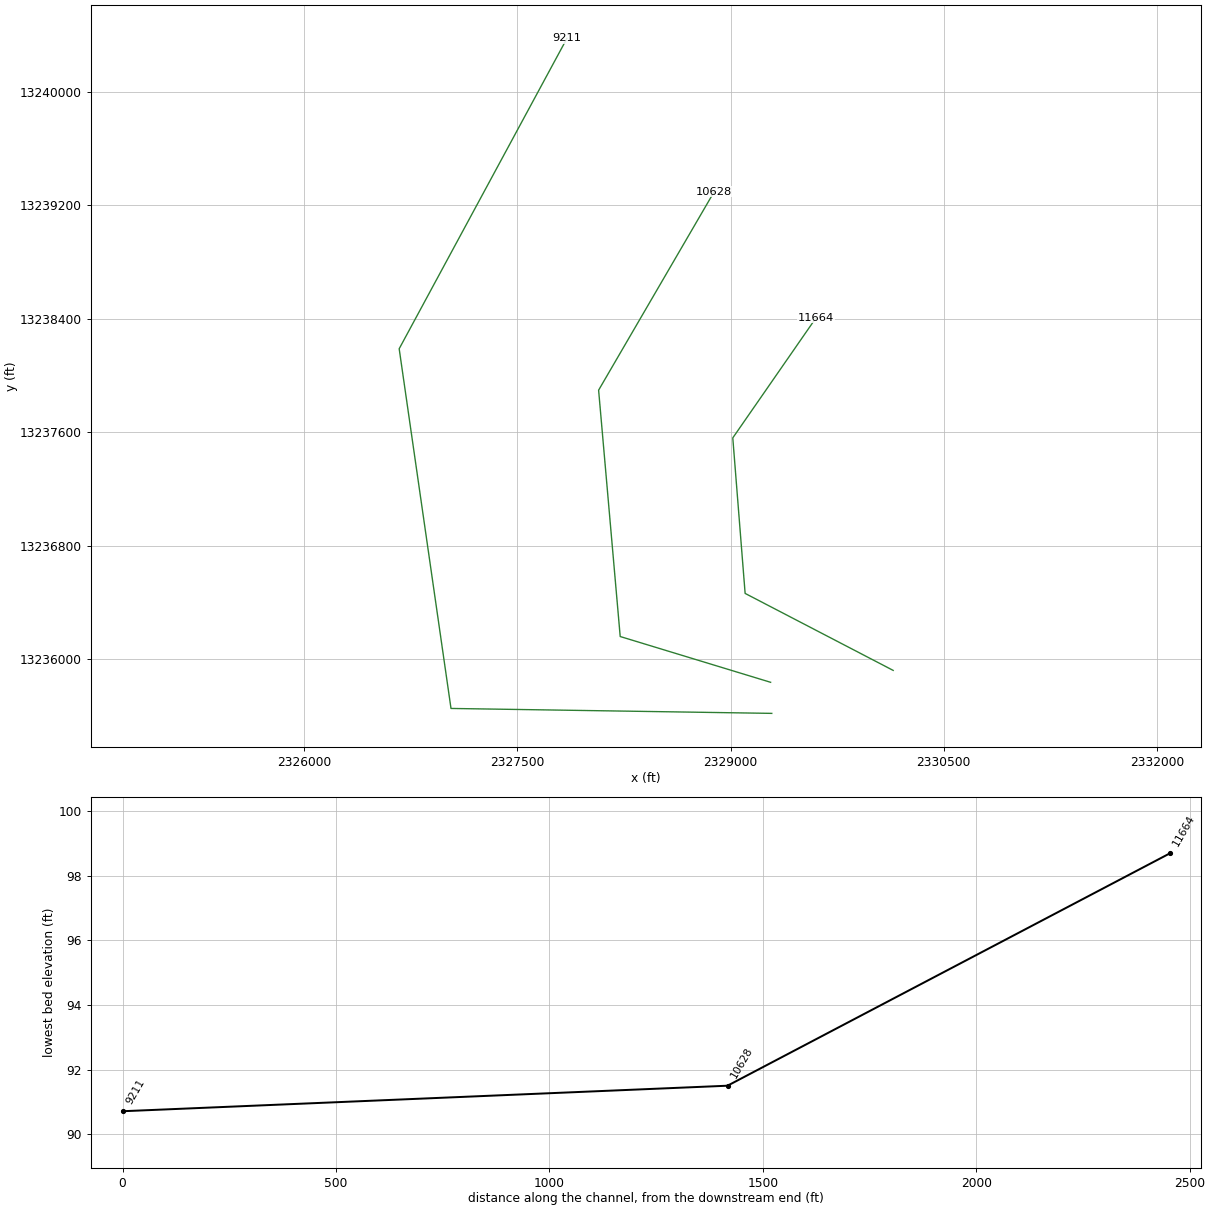
HEC-RAS study UNT016 IN PECR.prj: UNT016 IN PECR Base Level Engineering

--- UNT016 IN PECR.g01 (geometry) --- (continued)

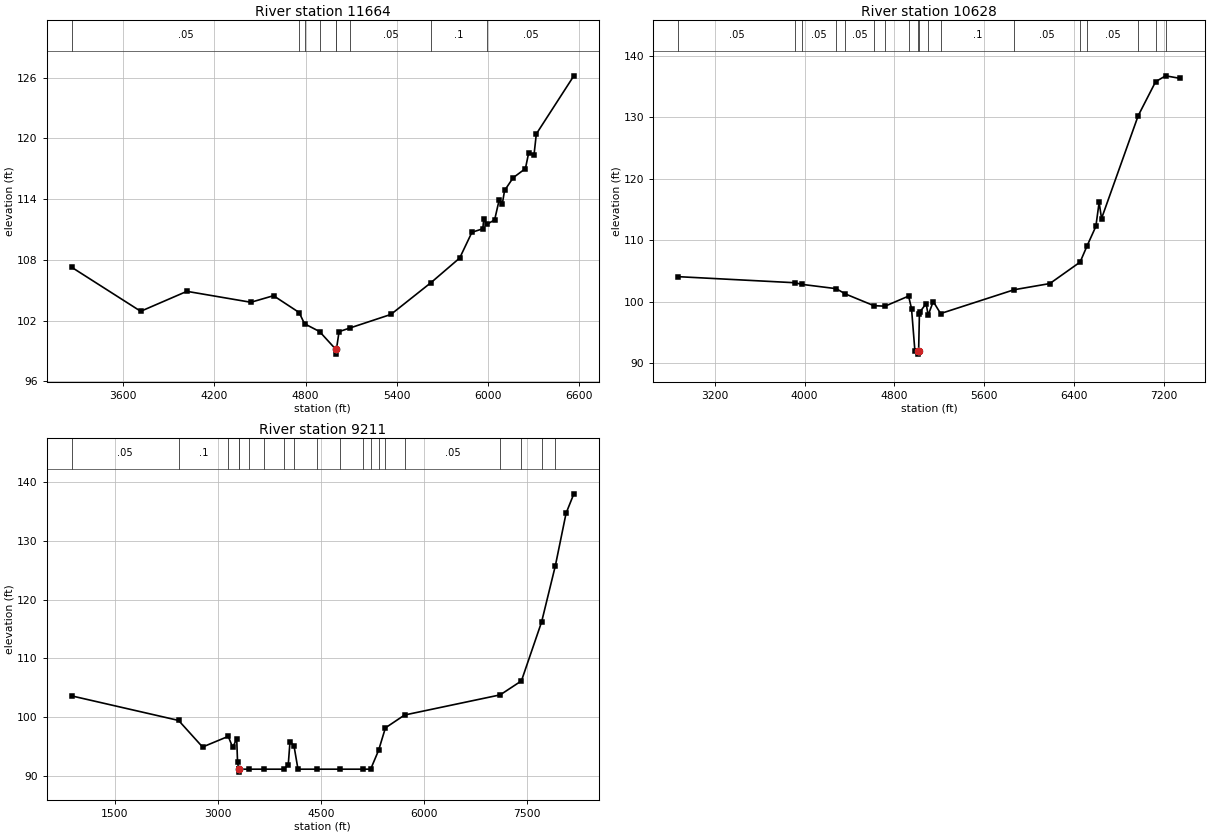
Type RM Length L Ch R = 1,11664,1036,1036,1036
BEGIN DESCRIPTION:
UNT016 IN PECR 20.0
END DESCRIPTION:
XS GIS Cut Line= 4
      2330144.44     13235922.08      2329102.79     13236464.62
      2329015.98     13237560.54      2329601.91     13238406.88
#Sta/Elev= 30
  3261.4  107.26  3714.9  102.92  4018.7  104.89  4439.9  103.81  4588.6  104.46
  4757.2  102.80  4792.6  101.69  4891.5  100.92  4996.9   99.19  4999.6   98.69
  5002.9   99.19  5019.9  100.91  5089.2  101.26  5361.0  102.61  5625.6  105.76
  5813.6  108.18  5894.0  110.72  5965.6  111.07  5971.7  112.00  5993.4  111.52
  6043.3  111.94  6073.1  113.90  6094.0  113.53  6108.9  114.85  6165.6  116.11
  6246.0  117.01  6267.0  118.54  6302.8  118.40  6317.7  120.43  6564.6  126.17
#Mann=9,-1,0
  3261.4    0.05       0  4757.2     0.1       0  4792.6    0.05       0
  4891.5     0.1       0  4996.9    0.07       0  5002.9     0.1       0
  5089.2    0.05       0  5625.6     0.1       0  5993.4    0.05       0
Bank Sta=4996.9,5002.9
Exp/Cntr=0.3,0.1

Type RM Length L Ch R = 1,10628,1417,1417,1417
BEGIN DESCRIPTION:
UNT016 IN PECR 17.0
END DESCRIPTION:
XS GIS Cut Line= 4
      2329282.05     13235838.23      2328223.88     13236160.80
      2328071.97     13237896.91      2328885.77     13239296.64
#Sta/Elev= 30
  2876.0  104.10  3916.2  103.11  3974.6  102.85  4281.9  102.15  4361.9  101.30
  4617.4   99.38  4716.3   99.30  4925.8  100.94  4952.0   98.92  4982.1   92.03
  5009.2   92.00  5012.0   91.50  5015.2   92.00  5022.3   97.96  5027.7   98.39
  5082.5   99.72  5100.0   97.82  5145.2  100.06  5210.8   98.10  5866.4  101.98
  6183.0  102.98  6452.3  106.47  6515.8  109.17  6592.5  112.27  6621.6  116.19
  6643.1  113.56  6969.2  130.28  7124.5  135.82  7213.4  136.77  7344.1  136.35
#Mann=18,-1,0
  2876.0    0.05       0  3916.2     0.1       0  3974.6    0.05       0
  4281.9     0.1       0  4361.9    0.05       0  4617.4     0.1       0
  4716.3    0.05       0  4925.8    0.16       0  5009.2    0.07       0
  5015.2    0.16       0  5100.0    0.05       0  5210.8     0.1       0
  5866.4    0.05       0  6452.3     0.1       0  6515.8    0.05       0
  6969.2     0.1       0  7124.5    0.05       0  7213.4     0.1       0
Bank Sta=5009.2,5015.2
Exp/Cntr=0.3,0.1

Type RM Length L Ch R = 1,9211,0,0,0
BEGIN DESCRIPTION:
UNT016 IN PECR 1.0
END DESCRIPTION:
XS GIS Cut Line= 4
      2329290.31     13235619.21      2327033.36     13235653.94
      2326668.78     13238188.66      2327849.35     13240376.19
#Sta/Elev= 30
   876.3  103.64  2430.2   99.48  2779.1   94.97  3153.0   96.78  3217.3   94.89
  3275.7   96.37  3288.0   92.38  3305.2   91.21  3308.0   90.71  3311.2   91.21
  3451.2   91.21  3665.5   91.21  3957.8   91.21  4025.5   91.96  4050.9   95.88
  4108.3   95.22  4167.0   91.21  4443.4   91.21  4781.6   91.21  5114.2   91.21
  5224.3   91.21  5339.5   94.40  5438.9   98.22  5717.7  100.40  7109.0  103.82
  7417.5  106.19  7711.3  116.20  7910.8  125.71  8067.2  134.64  8180.1  137.93
#Mann=20,-1,0
   876.3    0.05       0  2430.2     0.1       0  3153.0     0.1       0
  3305.2    0.07       0  3311.2     0.1       0  3451.2    0.05       0
  3665.5    0.07       0  3957.8     0.1       0  4108.3    0.07       0
  4443.4    0.05       0  4781.6    0.07       0  5114.2     0.1       0
  5224.3    0.07       0  5339.5     0.1       0  5438.9    0.08       0
  5717.7    0.05       0  7109.0     0.1       0  7417.5    0.16       0
  7711.3     0.1       0  7910.8     0.1       0
Bank Sta=3305.2,3311.2
Exp/Cntr=0.3,0.1

Chan Stop Cuts=-1