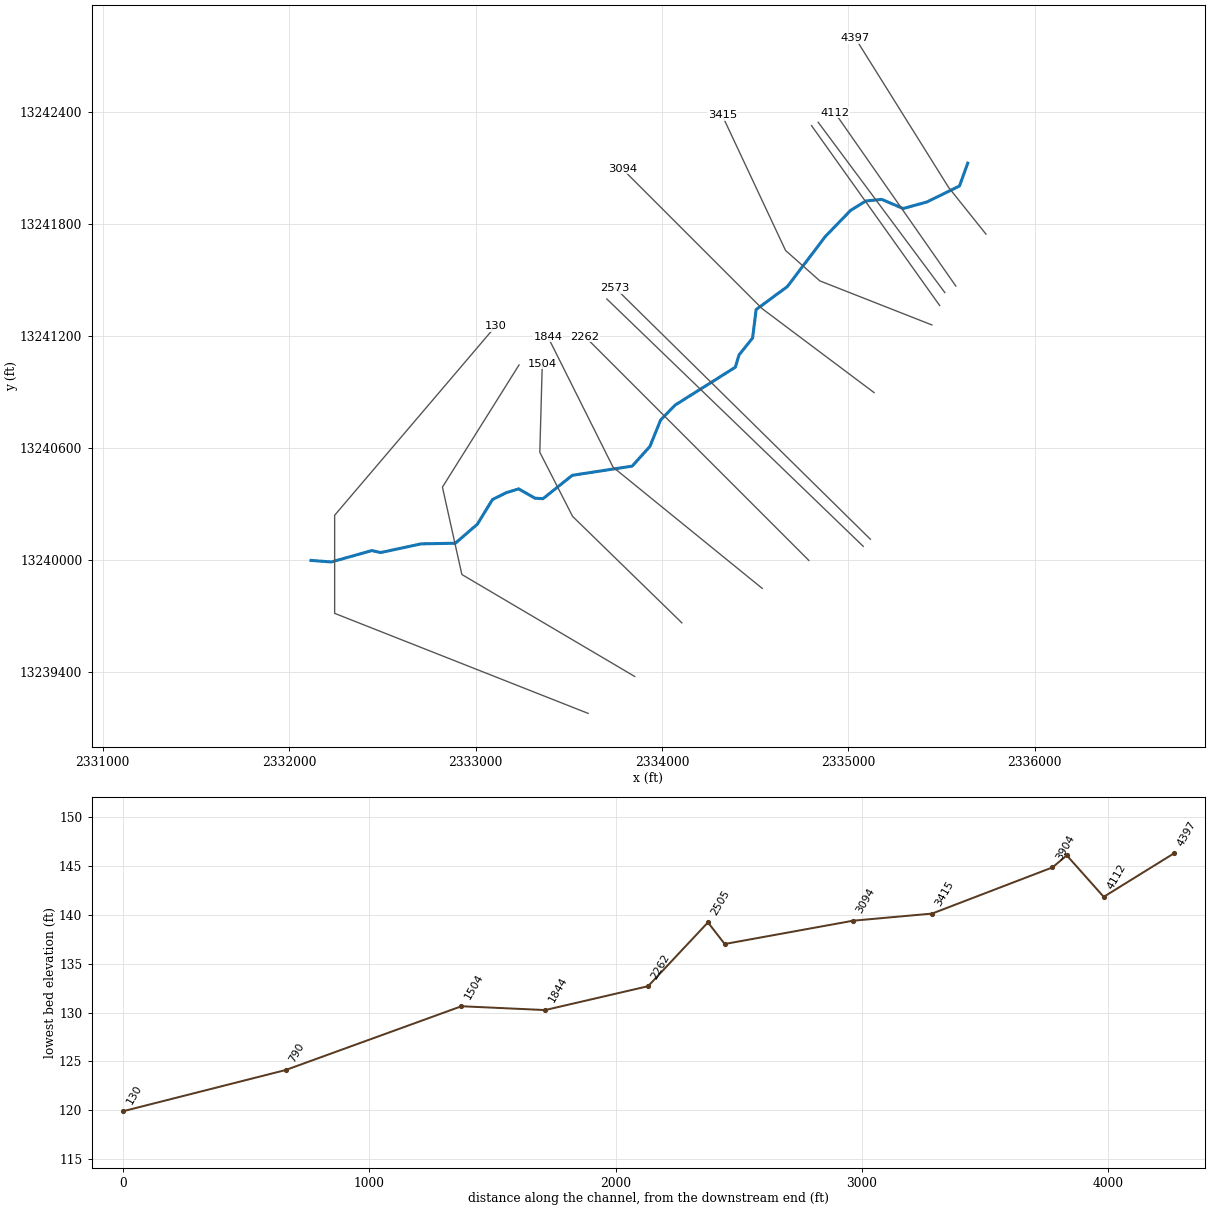
--- UNT017 IN PECR.prj (project) ---

Proj Title=UNT017 IN PECR Base Level Engineering
Current Plan=p01
Default Exp/Contr=0.3,0.1
English Units
Geom File=g01
Flow File=f01
Plan File=p01
Y Axis Title=Elevation
X Axis Title(PF)=Main Channel Distance
X Axis Title(XS)=Station
BEGIN DESCRIPTION:
UNT017 IN PECR
END DESCRIPTION:
DSS Export Rating Curves= 0
DSS Export Rating Curve Sorted= 0
DSS Export Volume Flow Curves= 0
DXF OffsetX= 0
DXF OffsetY= 0
DXF ScaleX= 1
DXF ScaleY= 10

--- UNT017 IN PECR.p01 (plan) ---

Plan Title=Multiple Run
Short Identifier=Multiple
Geom File=g01
Flow File=f01
Subcritical Flow
K Sum by GR= 0
Std Step Tol= 0.01
Critical Tol= 0.01
Num of Std Step Trials= 20
Max Error Tol= 0.3
Flow Tol Ratio= 0.001
Split Flow NTrial= 30
Split Flow Tol= 0.02
Split Flow Ratio= 0.02
Log Output Level= 0
Friction Slope Method= 1
Unsteady Friction Slope Method= 2
Unsteady Bridges Friction Slope Method= 1
Parabolic Critical Depth
Global Vel Dist=  1 , 1 , 1
Global Log Level= 0
CheckData=True
Encroach Param= -1, 0, 0, 0
BEGIN DESCRIPTION:
Multiple Run
END DESCRIPTION:

--- UNT017 IN PECR.f01 (steady flow) ---

Flow Title=Multiple
Program Version=4.10
Number of Profiles= 7
Profile Names=10-year,25-year,50-year,1pct_min,100-year,1pct_plu,500-year
River Rch & RM=UNT017 IN PECR,Reach-1         ,4397
     603     841    1038     935    1265    1711    1885
Boundary for River Rch & Prof#=UNT017 IN PECR,Reach-1         , 1
Up Type= 0
Dn Type= 3
Dn Slope=0.005
Boundary for River Rch & Prof#=UNT017 IN PECR,Reach-1         , 2
Up Type= 0
Dn Type= 3
Dn Slope=0.005
Boundary for River Rch & Prof#=UNT017 IN PECR,Reach-1         , 3
Up Type= 0
Dn Type= 3
Dn Slope=0.005
Boundary for River Rch & Prof#=UNT017 IN PECR,Reach-1         , 4
Up Type= 0
Dn Type= 3
Dn Slope=0.005
Boundary for River Rch & Prof#=UNT017 IN PECR,Reach-1         , 5
Up Type= 0
Dn Type= 3
Dn Slope=0.005
Boundary for River Rch & Prof#=UNT017 IN PECR,Reach-1         , 6
Up Type= 0
Dn Type= 3
Dn Slope=0.005
Boundary for River Rch & Prof#=UNT017 IN PECR,Reach-1         , 7
Up Type= 0
Dn Type= 3
Dn Slope=0.005
DSS Import GetInterval= 0
DSS Import GetPeak= 0
DSS Import FillOption= 0

--- UNT017 IN PECR.g01 (geometry) ---

Geom Title=Existing Conditions
Program Version=4.10

River Reach=UNT017 IN PECR  ,Reach-1
Reach XY= 30
        2335640.      13242127.2      2335595.73     13242004.81
      2335420.82      13241919.3      2335294.08     13241884.15
       2335178.2     13241933.19      2335093.17     13241924.38
      2335011.21     13241873.56      2334875.41     13241733.17
      2334672.33     13241465.33      2334505.02     13241342.13
      2334486.27     13241190.05      2334413.68     13241099.28
      2334393.39     13241032.82      2334070.47     13240829.84
      2333992.76     13240749.65      2333935.24     13240607.88
       2333840.4     13240502.57       2333519.2     13240453.29
      2333362.34     13240328.08       2333319.4     13240330.38
      2333231.22     13240380.46      2333164.25     13240359.84
      2333091.06      13240323.4      2333009.91     13240190.99
      2332891.86     13240088.97      2332708.22     13240085.65
      2332491.89     13240039.08      2332443.89     13240049.53
      2332227.27      13239988.6      2332117.72     13239996.85

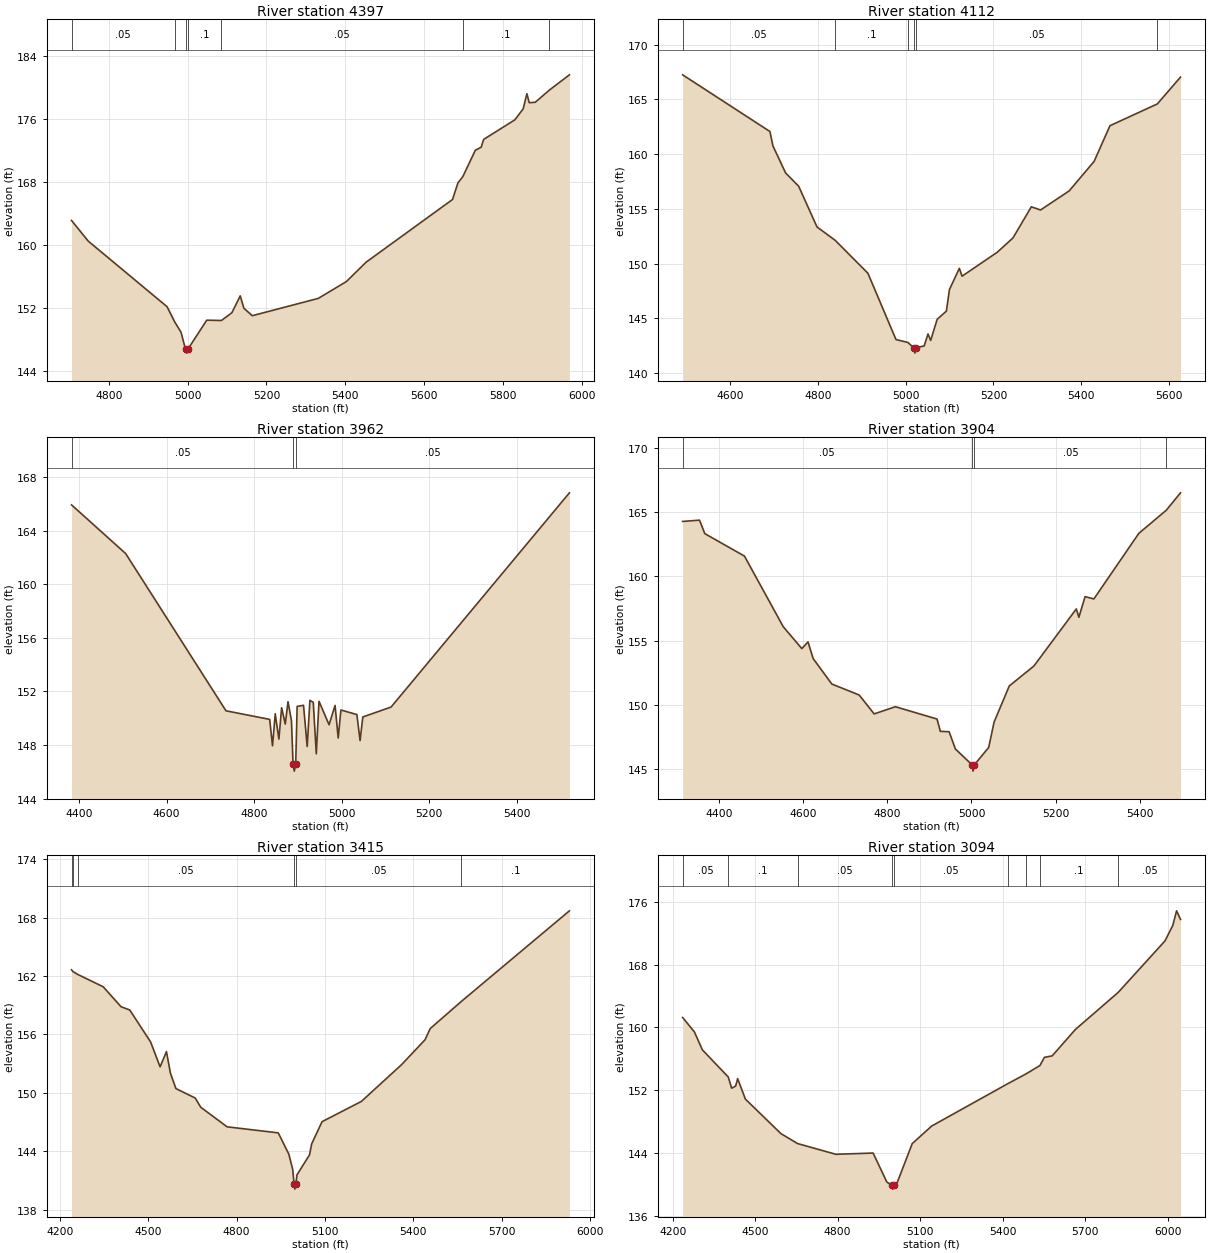
Type RM Length L Ch R = 1 ,4397    ,285,285,285
BEGIN DESCRIPTION:
UNT017 IN PECR 9.0
END DESCRIPTION:
XS GIS Cut Line= 3
      2335737.73     13241746.84      2335537.72     13241996.85
      2335037.71     13242796.88
#Sta/Elev= 30
  4705.4  163.13  4747.8   160.5  4947.9  152.16  4967.2  150.23  4983.2  148.92
  4994.6  146.76  4997.3  146.26  5000.6  146.76  5048.6  150.45  5085.9  150.41
  5112.3   151.4  5133.5  153.54  5142.9  151.96  5164.1  151.02  5331.6  153.22
  5402.9  155.36  5453.1  157.83  5672.4   165.8    5686   167.9  5698.6  168.72
  5730.2  172.06  5744.9  172.44  5751.4  173.44  5830.4  175.92  5851.6  177.32
  5861.1  179.25    5867  178.11  5882.3  178.16  5918.4  179.72    5969  181.65
#Mann= 7 ,-1 , 0
  4705.4     .05       0  4967.2      .1       0  4994.6     .07       0
  5000.6      .1       0  5085.9     .05       0  5698.6      .1       0
  5918.4     .05       0
Bank Sta=4994.6,5000.6
XS Rating Curve= 0 ,0
Exp/Cntr=0.3,0.1

Type RM Length L Ch R = 1 ,4112    ,150,150,150
BEGIN DESCRIPTION:
Mapping XS 538d210e
END DESCRIPTION:
XS GIS Cut Line= 2
      2335576.14     13241468.16      2334926.83     13242398.72
#Sta/Elev= 30
  4491.8  167.25  4690.7  162.07  4697.5  160.76  4726.5  158.28  4756.1  157.08
    4798  153.35  4839.4  152.13    4914  149.12    4978  143.06    5005   142.8
  5018.3  142.32  5021.1  141.82  5024.3  142.32  5042.3  142.48    5051  143.57
  5057.1  142.98  5071.9  144.91  5092.9  145.66  5099.9  147.64  5122.5  149.57
  5128.6  148.85  5208.9  151.04  5244.7  152.35  5286.5  155.19  5307.5   154.9
  5372.9  156.65  5429.6  159.34  5465.7   162.6  5573.6  164.59  5626.5  167.04
#Mann= 6 ,-1 , 0
  4491.8     .05       0  4839.4      .1       0    5005     .05       0
  5018.3     .07       0  5024.3     .05       0  5573.6      .1       0
Bank Sta=5018.3,5024.3
XS Rating Curve= 0 ,0
Exp/Cntr=0.3,0.1

Type RM Length L Ch R = 1 ,3962    ,58,58,58
BEGIN DESCRIPTION:
UNT017 IN PECR 8.0
END DESCRIPTION:
XS GIS Cut Line= 2
      2335517.13     13241433.41      2334837.73     13242346.85
#Sta/Elev= 30
  4382.6  165.92  4506.3  162.29  4735.7  150.56  4835.6  149.92  4842.1  147.95
  4848.3  150.34  4856.7  148.45  4862.9  150.79  4871.3  149.57  4877.5  151.24
  4885.4  149.83  4889.1  146.56  4891.9  146.06  4895.1  146.56  4898.4  150.89
    4913  150.97  4921.4   147.9  4927.6  151.34  4935.3  151.19  4942.2  147.35
  4948.4  151.27  4971.4  149.52  4985.1  150.96  4992.3  148.53  4998.5  150.62
    5035  150.28  5042.3  148.34  5048.6   150.1  5113.2  150.84    5521  166.82
#Mann= 3 ,-1 , 0
  4382.6     .05       0  4889.1     .03       0  4895.1     .05       0
Bank Sta=4889.1,4895.1
XS Rating Curve= 0 ,0
Exp/Cntr=0.3,0.1

Type RM Length L Ch R = 1 ,3904    ,489,489,489
BEGIN DESCRIPTION:
Mapping XS 8e918dea
END DESCRIPTION:
XS GIS Cut Line= 2
      2335489.36     13241363.96      2334802.31      13242328.6
#Sta/Elev= 30
    4313  164.29  4353.1  164.39  4365.7  163.34    4460  161.59  4552.2  156.09
  4596.5  154.38  4611.2   154.9  4623.5   153.6  4667.8  151.62    4733  150.76
  4768.6  149.29    4819  149.85  4918.1  148.89    4926  147.93  4946.9   147.9
  4961.7  146.56  5001.1  145.33  5003.8  144.83  5007.1  145.33  5040.9  146.67
  5053.9  148.66    5090  151.47  5148.5  153.02  5249.4  157.47  5255.5  156.82
  5270.3  158.43  5291.2  158.25  5398.1  163.36  5463.3  165.16  5497.3  166.52
#Mann= 4 ,-1 , 0
    4313     .05       0  5001.1     .03       0  5007.1     .05       0
  5463.3      .1       0
Bank Sta=5001.1,5007.1
XS Rating Curve= 0 ,0
Exp/Cntr=0.3,0.1

Type RM Length L Ch R = 1 ,3415    ,321,321,321
BEGIN DESCRIPTION:
UNT017 IN PECR 7.0
END DESCRIPTION:
XS GIS Cut Line= 4
      2335447.65     13241259.82      2334846.99     13241495.92
      2334662.96     13241659.11      2334323.39     13242383.29
#Sta/Elev= 30
  4239.5  162.64  4243.4  162.48  4260.2  162.17  4346.9   160.9  4407.5  158.85
  4437.3  158.51    4508  155.23  4540.3  152.67  4561.8  154.24  4575.5  152.01
    4594  150.44  4659.5  149.47  4678.5  148.52  4767.9  146.51  4941.6  145.89
  4977.5  143.71  4990.9  142.11  4995.4  140.61  4998.2  140.11  5001.4  140.61
  5005.1  141.57  5047.8  143.63  5055.3  144.77  5090.4  147.04    5224  149.12
  5360.3  152.89  5440.4  155.46  5457.7   156.6  5563.5  159.39  5930.7   168.7
#Mann= 6 ,-1 , 0
  4239.5     .05       0  4243.4      .1       0  4260.2     .05       0
  4995.4     .03       0  5001.4     .05       0  5563.5      .1       0
Bank Sta=4995.4,5001.4
XS Rating Curve= 0 ,0
Exp/Cntr=0.3,0.1

Type RM Length L Ch R = 1 ,3094    ,521,521,521
BEGIN DESCRIPTION:
UNT017 IN PECR 6.0
END DESCRIPTION:
XS GIS Cut Line= 3
      2335137.72     13240896.85      2334537.72     13241346.85
      2333787.69     13242096.88
#Sta/Elev= 30
  4236.3  161.26    4279  159.42  4308.2  157.13  4402.3  153.67  4414.4  152.25
    4429  152.51  4436.3  153.47  4464.4  150.86  4593.6  146.46  4654.2  145.19
  4793.6  143.82    4929  143.98    4979  140.28  4997.4  139.88  5000.2  139.38
  5003.4  139.88  5014.6  140.03  5071.2  145.18  5141.9  147.42  5420.2  152.85
  5484.1  154.05  5535.7  155.14    5552  156.18  5580.3  156.37  5665.1  159.75
  5820.1  164.45  5990.4  171.02  6018.7  172.98  6032.8  174.86    6047  173.77
#Mann= 9 ,-1 , 0
  4236.3     .05       0  4402.3      .1       0  4654.2     .05       0
  4997.4     .03       0  5003.4     .05       0  5420.2      .1       0
  5484.1     .05       0  5535.7      .1       0  5820.1     .05       0
Bank Sta=4997.4,5003.4
XS Rating Curve= 0 ,0
Exp/Cntr=0.3,0.1

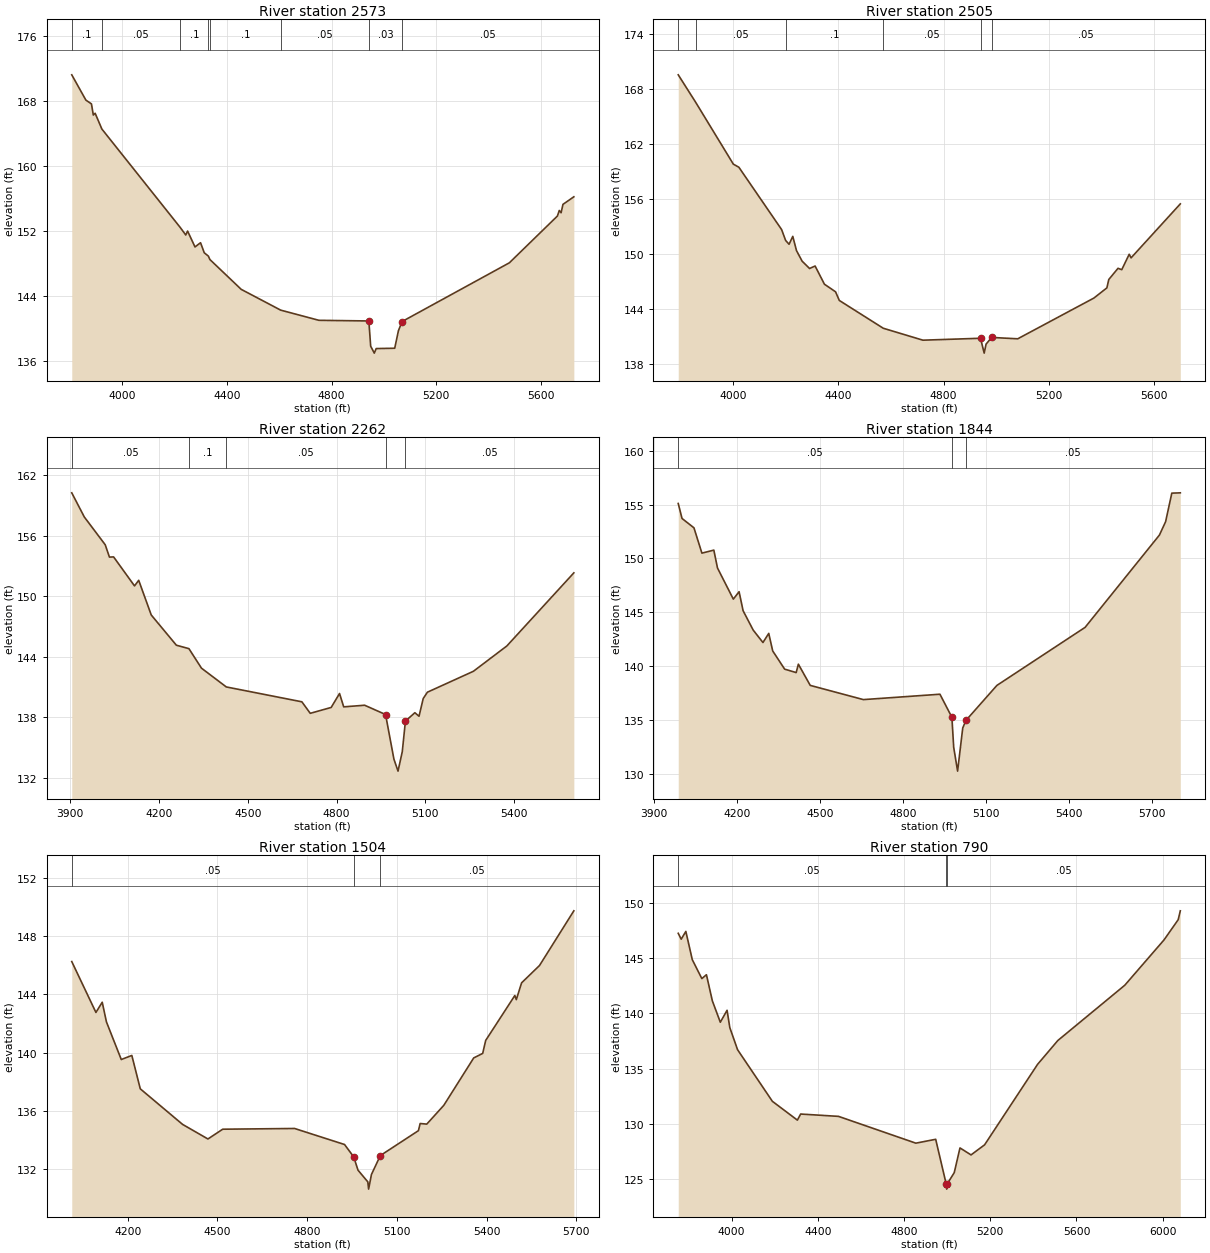
Type RM Length L Ch R = 1 ,2573    ,68,68,68
BEGIN DESCRIPTION:
Mapping XS 657cae73
END DESCRIPTION:
XS GIS Cut Line= 2
      2335117.85     13240110.47      2333749.76     13241457.73
#Sta/Elev= 30
    3806  171.18  3860.1  168.07  3881.3  167.61  3888.4  166.24  3895.4  166.46
  3921.2  164.52  4220.9  152.43  4241.9  151.51    4249  151.99  4277.3  150.04
  4298.5  150.56  4312.6  149.33  4328.6  148.91  4334.1   148.5  4454.1  144.83
    4605  142.28  4751.1  141.03  4942.1  140.95  4949.1  137.85    4963     137
  4970.3  137.56  5041.1   137.6  5055.2  139.75  5069.3  140.88  5479.4  148.09
  5663.3  153.84  5670.4  154.52  5677.4  154.24  5684.5  155.27  5726.1   156.2
#Mann= 8 ,-1 , 0
    3806      .1       0  3921.2     .05       0  4220.9      .1       0
  4328.6     .05       0  4334.1      .1       0    4605     .05       0
  4942.1     .03       0  5069.3     .05       0
Bank Sta=4942.1,5069.3
XS Rating Curve= 0 ,0
Exp/Cntr=0.3,0.1

Type RM Length L Ch R = 1 ,2505    ,243,243,243
BEGIN DESCRIPTION:
UNT017 IN PECR 5.0
END DESCRIPTION:
XS GIS Cut Line= 2
      2335079.61     13240072.32       2333704.6     13241398.72
#Sta/Elev= 30
  3790.5  169.53  3856.4  166.56  4000.2   159.8  4021.3  159.46  4183.9  152.67
  4199.1  151.49  4212.2  151.07  4226.4  151.93  4240.5  150.38  4261.9  149.23
  4290.2  148.43  4311.3   148.7  4346.8  146.72  4389.2  145.89  4403.4  144.95
  4570.7  141.92  4721.6  140.62  4940.8  140.83  4954.7  139.21  4961.9  140.19
  4983.2  140.92  5082.3  140.77  5372.2  145.21  5421.6  146.32  5428.8  147.23
    5464  148.45  5478.2   148.3  5506.5  149.98  5513.7  149.59    5701  155.47
#Mann= 6 ,-1 , 0
  3790.5      .1       0  3856.4     .05       0  4199.1      .1       0
  4570.7     .05       0  4940.8     .03       0  4983.2     .05       0
Bank Sta=4940.8,4983.2
XS Rating Curve= 0 ,0
Exp/Cntr=0.3,0.1

Type RM Length L Ch R = 1 ,2262    ,418,418,418
BEGIN DESCRIPTION:
UNT017 IN PECR 4.0
END DESCRIPTION:
XS GIS Cut Line= 3
      2334787.72     13239996.85      2333987.72     13240796.85
      2333587.69     13241196.88
#Sta/Elev= 30
  3905.1  160.23  3947.5  157.84  4018.2  155.09  4032.4  153.87  4046.5  153.89
  4117.2  151.02  4131.4  151.57  4173.8  148.14  4258.7  145.15  4301.1  144.81
  4343.5  142.88  4427.5  141.02  4682.9  139.55  4711.2  138.41  4781.9  138.99
  4810.2  140.37  4824.3  139.05  4895.1  139.21  4965.8  138.29    4994  133.88
  5007.9  132.69  5022.3  134.62  5032.9  137.64  5064.8  138.47  5078.9  138.12
    5093  139.87  5107.2   140.5  5262.7  142.57  5375.9  145.08  5602.2  152.31
#Mann= 5 ,-1 , 0
  3905.1     .05       0  4301.1      .1       0  4427.5     .05       0
  4965.8     .03       0  5032.9     .05       0
Bank Sta=4965.8,5032.9
XS Rating Curve= 0 ,0
Exp/Cntr=0.3,0.1

Type RM Length L Ch R = 1 ,1844    ,340,340,340
BEGIN DESCRIPTION:
UNT017 IN PECR 3.0
END DESCRIPTION:
XS GIS Cut Line= 3
      2334537.75     13239846.83      2333737.72     13240496.85
      2333387.74     13241196.82
#Sta/Elev= 30
  3988.9   155.1  4002.6  153.71  4045.7  152.84  4074.4  150.49  4117.5  150.77
  4130.7  149.11  4187.9  146.22  4208.7  146.91  4223.1  145.15  4259.5  143.35
  4294.9  142.19  4315.8  143.04  4330.1  141.41  4373.2  139.72  4414.9   139.4
  4422.8  140.18  4465.7  138.21  4657.7  136.89  4934.2  137.39  4977.3  135.25
  4983.8  132.47  4997.9  130.25  5016.5  134.26  5028.1  134.96  5139.9  138.21
  5458.5   143.6  5726.9  152.17  5749.2  153.41  5771.6  156.06  5802.3  156.09
#Mann= 3 , 0 , 0
  3988.9     .05       0  4977.3     .03       0  5028.1     .05       0
Bank Sta=4977.3,5028.1
XS Rating Curve= 0 ,0
Exp/Cntr=0.3,0.1

Type RM Length L Ch R = 1 ,1504    ,714,714,714
BEGIN DESCRIPTION:
UNT017 IN PECR 2.0
END DESCRIPTION:
XS GIS Cut Line= 4
      2334106.88     13239661.92      2333520.75     13240232.92
      2333344.92     13240577.03      2333358.15     13241051.63
#Sta/Elev= 30
  4012.6  146.25  4093.4  142.76  4114.5  143.46  4128.6  142.11  4178.2  139.53
  4213.5  139.81  4241.8  137.52  4383.3  135.08  4468.1  134.08  4517.5  134.75
    4758   134.8  4925.1   133.7  4955.8  132.85  4970.1  131.94  5002.9  131.14
  5005.6  130.64    5015  131.64  5044.7  132.94  5172.2  134.65    5178  135.14
  5200.2   135.1  5257.2  136.39  5357.2  139.64  5387.2  139.95  5397.2  140.84
  5494.7  143.92  5499.7  143.64  5517.3  144.79  5577.3  145.98  5692.1  149.73
#Mann= 3 , 0 , 0
  4012.6     .05       0  4955.8     .03       0  5044.7     .05       0
Bank Sta=4955.8,5044.7
XS Rating Curve= 0 ,0
Exp/Cntr=0.3,0.1

Type RM Length L Ch R = 1 ,790     ,660,660,660
BEGIN DESCRIPTION:
Mapping XS 78165d00
END DESCRIPTION:
XS GIS Cut Line= 4
      2333853.91      13239374.4      2332926.85     13239921.26
      2332822.68     13240390.01      2333233.45     13241045.17
#Sta/Elev= 30
  3752.1  147.22  3765.9  146.69  3787.4  147.39  3817.3  144.84  3861.6  143.13
    3883  143.48  3910.3  141.13  3947.4  139.19  3978.7  140.27  3991.5   138.7
  4027.4  136.71  4188.9  132.05    4305  130.35  4320.1   130.9  4495.8  130.69
  4854.7  128.27  4946.8  128.62  4995.1  124.62  4997.8  124.12  5001.1  124.62
  5032.9  125.61  5059.5  127.84  5110.8  127.21  5173.7  128.12  5419.3  135.38
  5513.6  137.54  5824.2  142.53  6006.2  146.62  6072.1  148.45  6081.9  149.25
#Mann= 3 ,-1 , 0
  3752.1     .05       0  4995.1     .03       0  5001.1     .05       0
Bank Sta=4995.1,5001.1
XS Rating Curve= 0 ,0
Exp/Cntr=0.3,0.1

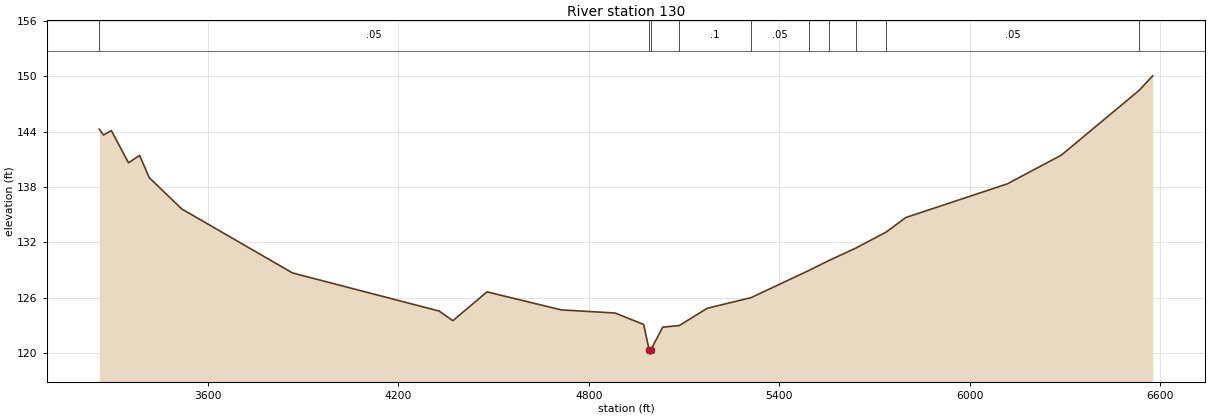
Type RM Length L Ch R = 1 ,130     ,0,0,0
BEGIN DESCRIPTION:
UNT017 IN PECR 1.0
END DESCRIPTION:
XS GIS Cut Line= 4
      2333603.92     13239176.48      2332244.56     13239712.93
      2332244.56     13240238.97      2333107.96     13241253.22
#Sta/Elev= 30
    3258  144.25  3271.3  143.63  3295.7  144.12  3349.8  140.63    3385  141.42
  3415.2  139.02  3517.6  135.63  3866.6   128.7    4329  124.57    4372  123.53
  4479.5  126.65  4713.5   124.7  4883.3  124.36  4973.3  123.12  4990.3  120.41
  4993.1  119.91  4996.3  120.41  5033.3  122.83  5085.2     123  5173.3  124.87
  5311.9  126.03  5495.3  128.99  5556.8  130.04  5641.7  131.39  5737.2  133.12
  5799.4   134.7  6118.9  138.34  6289.2  141.45    6534  148.45  6577.4  150.04
#Mann= 10 ,-1 , 0
    3258     .05       0  4990.3     .03       0  4996.3     .05       0
  5085.2      .1       0  5311.9     .05       0  5495.3      .1       0
  5556.8     .05       0  5641.7     .08       0  5737.2     .05       0
    6534      .1       0
Bank Sta=4990.3,4996.3
XS Rating Curve= 0 ,0
Exp/Cntr=0.3,0.1

Chan Stop Cuts=-1
Use User Specified Reach Order=0
Composite Channel Slope=5