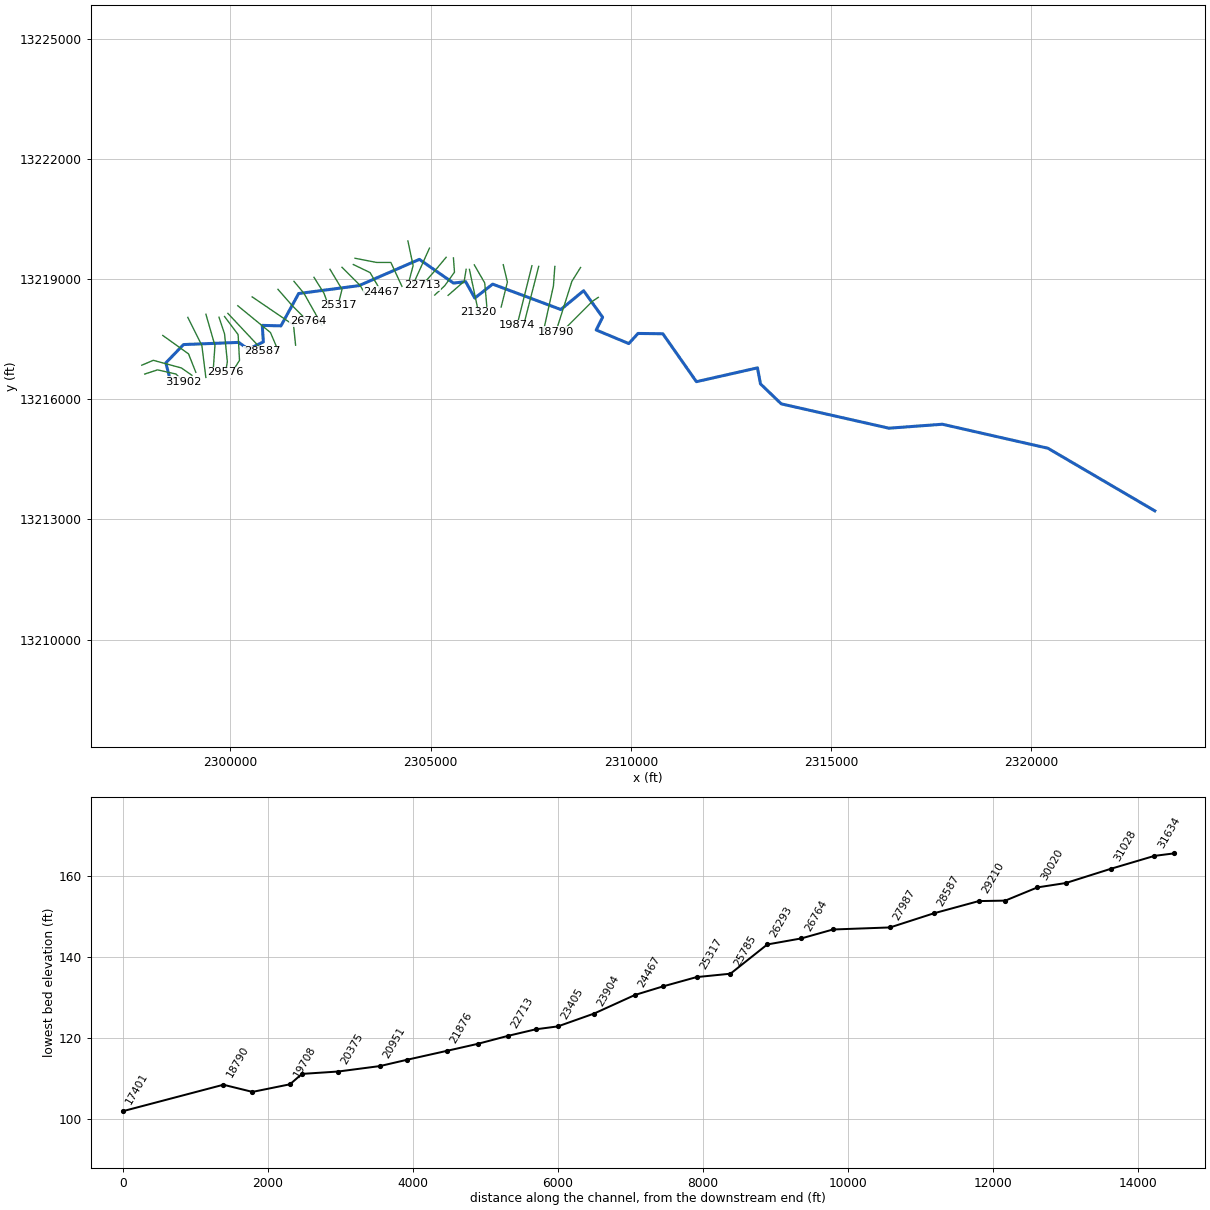
--- UNT018 IN PECR.prj (project) ---

Proj Title=UNT018 IN PECR Base Level Engineering
Current Plan=p01
Default Exp/Contr=0.3,0.1
English Units
Geom File=g01
Flow File=f01
Plan File=p01
Y Axis Title=Elevation
X Axis Title(PF)=Main Channel Distance
X Axis Title(XS)=Station
BEGIN DESCRIPTION:
UNT018 IN PECR
END DESCRIPTION:
DSS Export Rating Curves= 0
DSS Export Rating Curve Sorted= 0
DSS Export Volume Flow Curves= 0
DXF OffsetX= 0
DXF OffsetY= 0
DXF ScaleX= 1
DXF ScaleY= 10

--- UNT018 IN PECR.p01 (plan) ---

Plan Title=Multiple Run
Short Identifier=Multiple
Geom File=g01
Flow File=f01
Subcritical Flow
K Sum by GR= 0
Std Step Tol= 0.01
Critical Tol= 0.01
Num of Std Step Trials= 20
Max Error Tol= 0.3
Flow Tol Ratio= 0.001
Split Flow NTrial= 30
Split Flow Tol= 0.02
Split Flow Ratio= 0.02
Log Output Level= 0
Friction Slope Method= 1
Unsteady Friction Slope Method= 2
Unsteady Bridges Friction Slope Method= 1
Parabolic Critical Depth
Global Vel Dist=  1 , 1 , 1
Global Log Level= 0
CheckData=True
Encroach Param= -1, 0, 0, 0
BEGIN DESCRIPTION:
Multiple Run
END DESCRIPTION:

--- UNT018 IN PECR.f01 (steady flow) ---

Flow Title=Multiple
Program Version=4.10
Number of Profiles= 7
Profile Names=10-year,25-year,50-year,1pct_min,100-year,1pct_plu,500-year
River Rch & RM=UNT018 IN PECR,Reach-1         ,31902
     469     646     790     706     954    1290    1397
River Rch & RM=UNT018 IN PECR,Reach-1         ,31028
     895    1276    1598    1458    1972    2667    3016
River Rch & RM=UNT018 IN PECR,Reach-1         ,23405
    1229    1783    2257    2080    2812    3803    4389
River Rch & RM=UNT018 IN PECR,Reach-1         ,22713
    1446    2111    2684    2483    3359    4542    5284
River Rch & RM=UNT018 IN PECR,Reach-1         ,17401
    1484    2168    2759    2554    3454    4671    5441
River Rch & RM=UNT018 IN PECR,Reach-1         ,14840
    1961    2897    3714    3460    4680    6329    7468
River Rch & RM=UNT018 IN PECR,Reach-1         ,11064
    2064    3050    3911    3643    4927    6663    7860
River Rch & RM=UNT018 IN PECR,Reach-1         ,8601
    2180    3219    4125    3839    5192    7022    8269
River Rch & RM=UNT018 IN PECR,Reach-1         ,4553
    2344    3472    4458    4156    5621    7602    8982
River Rch & RM=UNT018 IN PECR,Reach-1         ,4058
    2354    3478    4456    4147    5608    7584    8924
Boundary for River Rch & Prof#=UNT018 IN PECR,Reach-1         , 1
Up Type= 0
Dn Type= 3
Dn Slope=0.0001
Boundary for River Rch & Prof#=UNT018 IN PECR,Reach-1         , 2
Up Type= 0
Dn Type= 3
Dn Slope=0.0001
Boundary for River Rch & Prof#=UNT018 IN PECR,Reach-1         , 3
Up Type= 0
Dn Type= 3
Dn Slope=0.0001
Boundary for River Rch & Prof#=UNT018 IN PECR,Reach-1         , 4
Up Type= 0
Dn Type= 3
Dn Slope=0.0001
Boundary for River Rch & Prof#=UNT018 IN PECR,Reach-1         , 5
Up Type= 0
Dn Type= 3
Dn Slope=0.0001
Boundary for River Rch & Prof#=UNT018 IN PECR,Reach-1         , 6
Up Type= 0
Dn Type= 3
Dn Slope=0.0001
Boundary for River Rch & Prof#=UNT018 IN PECR,Reach-1         , 7
Up Type= 0
Dn Type= 3
Dn Slope=0.0001
DSS Import GetInterval= 0
DSS Import GetPeak= 0
DSS Import FillOption= 0

--- UNT018 IN PECR.g01 (geometry) ---

Geom Title=Existing Conditions
Program Version=4.10

River Reach=UNT018 IN PECR  ,Reach-1
Reach XY= 30
      2298499.85     13216472.73      2298389.61     13216911.53
      2298830.87     13217367.82      2300208.19     13217421.55
      2300451.93     13217248.77      2300822.98     13217433.85
      2300797.26     13217846.48      2301262.91     13217834.18
        2301705.      13218641.8      2303211.81     13218839.05
      2304718.86     13219495.13        2305571.      13218902.6
      2305874.51     13218938.81      2306103.26     13218528.32
      2306548.72     13218876.98      2308251.53     13218242.92
      2308820.29     13218711.91      2309294.04     13218050.73
      2309134.59     13217731.27      2309947.84     13217392.52
      2310178.59     13217645.13      2310798.14     13217637.59
      2311636.81     13216440.93      2313161.63     13216785.83
      2313235.82     13216386.93      2313754.91     13215886.93
      2316444.15     13215279.29      2317777.48     13215378.25
       2320412.9     13214779.29      2323081.32     13213216.34

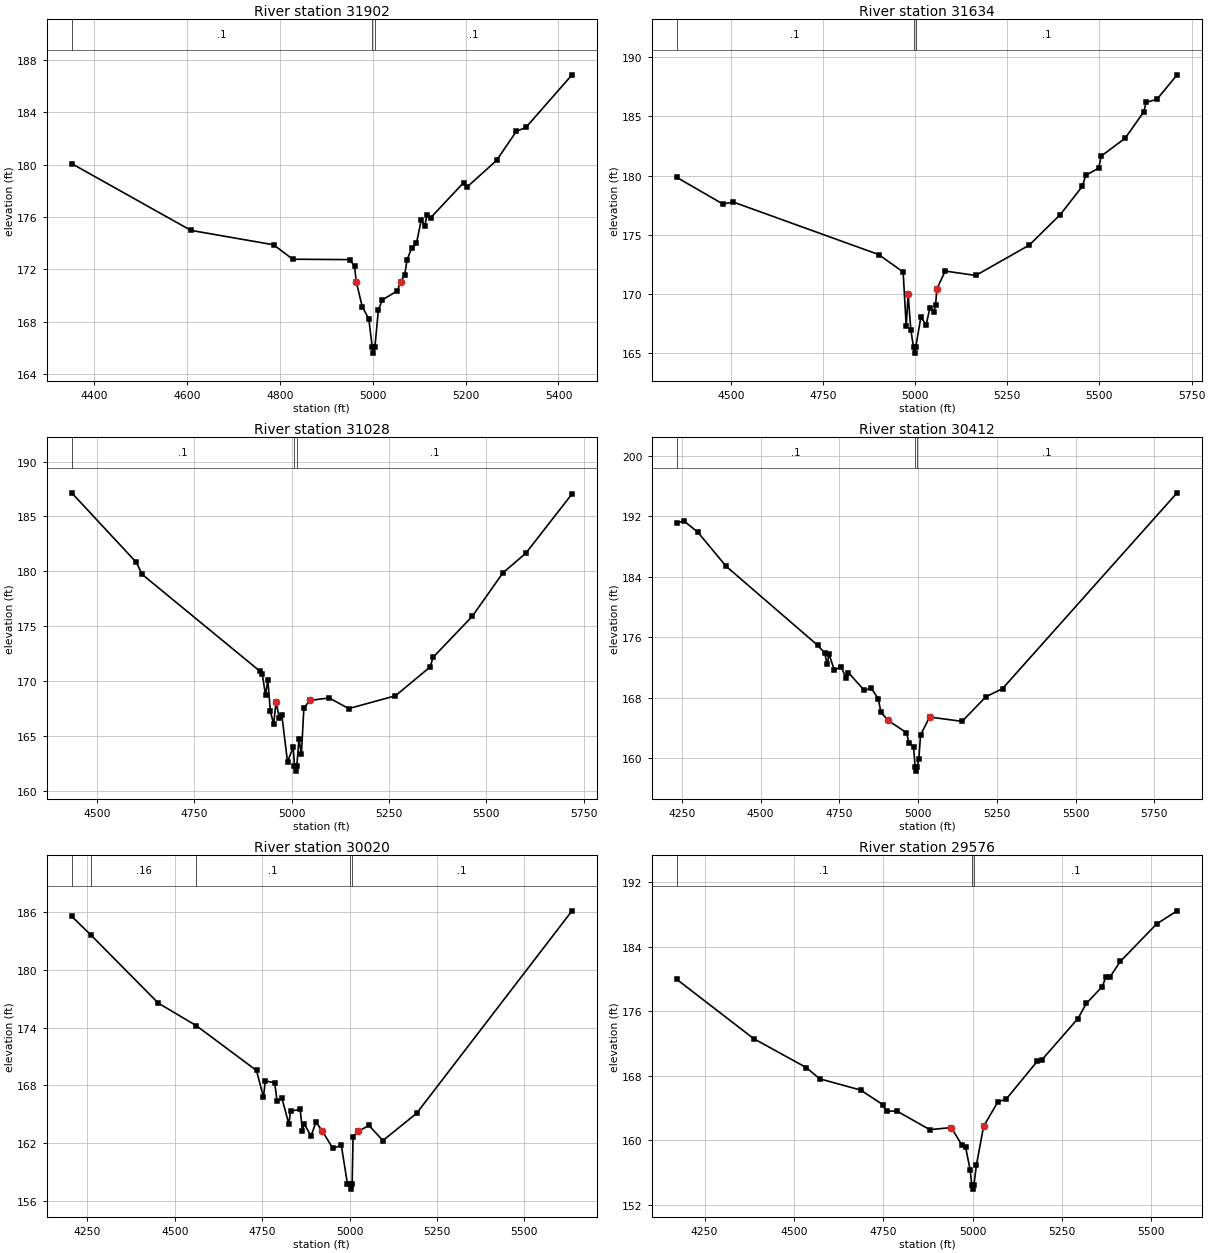
Type RM Length L Ch R = 1 ,31902   ,268,268,268
BEGIN DESCRIPTION:
UNT018 IN PECR 65.0
END DESCRIPTION:
XS GIS Cut Line= 4
      2297861.51     13216631.67       2298182.7     13216735.84
      2298642.77     13216631.67      2298832.64     13216441.79
#Sta/Elev= 30
  4351.3  180.07  4608.1  174.98  4786.4  173.88  4827.4  172.78  4950.4  172.75
  4960.7  172.24 4964.43  171.04  4977.4  169.15  4991.4  168.23  4998.7  166.12
  5001.5  165.62  5004.7  166.12    5012   168.9  5020.5  169.68    5053  170.37
 5059.89  171.07  5068.8   171.6  5073.9  172.75  5083.7  173.62    5094  173.98
  5104.2  175.74    5112  175.34  5117.1  176.18  5124.7  175.94  5195.9  178.63
  5202.9  178.28  5266.6  180.31    5309  182.52  5330.2  182.84  5429.2  186.84
#Mann= 3 ,-1 , 0
  4351.3      .1       0  4998.7     .07       0  5004.7      .1       0
Bank Sta=4964.43,5059.89
XS Rating Curve= 0 ,0
Exp/Cntr=0.3,0.1

Type RM Length L Ch R = 1 ,31634   ,606,606,606
BEGIN DESCRIPTION:
UNT018 IN PECR 64.0
END DESCRIPTION:
XS GIS Cut Line= 4
        2297789.     13216852.72      2298075.45     13216974.25
      2298778.57     13216783.27      2299038.39      13216601.4
#Sta/Elev= 30
  4353.7  179.85  4478.4  177.61  4507.5  177.76  4901.6  173.33  4967.7  171.86
    4976  167.26  4981.2  169.99  4988.4     167  4995.8  165.51  4998.6  165.01
  5001.8  165.51  5015.8  168.06  5029.9  167.38  5040.3  168.83  5050.5   168.5
  5055.6  169.06 5059.09  170.44  5081.7  171.94  5164.6  171.57  5309.7  174.13
  5393.5   176.7  5453.9   179.1  5462.6  180.02  5498.4  180.64  5504.5  181.64
  5569.9  183.16  5620.4  185.39  5626.5  186.18  5656.2  186.45  5710.6  188.51
#Mann= 3 ,-1 , 0
  4353.7      .1       0  4995.8     .07       0  5001.8      .1       0
Bank Sta=4981.2,5059.09
XS Rating Curve= 0 ,0
Exp/Cntr=0.3,0.1

Type RM Length L Ch R = 1 ,31028   ,616,616,616
BEGIN DESCRIPTION:
UNT018 IN PECR 63.0
END DESCRIPTION:
XS GIS Cut Line= 3
      2298312.93     13217595.19      2298955.27     13217135.14
      2299137.57     13216675.03
#Sta/Elev= 30
  4434.9  187.15    4601  180.81  4615.8  179.72  4917.9  170.91  4924.1  170.67
  4932.7  168.74  4938.8  170.09  4945.1  167.27  4953.6  166.06  4959.7   168.1
  4968.3  166.59  4974.4  166.95  4989.2  162.64  5003.9  163.97  5007.1  162.29
  5009.8  161.79  5013.1  162.29  5018.7  164.72  5024.8  163.31  5031.2   167.5
  5045.7  168.23  5096.1  168.46  5146.4  167.49  5266.2  168.65  5355.7  171.29
    5363  172.16  5463.8   175.9  5542.2  179.85  5601.6  181.66  5719.9  187.05
#Mann= 3 ,-1 , 0
  4434.9      .1       0  5007.1     .07       0  5013.1      .1       0
Bank Sta=4959.7,5045.7
XS Rating Curve= 0 ,0
Exp/Cntr=0.3,0.1

Type RM Length L Ch R = 1 ,30412   ,392,392,392
BEGIN DESCRIPTION:
UNT018 IN PECR 62.0
END DESCRIPTION:
XS GIS Cut Line= 3
      2298937.74     13218046.82      2299287.72     13217346.85
      2299387.72     13216546.86
#Sta/Elev= 30
  4233.7  191.09    4256   191.4  4300.7  189.89  4390.2   185.4  4680.9  174.95
  4703.2  173.94  4711.6  172.41  4717.2  173.77    4734  171.65  4756.3  172.11
  4770.3  170.62  4778.7  171.33    4829  168.99  4851.4  169.26  4873.7  167.87
  4882.1  166.08  4904.5  165.02  4963.2  163.37  4971.6  161.98  4985.5  161.55
  4990.9   158.8  4993.7   158.3  4996.9   158.8  5002.3  159.87  5007.9  163.06
  5036.4  165.45  5139.7  164.88  5215.3  168.13  5268.2  169.21  5822.5   195.1
#Mann= 3 ,-1 , 0
  4233.7      .1       0  4990.9     .07       0  4996.9      .1       0
Bank Sta=4904.5,5036.4
XS Rating Curve= 0 ,0
Exp/Cntr=0.3,0.1

Type RM Length L Ch R = 1 ,30020   ,444,444,444
BEGIN DESCRIPTION:
UNT018 IN PECR 61.0
END DESCRIPTION:
XS GIS Cut Line= 3
       2299389.3      13218124.7      2299614.99     13217343.47
      2299571.59     13216727.17
#Sta/Elev= 30
  4205.1  185.55  4261.2  183.57  4452.7  176.54  4561.7  174.19  4733.7  169.54
  4753.6  166.77  4758.8  168.46  4785.8  168.26  4792.4  166.37  4806.6  166.64
  4826.1  163.99  4831.3  165.32  4858.6  165.51  4864.9   163.3  4870.1  163.99
  4889.8  162.73  4903.7  164.19  4921.1  163.29  4952.3  161.44  4976.2  161.78
  4993.9  157.75  5001.3  157.72  5004.1  157.22  5007.3  157.72  5009.8  162.68
  5024.9  163.22  5055.3  163.84  5095.1  162.26  5191.6  165.09  5636.1  186.12
#Mann= 5 ,-1 , 0
  4205.1      .1       0  4261.2     .16       0  4561.7      .1       0
  5001.3     .07       0  5007.3      .1       0
Bank Sta=4921.1,5024.9
XS Rating Curve= 0 ,0
Exp/Cntr=0.3,0.1

Type RM Length L Ch R = 1 ,29576   ,366,366,366
BEGIN DESCRIPTION:
UNT018 IN PECR 60.0
END DESCRIPTION:
XS GIS Cut Line= 4
      2299716.07     13218050.66      2299854.96     13217633.97
      2299924.41     13216939.52      2299881.23     13216680.43
#Sta/Elev= 30
  4172.3  179.97  4387.7  172.61  4534.7  169.03  4572.2  167.63  4686.7  166.24
  4749.3  164.41  4759.4  163.59  4787.2  163.66    4880  161.33  4940.3  161.58
  4970.4  159.39  4980.5  159.14  4993.3  156.31  4997.6  154.45  5000.3  153.95
  5003.6  154.45  5010.6   156.9  5030.7  161.73  5070.9  164.79  5093.8   165.1
  5181.5  169.84  5194.3  170.01  5294.8  175.11  5318.5     177  5362.8  179.07
    5373  180.27  5384.4  180.28  5413.5   182.2  5514.9  186.84  5572.1  188.47
#Mann= 3 ,-1 , 0
  4172.3      .1       0  4997.6     .07       0  5003.6      .1       0
Bank Sta=4940.3,5030.7
XS Rating Curve= 0 ,0
Exp/Cntr=0.3,0.1

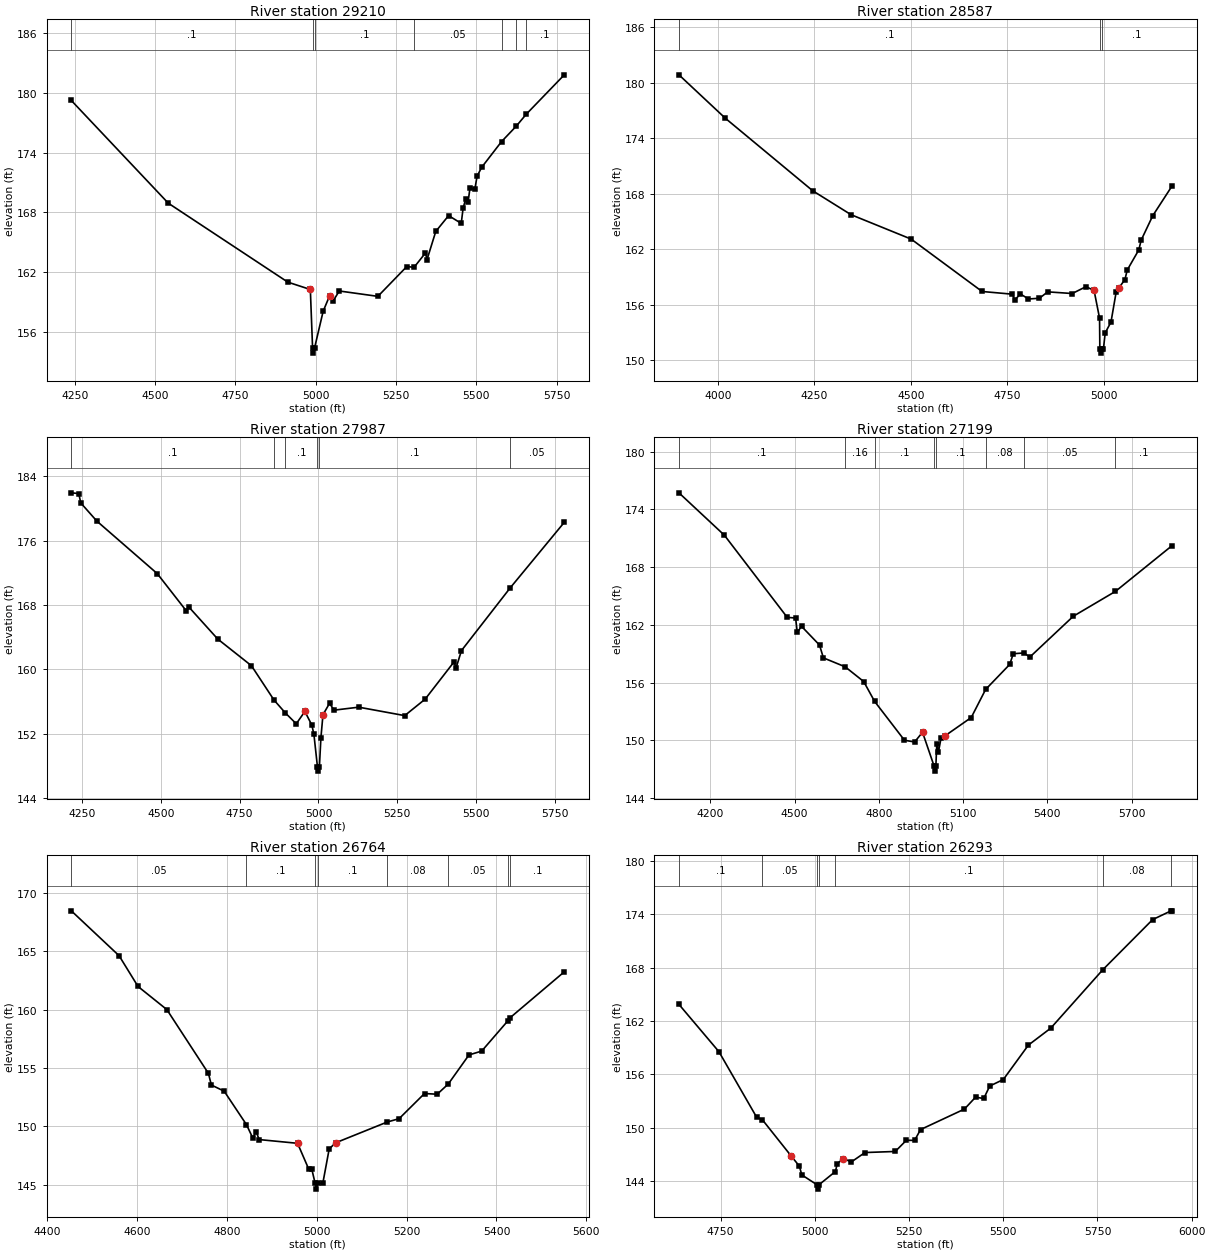
Type RM Length L Ch R = 1 ,29210   ,623,623,623
BEGIN DESCRIPTION:
UNT018 IN PECR 59.0
END DESCRIPTION:
XS GIS Cut Line= 4
      2299854.94     13218068.02       2300193.5     13217616.61
      2300228.23     13216974.25      2300054.64      13216696.5
#Sta/Elev= 30
    4239  179.24    4541  168.91  4913.2  160.97  4983.3  160.23  4990.3  154.33
  4993.1  153.83  4996.3  154.33  5023.3  158.05  5043.4   159.6  5053.4  159.03
  5073.4  160.08  5193.6  159.54  5283.7  162.54  5306.3  162.46  5341.7   163.9
  5346.7  163.24  5373.9  166.07  5413.9  167.66  5453.2  166.88  5459.1  168.43
  5467.1  169.32  5474.4  169.02  5480.3   170.4  5495.6  170.33  5502.5  171.62
  5516.9  172.52  5578.6   175.1  5624.6  176.66  5655.4  177.85  5774.1  181.82
#Mann= 7 ,-1 , 0
    4239      .1       0  4990.3     .07       0  4996.3      .1       0
  5306.3     .05       0  5578.6      .1       0  5624.6     .05       0
  5655.4      .1       0
Bank Sta=4983.3,5043.4
XS Rating Curve= 0 ,0
Exp/Cntr=0.3,0.1

Type RM Length L Ch R = 1 ,28587   ,600,600,600
BEGIN DESCRIPTION:
UNT018 IN PECR 58.0
END DESCRIPTION:
XS GIS Cut Line= 3
      2299937.72     13218146.85      2300687.72     13217346.85
      2300787.74     13217196.82
#Sta/Elev= 30
  3899.5  180.86  4019.9  176.16  4246.1  168.33  4345.2  165.75    4501  163.11
  4684.7  157.45  4762.8  157.16  4769.7  156.53  4783.8  157.19  4804.9  156.64
  4833.2  156.72  4854.7  157.41  4918.2  157.23  4953.8  157.97  4974.8  157.56
    4989  154.56  4989.7  151.29  4992.4  150.79  4995.7  151.29  4999.1  151.29
  5003.6  152.98  5018.6  154.15  5032.1  157.42  5039.6  157.87  5054.7  158.74
  5060.7  159.77  5090.7  161.95  5096.7  162.99  5126.8  165.64  5176.4  168.83
#Mann= 3 ,-1 , 0
  3899.5      .1       0  4989.7     .07       0  4995.7      .1       0
Bank Sta=4974.8,5039.6
XS Rating Curve= 0 ,0
Exp/Cntr=0.3,0.1

Type RM Length L Ch R = 1 ,27987   ,788,788,788
BEGIN DESCRIPTION:
UNT018 IN PECR 57.0
END DESCRIPTION:
XS GIS Cut Line= 3
      2300184.84     13218337.08       2301000.8     13217668.69
      2301200.03     13217200.92
#Sta/Elev= 30
  4216.3  181.96  4239.9  181.87  4246.3   180.7  4297.3  178.44  4488.9   171.9
  4581.5  167.24    4588  167.79  4680.6  163.76  4787.5  160.44    4859  156.17
  4895.1  154.56  4929.6  153.21  4956.9  154.75  4979.1  153.04  4985.6  151.88
  4996.9  147.82  4999.7  147.32  5002.9  147.82  5007.8   151.5  5014.3  154.34
  5035.1  155.76  5049.5  154.91  5127.7  155.28  5273.5  154.23  5338.3  156.28
  5429.9  160.92  5436.1  160.14  5453.5  162.33    5608  170.13  5779.5  178.29
#Mann= 6 ,-1 , 0
  4216.3      .1       0    4859     .16       0  4895.1      .1       0
  4996.9     .07       0  5002.9      .1       0    5608     .05       0
Bank Sta=4956.9,5014.3
XS Rating Curve= 0 ,0
Exp/Cntr=0.3,0.1

Type RM Length L Ch R = 1 ,27199   ,435,435,435
BEGIN DESCRIPTION:
UNT018 IN PECR 56.0
END DESCRIPTION:
XS GIS Cut Line= 3
      2300543.81     13218558.75      2301576.79     13217855.63
      2301628.87     13217352.19
#Sta/Elev= 30
  4088.1  175.73  4250.1  171.32  4473.7  162.79  4503.6  162.72  4509.6  161.22
  4524.6  161.86  4588.8  159.91  4602.5  158.58  4680.1  157.65  4746.1  156.12
  4785.1  154.05  4891.2  150.02  4927.5  149.84  4955.6  150.85  4997.1  147.31
  4999.8  146.81  5003.1  147.31  5006.4  149.64  5012.5  148.83  5021.4  150.22
  5036.3  150.49  5129.1  152.38  5180.4   155.3  5266.2   157.9  5278.8  159.01
  5317.1  159.09  5337.7  158.66  5492.4   162.9  5642.8  165.49  5843.8  170.23
#Mann= 8 ,-1 , 0
  4088.1      .1       0  4680.1     .16       0  4785.1      .1       0
  4997.1     .07       0  5003.1      .1       0  5180.4     .08       0
  5317.1     .05       0  5642.8      .1       0
Bank Sta=4955.6,5036.3
XS Rating Curve= 0 ,0
Exp/Cntr=0.3,0.1

Type RM Length L Ch R = 1 ,26764   ,471,471,471
BEGIN DESCRIPTION:
UNT018 IN PECR 55.0
END DESCRIPTION:
XS GIS Cut Line= 3
      2301187.75     13218746.82      2301537.72     13218346.85
      2301937.69     13217946.89
#Sta/Elev= 30
  4453.8  168.48  4560.1  164.63  4602.3  161.99  4666.4  160.01  4758.9  154.54
  4765.5  153.54    4794  153.01  4843.6  150.14  4857.6     149  4865.2  149.54
  4871.8  148.86  4957.3  148.54  4981.9  146.35  4988.8  146.35  4996.4  145.11
  4999.2  144.61  5002.4  145.11  5013.5  145.11  5027.7  148.06  5041.8  148.58
  5157.1  150.37  5183.2  150.65  5239.8  152.81  5268.1  152.75  5292.8  153.63
  5338.8  156.12  5367.1  156.45  5425.9  159.07  5430.9  159.33  5550.9  163.25
#Mann= 8 ,-1 , 0
  4453.8     .05       0  4843.6      .1       0  4996.4     .07       0
  5002.4      .1       0  5157.1     .08       0  5292.8     .05       0
  5425.9     .08       0  5430.9      .1       0
Bank Sta=4957.3,5041.8
XS Rating Curve= 0 ,0
Exp/Cntr=0.3,0.1

Type RM Length L Ch R = 1 ,26293   ,508,508,508
BEGIN DESCRIPTION:
UNT018 IN PECR 54.0
END DESCRIPTION:
XS GIS Cut Line= 3
      2301587.72     13218946.85      2301837.72     13218646.85
      2302287.73     13217846.84
#Sta/Elev= 30
  4639.2  163.86  4745.3  158.55  4845.5  151.18  4860.5  150.91  4937.9  146.79
  4958.8  145.69  4965.3  144.71  5005.2  143.61    5008  143.11  5011.2  143.61
  5054.5  145.09  5059.3  145.96  5075.3  146.54    5097  146.17    5133  147.22
  5213.3  147.34  5242.9   148.6  5264.6  148.58  5280.5   149.8  5396.9   152.1
  5426.5  153.44  5448.2  153.29  5464.1  154.69  5500.1  155.42  5566.7  159.29
    5626  161.19  5764.1  167.75  5896.3  173.38  5945.4  174.37  5947.6  174.37
#Mann= 7 ,-1 , 0
  4639.2      .1       0  4860.5     .05       0  5005.2     .04       0
  5011.2     .05       0  5054.5      .1       0  5764.1     .08       0
  5945.4     .05       0
Bank Sta=4937.9,5075.3
XS Rating Curve= 0 ,0
Exp/Cntr=0.3,0.1

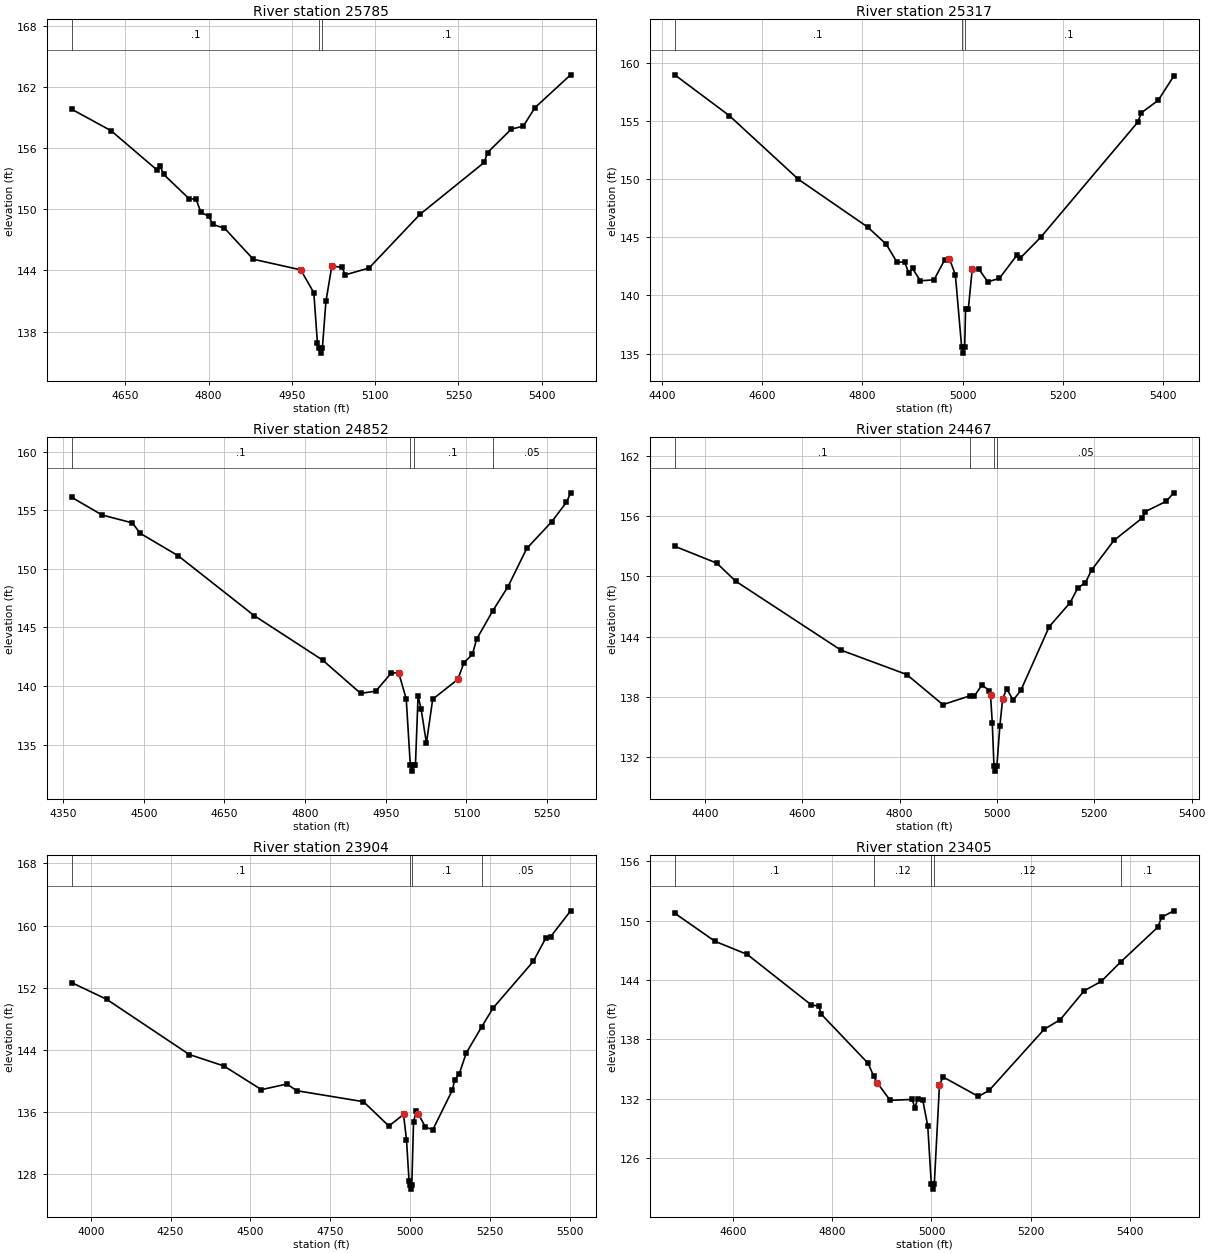
Type RM Length L Ch R = 1 ,25785   ,468,468,468
BEGIN DESCRIPTION:
UNT018 IN PECR 53.0
END DESCRIPTION:
XS GIS Cut Line= 3
      2302087.72     13219046.85      2302337.72     13218646.85
      2302487.72     13218246.85
#Sta/Elev= 30
  4553.2  159.81  4624.5  157.69  4706.5  153.87    4713  154.21  4718.9  153.42
  4764.9  151.02  4777.3  150.99  4786.1  149.69  4800.8  149.29  4807.3   148.5
  4828.5  148.14  4880.4  145.09  4965.9  144.05  4989.5   141.8    4996  136.87
  4998.9  136.38  5001.6  135.88  5004.9  136.38  5011.3  140.96  5021.9  144.41
    5040   144.3  5046.3  143.56    5089  144.23  5180.6  149.49  5296.3  154.58
  5302.6  155.56  5345.3  157.86  5366.7  158.14    5388  159.97  5452.1  163.18
#Mann= 3 ,-1 , 0
  4553.2      .1       0  4998.9     .07       0  5004.9      .1       0
Bank Sta=4965.9,5021.9
XS Rating Curve= 0 ,0
Exp/Cntr=0.3,0.1

Type RM Length L Ch R = 1 ,25317   ,465,465,465
BEGIN DESCRIPTION:
UNT018 IN PECR 52.0
END DESCRIPTION:
XS GIS Cut Line= 3
       2302487.7     13219246.89      2302787.72     13218746.85
      2302687.73      13218346.9
#Sta/Elev= 30
  4425.8  158.97  4534.7  155.46  4672.7  149.98  4810.7  145.88  4847.6  144.41
    4869  142.87  4884.5  142.86  4892.3  141.96  4900.1  142.33  4915.6  141.26
  4942.9  141.34  4964.2  143.05  4973.9  143.15  4985.6  141.77  4998.2  135.54
  5000.9  135.04  5004.2  135.54    5006  138.85  5011.5  138.85  5019.2  142.24
  5032.1  142.29  5050.2  141.17  5073.4  141.47  5109.4  143.52  5114.6  143.19
  5155.8     145  5349.1  154.88  5356.8  155.71  5390.3  156.78  5421.2  158.86
#Mann= 3 ,-1 , 0
  4425.8      .1       0  4998.2     .07       0  5004.2      .1       0
Bank Sta=4973.9,5019.2
XS Rating Curve= 0 ,0
Exp/Cntr=0.3,0.1

Type RM Length L Ch R = 1 ,24852   ,385,385,385
BEGIN DESCRIPTION:
UNT018 IN PECR 51.0
END DESCRIPTION:
XS GIS Cut Line= 3
      2302787.73     13219296.84      2303237.72     13218846.85
      2303387.71     13218596.88
#Sta/Elev= 30
  4365.8  156.11  4422.3   154.6  4478.9  153.92  4493.1  153.04  4563.8  151.12
  4705.2  146.01  4832.5  142.21  4903.2  139.37  4931.5  139.56  4959.8  141.09
  4973.9  141.14    4988  138.89  4995.6  133.23  4998.4  132.73  5001.6  133.23
  5005.1  133.23    5010  139.14  5015.8     138  5025.5  135.12  5037.2  138.87
  5083.8  140.56  5095.5     142    5111  142.69  5118.8  143.99  5149.2  146.44
  5177.1  148.47  5212.1  151.74  5258.7  154.03    5286  155.69  5293.7  156.49
#Mann= 4 ,-1 , 0
  4365.8      .1       0  4995.6     .07       0  5001.6      .1       0
  5149.2     .05       0
Bank Sta=4973.9,5083.8
XS Rating Curve= 0 ,0
Exp/Cntr=0.3,0.1

Type RM Length L Ch R = 1 ,24467   ,563,563,563
BEGIN DESCRIPTION:
UNT018 IN PECR 50.0
END DESCRIPTION:
XS GIS Cut Line= 3
      2303069.83     13219366.05      2303486.52     13219166.39
      2303772.37     13218681.31
#Sta/Elev= 30
  4338.1  153.01  4424.5  151.33  4463.4  149.53  4679.5  142.67  4814.7  140.24
  4888.9  137.24  4945.4  138.13  4953.3  138.06  4968.9  139.19  4984.6  138.64
 4986.82  138.19  4990.4  135.46  4993.9  131.12  4996.7  130.62  4999.9  131.12
    5006  135.12  5011.8  137.85  5020.2  138.81  5033.3  137.69    5049  138.65
  5107.5  145.01  5150.4   147.4  5166.1  148.86  5181.7  149.38  5194.3  150.63
  5240.3  153.59  5298.7  155.83  5304.7  156.46  5347.6  157.48  5363.2  158.33
#Mann= 4 ,-1 , 0
  4338.1      .1       0  4945.4     .05       0  4993.9    .035       0
  4999.9     .05       0
Bank Sta=4986.82,5011.8
XS Rating Curve= 0 ,0
Exp/Cntr=0.3,0.1

Type RM Length L Ch R = 1 ,23904   ,499,499,499
BEGIN DESCRIPTION:
UNT018 IN PECR 49.0
END DESCRIPTION:
XS GIS Cut Line= 4
      2303113.21      13219522.3      2303651.45     13219418.13
      2304007.35     13219418.13      2304284.51     13218820.49
#Sta/Elev= 30
  3940.2  152.65  4049.8   150.5  4308.7  143.38  4417.3   141.9  4534.7  138.85
  4614.7  139.58  4644.7  138.72  4854.2   137.3  4933.9  134.16  4979.7  135.65
    4989   132.4  4997.1  127.05  4999.6  126.53  5002.4  126.03  5005.6  126.53
  5011.1   134.7    5020  136.15  5025.5  135.75  5048.4  134.03  5071.4  133.68
  5132.3  138.76  5140.1   140.1  5154.4  140.93  5176.4  143.59  5224.6  146.96
  5260.1  149.37  5385.9  155.37    5426  158.44    5441  158.59  5503.1   161.9
#Mann= 4 ,-1 , 0
  3940.2      .1       0  4999.6     .07       0  5005.6      .1       0
  5224.6     .05       0
Bank Sta=4979.7,5025.5
XS Rating Curve= 0 ,0
Exp/Cntr=0.3,0.1

Type RM Length L Ch R = 1 ,23405   ,307,307,307
BEGIN DESCRIPTION:
UNT018 IN PECR 48.0
END DESCRIPTION:
XS GIS Cut Line= 3
       2304432.7     13219956.31      2304562.91       13219340.
      2304467.42     13218975.41
#Sta/Elev= 30
    4482  150.76  4563.2  147.92  4628.4  146.59  4757.4  141.49  4772.5  141.36
  4777.8  140.54    4872  135.59  4883.7  134.25  4890.3  133.63  4916.7  131.84
  4961.3  131.93  4966.4  131.06    4972  131.96  4982.3   131.9  4992.5  129.24
  4999.7  123.36  5002.4  122.86  5005.7  123.36  5016.1  133.34  5023.1  134.21
  5094.7  132.23  5116.5  132.85  5227.4  139.02  5259.9     140  5308.2  142.92
  5342.6  143.87  5382.2  145.85  5456.3  149.33  5464.7  150.36  5488.8     151
#Mann= 5 ,-1 , 0
    4482      .1       0  4883.7     .12       0  4999.7     .07       0
  5005.7     .12       0  5382.2      .1       0
Bank Sta=4890.3,5016.1
XS Rating Curve= 0 ,0
Exp/Cntr=0.3,0.1

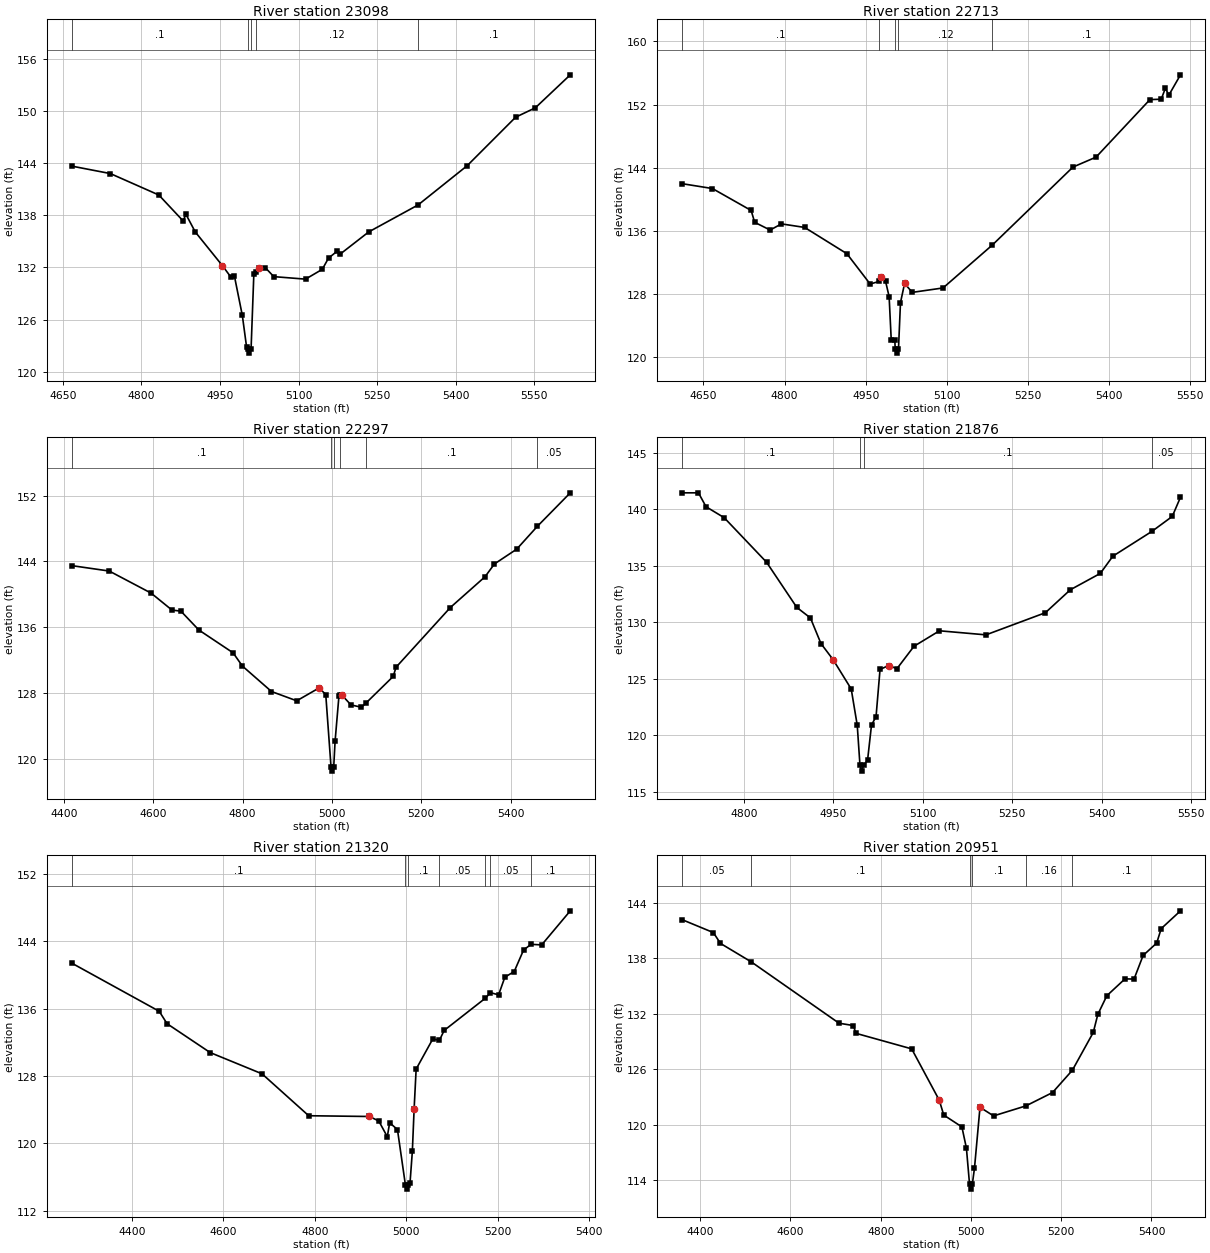
Type RM Length L Ch R = 1 ,23098   ,385,385,385
BEGIN DESCRIPTION:
UNT018 IN PECR 47.0
END DESCRIPTION:
XS GIS Cut Line= 2
      2304970.91     13219774.07      2304580.28     13218906.01
#Sta/Elev= 30
  4666.6  143.67  4740.5  142.81  4833.1  140.34  4879.4  137.36  4884.9  138.11
  4902.6  136.09  4954.4  132.21  4970.6  130.89  4977.5  130.97  4992.5  126.47
  5000.7   122.8  5003.2  122.63  5005.9  122.13  5009.2  122.63  5014.5  131.28
  5018.3  131.53  5023.8   131.9  5036.4  131.97  5052.5  130.94  5113.1  130.65
  5145.1  131.78    5157  133.07  5173.7  133.88  5179.2  133.53  5233.8  136.09
  5328.1   139.2  5421.6  143.71  5514.2   149.3  5551.8  150.38  5618.5  154.18
#Mann= 5 ,-1 , 0
  4666.6      .1       0  5003.2     .07       0  5009.2      .1       0
  5018.3     .12       0  5328.1      .1       0
Bank Sta=4954.4,5023.8
XS Rating Curve= 0 ,0
Exp/Cntr=0.3,0.1

Type RM Length L Ch R = 1 ,22713   ,416,416,416
BEGIN DESCRIPTION:
UNT018 IN PECR 46.0
END DESCRIPTION:
XS GIS Cut Line= 3
      2305387.71     13219546.84      2305137.72     13219246.85
      2304787.72     13218846.86
#Sta/Elev= 30
    4610  141.98  4666.6  141.36  4738.2  138.58  4744.7  137.08  4773.3   136.1
  4794.2  136.88  4837.1  136.43  4915.2   133.1  4958.2  129.26  4975.1  129.59
    4979  130.13  4986.8  129.58  4993.3  127.67  4997.2  122.18  5003.8  122.18
  5004.6     121  5007.4   120.5  5010.6     121  5014.3   126.9  5021.9  129.33
  5036.1   128.2    5093  128.76  5184.3  134.21  5333.2  144.08  5375.9  145.34
  5475.5  152.63  5496.4  152.68    5504  154.06  5510.6  153.21    5532  155.77
#Mann= 5 ,-1 , 0
    4610      .1       0  4975.1     .12       0  5004.6     .07       0
  5010.6     .12       0  5184.3      .1       0
Bank Sta=4979,5021.9
XS Rating Curve= 0 ,0
Exp/Cntr=0.3,0.1

Type RM Length L Ch R = 1 ,22297   ,421,421,421
BEGIN DESCRIPTION:
UNT018 IN PECR 45.0
END DESCRIPTION:
XS GIS Cut Line= 4
      2305569.85     13219530.95      2305595.89     13219175.07
      2305352.84     13218836.53      2305101.93     13218602.93
#Sta/Elev= 30
    4417  143.49  4501.3  142.83    4595  140.15  4641.7  138.09  4661.7  137.96
  4701.9  135.67  4778.5   132.9  4799.4  131.29  4864.5   128.2    4921  127.07
  4971.3  128.64    4986  127.82  4997.8  119.03  5000.5  118.53  5003.8  119.03
  5006.9  122.18  5015.5  127.65  5018.5  127.72  5021.7  127.79  5042.5  126.57
  5065.8  126.29  5075.9  126.79  5137.1  130.04  5143.2  131.14  5264.9   138.4
  5342.6  142.14  5363.6  143.69  5413.5  145.49  5459.5  148.25  5533.4  152.33
#Mann= 6 ,-1 , 0
    4417      .1       0  4997.8     .07       0  5003.8      .1       0
  5018.5     .12       0  5075.9      .1       0  5459.5     .05       0
Bank Sta=4971.3,5021.7
XS Rating Curve= 0 ,0
Exp/Cntr=0.3,0.1

Type RM Length L Ch R = 1 ,21876   ,556,556,556
BEGIN DESCRIPTION:
UNT018 IN PECR 44.0
END DESCRIPTION:
XS GIS Cut Line= 3
      2305887.73     13219246.89      2305837.72     13218946.85
      2305437.71     13218596.84
#Sta/Elev= 30
  4696.1  141.45    4724  141.45  4736.7  140.22  4767.1  139.25  4838.1  135.31
  4888.8  131.31  4911.6  130.38  4929.3  128.11  4949.6  126.69    4980  124.09
  4990.1  120.88  4994.7  117.32  4997.5  116.82  5000.7  117.32  5007.4  117.79
    5014   120.9  5021.6  121.64  5028.3  125.82  5042.5  126.16  5056.7  125.89
  5085.2  127.87  5127.9  129.24  5205.8  128.88  5305.4  130.84  5347.2  132.87
  5397.5  134.32  5418.4  135.84  5483.7  138.03    5518  139.36  5531.8  141.06
#Mann= 4 ,-1 , 0
  4696.1      .1       0  4994.7     .07       0  5000.7      .1       0
  5483.7     .05       0
Bank Sta=4949.6,5042.5
XS Rating Curve= 0 ,0
Exp/Cntr=0.3,0.1

Type RM Length L Ch R = 1 ,21320   ,369,369,369
BEGIN DESCRIPTION:
UNT018 IN PECR 43.0
END DESCRIPTION:
XS GIS Cut Line= 2
      2305969.16     13219244.52      2306194.85     13218176.81
#Sta/Elev= 30
  4267.9  141.39  4459.7  135.67  4476.8   134.2  4571.1  130.78  4684.6  128.26
  4786.8  123.29  4919.7   123.2  4940.1  122.67  4958.8   120.8  4963.9  122.46
    4981  121.65  4998.4  115.09  5001.2  114.59  5004.4  115.09  5008.5  115.32
  5013.6  119.07  5017.5  124.12  5021.9  128.82  5058.2  132.38  5072.9  132.24
  5083.2   133.4  5173.3  137.22  5184.6  137.88  5202.3  137.62  5216.1  139.72
  5236.5  140.38  5257.1  142.95  5273.6  143.61  5296.6  143.54  5359.2  147.58
#Mann= 7 ,-1 , 0
  4267.9      .1       0  4998.4     .07       0  5004.4      .1       0
  5072.9     .05       0  5173.3      .1       0  5184.6     .05       0
  5273.6      .1       0
Bank Sta=4919.7,5017.5
XS Rating Curve= 0 ,0
Exp/Cntr=0.3,0.1

Type RM Length L Ch R = 1 ,20951   ,576,576,576
BEGIN DESCRIPTION:
UNT018 IN PECR 42.0
END DESCRIPTION:
XS GIS Cut Line= 3
      2306090.67     13219357.38       2306351.1     13218905.97
      2306403.19     13218324.35
#Sta/Elev= 30
  4359.2  142.17  4429.1  140.76  4444.9  139.59  4513.3  137.59  4707.7  130.97
  4739.3  130.72    4745  129.88  4868.6   128.2  4929.7  122.66  4939.7  121.05
  4979.9  119.77  4989.9  117.48  4996.9  113.55  4999.7  113.05  5002.9  113.55
  5007.8  115.32    5020  121.89  5050.1  120.96  5121.7  122.04  5180.7  123.48
  5224.7  125.89    5271  129.97  5281.1  131.92  5301.1  133.94  5341.3  135.76
  5361.4  135.74  5381.5  138.29  5411.6  139.63  5421.6  141.19  5464.3  143.11
#Mann= 6 ,-1 , 0
  4359.2     .05       0  4513.3      .1       0  4996.9     .07       0
  5002.9      .1       0  5121.7     .16       0  5224.7      .1       0
Bank Sta=4929.7,5020
XS Rating Curve= 0 ,0
Exp/Cntr=0.3,0.1

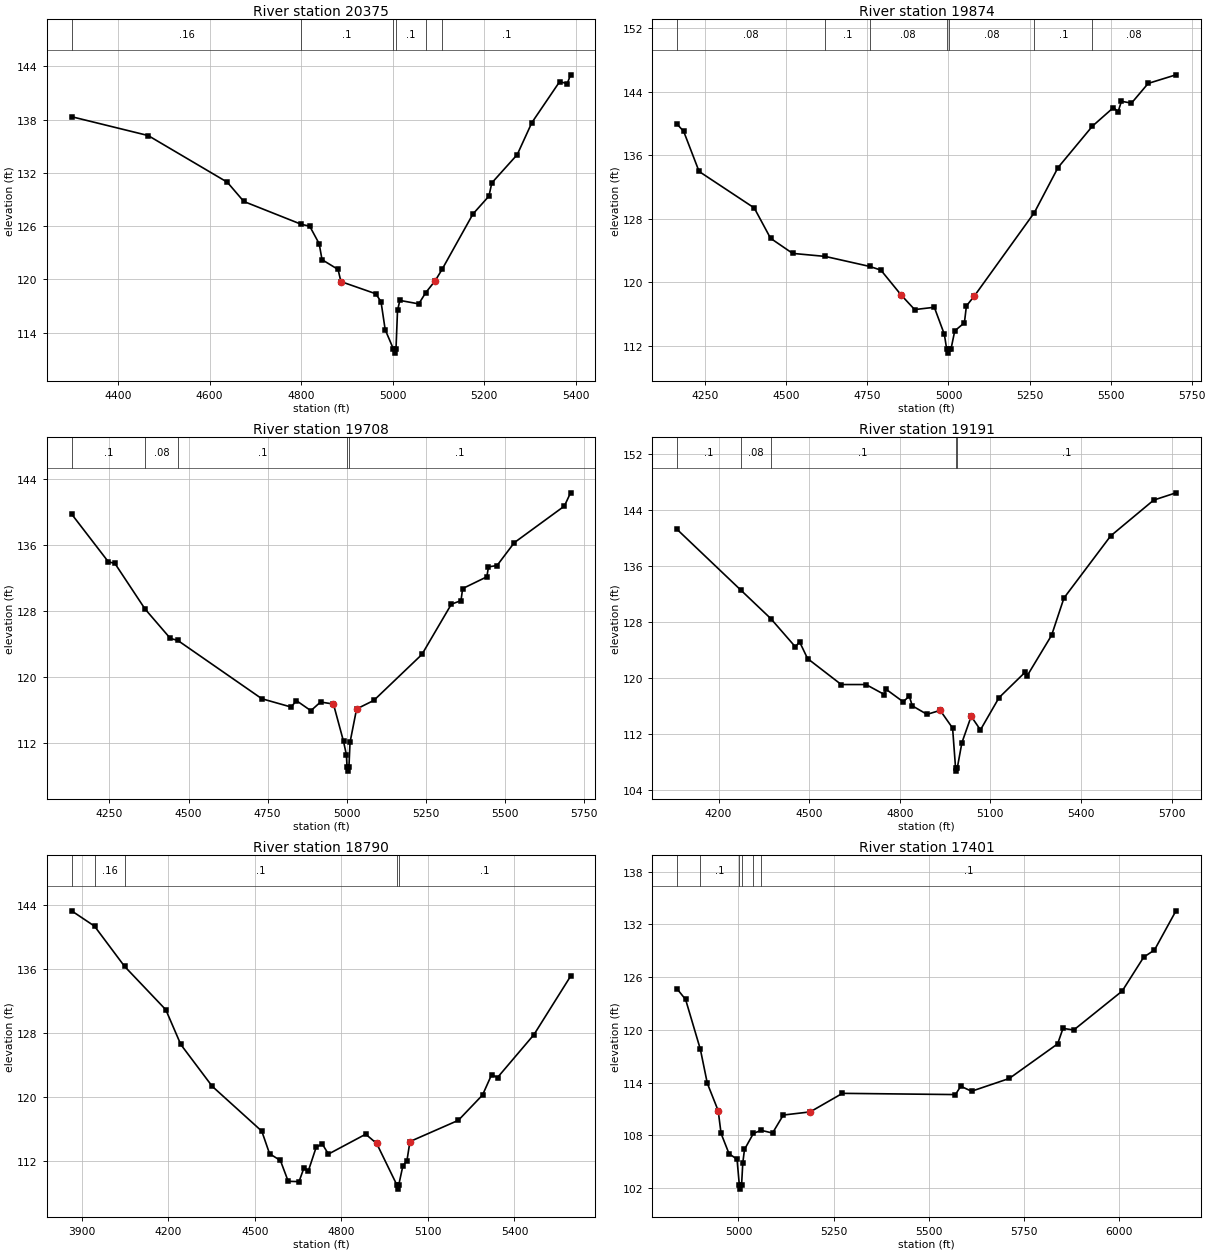
Type RM Length L Ch R = 1 ,20375   ,501,501,501
BEGIN DESCRIPTION:
UNT018 IN PECR 41.0
END DESCRIPTION:
XS GIS Cut Line= 3
      2306813.33     13219362.83      2306917.51     13218928.76
      2306761.27     13218303.79
#Sta/Elev= 30
  4298.5  138.34  4465.7  136.22  4638.8  130.96  4674.9  128.79  4800.4  126.22
    4819     126  4839.6  124.03  4845.9  122.23  4880.9  121.13  4887.2  119.76
  4963.3  118.39  4974.8   117.5  4983.9  114.35  5001.6   112.2  5004.3   111.7
  5007.6   112.2  5010.9  116.51    5016  117.64  5057.3  117.25  5072.5  118.51
  5093.3  119.86  5108.2  121.13  5175.8  127.38  5210.7  129.39    5217  130.88
  5272.6  134.07  5304.6  137.68  5365.3  142.29  5381.9  142.07  5389.1  143.06
#Mann= 6 ,-1 , 0
  4298.5     .16       0  4800.4      .1       0  5001.6     .07       0
  5007.6      .1       0  5072.5     .16       0  5108.2      .1       0
Bank Sta=4887.2,5093.3
XS Rating Curve= 0 ,0
Exp/Cntr=0.3,0.1

Type RM Length L Ch R = 1 ,19874   ,166,166,166
BEGIN DESCRIPTION:
UNT018 IN PECR 40.0
END DESCRIPTION:
XS GIS Cut Line= 2
      2307529.49     13219336.77      2307156.23     13217843.72
#Sta/Elev= 30
  4162.7  139.93  4183.2  139.01  4230.7  133.97  4400.8  129.38  4451.2  125.56
  4519.3  123.66  4619.7  123.28  4756.8  122.02  4791.4  121.56  4854.3  118.41
  4895.6  116.59  4956.3  116.88  4987.2  113.48  4994.5  111.61  4997.3  111.11
  5000.5  111.61  5007.8  111.63  5019.3  113.91  5049.1  114.93  5055.3  117.05
    5080  118.31    5265   128.8  5337.7  134.45  5443.9  139.67  5508.9  142.01
  5523.2  141.49  5533.5   142.8  5564.5  142.57    5616  145.05  5701.7  146.13
#Mann= 7 ,-1 , 0
  4162.7     .08       0  4619.7      .1       0  4756.8     .08       0
  4994.5     .07       0  5000.5     .08       0    5265      .1       0
  5443.9     .08       0
Bank Sta=4854.3,5080
XS Rating Curve= 0 ,0
Exp/Cntr=0.3,0.1

Type RM Length L Ch R = 1 ,19708   ,517,517,517
BEGIN DESCRIPTION:
UNT018 IN PECR 39.0
END DESCRIPTION:
XS GIS Cut Line= 2
      2307698.74     13219319.34      2307308.18     13217791.78
#Sta/Elev= 30
  4130.4  139.76  4246.5  133.96  4267.1  133.77  4362.6  128.22  4442.6  124.65
  4465.3  124.43  4731.6  117.33  4824.5  116.32  4840.5  117.11  4886.5  115.88
    4917  116.93  4957.8  116.69  4989.7  112.15  4998.7  110.54  5000.8  109.04
  5003.6  108.54  5006.8  109.04  5010.3  112.05    5031  116.09  5085.5  117.13
  5237.4  122.71  5330.4  128.81  5360.9  129.25  5366.1  130.71  5442.6  132.14
  5447.8  133.35  5474.8  133.51  5529.4  136.29  5687.6  140.73  5707.1  142.34
#Mann= 5 ,-1 , 0
  4130.4      .1       0  4362.6     .08       0  4465.3      .1       0
  5000.8     .07       0  5006.8      .1       0
Bank Sta=4957.8,5031
XS Rating Curve= 0 ,0
Exp/Cntr=0.3,0.1

Type RM Length L Ch R = 1 ,19191   ,401,401,401
BEGIN DESCRIPTION:
UNT018 IN PECR 38.0
END DESCRIPTION:
XS GIS Cut Line= 3
      2308101.49       13219318.      2308066.77     13218831.89
      2307815.04     13217694.77
#Sta/Elev= 30
  4062.4   141.2  4273.4  132.53  4372.6  128.46  4454.5   124.4  4467.9  125.15
  4494.6  122.74  4606.1  119.03  4688.1  119.03    4749   117.6  4754.1  118.37
    4811  116.57  4831.4  117.37  4841.3  115.99  4890.1  114.77  4933.7  115.34
  4974.8  112.81  4984.5  107.16  4987.3  106.66  4990.5  107.16  5005.6  110.72
  5036.3  114.49    5067  112.55  5128.6  117.16  5215.9  120.83    5221  120.23
  5302.6  126.07  5343.5  131.39  5498.1  140.26  5640.6  145.38  5714.4  146.42
#Mann= 5 ,-1 , 0
  4062.4      .1       0  4273.4     .08       0  4372.6      .1       0
  4984.5     .07       0  4990.5      .1       0
Bank Sta=4933.7,5036.3
XS Rating Curve= 0 ,0
Exp/Cntr=0.3,0.1

Type RM Length L Ch R = 1 ,18790   ,1389,1389,1389
BEGIN DESCRIPTION:
UNT018 IN PECR 37.0
END DESCRIPTION:
XS GIS Cut Line= 3
      2308743.83     13219291.93      2308526.84     13218944.73
      2308127.54     13217686.08
#Sta/Elev= 30
  3864.5  143.29  3943.9  141.37  4047.9  136.34  4191.1   130.9    4243  126.55
    4352  121.31  4523.9  115.69  4550.9  112.86  4588.4  112.02  4615.5  109.41
    4653  109.37  4670.4  111.12  4685.2   110.7  4712.3  113.66  4733.3   114.1
    4755  112.82  4884.1  115.31  4922.2  114.15  4992.6  108.93  4995.3  108.43
  4998.6  108.93  5013.2  111.36  5027.1  111.98  5037.6  114.39  5205.4  117.05
  5289.3  120.22  5320.8  122.77  5341.2  122.41  5467.7  127.79  5594.4  135.09
#Mann= 5 ,-1 , 0
  3864.5      .1       0  3943.9     .16       0  4047.9      .1       0
  4992.6     .07       0  4998.6      .1       0
Bank Sta=4922.2,5037.6
XS Rating Curve= 0 ,0
Exp/Cntr=0.3,0.1

Type RM Length L Ch R = 1 ,17401   ,276,276,276
BEGIN DESCRIPTION:
UNT018 IN PECR 36.0
END DESCRIPTION:
XS GIS Cut Line= 3
      2309187.71     13218546.85      2309037.72     13218446.85
      2308237.74     13217646.88
#Sta/Elev= 30
  4838.6  124.67  4861.1  123.46    4900  117.77  4918.2  113.92  4946.8   110.8
  4954.3  108.22  4975.3  105.91  4996.3  105.28  5002.3  102.38  5005.1  101.88
  5008.3  102.38  5011.4  104.85  5015.9  106.39  5039.4  108.23  5060.2  108.57
  5089.6  108.26  5117.9  110.31  5188.6  110.67  5273.4  112.78  5570.4  112.64
  5584.5  113.59  5612.8  113.02  5711.8  114.47  5839.1  118.41  5853.2  120.17
  5881.5  119.99  6008.8  124.42  6065.4  128.28  6093.7  129.09  6150.2  133.55
#Mann= 6 ,-1 , 0
  4838.6     .05       0    4900      .1       0  5002.3     .07       0
  5008.3      .1       0  5039.4     .16       0  5060.2      .1       0
Bank Sta=4946.8,5188.6
XS Rating Curve= 0 ,0
Exp/Cntr=0.3,0.1