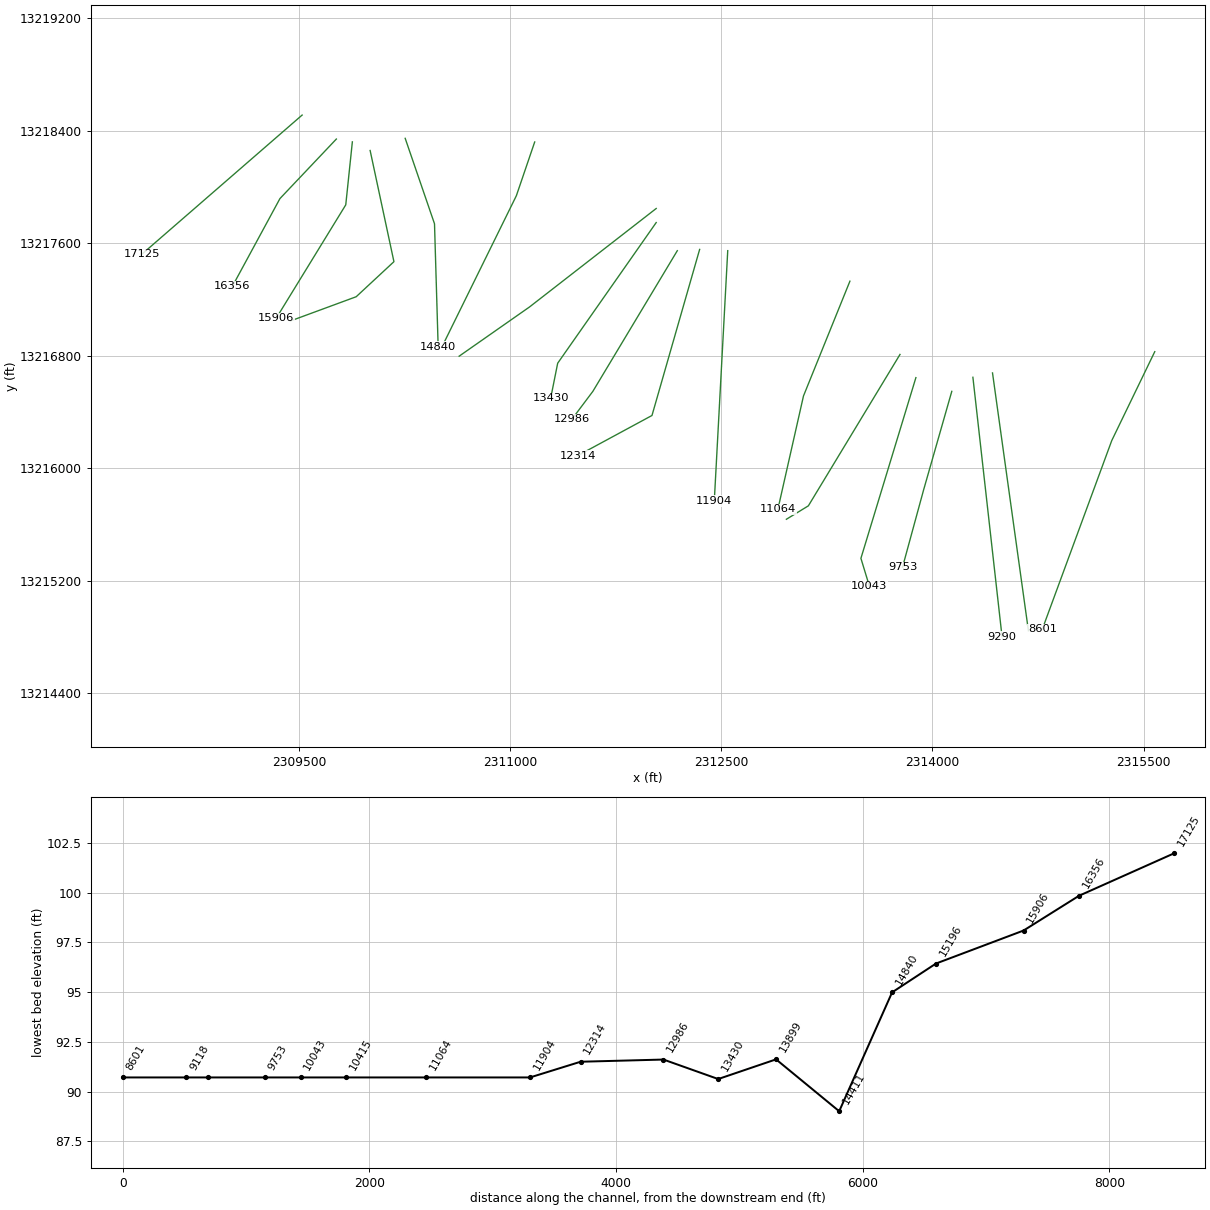
HEC-RAS study UNT018 IN PECR.prj: UNT018 IN PECR Base Level Engineering

--- UNT018 IN PECR.g01 (geometry) --- (continued)

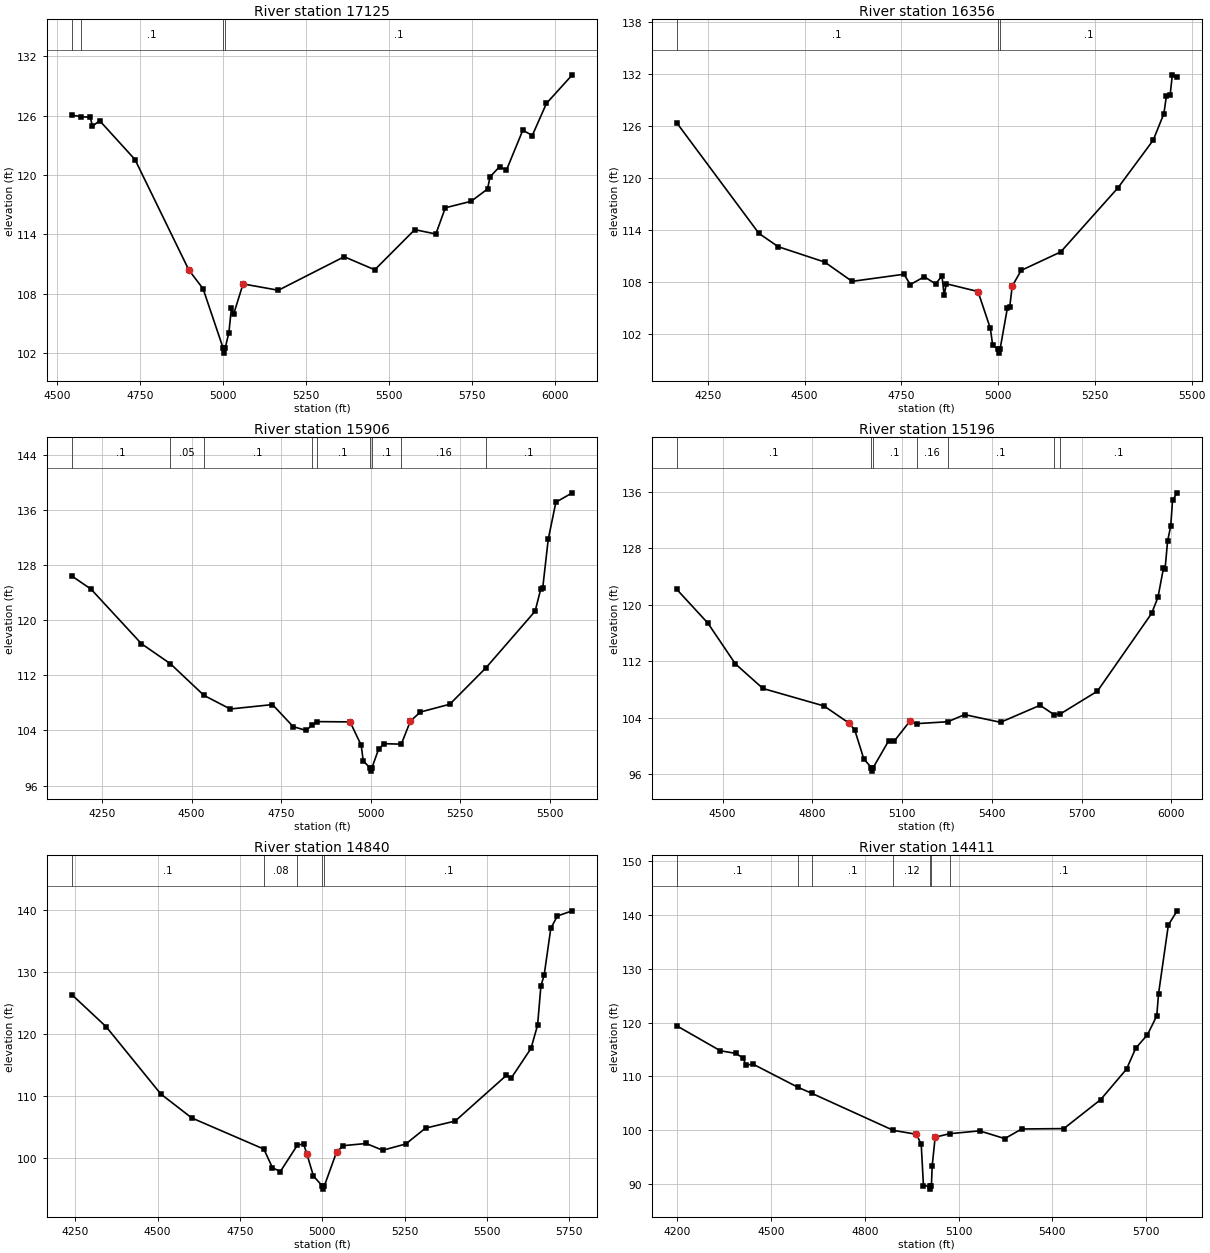
Type RM Length L Ch R = 1 ,17125   ,769,769,769
BEGIN DESCRIPTION:
UNT018 IN PECR 35.0
END DESCRIPTION:
XS GIS Cut Line= 2
      2309522.07     13218511.08      2308383.12      13217521.5
#Sta/Elev= 30
  4544.5  126.05  4573.2   125.9  4600.5  125.83  4607.1  124.95    4629  125.48
  4735.3  121.56  4897.7  110.38  4940.4   108.5    5001  102.48  5003.8  101.98
    5007  102.48  5018.3  104.06  5025.9  106.54  5032.5  105.91    5061  108.98
  5167.4  108.34  5365.8  111.73  5457.9  110.41  5578.5  114.47  5642.1  114.03
  5670.6  116.68  5748.5  117.34  5797.8  118.58  5805.5  119.82    5834  120.83
  5854.8  120.49  5904.2  124.53  5932.7  123.99  5975.4  127.24  6053.3  130.13
#Mann= 4 ,-1 , 0
  4544.5     .05       0  4573.2      .1       0    5001     .07       0
    5007      .1       0
Bank Sta=4897.7,5061
XS Rating Curve= 0 ,0
Exp/Cntr=0.3,0.1

Type RM Length L Ch R = 1 ,16356   ,450,450,450
BEGIN DESCRIPTION:
UNT018 IN PECR 34.0
END DESCRIPTION:
XS GIS Cut Line= 3
      2309765.22     13218340.58      2309364.56     13217917.48
      2309026.02     13217292.48
#Sta/Elev= 30
    4169  126.39  4381.9  113.63  4431.7   112.1  4551.8  110.33  4622.6  108.11
  4756.8  108.93    4773  107.74  4809.3  108.64  4838.6  107.81  4854.8  108.75
  4860.5  106.53  4866.2  107.83    4948  106.94  4979.9  102.69    4986  100.73
  4999.2  100.35    5002   99.85  5005.2  100.35  5024.1   105.1  5029.8  105.12
  5036.4  107.56  5059.5  109.37  5161.8   111.5  5309.7  118.88  5400.7  124.36
  5428.3  127.42  5434.8  129.45  5444.4  129.54  5450.1  131.88  5462.5  131.58
#Mann= 3 ,-1 , 0
    4169      .1       0  4999.2     .07       0  5005.2      .1       0
Bank Sta=4948,5036.4
XS Rating Curve= 0 ,0
Exp/Cntr=0.3,0.1

Type RM Length L Ch R = 1 ,15906   ,710,710,710
BEGIN DESCRIPTION:
UNT018 IN PECR 33.0
END DESCRIPTION:
XS GIS Cut Line= 3
      2309878.93     13218320.57      2309832.06     13217872.68
      2309337.26     13217065.38
#Sta/Elev= 30
  4165.6  126.41  4219.6  124.49  4360.4  116.57  4440.7  113.69  4534.6  109.09
  4608.1  107.11    4726  107.75    4784  104.54  4820.7     104  4835.3  104.75
  4849.2  105.28  4942.6  105.24  4973.5  101.87  4979.4   99.57  4997.7    98.6
  5000.4    98.1  5003.7    98.6    5022  101.26  5037.4  102.08  5085.5  102.01
  5110.9  105.35  5138.8  106.67  5220.9   107.8  5321.6  113.07    5459  121.29
  5474.5  124.45  5480.3  124.68  5495.7  131.73    5517   137.1  5562.8  138.46
#Mann= 9 ,-1 , 0
  4165.6      .1       0  4440.7     .05       0  4534.6      .1       0
  4835.3     .05       0  4849.2      .1       0  4997.7     .07       0
  5003.7      .1       0  5085.5     .16       0  5321.6      .1       0
Bank Sta=4942.6,5110.9
XS Rating Curve= 0 ,0
Exp/Cntr=0.3,0.1

Type RM Length L Ch R = 1 ,15196   ,356,356,356
BEGIN DESCRIPTION:
UNT018 IN PECR 32.0
END DESCRIPTION:
XS GIS Cut Line= 4
      2310005.25      13218259.2      2310174.31     13217468.78
      2309906.22     13217219.56      2309437.68     13217046.84
#Sta/Elev= 30
  4345.9   122.2  4450.6  117.39  4542.6  111.62  4634.6  108.14  4839.2  105.66
    4921  103.28  4941.4  102.31  4972.1   98.16  4997.4   96.94  5000.2   96.44
  5003.4   96.94    5055  100.72  5074.4  100.72  5125.5  103.48  5148.4  103.16
  5253.1  103.43  5308.9  104.44  5429.1  103.35  5561.3  105.76  5607.6  104.45
  5627.7   104.5  5753.1  107.76  5934.3  118.76  5955.6  121.06  5973.9  125.17
  5979.2     125  5987.6  128.97  5998.2  131.14  6004.3  134.77  6019.6  135.83
#Mann= 7 ,-1 , 0
  4345.9      .1       0  4997.4     .07       0  5003.4      .1       0
  5148.4     .16       0  5253.1      .1       0  5607.6     .16       0
  5627.7      .1       0
Bank Sta=4921,5125.5
XS Rating Curve= 0 ,0
Exp/Cntr=0.3,0.1

Type RM Length L Ch R = 1 ,14840   ,429,429,429
BEGIN DESCRIPTION:
UNT018 IN PECR 31.0
END DESCRIPTION:
XS GIS Cut Line= 3
      2310254.28     13218345.73       2310462.6     13217738.14
      2310488.64     13216861.64
#Sta/Elev= 30
  4239.5  126.38    4344  121.19    4510  110.33  4603.9  106.47  4822.6  101.45
  4848.8   98.44  4872.6   97.82    4924  102.05  4943.1   102.3  4953.1  100.69
  4973.1   97.11  5000.1   95.49  5002.9   94.99  5006.1   95.49  5043.2  100.95
  5063.2     102  5133.2  102.35  5183.2  101.26  5253.3  102.27  5313.3  104.83
  5403.3  105.97  5558.9  113.35  5573.4   112.9  5633.4  117.69  5653.4  121.45
  5663.4  127.75  5673.4  129.54  5693.5  137.06  5713.5  139.05  5758.7  139.88
#Mann= 5 ,-1 , 0
  4239.5      .1       0  4822.6     .08       0    4924      .1       0
  5000.1     .07       0  5006.1      .1       0
Bank Sta=4953.1,5043.2
XS Rating Curve= 0 ,0
Exp/Cntr=0.3,0.1

Type RM Length L Ch R = 1 ,14411   ,512,512,512
BEGIN DESCRIPTION:
UNT018 IN PECR 30.0
END DESCRIPTION:
XS GIS Cut Line= 3
      2311174.42     13218319.76       2311044.2     13217937.79
      2310514.79     13216861.62
#Sta/Elev= 30
    4197  119.42  4337.4  114.75  4386.6  114.27  4411.4  113.36  4417.9  112.12
  4443.1  112.23    4586  107.95  4631.2  106.81  4891.2   99.94  4965.1   99.22
  4980.5   97.33  4987.6   89.68    5007   89.51  5009.8   89.01    5013   89.51
  5015.6   93.32  5025.1   98.68  5071.4   99.32  5167.3   99.85    5248   98.41
  5302.2   100.2    5437  100.27  5554.9  105.66    5638  111.35  5667.3  115.23
  5704.9  117.74  5734.7  121.25  5740.3  125.33  5771.8  138.16  5799.9  140.79
#Mann= 7 ,-1 , 0
    4197      .1       0    4586     .08       0  4631.2      .1       0
  4891.2     .12       0    5007     .07       0    5013     .12       0
  5071.4      .1       0
Bank Sta=4965.1,5025.1
XS Rating Curve= 0 ,0
Exp/Cntr=0.3,0.1

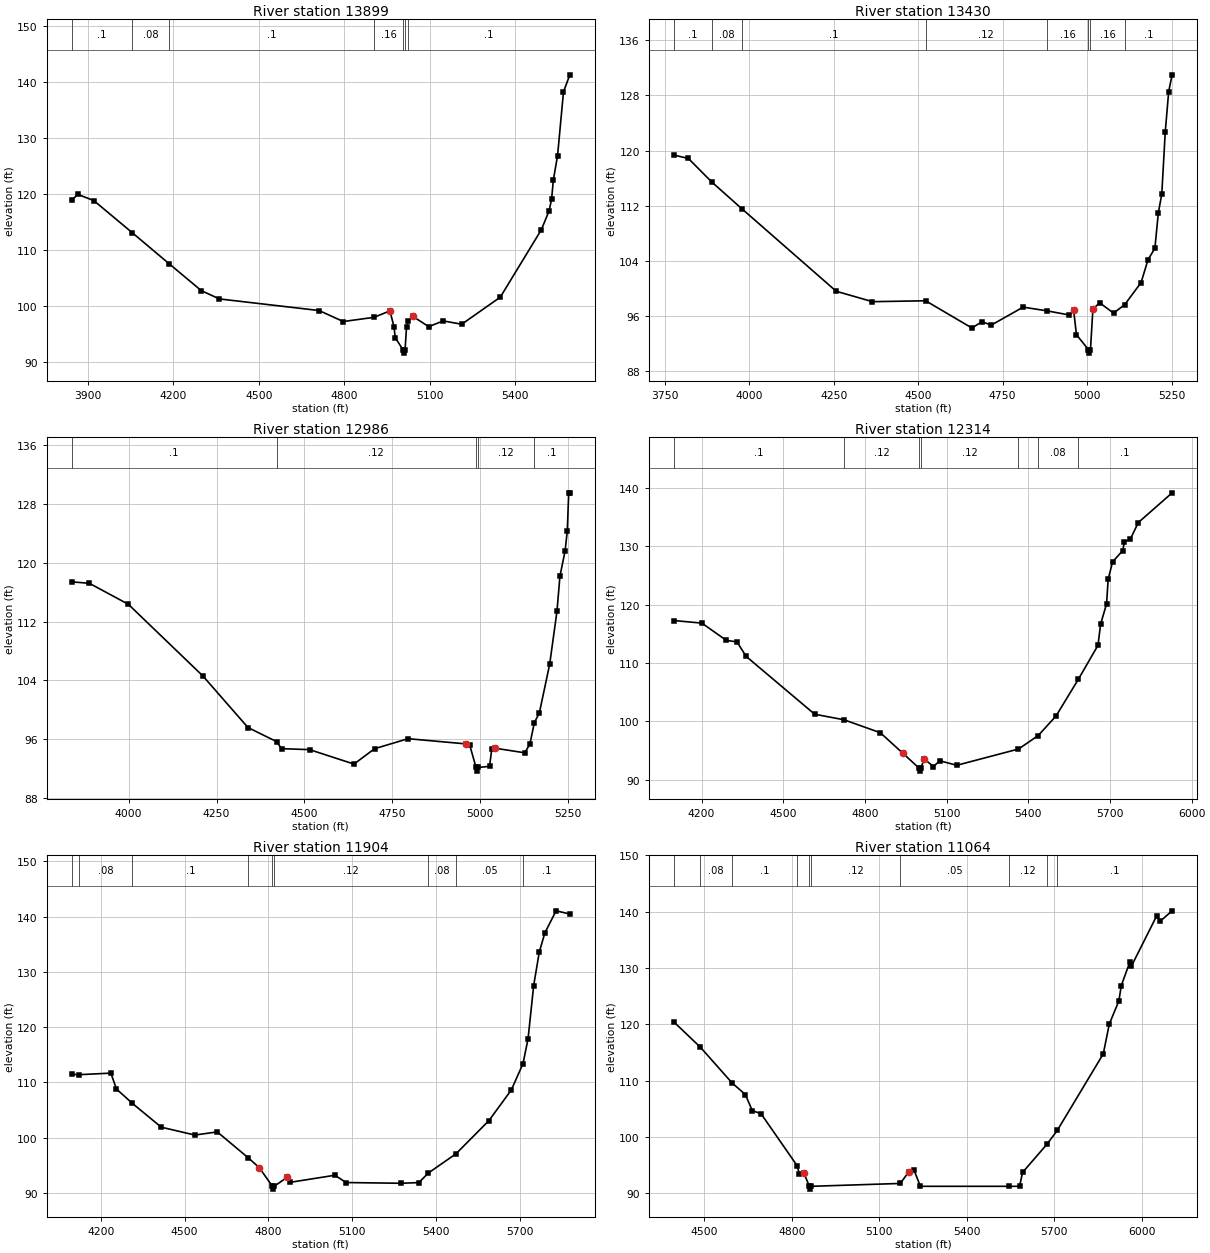
Type RM Length L Ch R = 1 ,13899   ,469,469,469
BEGIN DESCRIPTION:
UNT018 IN PECR 29.0
END DESCRIPTION:
XS GIS Cut Line= 3
      2312037.68     13217846.83      2311137.72     13217146.85
      2310637.68     13216796.83
#Sta/Elev= 30
  3842.4  118.86  3864.1  119.91  3920.2  118.82  4054.9  113.11  4186.3   107.5
  4298.4  102.75  4361.8  101.28    4712   99.21    4797   97.25  4905.9   98.01
  4960.8   99.16  4975.3   96.28  4979.4   94.39  5007.9   92.12  5010.6   91.62
  5013.9   92.12  5019.1   96.21  5025.9   97.37  5040.5   98.19  5097.2   96.34
  5147.8   97.36  5213.1   96.77  5348.7   101.6    5493  113.63  5520.1     117
  5528.8  119.05  5534.9  122.47  5549.7  126.79  5570.6   138.2  5592.9  141.22
#Mann= 7 ,-1 , 0
  3842.4      .1       0  4054.9     .08       0  4186.3      .1       0
  4905.9     .16       0  5007.9     .07       0  5013.9     .16       0
  5025.9      .1       0
Bank Sta=4960.8,5040.5
XS Rating Curve= 0 ,0
Exp/Cntr=0.3,0.1

Type RM Length L Ch R = 1 ,13430   ,444,444,444
BEGIN DESCRIPTION:
UNT018 IN PECR 28.0
END DESCRIPTION:
XS GIS Cut Line= 3
       2312037.7     13217746.83      2311337.72     13216746.85
      2311287.72     13216496.83
#Sta/Elev= 30
  3776.2  119.35  3819.3  118.85  3888.7  115.43  3977.7  111.56    4257    99.6
  4364.3   98.09  4521.9   98.22    4659   94.27  4688.6   95.19  4716.1   94.69
  4810.7    97.3  4879.8   96.77  4947.6   96.16  4960.2   96.83  4968.5   93.31
    5004   91.13  5006.8   90.63    5010   91.13  5017.2   97.04  5037.6   97.92
  5078.4   96.43  5111.6   97.67    5160  100.87  5180.4  104.17  5200.8  105.84
    5211  110.97  5221.2  113.68  5231.4  122.65  5241.6  128.54  5251.8  130.98
#Mann= 8 ,-1 , 0
  3776.2      .1       0  3888.7     .08       0  3977.7      .1       0
  4521.9     .12       0  4879.8     .16       0    5004     .07       0
    5010     .16       0  5111.6      .1       0
Bank Sta=4960.2,5017.2
XS Rating Curve= 0 ,0
Exp/Cntr=0.3,0.1

Type RM Length L Ch R = 1 ,12986   ,672,672,672
BEGIN DESCRIPTION:
UNT018 IN PECR 27.0
END DESCRIPTION:
XS GIS Cut Line= 3
      2312187.71     13217546.84      2311587.72     13216546.85
       2311437.7     13216346.83
#Sta/Elev= 30
    3838  117.41  3888.5  117.21  3999.3  114.35  4211.2  104.58  4339.4   97.55
  4420.8   95.63  4434.7   94.67  4514.4   94.54  4640.7   92.57    4699   94.66
  4794.3   96.03  4959.5   95.32  4969.2   95.23  4987.6   92.11  4990.3   91.61
  4993.6   92.11    5026   92.26  5032.3   94.61  5040.6   94.74    5126   94.11
  5140.6   95.29  5153.3    98.2  5167.7   99.58  5196.9  106.18  5217.7  113.43
    5226  118.16  5240.6   121.6  5246.9  124.29    5251  129.54  5254.2  129.54
#Mann= 5 ,-1 , 0
    3838      .1       0  4420.8     .12       0  4987.6     .07       0
  4993.6     .12       0  5153.3      .1       0
Bank Sta=4959.5,5040.6
XS Rating Curve= 0 ,0
Exp/Cntr=0.3,0.1

Type RM Length L Ch R = 1 ,12314   ,410,410,410
BEGIN DESCRIPTION:
UNT018 IN PECR 26.0
END DESCRIPTION:
XS GIS Cut Line= 3
      2312346.28     13217555.85      2312007.74     13216375.29
      2311478.21     13216088.82
#Sta/Elev= 30
    4098  117.26    4201  116.82  4290.9  113.86  4329.8  113.62  4363.5  111.13
  4615.4  101.23  4722.6  100.29  4856.4   98.07  4939.6   94.54    4999      92
  5001.8    91.5    5005      92  5017.7   93.58  5051.5   92.28  5074.8   93.27
  5137.3    92.5  5363.8   95.28  5436.3   97.58  5501.9  100.94  5583.5  107.19
  5655.9  113.02  5665.6  116.65  5687.5  120.13  5693.2  124.29  5709.4  127.29
  5746.8  129.23  5753.1  130.72    5775   131.2  5803.7  134.01  5928.2  139.11
#Mann= 7 ,-1 , 0
    4098      .1       0  4722.6     .12       0    4999     .07       0
    5005     .12       0  5363.8     .05       0  5436.3     .08       0
  5583.5      .1       0
Bank Sta=4939.6,5017.7
XS Rating Curve= 0 ,0
Exp/Cntr=0.3,0.1

Type RM Length L Ch R = 1 ,11904   ,840,840,840
BEGIN DESCRIPTION:
UNT018 IN PECR 25.0
END DESCRIPTION:
XS GIS Cut Line= 2
      2312545.94      13217547.2      2312450.45     13215767.66
#Sta/Elev= 30
  4095.8  111.48  4123.8  111.41  4236.3  111.69  4256.4  108.81  4312.8  106.24
  4416.6  101.91  4536.8  100.49  4616.9  101.06  4728.4   96.34  4767.1    94.6
  4814.2   91.21  4816.9   90.71  4820.2   91.21  4867.3   92.87  4877.3   91.94
  5037.5   93.22  5077.6    91.9  5274.2   91.77  5337.9   91.89  5371.4   93.61
  5470.5   97.09  5588.3  103.09  5668.4  108.63  5710.3  113.39  5728.5  117.92
  5748.5  127.51  5768.5  133.57  5788.6  137.05  5828.6  141.04  5877.9  140.47
#Mann= 9 ,-1 , 0
  4095.8      .1       0  4123.8     .08       0  4312.8      .1       0
  4728.4     .12       0  4814.2     .07       0  4820.2     .12       0
  5371.4     .08       0  5470.5     .05       0  5710.3      .1       0
Bank Sta=4767.1,4867.3
XS Rating Curve= 0 ,0
Exp/Cntr=0.3,0.1

Type RM Length L Ch R = 1 ,11064   ,649,649,649
BEGIN DESCRIPTION:
UNT018 IN PECR 23.0
END DESCRIPTION:
XS GIS Cut Line= 3
      2313413.99     13217330.14      2313084.13     13216514.18
      2312901.84     13215706.92
#Sta/Elev= 30
  4395.7  120.41  4486.3  115.94  4595.2  109.58  4640.6  107.52  4664.7  104.64
  4694.2  104.13  4818.3   94.87  4825.6   93.44  4841.5   93.57  4860.1   91.21
  4862.8   90.71  4866.1   91.21  5171.9   91.72  5201.2   93.81    5219   94.07
  5240.6   91.21  5543.2   91.21  5580.6   91.21  5590.9   93.68  5674.7    98.7
  5709.7  101.13  5867.5  114.74  5888.2  120.05  5920.9  124.14  5929.2  126.87
    5959  131.12  5964.1  130.34  6050.6  139.26  6062.5   138.3  6103.4  140.15
#Mann= 10 ,-1 , 0
  4395.7      .1       0  4486.3     .08       0  4595.2      .1       0
  4818.3     .12       0  4860.1     .07       0  4866.1     .12       0
  5171.9     .05       0  5543.2     .12       0  5674.7     .08       0
  5709.7      .1       0
Bank Sta=4841.5,5201.2
XS Rating Curve= 0 ,0
Exp/Cntr=0.3,0.1

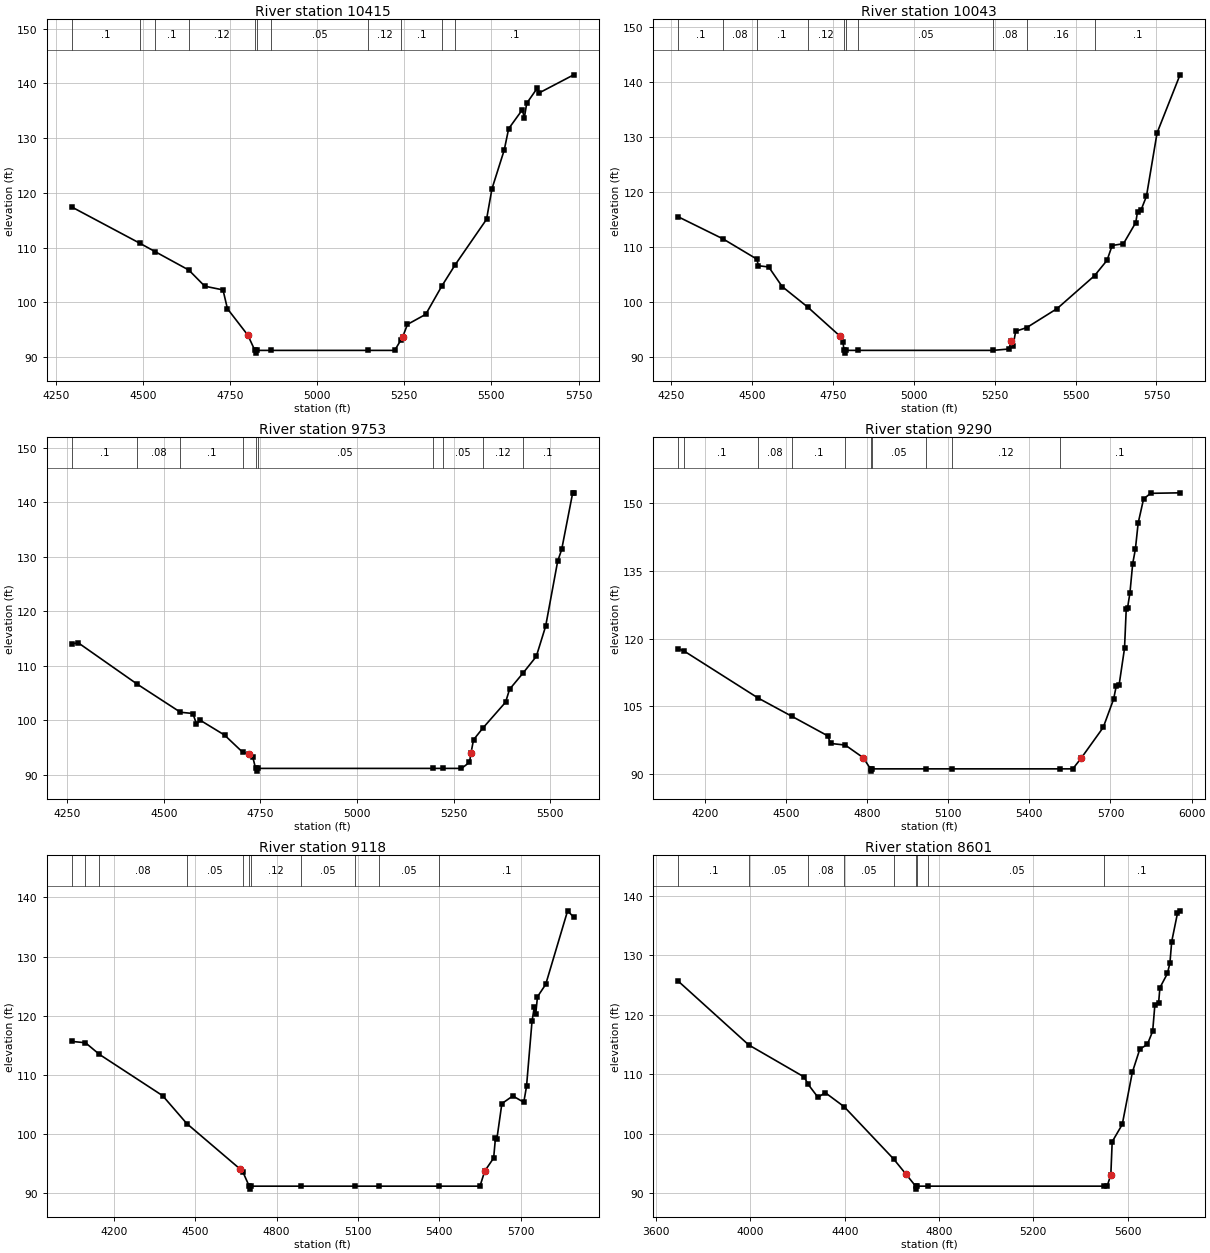
Type RM Length L Ch R = 1 ,10415   ,372,372,372
BEGIN DESCRIPTION:
UNT018 IN PECR 22.0
END DESCRIPTION:
XS GIS Cut Line= 3
      2313769.87     13216809.29      2313118.85     13215732.93
      2312962.64     13215637.46
#Sta/Elev= 30
  4295.2  117.41  4491.7  110.75  4534.6  109.25  4631.2  105.89    4677  102.94
  4729.4  102.26  4742.1   98.82  4800.6      94  4820.9   91.21  4823.7   90.71
  4826.9   91.21  4868.6   91.21  5145.4   91.21  5222.2   91.21    5240   93.09
  5244.7    93.6    5259   95.96  5311.4    97.8  5357.6  102.97  5396.1  106.87
    5486  115.16  5501.5  120.73  5536.8  127.83  5549.4  131.71  5588.6  135.17
  5594.5  133.71  5601.3  136.36  5631.3   139.1  5637.1  138.26  5736.2  141.56
#Mann= 11 ,-1 , 0
  4295.2      .1       0  4491.7     .08       0  4534.6      .1       0
  4631.2     .12       0  4820.9     .04       0  4826.9     .12       0
  4868.6     .05       0  5145.4     .12       0    5240      .1       0
  5357.6     .08       0  5396.1      .1       0
Bank Sta=4800.6,5244.7
XS Rating Curve= 0 ,0
Exp/Cntr=0.3,0.1

Type RM Length L Ch R = 1 ,10043   ,290,290,290
BEGIN DESCRIPTION:
UNT018 IN PECR 21.0
END DESCRIPTION:
XS GIS Cut Line= 3
      2313882.73     13216644.37      2313492.12     13215359.66
      2313552.51     13215161.23
#Sta/Elev= 30
  4272.5   115.5  4411.4  111.47  4515.6   107.8  4520.7  106.59  4552.4  106.37
  4593.9  102.81  4672.8   99.08  4771.6   93.85    4782   92.73  4784.7   91.21
  4787.5   90.71  4790.7   91.21  4828.2   91.21  5245.1   91.21  5294.2   91.46
  5301.6   92.95  5306.8   91.92  5315.1   94.68  5349.3   95.35  5443.5   98.82
  5558.6  104.78  5597.3  107.58  5613.1  110.27    5648   110.6  5686.1  114.45
  5691.4  116.42  5701.8  116.64    5719  119.22  5751.8  130.73  5822.7  141.29
#Mann= 10 ,-1 , 0
  4272.5      .1       0  4411.4     .08       0  4515.6      .1       0
  4672.8     .12       0  4784.7     .03       0  4790.7     .12       0
  4828.2     .05       0  5245.1     .08       0  5349.3     .16       0
  5558.6      .1       0
Bank Sta=4771.6,5301.6
XS Rating Curve= 0 ,0
Exp/Cntr=0.3,0.1

Type RM Length L Ch R = 1 ,9753    ,463,463,463
BEGIN DESCRIPTION:
UNT018 IN PECR 20.0
END DESCRIPTION:
XS GIS Cut Line= 3
      2314137.72     13216546.85      2313937.72     13215846.85
      2313787.72     13215296.85
#Sta/Elev= 30
  4262.2  114.07  4279.1  114.24  4431.8  106.65  4543.3  101.51  4575.5  101.28
  4584.6   99.38    4595  100.02  4657.4   97.32  4704.7   94.14  4721.1   93.83
  4730.2   93.32  4737.6   91.21  4740.4   90.71  4743.6   91.21  5195.4   91.21
    5222   91.21  5270.1   91.21  5290.8   92.32 5294.55   93.98  5301.2   96.46
  5325.3    98.6  5384.1  103.35  5394.4  105.72  5428.5  108.63  5463.5  111.74
  5487.7  117.28  5518.8   129.2  5529.2  131.37  5557.7  141.76  5560.3  141.76
#Mann= 10 ,-1 , 0
  4262.2      .1       0  4431.8     .08       0  4543.3      .1       0
  4704.7     .05       0  4737.6     .04       0  4743.6     .05       0
  5195.4     .12       0    5222     .05       0  5325.3     .12       0
  5428.5      .1       0
Bank Sta=4721.1,5294.55
XS Rating Curve= 0 ,0
Exp/Cntr=0.3,0.1

Type RM Length L Ch R = 1 ,9290    ,172,172,172
BEGIN DESCRIPTION:
UNT018 IN PECR 19.0
END DESCRIPTION:
XS GIS Cut Line= 2
      2314287.72     13216646.84      2314494.76     13214802.92
#Sta/Elev= 30
  4101.6  117.77    4125   117.2  4397.5  106.86  4521.4  102.85    4655    98.5
  4665.1   96.83  4719.6   96.47  4785.9   93.68    4813   91.21  4815.8   90.71
    4819   91.21  5016.9   91.21    5116   91.21  5512.1   91.21  5560.7   91.21
  5590.9   93.51  5673.2  100.37  5711.6  106.62  5721.7  109.62  5731.8  109.71
  5751.9  117.83  5758.3  126.59  5763.3  126.85    5772  130.12  5782.1  136.55
  5792.1  139.75  5802.2  145.47  5822.3  150.85  5848.3   152.1  5957.1  152.21
#Mann= 10 ,-1 , 0
  4101.6     .16       0    4125      .1       0  4397.5     .08       0
  4521.4      .1       0  4719.6     .05       0    4813     .04       0
    4819     .05       0  5016.9      .1       0    5116     .12       0
  5512.1      .1       0
Bank Sta=4785.9,5590.9
XS Rating Curve= 0 ,0
Exp/Cntr=0.3,0.1

Type RM Length L Ch R = 1 ,9118    ,517,517,517
BEGIN DESCRIPTION:
UNT018 IN PECR 18.0
END DESCRIPTION:
XS GIS Cut Line= 2
      2314427.06     13216677.85      2314682.27     13214844.52
#Sta/Elev= 30
  4044.8  115.66  4095.3  115.44  4146.7  113.47    4380  106.49    4469  101.78
  4666.4   94.07  4675.3   93.67  4699.1   91.21  4701.8   90.71  4705.1   91.21
  4890.1   91.21  5088.8   91.21  5178.5   91.21  5399.2   91.21  5550.2   91.21
 5567.69   93.76  5600.6   95.96  5607.3   99.38  5612.4   99.16  5630.9  105.16
  5671.3  106.45  5711.7  105.38  5721.8  108.06    5742  119.03  5750.5  121.49
  5755.6  120.23  5762.2  123.21  5792.5  125.29  5873.3  137.72  5895.8  136.65
#Mann= 11 ,-1 , 0
  4044.8     .08       0  4095.3      .1       0  4146.7     .08       0
    4469     .05       0  4675.3     .12       0  4699.1    .033       0
  4705.1     .12       0  4890.1     .05       0  5088.8      .1       0
  5178.5     .05       0  5399.2      .1       0
Bank Sta=4666.4,5567.69
XS Rating Curve= 0 ,0
Exp/Cntr=0.3,0.1

Type RM Length L Ch R = 1 ,8601    ,596,596,596
BEGIN DESCRIPTION:
UNT018 IN PECR 17.0
END DESCRIPTION:
XS GIS Cut Line= 3
      2315579.85     13216828.98      2315274.28     13216196.99
      2314781.21     13214856.69
#Sta/Elev= 30
  3692.7  125.69  3992.5  114.95  4228.2  109.55  4244.3  108.34  4286.4  106.14
  4317.1  106.93  4397.5  104.56  4607.1   95.79  4657.9   93.32  4700.8   91.21
  4703.6   90.71  4706.8   91.21  4755.3   91.21  5501.1   91.21  5513.6   91.21
  5529.2   93.15  5534.9   98.68  5577.6  101.58  5620.6  110.37  5652.1  114.24
  5684.1  115.03  5706.7  117.25  5716.1   121.7  5731.8  121.94  5737.4  124.56
  5769.3  126.96    5780  128.73  5787.4   132.3    5812  137.09  5822.8  137.49
#Mann= 9 ,-1 , 0
  3692.7      .1       0  3992.5     .05       0  4244.3     .08       0
  4397.5     .05       0  4607.1     .07       0  4700.8    .033       0
  4706.8     .07       0  4755.3     .05       0  5501.1      .1       0
Bank Sta=4657.9,5529.2
XS Rating Curve= 0 ,0
Exp/Cntr=0.3,0.1