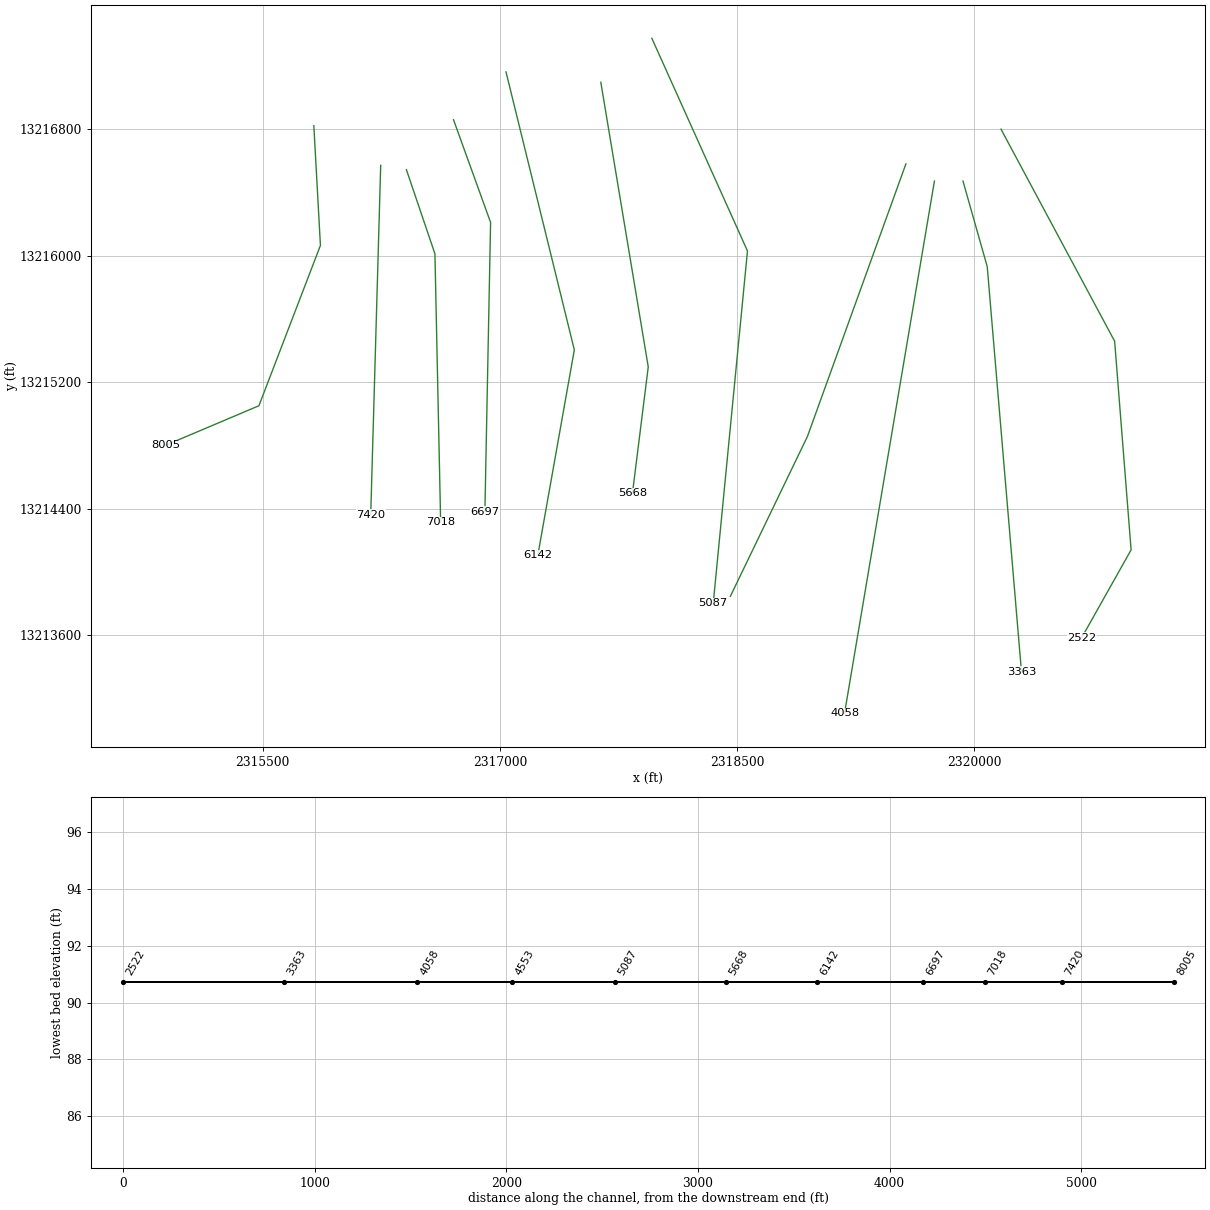
HEC-RAS study UNT018 IN PECR.prj: UNT018 IN PECR Base Level Engineering

--- UNT018 IN PECR.g01 (geometry) --- (continued)

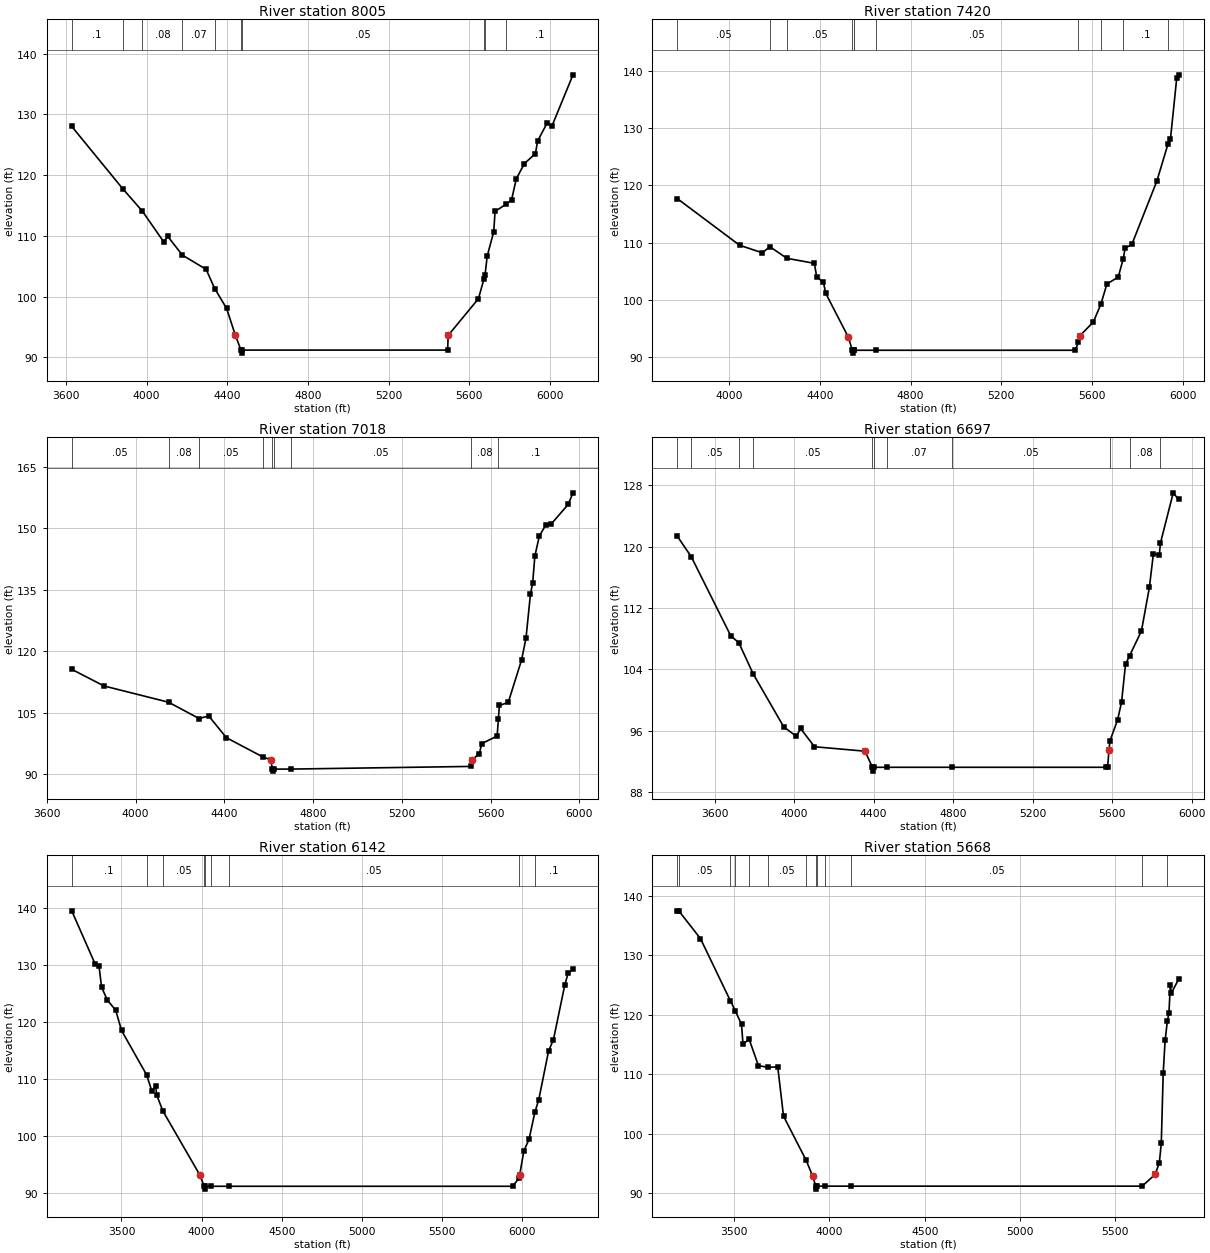
Type RM Length L Ch R = 1 ,8005    ,585,585,585
BEGIN DESCRIPTION:
UNT018 IN PECR 16.0
END DESCRIPTION:
XS GIS Cut Line= 4
      2315822.89     13216821.98      2315864.56     13216065.05
      2315475.67     13215051.16      2314886.24     13214801.52
#Sta/Elev= 30
  3629.3  128.04  3881.2  117.81    3980  114.06  4085.1  109.03  4105.1  109.93
  4177.6  106.85  4295.4   104.5  4337.7  101.35    4397   98.06 4439.71    93.7
    4468   91.21  4470.8   90.71    4474   91.21  5492.2   91.21 5494.83   93.63
  5644.8   99.67  5672.5  102.95  5677.6  103.62  5688.3  106.69  5720.8  110.72
  5727.1  114.05  5782.9  115.24    5809  115.95  5832.7  119.43  5872.9  121.93
  5927.2  123.56  5938.3  125.64  5985.6  128.62  6009.3  128.11  6113.4  136.53
#Mann= 10 ,-1 , 0
  3629.3      .1       0  3881.2     .05       0    3980     .08       0
  4177.6     .07       0  4337.7     .05       0    4468    .033       0
    4474     .05       0  5672.5      .1       0  5677.6     .08       0
  5782.9      .1       0
Bank Sta=4439.71,5494.83
XS Rating Curve= 0 ,0
Exp/Cntr=0.3,0.1

Type RM Length L Ch R = 1 ,7420    ,402,402,402
BEGIN DESCRIPTION:
UNT018 IN PECR 15.0
END DESCRIPTION:
XS GIS Cut Line= 2
      2316245.73     13216571.41      2316182.58     13214361.01
#Sta/Elev= 30
  3770.9  117.66  4045.6  109.53  4145.6  108.21  4179.5  109.26  4254.4  107.25
  4375.7  106.37  4385.7  104.03  4415.7  103.03  4425.7  101.14  4525.8   93.47
  4542.8   91.21  4545.5   90.71  4548.8   91.21  4551.2   91.21  4646.7   91.21
  5526.2   91.21  5540.5   92.63  5546.2   93.71  5606.2   96.13  5639.4   99.24
  5666.2  102.78  5716.2  103.97  5738.3   107.2  5746.3  109.02  5776.3  109.69
  5886.3   120.7  5936.2  127.26  5946.3  127.98  5974.3  138.74  5982.2  139.25
#Mann= 11 ,-1 , 0
  3770.9     .05       0  4179.5     .08       0  4254.4     .05       0
  4542.8    .033       0  4548.8     .05       0  4551.2     .07       0
  4646.7     .05       0  5540.5      .1       0  5639.4     .08       0
  5738.3      .1       0  5936.2     .08       0
Bank Sta=4525.8,5546.2
XS Rating Curve= 0 ,0
Exp/Cntr=0.3,0.1

Type RM Length L Ch R = 1 ,7018    ,321,321,321
BEGIN DESCRIPTION:
UNT018 IN PECR 14.0
END DESCRIPTION:
XS GIS Cut Line= 3
      2316408.18     13216544.37      2316588.69     13216011.86
      2316624.79     13214315.12
#Sta/Elev= 30
  3711.8  115.58    3857  111.52  4148.5  107.54    4286  103.56  4329.1   104.2
  4409.1   98.87  4573.9   94.16  4609.2   93.48  4616.2   91.21  4618.9   90.71
  4622.2   91.21  4701.4   91.21  5510.2   91.86 5515.64   93.46  5549.4   94.97
  5559.4   97.42  5629.4   99.29  5635.1  103.54  5639.4  106.75  5679.4   107.5
  5739.4  117.86  5759.4   123.2  5779.4  133.92  5789.4   136.7  5799.4  143.26
  5819.4  148.12  5849.4  150.93  5874.1  151.15  5949.5  155.86  5971.2   158.7
#Mann= 9 ,-1 , 0
  3711.8     .05       0  4148.5     .08       0    4286     .05       0
  4573.9     .07       0  4616.2    .033       0  4622.2     .07       0
  4701.4     .05       0  5510.2     .08       0  5635.1      .1       0
Bank Sta=4609.2,5515.64
XS Rating Curve= 0 ,0
Exp/Cntr=0.3,0.1

Type RM Length L Ch R = 1 ,6697    ,555,555,555
BEGIN DESCRIPTION:
UNT018 IN PECR 13.0
END DESCRIPTION:
XS GIS Cut Line= 3
      2316706.02     13216860.25      2316940.68     13216210.42
      2316904.61     13214380.08
#Sta/Elev= 30
  3412.6  121.34  3482.5  118.68    3682  108.33  3721.8  107.47  3794.3  103.39
  3947.8   96.49  4011.6   95.24  4032.9   96.27  4102.7   93.89  4357.1   93.31
  4394.1   91.21  4396.9   90.71  4400.1   91.21  4465.9   91.21  4793.8   91.21
  5567.3   91.21  5577.4   91.25 5584.01   93.41  5589.3   94.66  5627.4   97.39
  5647.4    99.7  5667.4  104.65  5688.2  105.78  5747.4  108.98  5787.4  114.66
  5807.4  119.01  5837.4  118.93  5843.1  120.45  5907.4     127  5934.2  126.14
#Mann= 11 ,-1 , 0
  3412.6      .1       0  3482.5     .05       0  3721.8     .08       0
  3794.3     .05       0  4394.1    .033       0  4400.1     .05       0
  4465.9     .07       0  4793.8     .05       0  5589.3      .1       0
  5688.2     .08       0  5843.1      .1       0
Bank Sta=4357.1,5584.01
XS Rating Curve= 0 ,0
Exp/Cntr=0.3,0.1

Type RM Length L Ch R = 1 ,6142    ,474,474,474
BEGIN DESCRIPTION:
UNT018 IN PECR 12.0
END DESCRIPTION:
XS GIS Cut Line= 3
      2317038.16     13217162.29      2317470.19     13215404.29
      2317239.56     13214106.73
#Sta/Elev= 30
  3189.7  139.57  3334.4  130.32  3360.1  129.83    3376  126.18  3411.5  123.91
  3464.2  122.11  3500.6  118.56  3657.4  110.75  3689.6  107.92  3713.5  108.83
  3720.5   107.2  3758.4  104.43  3988.2   93.24  4016.1   91.21  4018.8   90.71
  4022.1   91.21  4061.4   91.21  4169.9   91.21    5942   91.21  5979.4    92.6
 5985.59   93.25  6011.1   97.41  6043.5   99.45  6080.3  104.23  6104.5  106.44
  6165.4  114.95  6195.9  116.95    6267  126.59  6287.3   128.6  6317.9  129.27
#Mann= 9 ,-1 , 0
  3189.7      .1       0  3657.4     .08       0  3758.4     .05       0
  4016.1    .033       0  4022.1     .05       0  4061.4     .07       0
  4169.9     .05       0  5979.4     .08       0  6080.3      .1       0
Bank Sta=3988.2,5985.59
XS Rating Curve= 0 ,0
Exp/Cntr=0.3,0.1

Type RM Length L Ch R = 1 ,5668    ,581,581,581
BEGIN DESCRIPTION:
UNT018 IN PECR 11.0
END DESCRIPTION:
XS GIS Cut Line= 3
      2317637.72     13217096.88      2317937.72     13215296.85
      2317837.72     13214496.84
#Sta/Elev= 30
  3201.2   137.5  3209.3  137.49  3322.9  132.83  3479.1  122.42  3505.3  120.72
  3538.3   118.4  3545.9  115.14  3578.8  115.87    3627  111.47  3678.5  111.18
  3728.4  111.27  3758.8  102.98  3877.8   95.54  3910.9   92.96  3928.2   91.21
  3930.9   90.71  3934.2   91.21  3977.5   91.21    4112   91.21  5641.4   91.21
 5709.57   93.19  5731.5   95.17  5741.6    98.4  5751.7  110.22  5761.7   115.7
  5773.8  119.03  5781.9  120.38  5789.4  125.09  5794.5  123.66  5832.3  125.98
#Mann= 13 ,-1 , 0
  3201.2      .1       0  3209.3     .05       0  3479.1      .1       0
  3505.3     .05       0  3578.8      .1       0  3678.5     .05       0
  3877.8     .12       0  3928.2    .033       0  3934.2     .12       0
  3977.5     .07       0    4112     .05       0  5641.4     .07       0
  5773.8     .08       0
Bank Sta=3910.9,5709.57
XS Rating Curve= 0 ,0
Exp/Cntr=0.3,0.1

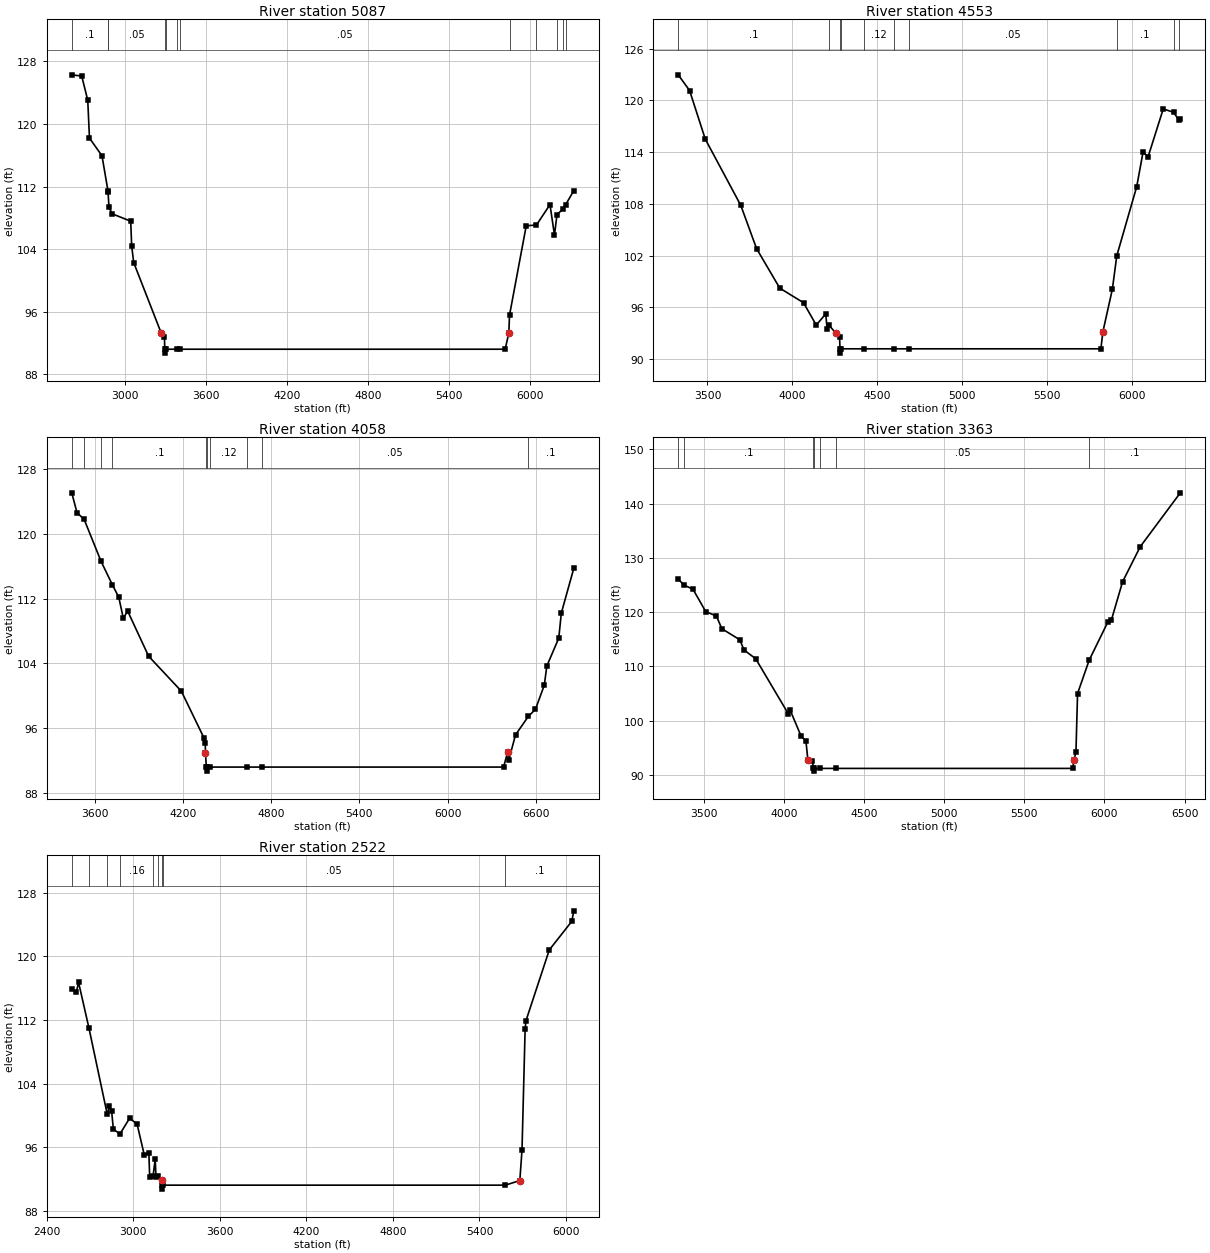
Type RM Length L Ch R = 1 ,5087    ,534,534,534
BEGIN DESCRIPTION:
UNT018 IN PECR 10.0
END DESCRIPTION:
XS GIS Cut Line= 3
      2317960.55     13217374.64      2318565.23     13216029.91
      2318348.67     13213801.23
#Sta/Elev= 30
  2609.2  126.29  2682.8  126.13  2727.4  123.04  2740.1   118.2  2832.7  115.94
  2876.8  111.47  2877.4  111.36  2884.5  109.36  2907.7  108.52  3045.3  107.58
  3052.1  104.45  3067.3  102.29  3271.5   93.24  3294.6   92.81  3297.1   91.21
  3299.9   90.71  3303.1   91.21  3389.4   91.21  3408.3   91.21  5814.8   91.21
  5841.7   93.28    5847   95.56  5970.6  106.99  6046.2  107.09  6146.3   109.7
  6179.5   105.8    6198  108.42  6245.3  109.18  6261.2  109.67  6322.8  111.49
#Mann= 12 ,-1 , 0
  2609.2      .1       0  2876.8     .08       0  2877.4     .05       0
  3297.1    .033       0  3303.1     .05       0  3389.4     .12       0
  3408.3     .05       0    5847      .1       0  6046.2     .08       0
    6198     .05       0  6245.3     .08       0  6261.2     .05       0
Bank Sta=3271.5,5841.7
XS Rating Curve= 0 ,0
Exp/Cntr=0.3,0.1

Type RM Length L Ch R = 1 ,4553    ,495,495,495
BEGIN DESCRIPTION:
UNT018 IN PECR 9.0
END DESCRIPTION:
XS GIS Cut Line= 3
      2319567.02     13216580.42      2318944.29     13214856.63
      2318456.93      13213845.8
#Sta/Elev= 30
  3327.8  122.96  3394.7  121.14  3486.7  115.52    3696  107.83  3788.8  102.82
  3925.4   98.24  4065.2   96.55    4140   93.96  4196.1   95.26  4203.5   93.56
    4216   93.93 4253.94   93.05  4277.4   92.59  4279.7   91.21  4282.5   90.71
  4285.7   91.21  4418.8   91.21  4600.4   91.21    4686   91.21  5815.4   91.21
 5826.85   93.16  5882.8   98.11  5908.9  101.99  6026.3  110.01  6063.7  114.03
  6092.9  113.44  6182.3  119.01  6242.8  118.62  6273.5  117.75  6282.8  117.79
#Mann= 10 ,-1 , 0
  3327.8      .1       0    4216     .16       0  4279.7    .033       0
  4285.7     .16       0  4418.8     .12       0  4600.4     .07       0
    4686     .05       0  5908.9      .1       0  6242.8     .08       0
  6273.5     .05       0
Bank Sta=4253.94,5826.85
XS Rating Curve= 0 ,0
Exp/Cntr=0.3,0.1

Type RM Length L Ch R = 1 ,4058    ,695,695,695
BEGIN DESCRIPTION:
UNT018 IN PECR 8.0
END DESCRIPTION:
XS GIS Cut Line= 2
      2319747.53     13216472.11      2319178.94     13213105.69
#Sta/Elev= 30
    3444  125.05  3479.8  122.59    3528  121.78    3643   116.6  3719.6  113.72
  3763.7  112.16  3794.1   109.6  3824.6  110.44  3966.6  104.89    4189  100.58
  4341.8   94.85  4351.9   94.15 4353.09   92.98  4359.1   91.21  4361.8   90.71
  4365.1   91.21  4383.3   91.21  4635.8   91.21  4736.5   91.21  6380.3   91.21
 6407.17   93.01  6415.4   92.06  6461.4   95.18  6549.3   97.48  6596.8   98.33
  6657.2  101.32  6674.4  103.68  6755.5  107.12    6773  110.22  6858.1  115.76
#Mann= 10 ,-1 , 0
    3444     .16       0    3528      .1       0    3643     .16       0
  3719.6      .1       0  4359.1    .033       0  4365.1      .1       0
  4383.3     .12       0  4635.8     .07       0  4736.5     .05       0
  6549.3      .1       0
Bank Sta=4353.09,6407.17
XS Rating Curve= 0 ,0
Exp/Cntr=0.3,0.1

Type RM Length L Ch R = 1 ,3363    ,841,841,841
BEGIN DESCRIPTION:
UNT018 IN PECR 6.0
END DESCRIPTION:
XS GIS Cut Line= 3
      2319928.04     13216472.14      2320081.47     13215930.64
      2320298.08      13213367.5
#Sta/Elev= 30
  3338.3  126.07  3375.9  124.97  3430.5  124.21  3510.1   120.1  3576.6  119.29
  3610.5  116.95  3722.7  114.91  3749.1  113.02  3821.9  111.42  4025.3  101.29
  4037.6  101.91  4105.6   97.15  4135.7   96.25 4148.19   92.68  4175.9    92.5
  4182.9   91.21  4185.7   90.71  4188.9   91.21    4223   91.21  4321.9   91.21
  5801.7   91.21 5808.52   92.74  5821.7   94.16  5831.8  105.01  5904.5  111.16
  6022.4  118.27  6042.5  118.49  6112.8  125.59  6223.2  132.06  6473.4  141.98
#Mann= 7 ,-1 , 0
  3338.3     .16       0  3375.9      .1       0  4182.9    .033       0
  4188.9      .1       0    4223     .07       0  4321.9     .05       0
  5904.5      .1       0
Bank Sta=4148.19,5808.52
XS Rating Curve= 0 ,0
Exp/Cntr=0.3,0.1

Type RM Length L Ch R = 1 ,2522    ,0,0,0
BEGIN DESCRIPTION:
UNT018 IN PECR 1.0
END DESCRIPTION:
XS GIS Cut Line= 4
      2320168.53      13216800.1      2320887.12     13215459.14
      2320991.29      13214139.7       2320678.8     13213584.17
#Sta/Elev= 30
  2572.4  115.86  2603.4  115.46  2619.7  116.72  2691.3     111  2818.5  100.13
  2833.3  101.12  2848.4  100.59  2860.9   98.26  2906.5   97.65  2973.2   99.62
    3025   98.93  3075.3   95.01  3107.1    95.3  3112.8    92.2  3135.9   92.33
    3151   94.45  3156.6   92.23  3170.9   92.31  3197.3   91.81  3197.5   91.21
  3200.2   90.71  3203.5   91.21  5579.6   91.21    5680   91.79  5695.1   95.62
  5716.8  110.86  5722.5   111.9  5884.4  120.82  6040.1  124.41  6054.7  125.74
#Mann= 9 ,-1 , 0
  2572.4      .1       0  2691.3     .16       0  2818.5      .1       0
  2906.5     .16       0  3135.9      .1       0  3170.9     .05       0
  3197.5    .033       0  3203.5     .05       0  5579.6      .1       0
Bank Sta=3197.3,5680
XS Rating Curve= 0 ,0
Exp/Cntr=0.3,0.1

Chan Stop Cuts=-1
Use User Specified Reach Order=0
Composite Channel Slope=5