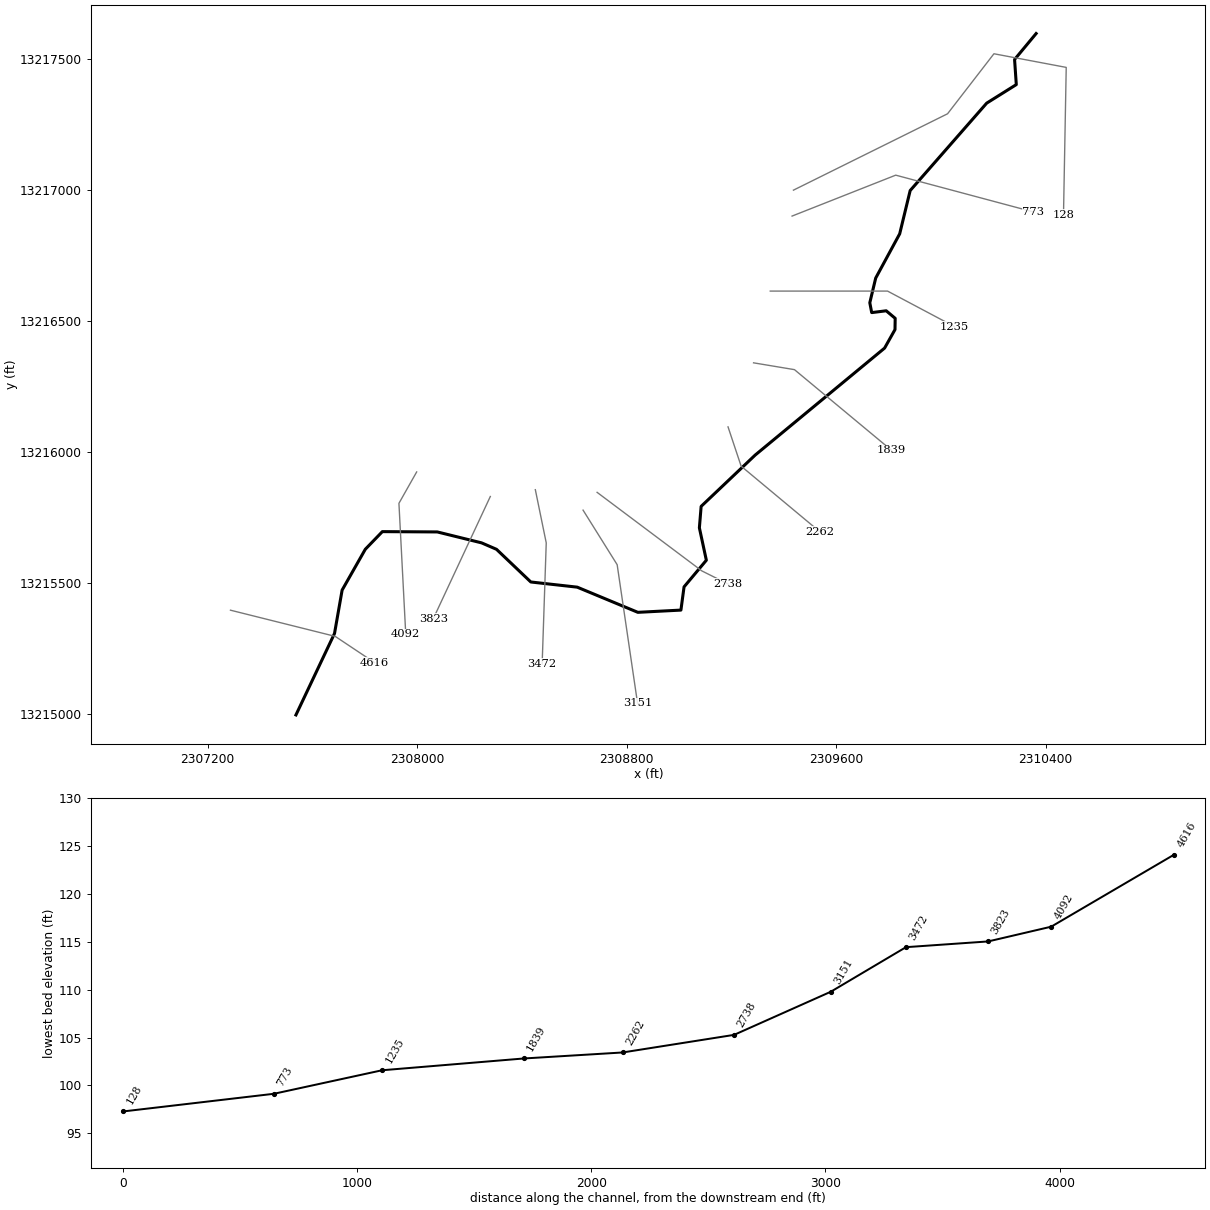
--- UNT019 IN PECR.prj (project) ---

Proj Title=UNT019 IN PECR Base Level Engineering
Current Plan=p01
Default Exp/Contr=0.3,0.1
English Units
Geom File=g01
Flow File=f01
Plan File=p01
Y Axis Title=Elevation
X Axis Title(PF)=Main Channel Distance
X Axis Title(XS)=Station
BEGIN DESCRIPTION:
UNT019 IN PECR
END DESCRIPTION:
DSS Export Rating Curves= 0
DSS Export Rating Curve Sorted= 0
DSS Export Volume Flow Curves= 0
DXF OffsetX= 0
DXF OffsetY= 0
DXF ScaleX= 1
DXF ScaleY= 10

--- UNT019 IN PECR.p01 (plan) ---

Plan Title=Multiple Run
Short Identifier=Multiple
Geom File=g01
Flow File=f01
Subcritical Flow
K Sum by GR= 0
Std Step Tol= 0.01
Critical Tol= 0.01
Num of Std Step Trials= 20
Max Error Tol= 0.3
Flow Tol Ratio= 0.001
Split Flow NTrial= 30
Split Flow Tol= 0.02
Split Flow Ratio= 0.02
Log Output Level= 0
Friction Slope Method= 1
Unsteady Friction Slope Method= 2
Unsteady Bridges Friction Slope Method= 1
Parabolic Critical Depth
Global Vel Dist=  1 , 1 , 1
Global Log Level= 0
CheckData=True
Encroach Param= -1, 0, 0, 0
BEGIN DESCRIPTION:
Multiple Run
END DESCRIPTION:

--- UNT019 IN PECR.f01 (steady flow) ---

Flow Title=Multiple
Program Version=4.10
Number of Profiles= 7
Profile Names=10-year,25-year,50-year,1pct_min,100-year,1pct_plu,500-year
River Rch & RM=UNT019 IN PECR,Reach-1         ,4616
     696     986    1229    1118    1512    2044    2297
Boundary for River Rch & Prof#=UNT019 IN PECR,Reach-1         , 1
Up Type= 0
Dn Type= 3
Dn Slope=0.005
Boundary for River Rch & Prof#=UNT019 IN PECR,Reach-1         , 2
Up Type= 0
Dn Type= 3
Dn Slope=0.005
Boundary for River Rch & Prof#=UNT019 IN PECR,Reach-1         , 3
Up Type= 0
Dn Type= 3
Dn Slope=0.005
Boundary for River Rch & Prof#=UNT019 IN PECR,Reach-1         , 4
Up Type= 0
Dn Type= 3
Dn Slope=0.005
Boundary for River Rch & Prof#=UNT019 IN PECR,Reach-1         , 5
Up Type= 0
Dn Type= 3
Dn Slope=0.005
Boundary for River Rch & Prof#=UNT019 IN PECR,Reach-1         , 6
Up Type= 0
Dn Type= 3
Dn Slope=0.005
Boundary for River Rch & Prof#=UNT019 IN PECR,Reach-1         , 7
Up Type= 0
Dn Type= 3
Dn Slope=0.005
DSS Import GetInterval= 0
DSS Import GetPeak= 0
DSS Import FillOption= 0

--- UNT019 IN PECR.g01 (geometry) ---

Geom Title=Existing Conditions
Program Version=4.10

River Reach=UNT019 IN PECR  ,Reach-1
Reach XY= 30
      2307537.72     13214996.85      2307685.03     13215307.97
      2307714.07     13215473.58      2307802.66     13215629.59
      2307867.72     13215696.85      2308077.53     13215695.68
      2308246.56     13215653.97      2308303.69     13215629.27
      2308434.55     13215504.57      2308611.77     13215484.82
      2308843.33     13215388.67      2309007.83     13215397.22
      2309019.76     13215485.89       2309104.9     13215587.64
       2309078.3     13215711.45      2309085.02     13215793.28
      2309291.39     13215989.21      2309785.56      13216397.7
      2309825.29      13216468.4      2309826.01     13216511.38
      2309791.72     13216540.15      2309736.34     13216533.22
      2309729.07     13216570.86      2309751.65     13216665.21
      2309843.19     13216834.02      2309883.25     13216999.28
      2310175.42     13217333.09      2310288.47     13217403.87
      2310281.92     13217499.75      2310364.22     13217598.89

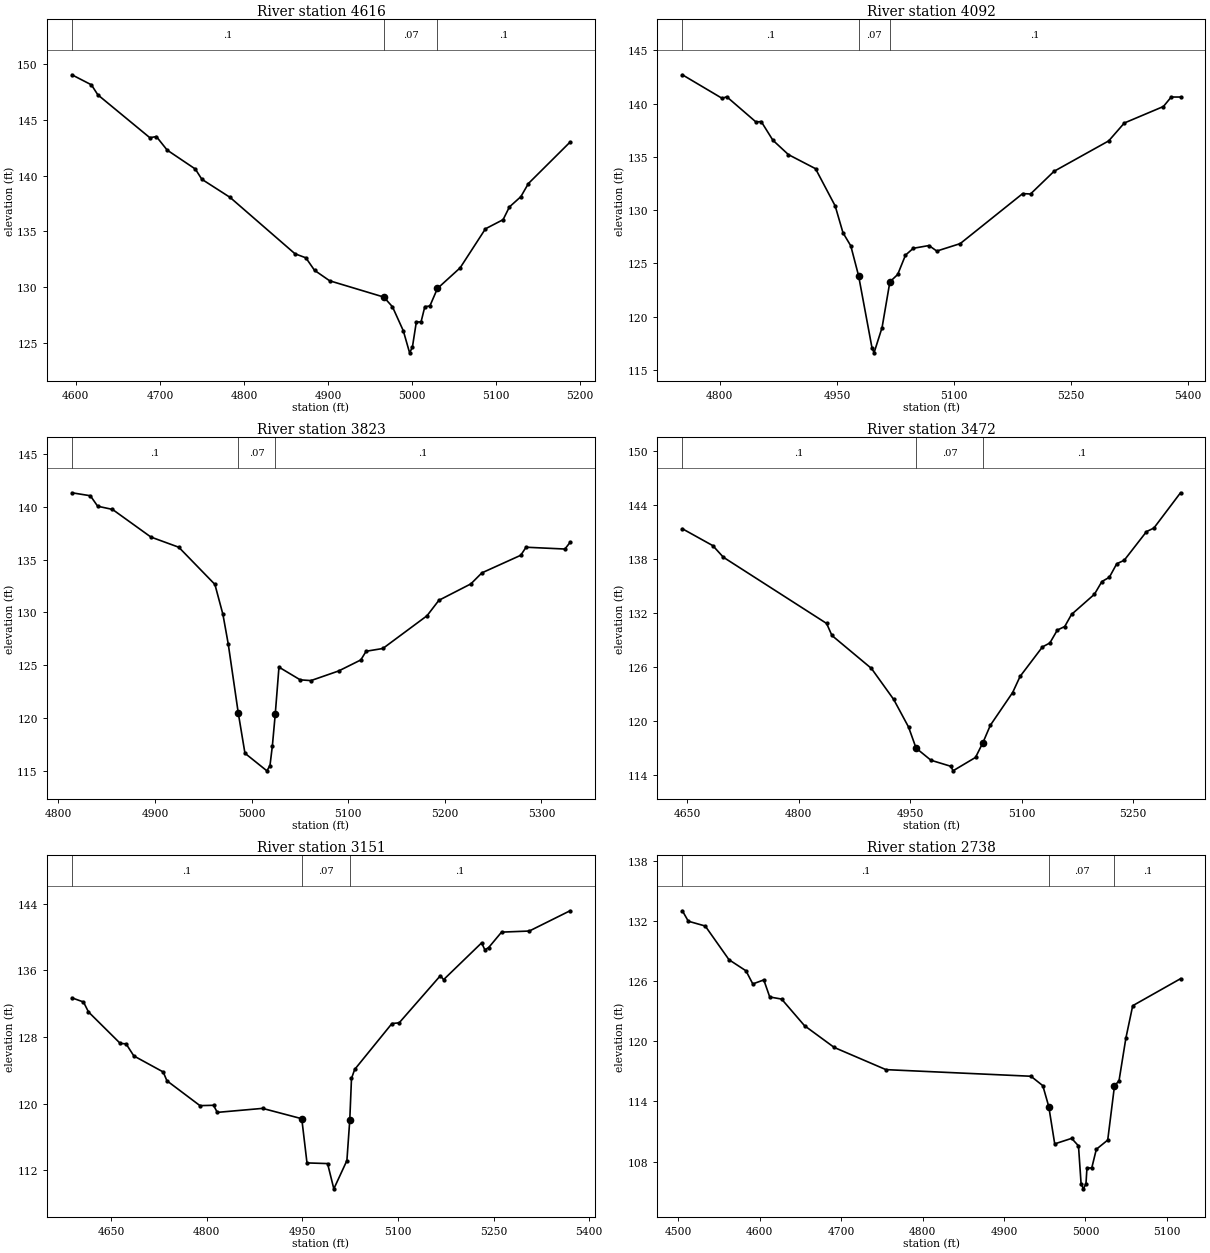
Type RM Length L Ch R = 1 ,4616    ,524,524,524
BEGIN DESCRIPTION:
UNT019 IN PECR 9.0
END DESCRIPTION:
XS GIS Cut Line= 3
      2307287.76     13215396.85      2307687.72     13215296.85
      2307837.68     13215196.88
#Sta/Elev= 30
  4595.3  149.04  4618.5  148.14  4626.2  147.24    4688   143.4  4695.8   143.5
  4708.6  142.29  4742.1  140.59  4749.9  139.67  4783.4  138.05  4860.7  132.99
  4873.6  132.63  4883.9  131.51  4901.9  130.57  4966.3  129.11  4976.6  128.24
  4989.5  126.09    4997  124.11  5000.3  124.61    5005  126.88  5010.6  126.88
  5015.1  128.25  5021.1  128.31  5030.1  129.88  5057.1  131.73  5087.2  135.23
  5108.2  136.05  5115.7  137.19  5129.3  138.11  5138.3  139.29  5187.8     143
#Mann= 3 , 0 , 0
  4595.3      .1       0  4966.3     .07       0  5030.1      .1       0
Bank Sta=4966.3,5030.1
XS Rating Curve= 0 ,0
Exp/Cntr=0.3,0.1

Type RM Length L Ch R = 1 ,4092    ,269,269,269
BEGIN DESCRIPTION:
UNT019 IN PECR 8.0
END DESCRIPTION:
XS GIS Cut Line= 3
      2307998.72     13215924.76      2307931.02     13215804.97
      2307957.06     13215304.94
#Sta/Elev= 30
    4752  142.71  4803.1  140.49  4808.8  140.65  4846.4  138.27    4853  138.32
    4868  136.56  4887.9  135.21  4922.6  133.89  4947.8  130.39  4957.8  127.87
  4967.8  126.64  4977.8  123.83  4994.9  117.09  4997.6  116.59  5007.9  118.97
  5017.9  123.26  5027.9  123.95  5037.9  125.77  5047.9  126.41    5068  126.67
    5078  126.15    5108  126.85  5188.1  131.55  5198.1  131.51  5228.2  133.64
  5298.3   136.5  5318.3  138.18  5368.4  139.73  5378.4  140.62  5390.3  140.62
#Mann= 3 , 0 , 0
    4752      .1       0  4977.8     .07       0  5017.9      .1       0
Bank Sta=4977.8,5017.9
XS Rating Curve= 0 ,0
Exp/Cntr=0.3,0.1

Type RM Length L Ch R = 1 ,3823    ,351,351,351
BEGIN DESCRIPTION:
UNT019 IN PECR 7.0
END DESCRIPTION:
XS GIS Cut Line= 2
      2308279.97     13215831.01      2308061.97     13215363.87
#Sta/Elev= 30
  4814.1   141.3  4833.2  141.02  4840.8  140.03  4856.1  139.73  4895.9  137.12
  4924.7  136.16  4962.1  132.65  4970.4  129.82  4975.9  127.03 4986.25  120.53
  4993.2  116.71  5015.9  115.05  5019.1  115.55  5021.6  117.43 5024.58  120.43
  5028.4  124.84  5050.4  123.64  5061.5  123.57  5090.2  124.48  5113.1  125.52
  5118.6  126.34  5135.9   126.6  5181.6  129.69  5193.9  131.15    5227   132.7
  5238.4  133.74  5278.6   135.4  5284.1  136.16  5324.3  135.99  5329.6  136.61
#Mann= 3 , 0 , 0
  4814.1      .1       0 4986.25     .07       0 5024.58      .1       0
Bank Sta=4986.25,5024.58
XS Rating Curve= 0 ,0
Exp/Cntr=0.3,0.1

Type RM Length L Ch R = 1 ,3472    ,321,321,321
BEGIN DESCRIPTION:
Mapping XS 78d479ad
END DESCRIPTION:
XS GIS Cut Line= 3
      2308451.86     13215857.02      2308493.52     13215653.93
      2308477.91     13215191.11
#Sta/Elev= 30
  4643.3  141.37  4684.3  139.49  4698.5   138.2  4837.4  130.84  4844.6   129.5
  4897.7  125.84  4927.7  122.39  4947.7  119.32  4957.8  116.98  4977.8  115.63
  5004.8  114.95  5007.5  114.45  5037.8  115.94  5047.8  117.59  5057.8  119.52
  5087.8  123.16  5097.8  124.95  5127.9  128.23  5137.9  128.67  5147.9   130.1
  5157.9   130.5    5167  131.84  5197.9  134.09  5207.9   135.5  5217.9  135.97
  5227.9  137.48  5237.9  137.86  5267.9  141.05  5277.9  141.45  5313.7  145.37
#Mann= 3 , 0 , 0
  4643.3      .1       0  4957.8     .07       0  5047.8      .1       0
Bank Sta=4957.8,5047.8
XS Rating Curve= 0 ,0
Exp/Cntr=0.3,0.1

Type RM Length L Ch R = 1 ,3151    ,413,413,413
BEGIN DESCRIPTION:
UNT019 IN PECR 6.0
END DESCRIPTION:
XS GIS Cut Line= 3
      2308634.14     13215778.92      2308764.35      13215570.6
      2308842.29     13215040.57
#Sta/Elev= 30
  4588.4   132.7  4606.6   132.2  4614.4  131.01  4664.3  127.23  4673.4  127.18
  4685.6  125.73  4731.6  123.81  4737.5  122.75  4789.3  119.77  4810.6  119.81
  4816.5  118.96  4887.5  119.44    4949   118.2  4957.2   112.9  4989.5  112.82
  4999.3  109.79  5019.8  113.18 5024.31  118.05    5027  123.03    5032  124.11
  5090.5  129.62  5101.8   129.7  5166.4  135.35  5171.5  134.88  5231.1  139.29
  5236.2  138.46  5242.2  138.73  5262.4  140.58  5305.9  140.71  5369.8  143.14
#Mann= 3 , 0 , 0
  4588.4      .1       0    4949     .07       0 5024.31      .1       0
Bank Sta=4949,5024.31
XS Rating Curve= 0 ,0
Exp/Cntr=0.3,0.1

Type RM Length L Ch R = 1 ,2738    ,476,476,476
BEGIN DESCRIPTION:
UNT019 IN PECR 5.0
END DESCRIPTION:
XS GIS Cut Line= 3
      2308687.72     13215846.86      2309087.72     13215546.85
      2309187.72     13215496.86
#Sta/Elev= 30
    4505  132.99  4512.3  131.95  4533.1  131.47  4562.3  128.11  4583.1  127.01
  4591.5   125.7    4605   126.1  4612.3   124.4  4626.9  124.19    4655  121.54
  4691.5  119.37    4755  117.16  4933.1   116.5  4947.7  115.56    4955  113.48
  4962.3  109.76  4983.1  110.31  4991.5  109.56  4994.7  105.78  4997.5  105.28
  5000.7  105.78  5001.9  107.36  5007.8  107.36  5013.4  109.22  5027.4  110.14
  5035.7  115.53  5041.3  116.06  5049.7   120.3  5058.1  123.53  5116.8  126.22
#Mann= 3 , 0 , 0
    4505      .1       0    4955     .07       0  5035.7      .1       0
Bank Sta=4955,5035.7
XS Rating Curve= 0 ,0
Exp/Cntr=0.3,0.1

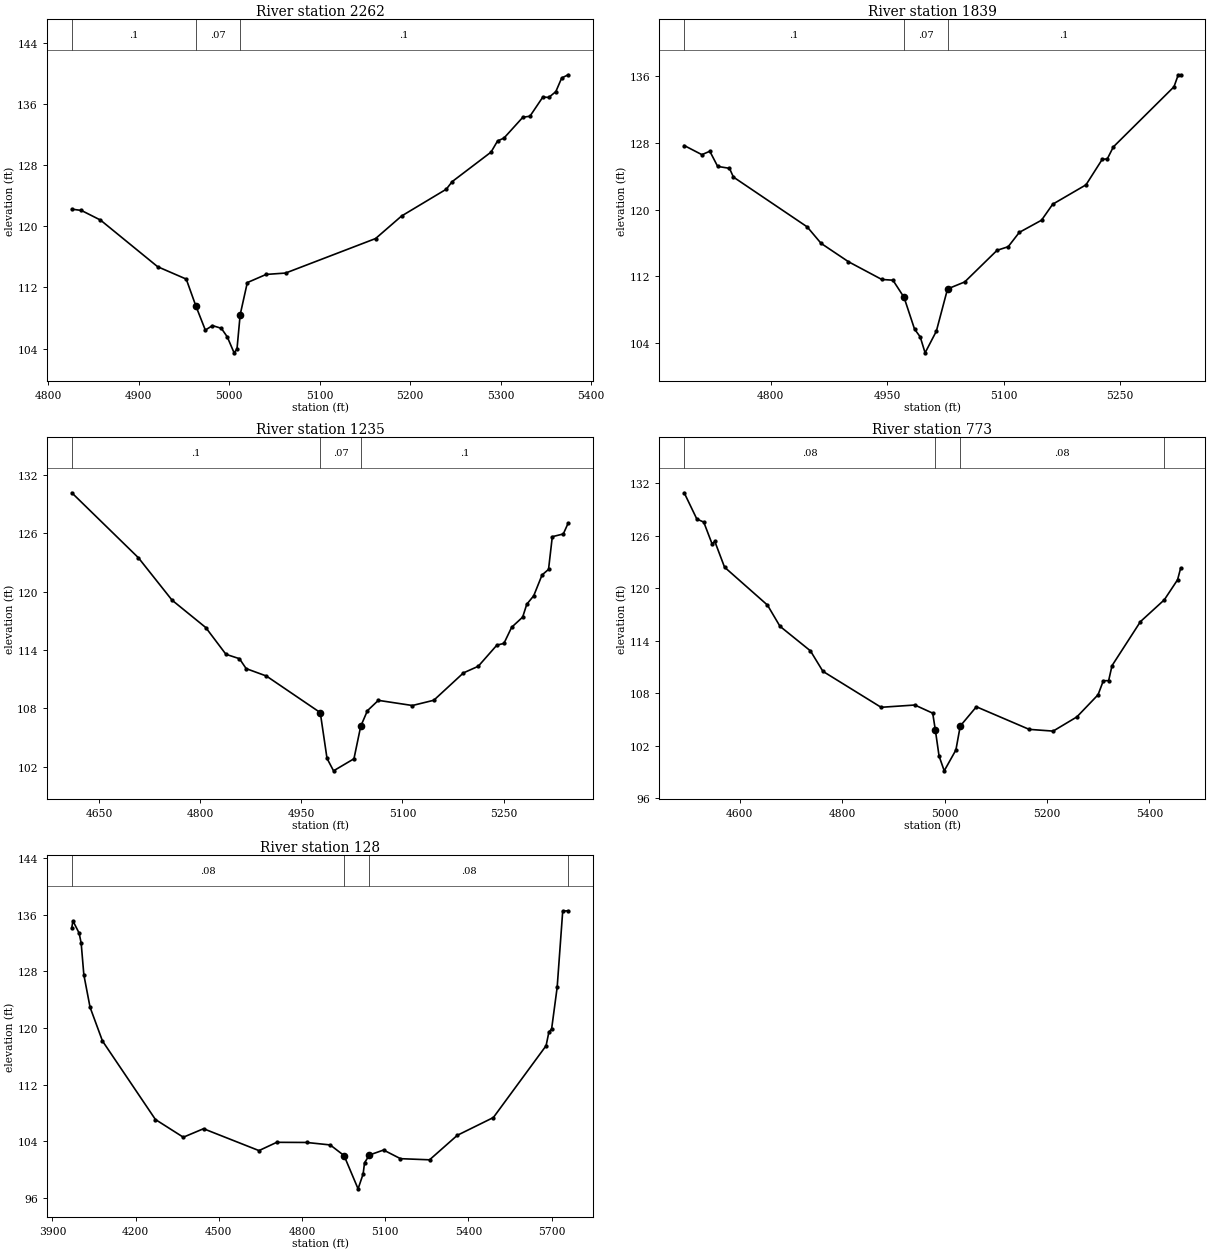
Type RM Length L Ch R = 1 ,2262    ,423,423,423
BEGIN DESCRIPTION:
UNT019 IN PECR 4.0
END DESCRIPTION:
XS GIS Cut Line= 3
       2309187.7      13216096.9      2309237.72     13215946.85
      2309537.74     13215696.84
#Sta/Elev= 30
  4825.9  122.26  4836.5  122.09  4857.6  120.83  4920.8  114.72  4952.4   113.1
    4963  109.59  4973.5  106.42  4981.4  107.01  4991.2  106.65  4997.7  105.54
  5005.3  103.44  5008.5  103.94    5012  108.43  5019.9  112.64  5040.7  113.71
  5062.2  113.89  5161.7  118.41  5190.4  121.36  5239.8  124.87  5246.4  125.87
  5289.3  129.73  5296.5  131.19  5303.6  131.57  5324.5   134.3  5332.3  134.43
  5346.6  136.95  5353.1  136.89  5360.9  137.65  5367.4  139.44  5374.6  139.86
#Mann= 3 , 0 , 0
  4825.9      .1       0    4963     .07       0    5012      .1       0
Bank Sta=4963,5012
XS Rating Curve= 0 ,0
Exp/Cntr=0.3,0.1

Type RM Length L Ch R = 1 ,1839    ,604,604,604
BEGIN DESCRIPTION:
UNT019 IN PECR 3.0
END DESCRIPTION:
XS GIS Cut Line= 3
      2309285.21     13216341.43      2309441.43     13216315.39
      2309811.23     13216008.09
#Sta/Elev= 30
  4688.5   127.7  4711.3   126.6  4721.5  127.01  4731.6  125.19  4746.8  124.96
  4751.9  123.91  4846.9  117.93  4864.8  115.95    4900  113.75  4942.9  111.62
  4957.3  111.53  4971.6  109.47  4985.1  105.66  4992.4  104.73  4998.7  102.81
  5013.2  105.41  5027.6  110.48  5049.7  111.32  5091.4  115.12  5105.7  115.55
    5120  117.27  5148.6  118.73    5163  120.65  5205.9  122.98  5226.8  126.04
  5233.3  126.09  5241.1  127.53  5319.2  134.75  5324.7  136.19  5327.7  136.19
#Mann= 3 , 0 , 0
  4688.5      .1       0  4971.6     .07       0  5027.6      .1       0
Bank Sta=4971.6,5027.6
XS Rating Curve= 0 ,0
Exp/Cntr=0.3,0.1

Type RM Length L Ch R = 1 ,1235    ,462,462,462
BEGIN DESCRIPTION:
Mapping XS 3596026d
END DESCRIPTION:
XS GIS Cut Line= 3
      2309348.92     13216615.39      2309796.85     13216615.39
      2310052.03     13216479.99
#Sta/Elev= 30
  4609.2  130.14    4708  123.47    4758  119.11    4808   116.3    4838  113.55
    4858   113.1    4868  112.08    4898  111.32    4978  107.56    4988  102.86
  4997.7  101.58    5028  102.82    5038  106.15    5048  107.76  5064.2  108.82
  5114.7  108.29  5146.5  108.83  5190.5  111.64  5212.5  112.32  5240.1  114.49
  5250.6  114.67  5262.1  116.33  5278.4  117.37  5284.5  118.69  5294.8  119.56
  5307.2   121.7  5316.8  122.27  5322.4  125.63  5338.7  125.91    5346  127.03
#Mann= 3 , 0 , 0
  4609.2      .1       0    4978     .07       0    5038      .1       0
Bank Sta=4978,5038
XS Rating Curve= 0 ,0
Exp/Cntr=0.3,0.1

Type RM Length L Ch R = 1 ,773     ,645,645,645
BEGIN DESCRIPTION:
UNT019 IN PECR 2.0
END DESCRIPTION:
XS GIS Cut Line= 3
      2309432.23     13216901.84       2309828.1      13217058.1
      2310353.45     13216917.66
#Sta/Elev= 30
  4491.4  130.89  4516.1  127.89  4529.6  127.54  4545.8  125.06  4551.2  125.33
  4570.2  122.39    4654  118.06  4678.4  115.64  4737.9  112.83  4762.3  110.49
  4875.9  106.38  4941.8  106.64  4976.7  105.71  4981.9  103.77  4989.1  100.82
  4999.2   99.12    5022   101.5  5030.5  104.24    5062  106.44    5165  103.86
  5211.9  103.66  5258.2  105.28  5299.6  107.81  5309.9  109.41  5320.3  109.43
  5326.9  111.14  5382.4  116.17    5429  118.66  5454.9  120.95  5460.8  122.26
#Mann= 4 ,-1 , 0
  4491.4     .08       0  4981.9     .05       0  5030.5     .08       0
    5429     .08       0
Bank Sta=4981.9,5030.5
XS Rating Curve= 0 ,0
Exp/Cntr=0.3,0.1

Type RM Length L Ch R = 1 ,128     ,0,0,0
BEGIN DESCRIPTION:
UNT019 IN PECR 1.0
END DESCRIPTION:
XS GIS Cut Line= 5
      2309437.46      13217000.8      2310026.01     13217292.48
       2310203.1     13217521.64      2310479.14     13217469.56
      2310468.72     13216907.04
#Sta/Elev= 30
    3970  134.16  3974.1  135.11  3996.5  133.38  4003.8  131.97  4013.4  127.51
  4035.8  122.92  4080.6  118.15  4271.6  107.06  4372.1  104.56    4445  105.76
    4645  102.67  4708.9  103.84  4816.7  103.82  4901.8  103.47  4951.7  101.97
  5002.3   97.27  5020.5   99.37  5025.6  100.95  5043.3  102.05  5094.2  102.75
  5155.2  101.53  5260.1  101.37  5360.1  104.83  5490.1  107.34  5680.2  117.48
  5690.2  119.38  5700.2  119.85  5720.2  125.73  5740.2   136.5    5760  136.54
#Mann= 4 ,-1 , 0
    3970     .08       0  4951.7     .05       0  5043.3     .08       0
    5760      .1       0
Bank Sta=4951.7,5043.3
XS Rating Curve= 0 ,0
Exp/Cntr=0.3,0.1

Chan Stop Cuts=-1
Use User Specified Reach Order=0
Composite Channel Slope=5