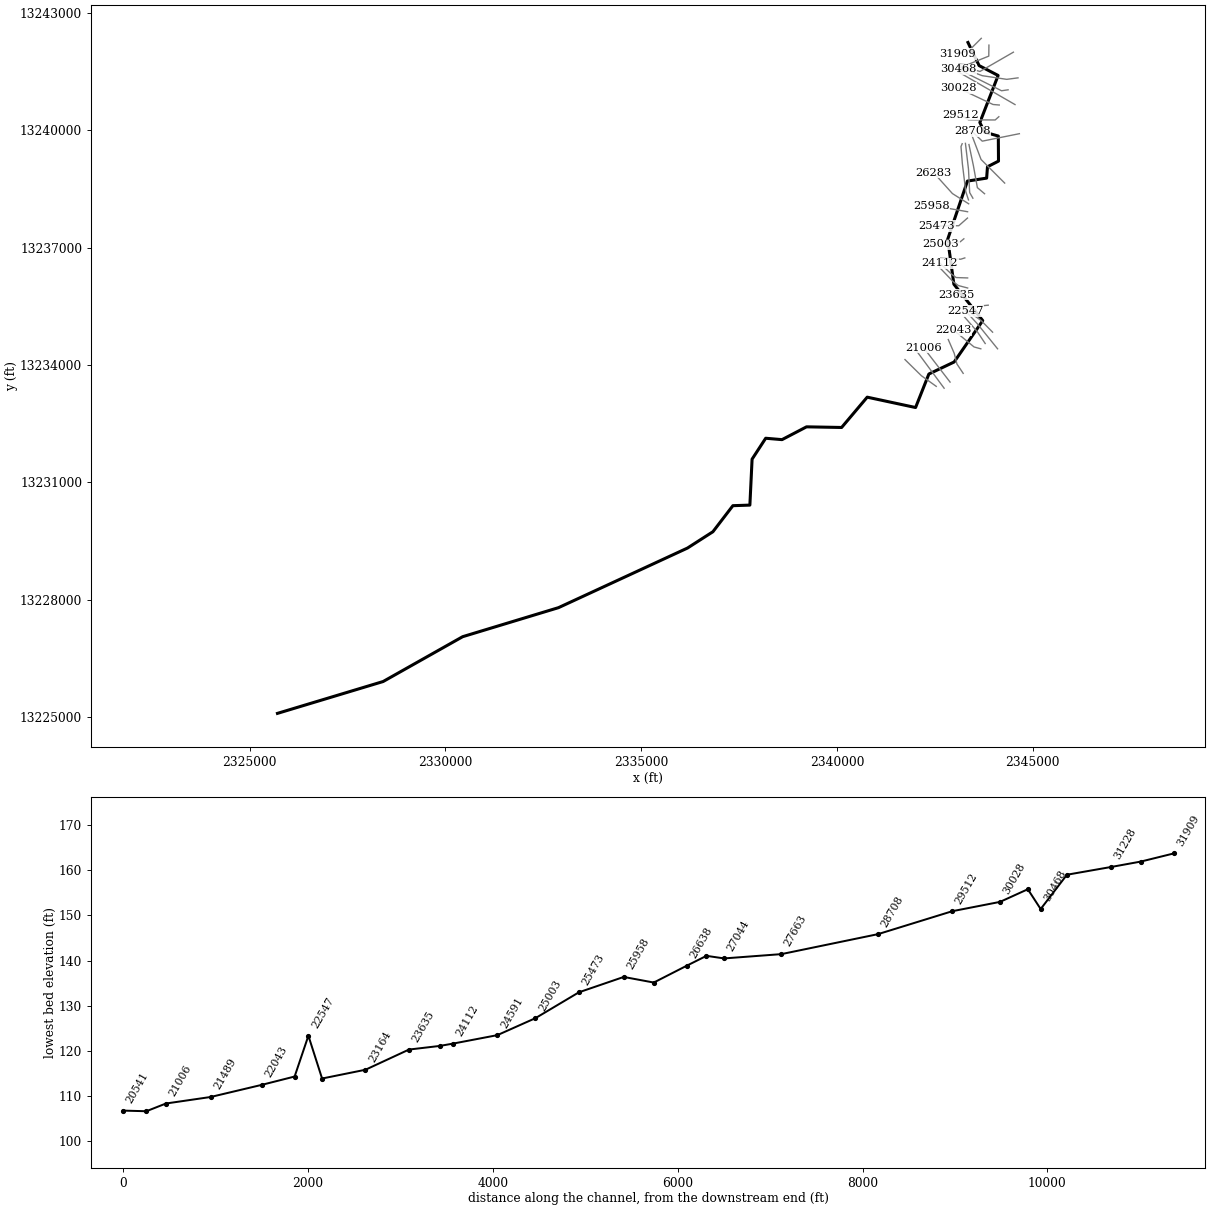
--- UNT020 IN PECR.prj (project) ---

Proj Title=UNT020 IN PECR Base Level Engineering
Current Plan=p01
Default Exp/Contr=0.3,0.1
English Units
Geom File=g01
Flow File=f01
Plan File=p01
Y Axis Title=Elevation
X Axis Title(PF)=Main Channel Distance
X Axis Title(XS)=Station
BEGIN DESCRIPTION:
UNT020 IN PECR
END DESCRIPTION:
DSS Export Rating Curves= 0
DSS Export Rating Curve Sorted= 0
DSS Export Volume Flow Curves= 0
DXF OffsetX= 0
DXF OffsetY= 0
DXF ScaleX= 1
DXF ScaleY= 10

--- UNT020 IN PECR.p01 (plan) ---

Plan Title=Multiple Run
Short Identifier=Multiple
Geom File=g01
Flow File=f01
Subcritical Flow
K Sum by GR= 0
Std Step Tol= 0.01
Critical Tol= 0.01
Num of Std Step Trials= 20
Max Error Tol= 0.3
Flow Tol Ratio= 0.001
Split Flow NTrial= 30
Split Flow Tol= 0.02
Split Flow Ratio= 0.02
Log Output Level= 0
Friction Slope Method= 1
Unsteady Friction Slope Method= 2
Unsteady Bridges Friction Slope Method= 1
Parabolic Critical Depth
Global Vel Dist=  1 , 1 , 1
Global Log Level= 0
CheckData=True
Encroach Param= -1, 0, 0, 0
BEGIN DESCRIPTION:
Multiple Run
END DESCRIPTION:

--- UNT020 IN PECR.f01 (steady flow) ---

Flow Title=Multiple
Program Version=4.10
Number of Profiles= 7
Profile Names=10-year,25-year,50-year,1pct_min,100-year,1pct_plu,500-year
River Rch & RM=UNT020 IN PECR,Reach-1         ,31909
     601     834    1025     920    1244    1682    1837
River Rch & RM=UNT020 IN PECR,Reach-1         ,31228
     753    1058    1311    1185    1602    2167    2402
River Rch & RM=UNT020 IN PECR,Reach-1         ,26638
     966    1376    1720    1567    2119    2866    3230
River Rch & RM=UNT020 IN PECR,Reach-1         ,23967
    1245    1799    2272    2090    2826    3822    4390
River Rch & RM=UNT020 IN PECR,Reach-1         ,22695
    1434    2083    2640    2435    3294    4454    5147
River Rch & RM=UNT020 IN PECR,Reach-1         ,19459
    2000    2946    3771    3508    4744    6416    7544
River Rch & RM=UNT020 IN PECR,Reach-1         ,15813
    1998    2942    3764    3500    4733    6401    7518
River Rch & RM=UNT020 IN PECR,Reach-1         ,15034
    2164    3186    4074    3785    5119    6923    8118
River Rch & RM=UNT020 IN PECR,Reach-1         ,9775
    2831    4202    5402    5042    6818    9221   10911
Boundary for River Rch & Prof#=UNT020 IN PECR,Reach-1         , 1
Up Type= 0
Dn Type= 3
Dn Slope=0.0001
Boundary for River Rch & Prof#=UNT020 IN PECR,Reach-1         , 2
Up Type= 0
Dn Type= 3
Dn Slope=0.0001
Boundary for River Rch & Prof#=UNT020 IN PECR,Reach-1         , 3
Up Type= 0
Dn Type= 3
Dn Slope=0.0001
Boundary for River Rch & Prof#=UNT020 IN PECR,Reach-1         , 4
Up Type= 0
Dn Type= 3
Dn Slope=0.0001
Boundary for River Rch & Prof#=UNT020 IN PECR,Reach-1         , 5
Up Type= 0
Dn Type= 3
Dn Slope=0.0001
Boundary for River Rch & Prof#=UNT020 IN PECR,Reach-1         , 6
Up Type= 0
Dn Type= 3
Dn Slope=0.0001
Boundary for River Rch & Prof#=UNT020 IN PECR,Reach-1         , 7
Up Type= 0
Dn Type= 3
Dn Slope=0.0001
DSS Import GetInterval= 0
DSS Import GetPeak= 0
DSS Import FillOption= 0

--- UNT020 IN PECR.g01 (geometry) ---

Geom Title=Existing Conditions
Program Version=4.10

River Reach=UNT020 IN PECR  ,Reach-1
Reach XY= 30
      2343347.58     13242240.91      2343631.82     13241650.14
      2344117.81     13241397.83      2343651.03     13240195.78
      2343769.41      13239949.7       2344122.6     13239849.43
      2344127.39      13239208.9      2343846.12     13239064.27
      2343824.45      13238774.3      2343333.79     13238698.28
      2342830.05       13237212.       2342987.5     13236063.58
      2343724.98     13235131.94      2342994.59     13234074.87
      2342348.72     13233767.01      2342009.48     13232910.85
      2340774.23     13233175.63      2340120.61     13232401.12
       2339224.5     13232417.36       2338598.8     13232090.28
      2338181.44     13232125.69      2337834.22     13231591.49
      2337777.72     13230416.85      2337343.62     13230402.28
      2336833.69     13229736.35      2336184.41     13229319.29
      2332890.14     13227795.85      2330442.23     13227053.67
      2328410.98     13225907.83      2325712.49     13225093.82

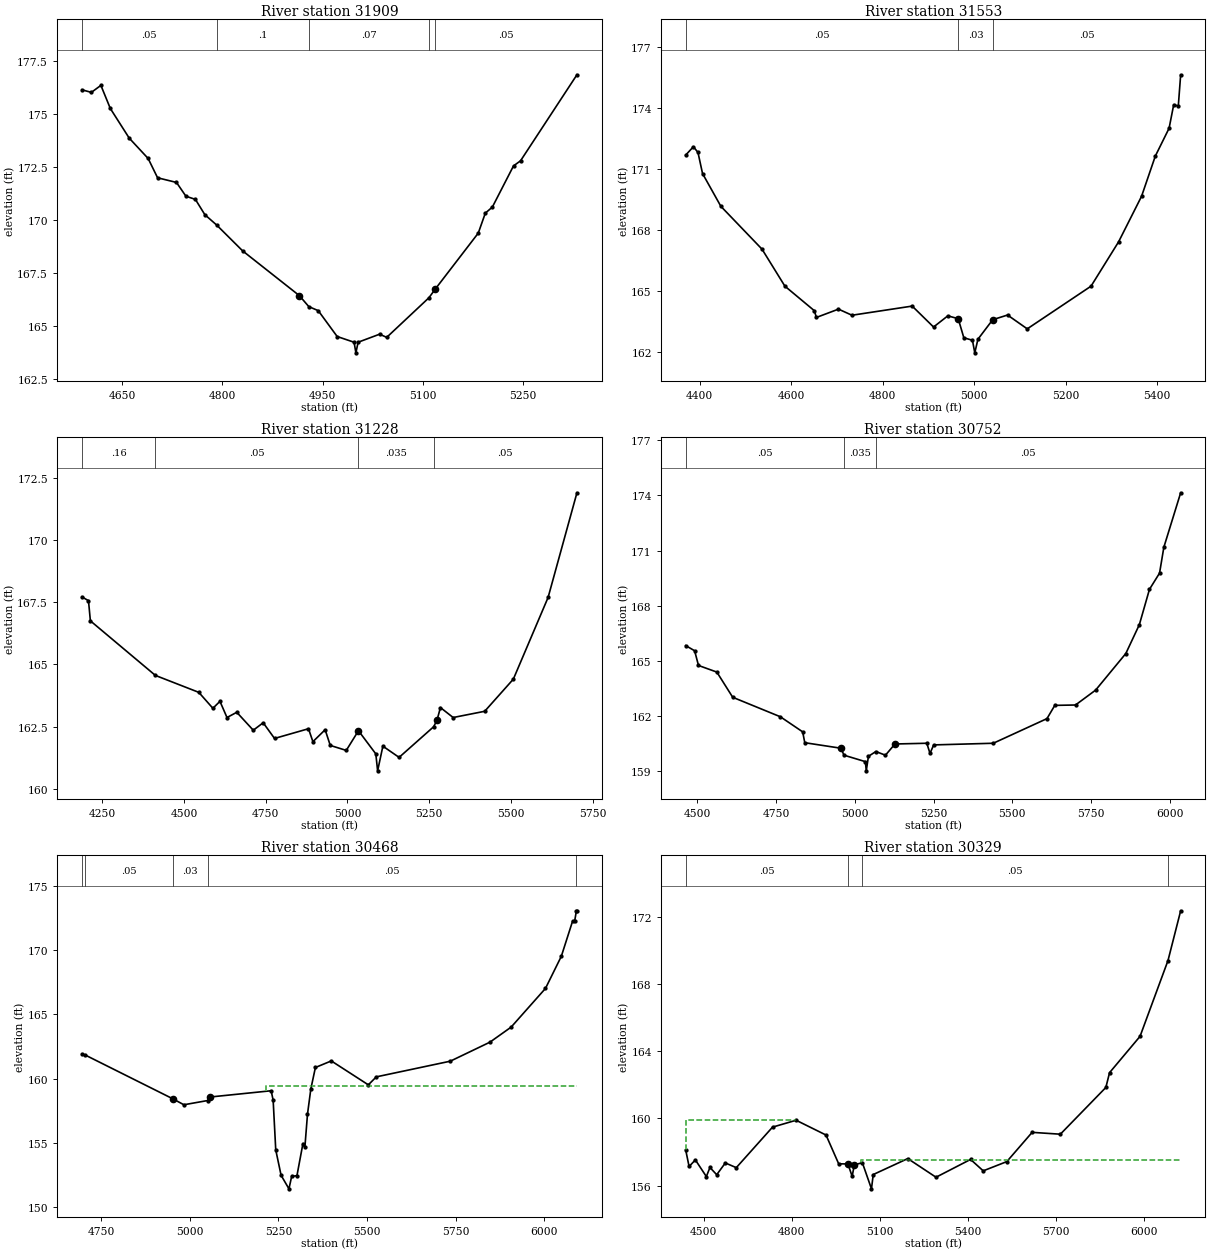
Type RM Length L Ch R = 1 ,31909   ,356,356,356
BEGIN DESCRIPTION:
UNT020 IN PECR 63.0
END DESCRIPTION:
XS GIS Cut Line= 3
       2343687.7     13242346.84      2343387.72     13242046.85
      2343087.69     13241946.84
#Sta/Elev= 30
  4590.1  176.15  4604.2  176.03  4618.4  176.36  4632.5  175.27  4660.8  173.87
  4689.1  172.91  4703.2     172  4731.5  171.78  4745.6  171.13  4759.8  170.98
  4773.9  170.26  4791.6  169.77  4830.5  168.55  4915.3  166.44  4929.5  165.92
  4943.6  165.73  4971.9  164.51  4997.2  164.24  4999.9  163.74  5003.2  164.24
  5035.4  164.62    5046  164.47  5109.2  166.34  5118.2  166.73    5183  169.39
  5193.5  170.33  5204.1  170.62  5235.7  172.56  5246.2   172.8  5330.6  176.86
#Mann= 5 ,-1 , 0
  4590.1     .05       0  4791.6      .1       0  4929.5     .07       0
  5109.2      .1       0  5118.2     .05       0
Bank Sta=4915.3,5118.2
XS Rating Curve= 0 ,0
Exp/Cntr=0.3,0.1

Type RM Length L Ch R = 1 ,31553   ,325,325,325
BEGIN DESCRIPTION:
UNT020 IN PECR 62.0
END DESCRIPTION:
XS GIS Cut Line= 4
      2343882.72     13242173.65      2343879.25     13241892.38
      2343327.17     13241670.15      2343122.53      13241687.5
#Sta/Elev= 30
  4369.3  171.67  4386.1  172.08  4396.1   171.8  4406.1  170.76  4446.1  169.15
  4536.1  167.04  4586.1  165.22  4650.6  164.01  4654.8  163.68  4703.2  164.09
  4732.7  163.79  4864.3  164.24    4911  163.21  4942.2  163.76  4964.9  163.62
  4977.2  162.68    4996  162.56  5001.1  161.94    5008  162.61  5040.3  163.57
  5072.7   163.8  5115.8  163.12  5255.2  165.22  5315.4   167.4  5365.6  169.64
  5395.7  171.62  5425.8  172.99  5435.9  174.15  5445.9  174.08  5451.1  175.62
#Mann= 3 , 0 , 0
  4369.3     .05       0  4964.9     .03       0  5040.3     .05       0
Bank Sta=4964.9,5040.3
XS Rating Curve= 0 ,0
Exp/Cntr=0.3,0.1

Type RM Length L Ch R = 1 ,31228   ,476,476,476
BEGIN DESCRIPTION:
Mapping XS 4e820a72
END DESCRIPTION:
XS GIS Cut Line= 3
      2344507.73     13241993.08      2343653.56     13241500.01
      2343146.58     13241645.86
#Sta/Elev= 30
    4188  167.71  4207.9  167.56  4213.7  166.75  4412.5  164.56  4545.3  163.88
  4588.4  163.24    4610  163.52  4631.5  162.87  4661.4  163.08  4711.9  162.36
  4742.2  162.66  4776.9  162.03  4880.8  162.42  4894.3   161.9  4931.7  162.38
  4947.4  161.75  4996.3  161.55  5033.6  162.34  5086.7  161.41  5092.2  160.73
  5108.3  161.72  5157.9  161.27  5263.6   162.5    5274  162.77  5284.3  163.27
  5323.2  162.87  5419.7  163.12  5507.3  164.41  5613.6  167.69  5701.8  171.89
#Mann= 4 ,-1 , 0
    4188     .16       0  4412.5     .05       0  5033.6    .035       0
  5263.6     .05       0
Bank Sta=5033.6,5274
XS Rating Curve= 0 ,0
Exp/Cntr=0.3,0.1

Type RM Length L Ch R = 1 ,30752   ,284,284,284
BEGIN DESCRIPTION:
UNT020 IN PECR 61.0
END DESCRIPTION:
XS GIS Cut Line= 4
      2344625.77     13241336.82      2344337.58     13241298.63
      2343712.58     13241392.38      2343104.96     13241621.54
#Sta/Elev= 30
  4462.7  165.83    4491  165.55  4503.3  164.75  4561.6  164.39    4612  163.02
  4763.4  161.96  4834.2  161.14  4840.9  160.55  4955.5  160.25  4965.6  159.87
  5033.4  159.52  5036.2  159.02  5043.1  159.81  5066.7  160.07  5097.1  159.87
  5127.4  160.48  5228.5  160.52  5238.6  159.97  5250.4  160.43  5439.6  160.52
  5610.2  161.86    5635  162.58  5700.8   162.6  5764.7  163.41  5860.6   165.4
  5903.6  166.97  5935.7  168.89  5967.7  169.77  5981.4  171.18  6034.8  174.14
#Mann= 3 ,-1 , 0
  4462.7     .05       0  4965.6    .035       0  5066.7     .05       0
Bank Sta=4955.5,5127.4
XS Rating Curve= 0 ,0
Exp/Cntr=0.3,0.1

Type RM Length L Ch R = 1 ,30468   ,139,139,139
BEGIN DESCRIPTION:
Mapping XS 28abfef7
END DESCRIPTION:
XS GIS Cut Line= 3
      2344372.32     13241031.27      2344205.64     13241006.96
      2343108.39     13241555.58
#Sta/Elev= 30
  4696.3  161.91  4703.9  161.86  4951.9  158.44  4983.6  157.97  5050.7   158.3
  5056.3  158.57  5229.6  159.06  5235.2  158.32  5242.5  154.46  5257.6  152.48
  5279.7  151.43  5287.3  152.39  5302.3  152.46  5319.1  154.95  5324.6  154.66
    5332  157.24  5341.4   159.2  5354.3  160.87  5399.1  161.38  5503.5  159.52
  5525.9  160.14  5734.5  161.36  5846.3  162.84    5906  164.01  6002.8  167.02
  6047.5  169.52  6079.3  172.26  6084.9  172.23    6090  173.06  6091.5  173.06
#Mann= 5 ,-1 , 0
  4696.3      .1       0  4703.9     .05       0  4951.9     .03       0
  5050.7     .05       0    6090     .08       0
#XS Ineff= 2 , 0
       0                 5214.44       0  159.45
Permanent Ineff=
       F       T
Bank Sta=4951.9,5056.3
XS Rating Curve= 0 ,0
Exp/Cntr=0.3,0.1

Type RM Length L Ch R = 1 ,30329   ,301,301,301
BEGIN DESCRIPTION:
UNT020 IN PECR 60.0
END DESCRIPTION:
XS GIS Cut Line= 2
      2344549.26     13240654.16       2343087.7     13241496.87
#Sta/Elev= 30
  4438.4  158.12  4449.9  157.14  4471.4  157.53  4508.8  156.54    4521  157.08
  4544.1  156.65  4573.4  157.35  4610.8  157.07  4734.3  159.48  4814.7  159.89
  4916.7  159.01  4959.8   157.3  4991.4  157.29  5005.8  156.55    5013  157.23
  5040.4  157.37  5071.6  155.81  5077.6  156.66  5195.4  157.61  5291.6   156.5
  5409.4  157.56  5452.5  156.88  5532.9  157.43  5619.2  159.17  5715.4  159.06
  5870.5  161.84  5883.1  162.72    5987  164.88  6082.3  169.39  6125.5  172.35
#Mann= 4 ,-1 , 0
  4438.4     .05       0  4991.4     .03       0  5040.4     .05       0
  6082.3     .08       0
#XS Ineff= 2 , 0
       0    4815  159.91    5035       0  157.55
Permanent Ineff=
       T       T
Bank Sta=4991.4,5013
XS Rating Curve= 0 ,0
Exp/Cntr=0.3,0.1

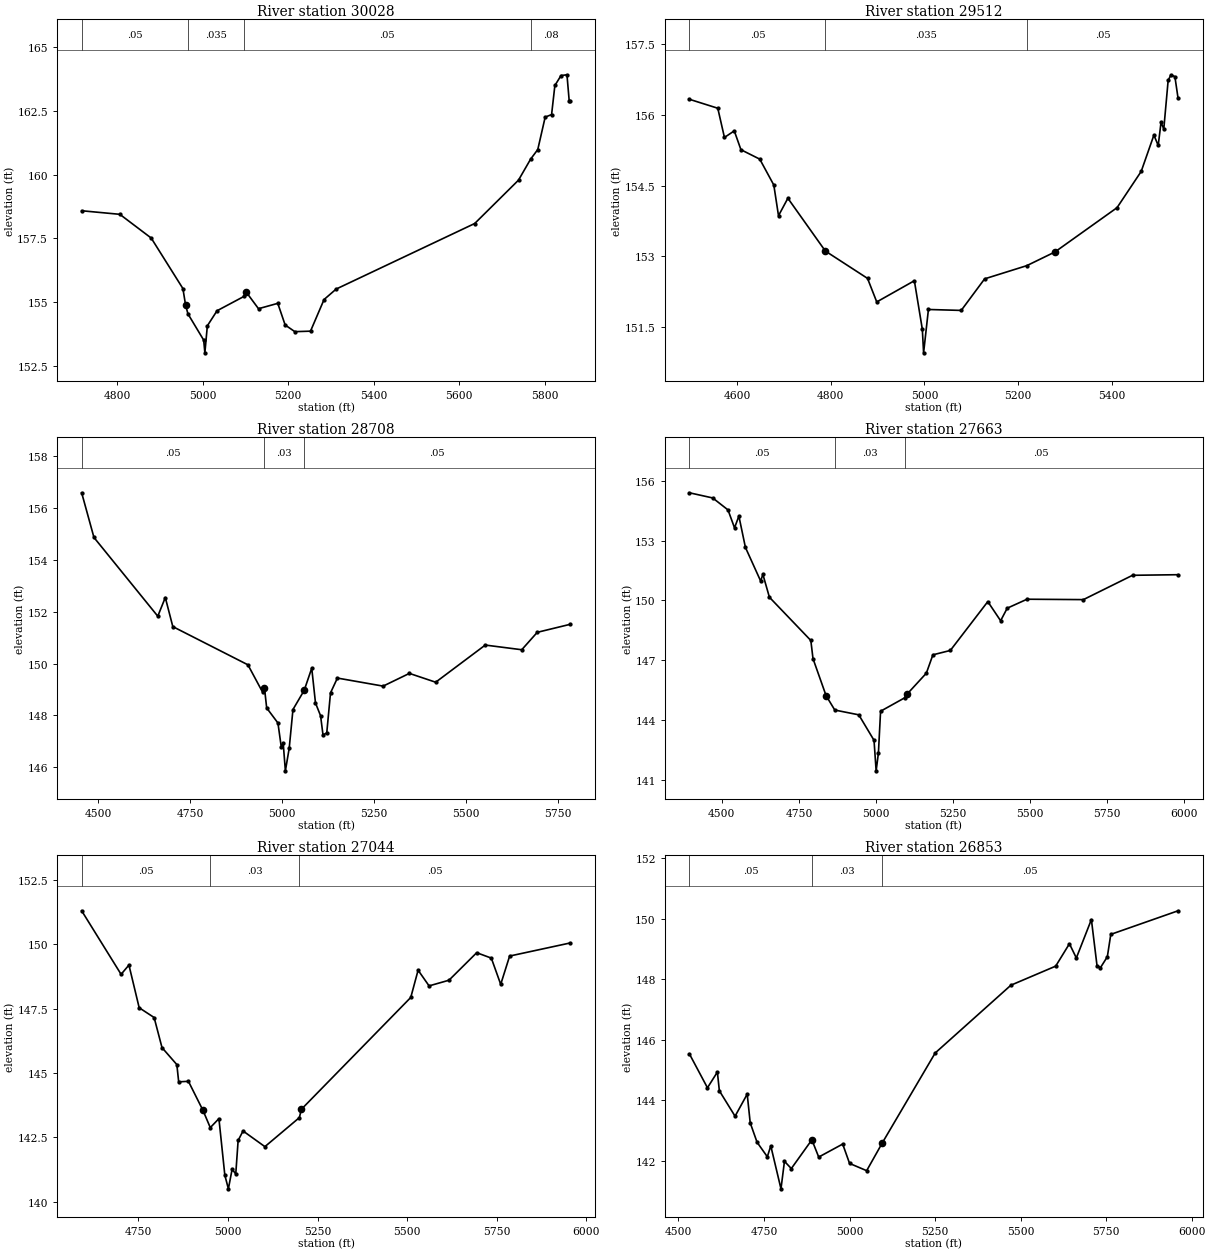
Type RM Length L Ch R = 1 ,30028   ,516,516,516
BEGIN DESCRIPTION:
Mapping XS ba36caf3
END DESCRIPTION:
XS GIS Cut Line= 3
      2344146.65     13240642.37      2343986.89     13240656.26
      2343098.04     13241076.39
#Sta/Elev= 30
  4716.8  158.58  4806.1  158.44  4879.5  157.51  4953.7  155.53  4959.8   154.9
  4965.4  154.54  5002.3  153.51  5005.1  153.01  5010.9  154.07  5033.6  154.66
  5096.4  155.22  5101.9  155.39  5130.6  154.74  5175.7  154.95    5193   154.1
  5215.7  153.84  5252.3  153.86    5284   155.1  5312.3  155.51  5636.5  158.08
    5739  159.78  5767.2   160.6  5784.1  160.98  5801.4  162.25  5816.4  162.35
  5824.1  163.49  5838.5  163.88  5852.4  163.91  5857.7  162.87  5860.3  162.87
#Mann= 4 ,-1 , 0
  4716.8     .05       0  4965.4    .035       0  5096.4     .05       0
  5767.2     .08       0
Bank Sta=4959.8,5101.9
XS Rating Curve= 0 ,0
Exp/Cntr=0.3,0.1

Type RM Length L Ch R = 1 ,29512   ,804,804,804
BEGIN DESCRIPTION:
UNT020 IN PECR 59.0
END DESCRIPTION:
XS GIS Cut Line= 4
       2344136.2     13240343.77      2344042.45     13240260.43
      2343361.89      13240263.9        2343162.     13240391.42
#Sta/Elev= 30
  4498.4  156.33    4559  156.14  4573.2  155.52  4594.2  155.66  4608.4  155.26
  4648.6  155.06  4678.6  154.51  4688.6  153.86  4708.6  154.23  4788.6  153.11
  4878.6  152.53  4898.3  152.03  4978.6  152.48  4995.6  151.45  4998.3  150.95
  5008.6  151.87  5078.6  151.85  5128.6  152.52  5218.6   152.8  5278.6  153.09
  5411.2  154.03  5462.8   154.8  5489.9  155.57  5499.1  155.35  5505.1  155.84
    5511   155.7  5520.3  156.73  5526.3  156.85  5534.7  156.81  5541.5  156.35
#Mann= 3 ,-1 , 0
  4498.4     .05       0  4788.6    .035       0  5218.6     .05       0
Bank Sta=4788.6,5278.6
XS Rating Curve= 0 ,0
Exp/Cntr=0.3,0.1

Type RM Length L Ch R = 1 ,28708   ,1045,1045,1045
BEGIN DESCRIPTION:
Mapping XS 55eb927c
END DESCRIPTION:
XS GIS Cut Line= 3
      2344660.45     13239909.73      2343712.58     13239718.76
      2343452.46     13239968.48
#Sta/Elev= 30
  4455.2  156.57  4488.6  154.85    4662  151.82  4682.4  152.54  4702.8  151.42
  4906.8  149.95  4946.6   148.9  4951.7  149.07  4957.8  148.29  4988.4  147.71
  4997.5  146.78  5002.6  146.95  5008.6  145.87    5019  146.74  5029.2  148.23
  5059.8  148.97  5080.2  149.82  5090.4  148.48  5104.2  147.99  5110.8  147.25
    5121  147.33  5131.2  148.87  5149.9  149.44  5274.1  149.13  5345.5  149.62
  5416.9  149.28  5551.6  150.71  5650.7  150.53  5692.8   151.2  5782.7  151.51
#Mann= 3 , 0 , 0
  4455.2     .05       0  4951.7     .03       0  5059.8     .05       0
Bank Sta=4951.7,5059.8
XS Rating Curve= 0 ,0
Exp/Cntr=0.3,0.1

Type RM Length L Ch R = 1 ,27663   ,619,619,619
BEGIN DESCRIPTION:
UNT020 IN PECR 58.0
END DESCRIPTION:
XS GIS Cut Line= 3
       2344285.3     13238647.43      2343681.97     13239250.75
      2343422.15     13239934.95
#Sta/Elev= 30
  4394.7   155.4  4470.4  155.14  4519.9  154.54  4541.1  153.64  4555.2  154.23
  4576.4  152.66  4625.9  150.97    4633  151.31  4654.2  150.16  4788.6  147.99
  4795.6  147.08  4838.1  145.22  4866.3   144.5  4944.1  144.26  4993.6  142.98
  5000.4  141.45  5007.8  142.34  5014.8  144.44  5092.6  145.11  5099.7  145.28
  5163.3  146.35  5184.5  147.27  5241.1  147.49  5362.6  149.94  5404.2  148.98
  5425.6  149.61  5489.8  150.06  5672.7  150.04    5832  151.26  5979.8  151.29
#Mann= 3 ,-1 , 0
  4394.7     .05       0  4866.3     .03       0  5092.6     .05       0
Bank Sta=4838.1,5099.7
XS Rating Curve= 0 ,0
Exp/Cntr=0.3,0.1

Type RM Length L Ch R = 1 ,27044   ,191,191,191
BEGIN DESCRIPTION:
UNT020 IN PECR 57.0
END DESCRIPTION:
XS GIS Cut Line= 4
      2343771.61     13238375.02      2343587.58     13238531.26
      2343486.89     13239090.29       2343372.9     13239632.61
#Sta/Elev= 30
  4591.5  151.31  4701.5  148.84  4723.4   149.2    4752  147.54  4793.7  147.16
  4815.7  145.99  4857.1  145.33  4862.2  144.66  4889.4  144.68    4930  143.55
  4950.4  142.88  4974.5  143.23    4991  141.03  5000.9   140.5  5011.3  141.26
  5021.5  141.08  5028.1  142.38  5041.8  142.75  5102.8  142.14  5199.1  143.27
  5204.4  143.59  5509.8  147.94  5530.3     149  5560.9  148.39  5616.4  148.61
  5693.8  149.68  5734.6  149.47  5760.8  148.45  5785.7  149.55  5955.1  150.06
#Mann= 3 ,-1 , 0
  4591.5     .05       0  4950.4     .03       0  5199.1     .05       0
Bank Sta=4930,5204.4
XS Rating Curve= 0 ,0
Exp/Cntr=0.3,0.1

Type RM Length L Ch R = 1 ,26853   ,215,215,215
BEGIN DESCRIPTION:
UNT020 IN PECR 56.0
END DESCRIPTION:
XS GIS Cut Line= 4
      2343473.66     13238261.14      2343391.17      13238404.4
      2343360.79     13239003.36      2343282.77     13239662.21
#Sta/Elev= 30
  4531.9  145.53  4584.7  144.41  4613.7  144.93  4619.5  144.31  4665.4  143.47
  4700.9   144.2  4709.7  143.25  4729.7  142.61  4759.7  142.13  4769.8  142.49
  4799.6  141.07  4809.8  141.98  4829.8  141.74  4889.9  142.69  4909.9  142.12
    4980  142.55  5000.1  141.91  5050.1  141.67 5096.36   142.6  5250.4  145.56
  5471.7   147.8  5602.6  148.43  5642.8  149.17    5663   148.7    5707  149.97
  5723.4  148.45  5733.5  148.38  5753.6  148.74  5763.7  149.48  5960.4  150.26
#Mann= 3 , 0 , 0
  4531.9     .05       0  4889.9     .03       0 5096.36     .05       0
Bank Sta=4889.9,5096.36
XS Rating Curve= 0 ,0
Exp/Cntr=0.3,0.1

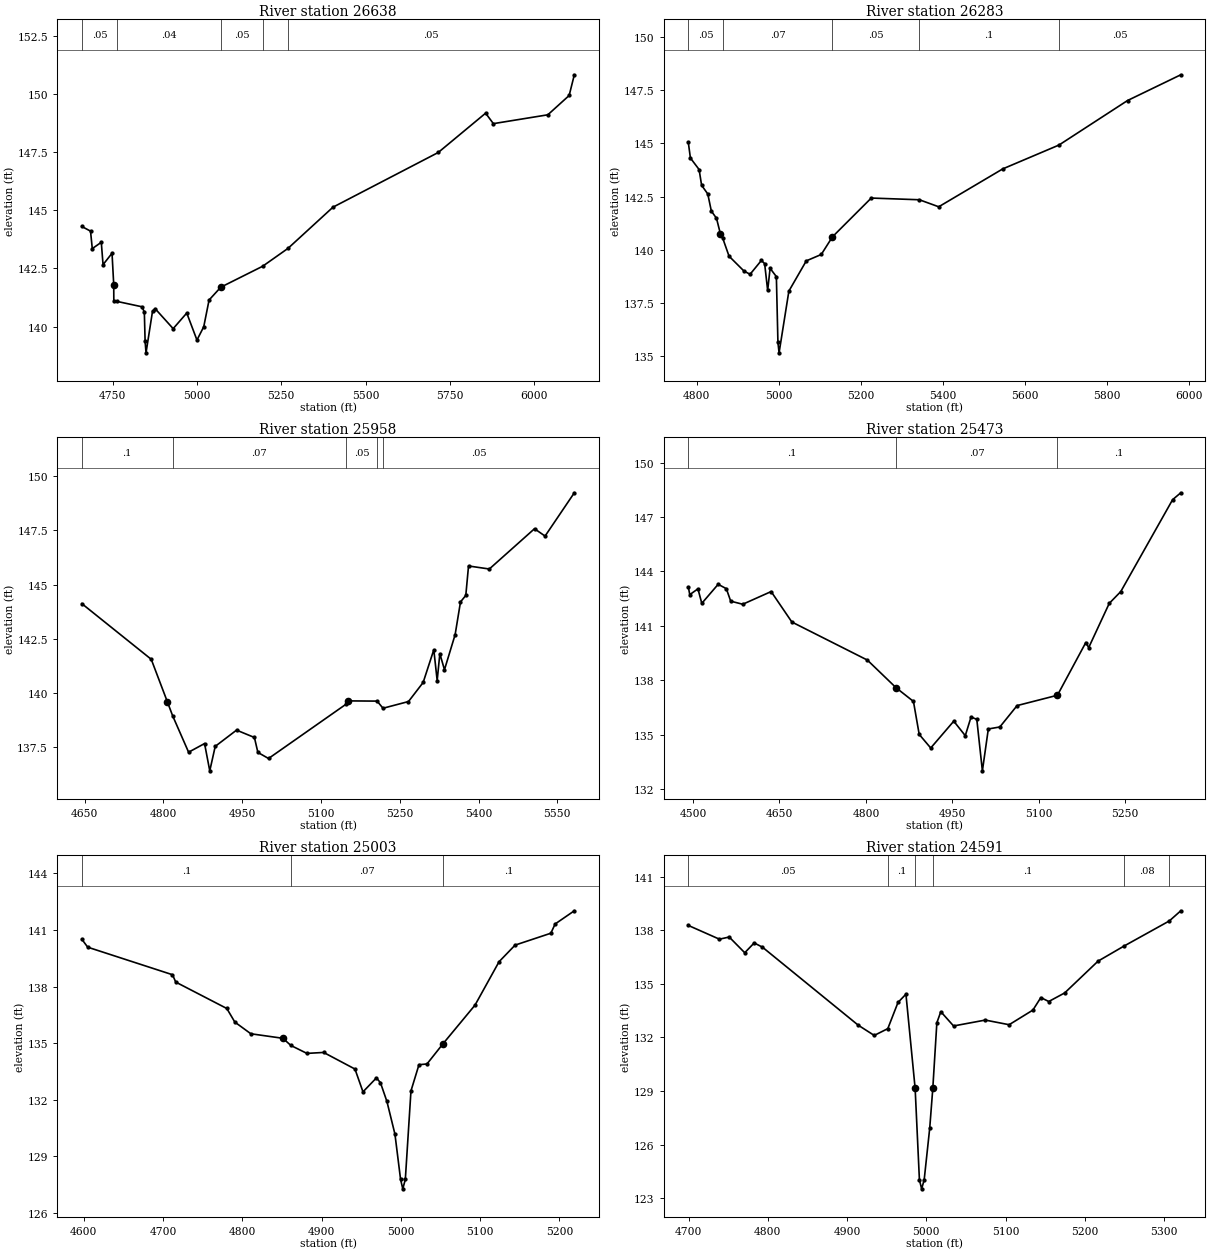
Type RM Length L Ch R = 1 ,26638   ,355,355,355
BEGIN DESCRIPTION:
UNT020 IN PECR 55.0
END DESCRIPTION:
XS GIS Cut Line= 5
      2343360.79     13238217.77      2343291.35     13238430.44
      2343204.54     13239142.25      2343169.82     13239580.61
      2343199.69     13239653.16
#Sta/Elev= 30
  4659.2   144.3  4684.9   144.1  4690.1  143.35  4716.8  143.62    4722  142.66
  4748.6  143.15 4753.64   141.8  4753.9  141.11  4763.4  141.08  4837.1  140.85
  4844.3  140.63  4846.6  139.37  4849.3  138.87  4868.6  140.66  4876.2  140.77
  4929.7  139.91    4970  140.58  5000.2  139.42  5020.3  139.99  5036.1  141.14
  5070.7  141.69  5194.7  142.59    5270  143.36  5403.2  145.13    5715  147.48
  5855.4  149.17  5878.4  148.72  6039.7   149.1  6102.9  149.93  6118.2  150.82
#Mann= 5 ,-1 , 0
  4659.2     .05       0  4763.4     .04       0  5070.7     .05       0
  5194.7      .1       0    5270     .05       0
Bank Sta=4753.64,5070.7
XS Rating Curve= 0 ,0
Exp/Cntr=0.3,0.1

Type RM Length L Ch R = 1 ,26283   ,325,325,325
BEGIN DESCRIPTION:
UNT020 IN PECR 54.0
END DESCRIPTION:
XS GIS Cut Line= 3
      2343365.16     13238117.92      2342951.15     13238378.73
      2342475.37     13238907.88
#Sta/Elev= 30
  4779.5  145.04  4784.6  144.31  4805.8  143.77  4811.9  143.03    4827  142.62
  4835.6  141.82  4848.2  141.48  4857.6  140.76  4863.5  140.54  4878.8   139.7
  4915.3     139  4930.1  138.85  4957.7   139.5  4965.6  139.35    4973  138.09
  4978.9  139.13  4994.2  138.74    4998  135.66  5000.8  135.16  5024.7  138.06
  5067.2  139.48  5103.7  139.78    5131  140.61  5225.6  142.43  5342.9  142.35
  5390.1  142.02  5546.3   143.8  5683.4  144.92  5850.5  147.01  5980.4  148.22
#Mann= 5 ,-1 , 0
  4779.5     .05       0  4863.5     .07       0    5131     .05       0
  5342.9      .1       0  5683.4     .05       0
Bank Sta=4857.6,5131
XS Rating Curve= 0 ,0
Exp/Cntr=0.3,0.1

Type RM Length L Ch R = 1 ,25958   ,485,485,485
BEGIN DESCRIPTION:
UNT020 IN PECR 53.0
END DESCRIPTION:
XS GIS Cut Line= 4
      2343337.62     13237914.46      2343238.86      13237933.1
      2342573.58     13238048.64      2342412.09     13238057.92
#Sta/Elev= 30
  4644.9  144.12    4777  141.55  4807.5   139.6  4817.6  138.95  4848.1  137.26
  4878.5  137.66  4888.4   136.4  4898.8  137.53  4939.4  138.28  4973.4  137.94
    4980  137.25  5000.3  136.97  5147.4  139.47  5152.5  139.63    5207  139.62
  5218.2  139.29  5266.7   139.6  5294.6  140.48  5314.9  141.99  5321.3  140.57
  5326.4  141.81  5335.2  141.07  5355.5  142.69  5365.7   144.2  5375.8   144.5
    5381  145.86  5420.6  145.72  5506.6  147.58  5526.7  147.24  5582.4  149.24
#Mann= 5 ,-1 , 0
  4644.9      .1       0  4817.6     .07       0  5147.4     .05       0
    5207      .1       0  5218.2     .05       0
Bank Sta=4807.5,5152.5
XS Rating Curve= 0 ,0
Exp/Cntr=0.3,0.1

Type RM Length L Ch R = 1 ,25473   ,470,470,470
BEGIN DESCRIPTION:
UNT020 IN PECR 52.0
END DESCRIPTION:
XS GIS Cut Line= 3
      2343334.74     13237753.34       2343113.4     13237558.04
      2342553.55     13237549.36
#Sta/Elev= 30
  4491.7  143.15  4494.2  142.72  4508.4  143.04  4515.1  142.24  4543.5  143.29
  4557.7  143.05  4565.3  142.36  4586.2  142.19  4635.5  142.89  4671.5  141.21
  4802.6  139.11  4852.6  137.58  4882.6  136.83  4892.6  135.01  4912.6  134.26
  4952.6  135.74  4972.6  134.94  4982.6  135.97  4992.6  135.84  5002.3     133
  5012.6  135.31  5032.6  135.42  5062.6   136.6  5132.6  137.17  5181.9  140.08
  5186.9   139.8  5222.6  142.24  5242.6  142.89  5332.6  147.96  5346.8  148.34
#Mann= 3 , 0 , 0
  4491.7      .1       0  4852.6     .07       0  5132.6      .1       0
Bank Sta=4852.6,5132.6
XS Rating Curve= 0 ,0
Exp/Cntr=0.3,0.1

Type RM Length L Ch R = 1 ,25003   ,412,412,412
BEGIN DESCRIPTION:
UNT020 IN PECR 51.0
END DESCRIPTION:
XS GIS Cut Line= 3
      2343242.62     13237223.11      2343149.41     13237146.68
      2342653.72     13237077.73
#Sta/Elev= 30
  4597.7  140.51  4605.1  140.09    4712  138.63  4716.1  138.24  4780.5  136.84
  4790.6  136.12  4810.8   135.5  4851.2  135.26  4861.3  134.88  4881.5  134.46
  4902.6  134.51  4942.1  133.63  4952.2  132.42  4969.1  133.16  4974.2  132.91
  4982.4  131.91  4992.5  130.18  4999.6  127.78  5002.4  127.28  5005.6  127.78
  5012.7  132.47  5022.8  133.86  5032.9   133.9  5053.1  134.97  5093.5  137.02
  5123.8  139.32    5144   140.2  5189.1  140.83  5194.5  141.32  5218.7  142.02
#Mann= 3 ,-1 , 0
  4597.7      .1       0  4861.3     .07       0  5053.1      .1       0
Bank Sta=4851.2,5053.1
XS Rating Curve= 0 ,0
Exp/Cntr=0.3,0.1

Type RM Length L Ch R = 1 ,24591   ,479,479,479
BEGIN DESCRIPTION:
UNT020 IN PECR 50.0
END DESCRIPTION:
XS GIS Cut Line= 3
      2343266.86     13236734.84      2343162.46     13236701.29
      2342651.38     13236727.31
#Sta/Elev= 30
  4699.7  138.27  4738.9   137.5  4751.3  137.62  4770.9  136.74  4782.8  137.29
  4793.3  137.05  4914.2  132.68  4934.3  132.11  4951.4  132.49  4964.3  133.96
  4974.3  134.42 4985.91  129.14  4991.3  124.02  4994.1  123.52  4997.3  124.02
  5004.3  126.92 5008.18  129.14  5013.3  132.82  5018.3  133.44  5034.4  132.64
  5074.4  132.97  5104.5  132.71  5134.5  133.53  5144.5  134.23  5154.5  134.01
  5174.6  134.49  5216.7  136.27  5248.9   137.1  5306.6  138.52  5321.1  139.09
#Mann= 6 ,-1 , 0
  4699.7     .05       0  4951.4      .1       0 4985.91     .07       0
 5008.18      .1       0  5248.9     .08       0  5306.6      .1       0
Bank Sta=4985.91,5008.18
XS Rating Curve= 0 ,0
Exp/Cntr=0.3,0.1

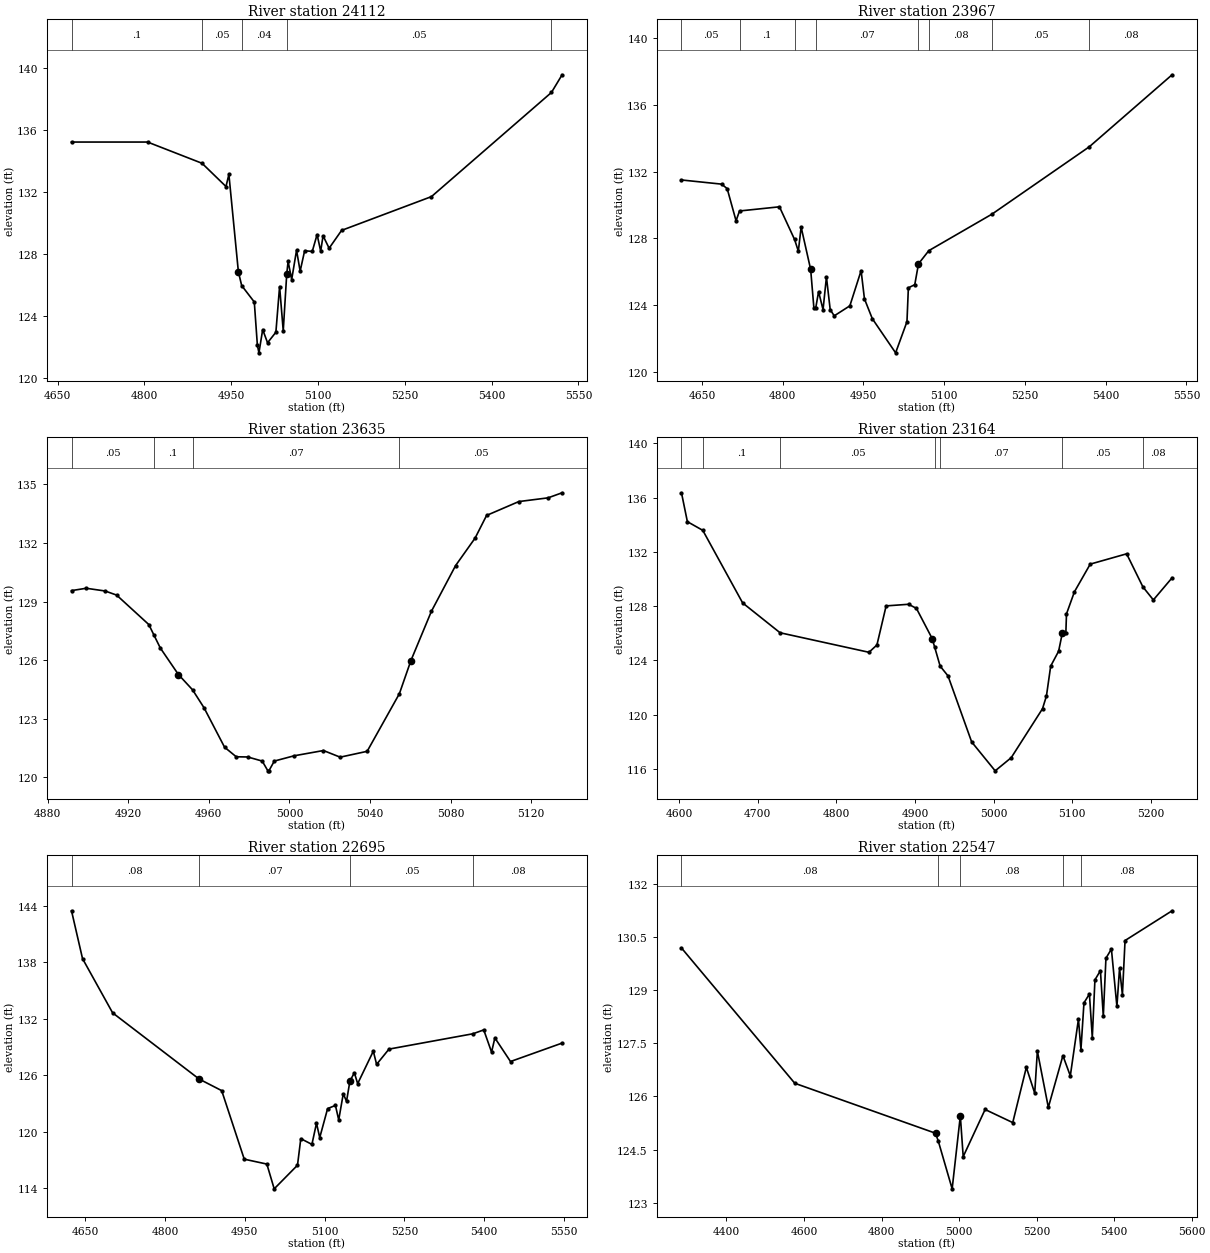
Type RM Length L Ch R = 1 ,24112   ,145,145,145
BEGIN DESCRIPTION:
Mapping XS 024a7ae7
END DESCRIPTION:
XS GIS Cut Line= 4
      2343339.08     13236222.87      2343045.27     13236232.75
      2342931.69      13236316.7      2342631.61     13236599.56
#Sta/Elev= 30
  4674.2  135.25  4805.6  135.25  4899.7  133.88  4941.1  132.38  4946.1  133.16
  4962.5  126.88  4968.2  125.99    4990  124.93  4995.3  122.15    4998  121.65
  5004.5  123.15  5012.9   122.3  5027.3  122.98  5033.7  125.93    5040  123.07
 5046.02  126.73  5048.4  127.55  5054.6  126.38    5063  128.27  5069.2  126.92
    5077  128.24  5090.1  128.19  5098.5  129.28  5104.7  128.21  5108.8   129.2
  5119.3   128.4  5140.8  129.55  5296.1  131.73  5503.4  138.45  5521.8  139.59
#Mann= 5 ,-1 , 0
  4674.2      .1       0  4899.7     .05       0  4968.2     .04       0
 5046.02     .05       0  5503.4     .08       0
Bank Sta=4962.5,5046.02
XS Rating Curve= 0 ,0
Exp/Cntr=0.3,0.1

Type RM Length L Ch R = 1 ,23967   ,332,332,332
BEGIN DESCRIPTION:
UNT020 IN PECR 49.0
END DESCRIPTION:
XS GIS Cut Line= 4
      2343339.82     13235965.76      2343101.15     13236028.68
      2342962.26     13236135.02       2342623.7     13236488.77
#Sta/Elev= 30
    4612   131.5  4686.6  131.25  4696.9  130.98  4713.4  129.05  4719.8  129.64
    4794  129.89  4822.1  127.93  4829.1  127.23  4834.3  128.67    4852  126.13
    4858  123.82  4861.4  123.82  4866.7   124.8    4875  123.72  4881.3  125.68
  4888.3  123.72  4895.8  123.35  4924.8  123.95  4945.7  126.06  4951.9  124.37
  4966.5  123.18  5009.8  121.13  5030.9     123  5033.5  125.03  5045.4  125.22
  5052.3  126.47  5071.5  127.26  5188.8  129.45  5369.6  133.49  5523.4  137.81
#Mann= 8 ,-1 , 0
    4612     .05       0  4719.8      .1       0  4822.1     .08       0
  4861.4     .07       0  5052.3      .1       0  5071.5     .08       0
  5188.8     .05       0  5369.6     .08       0
Bank Sta=4852,5052.3
XS Rating Curve= 0 ,0
Exp/Cntr=0.3,0.1

Type RM Length L Ch R = 1 ,23635   ,471,471,471
BEGIN DESCRIPTION:
UNT020 IN PECR 48.0
END DESCRIPTION:
XS GIS Cut Line= 2
      2343274.07     13235911.84      2343061.62     13235792.66
#Sta/Elev= 30
  4891.8  129.56  4899.1  129.68  4908.5  129.54  4914.2  129.33  4930.2  127.82
  4932.6  127.31  4935.9  126.62  4944.9  125.26  4951.9  124.48  4957.6  123.56
  4967.8  121.54  4973.6  121.05  4979.3  121.04  4986.5  120.83  4989.3  120.33
  4989.8  120.33  4992.5  120.83  5002.3   121.1  5016.9  121.37  5025.2  121.03
  5038.6  121.33  5054.6  124.28  5060.3  125.97  5070.5   128.5  5082.5  130.84
  5092.2  132.25  5097.9  133.41  5113.9  134.12  5128.4  134.31  5135.4  134.57
#Mann= 4 ,-1 , 0
  4891.8     .05       0  4932.6      .1       0  4951.9     .07       0
  5054.6     .05       0
Bank Sta=4944.9,5060.3
XS Rating Curve= 0 ,0
Exp/Cntr=0.3,0.1

Type RM Length L Ch R = 1 ,23164   ,469,469,469
BEGIN DESCRIPTION:
UNT020 IN PECR 47.0
END DESCRIPTION:
XS GIS Cut Line= 2
      2343865.14      13235526.7      2343244.06     13235466.37
#Sta/Elev= 30
  4603.1  136.36  4610.6  134.23  4630.2  133.59  4680.9  128.24  4728.5  126.04
  4841.6   124.6  4851.7  125.14  4863.4  128.02  4891.9  128.14  4901.9  127.84
    4922  125.61  4925.2  124.97  4932.1  123.58  4942.1  122.86  4972.2  117.99
  5002.1  115.86  5022.5  116.83  5062.3  120.44  5067.3  121.38  5072.7  123.58
  5082.8  124.68 5087.61  126.05 5091.99  126.01  5092.8  127.43  5102.9  129.06
    5123   131.1  5169.3  131.86    5190  129.42  5203.3  128.46  5227.1  130.09
#Mann= 7 ,-1 , 0
  4603.1     .05       0  4630.2      .1       0  4728.5     .05       0
  4925.2      .1       0  4932.1     .07       0 5087.61     .05       0
    5190     .08       0
Bank Sta=4922,5087.61
XS Rating Curve= 0 ,0
Exp/Cntr=0.3,0.1

Type RM Length L Ch R = 1 ,22695   ,148,148,148
BEGIN DESCRIPTION:
UNT020 IN PECR 46.0
END DESCRIPTION:
XS GIS Cut Line= 3
      2343976.76     13234836.62      2343683.97     13235133.75
      2343273.61     13235428.17
#Sta/Elev= 30
  4624.2  143.45  4644.9  138.37  4701.5  132.61  4864.1  125.58  4906.5  124.35
  4948.9  117.07  4991.4  116.55  5005.2  113.92    5049  116.43  5055.2  119.25
  5076.1  118.64  5084.7  120.89  5090.8  119.36  5105.6  122.44  5120.3  122.78
  5126.5  121.24    5135  124.01  5141.2  123.22  5147.5  125.36  5155.9  126.25
  5162.1  125.09  5191.5  128.54  5197.7  127.14    5221  128.76  5378.9  130.39
  5399.1   130.8  5413.8  128.44    5420  129.95  5449.4  127.44  5546.4   129.4
#Mann= 4 ,-1 , 0
  4624.2     .08       0  4864.1     .07       0  5147.5     .05       0
  5378.9     .08       0
Bank Sta=4864.1,5147.5
XS Rating Curve= 0 ,0
Exp/Cntr=0.3,0.1

Type RM Length L Ch R = 1 ,22547   ,149,149,149
BEGIN DESCRIPTION:
Mapping XS 3c716bfb
END DESCRIPTION:
XS GIS Cut Line= 3
      2344104.06     13234411.56      2343589.55     13235048.44
      2343286.41     13235376.61
#Sta/Elev= 30
    4284  130.19  4576.3  126.37  4939.3  124.96  4946.4  124.74  4982.2  123.39
  5003.3  125.45  5010.7   124.3  5067.2  125.63  5138.5  125.26  5173.6  126.82
  5195.2  126.09    5202  127.28  5230.3  125.69  5267.9  127.15    5287  126.58
    5308  128.18  5314.4  127.32  5322.2  128.64  5336.3  128.89  5343.7  127.66
  5350.5  129.29  5364.7  129.55  5372.1  128.26  5378.9   129.9    5393  130.16
  5407.2  128.54    5414  129.62  5421.4  128.87  5428.2   130.4  5549.5  131.24
#Mann= 5 ,-1 , 0
    4284     .08       0  4946.4     .07       0  5003.3     .08       0
  5267.9     .05       0  5314.4     .08       0
Bank Sta=4939.3,5003.3
XS Rating Curve= 0 ,0
Exp/Cntr=0.3,0.1

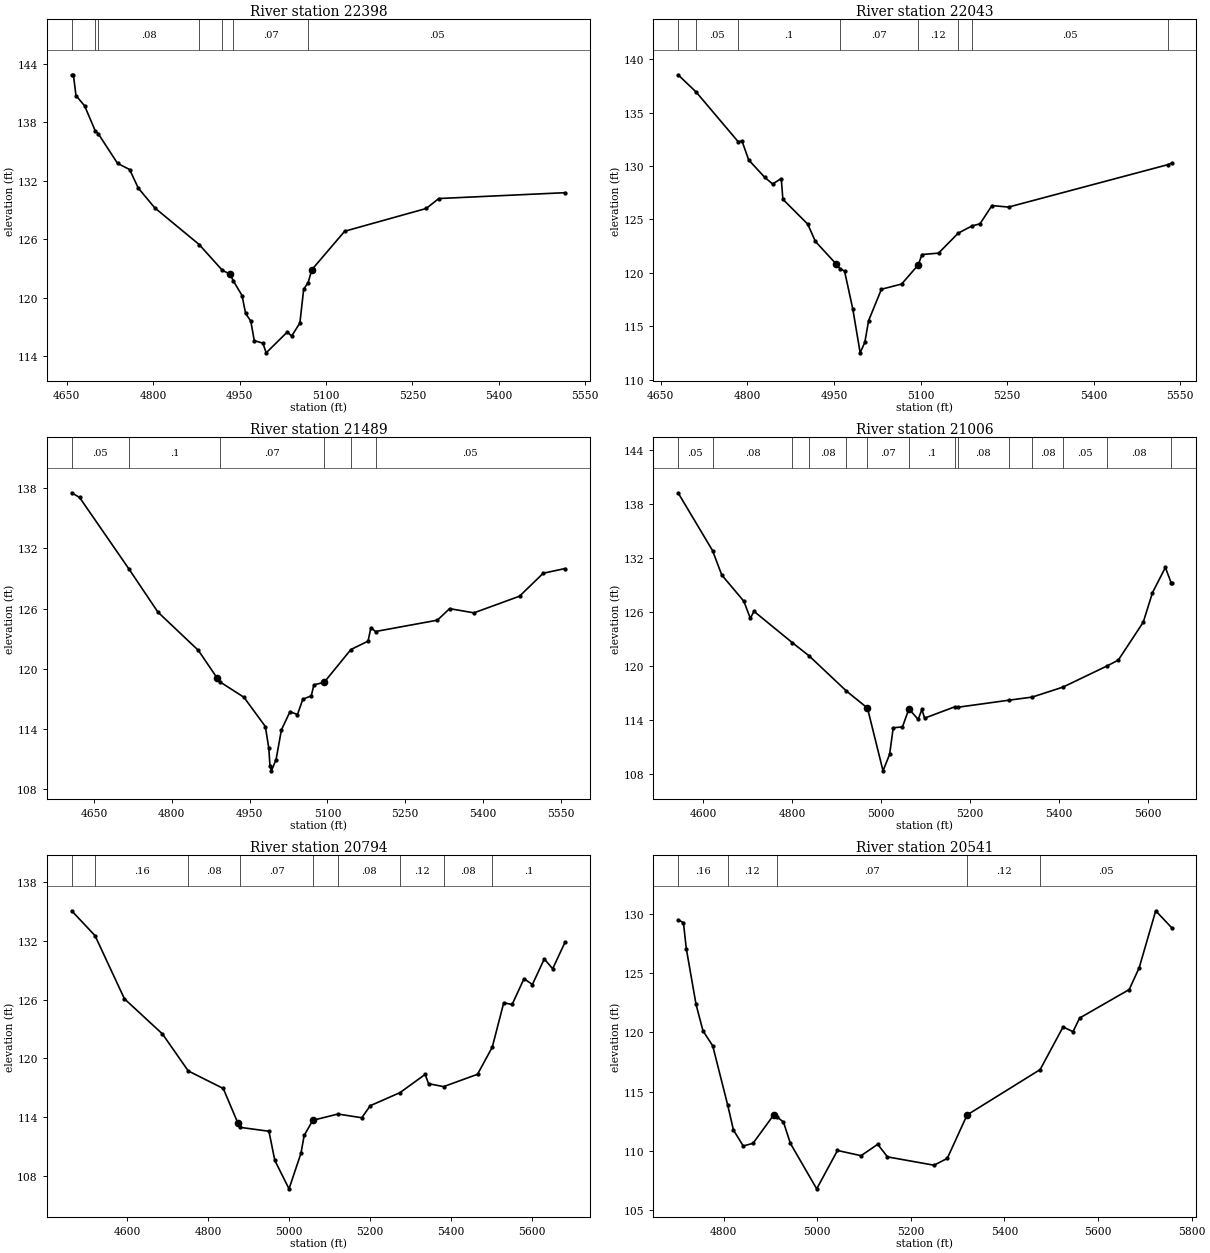
Type RM Length L Ch R = 1 ,22398   ,355,355,355
BEGIN DESCRIPTION:
UNT020 IN PECR 45.0
END DESCRIPTION:
XS GIS Cut Line= 3
      2343787.71     13234546.88      2343587.72     13234846.85
       2343262.7     13235221.88
#Sta/Elev= 30
  4658.6  142.85  4661.6  142.85  4666.1  140.72  4681.1  139.67  4699.3  137.14
  4704.9   136.8  4738.2  133.78  4759.2  133.14  4774.3  131.24  4802.8  129.22
  4879.9  125.46  4920.2  122.82  4933.5  122.42  4939.5  121.71  4954.5  120.22
  4960.5  118.41  4969.6  117.61  4975.6  115.61  4990.6  115.35  4996.3  114.36
  5032.9  116.49  5040.5  116.08  5054.8  117.41  5061.4  120.88    5069  121.54
  5075.6  122.88  5132.6  126.82  5274.1  129.15    5296  130.17  5515.4  130.77
#Mann= 7 ,-1 , 0
  4658.6      .1       0  4699.3     .05       0  4704.9     .08       0
  4879.9      .1       0  4920.2     .12       0  4939.5     .07       0
    5069     .05       0
Bank Sta=4933.5,5075.6
XS Rating Curve= 0 ,0
Exp/Cntr=0.3,0.1

Type RM Length L Ch R = 1 ,22043   ,554,554,554
BEGIN DESCRIPTION:
UNT020 IN PECR 44.0
END DESCRIPTION:
XS GIS Cut Line= 3
      2343675.76     13234411.54      2343503.34     13234458.82
      2342981.59     13234888.98
#Sta/Elev= 30
  4679.9  138.54  4711.2  136.93    4784  132.28  4790.6  132.35  4802.3  130.57
  4830.3  128.93  4843.8  128.32  4858.7  128.83  4861.5  126.89  4904.5  124.57
  4917.8  122.95    4954  120.82  4960.5  120.38  4968.3  120.18  4982.6  116.63
  4995.4  112.52  5003.5  113.51    5010  115.53  5032.2  118.47  5067.3  118.96
    5096  120.75  5102.5  121.72  5131.2  121.85  5165.3  123.72  5189.2   124.4
  5202.9  124.59  5223.7   126.3  5252.4  126.16  5528.5  130.13  5534.9  130.28
#Mann= 8 ,-1 , 0
  4679.9      .1       0  4711.2     .05       0    4784      .1       0
  4960.5     .07       0    5096     .12       0  5165.3      .1       0
  5189.2     .05       0  5528.5      .1       0
Bank Sta=4954,5096
XS Rating Curve= 0 ,0
Exp/Cntr=0.3,0.1

Type RM Length L Ch R = 1 ,21489   ,483,483,483
BEGIN DESCRIPTION:
UNT020 IN PECR 43.0
END DESCRIPTION:
XS GIS Cut Line= 4
      2343225.38     13233784.11      2343066.17     13234022.92
      2342995.82     13234298.74       2342844.6     13234647.72
#Sta/Elev= 30
  4606.7  137.55    4622  137.08  4717.4  129.94    4773  125.66  4851.1  121.84
  4887.2  119.09  4893.1  118.69  4939.1  117.16  4980.3  114.25    4987  112.08
  4989.2  110.33    4992  109.83    5001  110.95  5011.3  113.91  5027.9  115.73
  5042.3  115.44  5052.6  116.97  5068.8   117.3    5074   118.4  5093.9  118.66
  5145.3  121.92  5178.4  122.76    5184  124.11  5192.8  123.72  5312.2  124.85
  5335.7     126  5382.7  125.58  5470.6  127.24  5516.4  129.53  5558.7     130
#Mann= 6 ,-1 , 0
  4606.7     .05       0  4717.4      .1       0  4893.1     .07       0
  5093.9     .12       0  5145.3      .1       0  5192.8     .05       0
Bank Sta=4887.2,5093.9
XS Rating Curve= 0 ,0
Exp/Cntr=0.3,0.1

Type RM Length L Ch R = 1 ,21006   ,212,212,212
BEGIN DESCRIPTION:
UNT020 IN PECR 42.0
END DESCRIPTION:
XS GIS Cut Line= 2
      2342890.39     13233561.02      2342213.42     13234441.95
#Sta/Elev= 30
  4542.9  139.26  4620.6  132.84  4641.2  130.14    4691  127.22  4705.6  125.32
  4713.8   126.1  4799.9  122.63  4837.8  121.16  4921.7  117.26  4969.3  115.36
  5004.3  108.39  5019.1  110.21  5027.3  113.17  5048.1  113.27  5062.6  115.27
  5083.5  114.09  5091.7   115.2    5098  114.24  5165.4  115.49  5172.7  115.45
  5287.3  116.23  5340.2  116.58  5409.1  117.68  5507.6  120.01  5533.9  120.68
  5590.1  124.89  5610.9  128.17  5639.9  130.97  5652.8  129.28  5653.9  129.24
#Mann= 14 ,-1 , 0
  4542.9     .05       0  4620.6     .08       0  4799.9      .1       0
  4837.8     .08       0  4921.7     .12       0  4969.3     .07       0
  5062.6      .1       0  5165.4     .05       0  5172.7     .08       0
  5287.3     .05       0  5340.2     .08       0  5409.1     .05       0
  5507.6     .08       0  5652.8     .05       0
Bank Sta=4969.3,5062.6
XS Rating Curve= 0 ,0
Exp/Cntr=0.3,0.1

Type RM Length L Ch R = 1 ,20794   ,253,253,253
BEGIN DESCRIPTION:
UNT020 IN PECR 41.0
END DESCRIPTION:
XS GIS Cut Line= 2
      2342738.51     13233404.73      2342013.65     13234385.68
#Sta/Elev= 30
  4463.2  135.08    4521  132.54  4593.6  126.09  4687.6   122.5  4751.4  118.72
  4837.9  116.93  4873.4  113.45  4879.6  112.96  4950.8  112.56  4965.2  109.59
  5000.4  106.68  5029.9  110.31  5037.8  112.13  5059.2  113.68  5121.3  114.32
  5180.2  113.94  5201.1  115.17  5274.8  116.51  5336.8  118.37  5345.2  117.42
  5382.4  117.12  5466.2  118.38  5502.7  121.15    5531  125.68  5551.8  125.51
  5581.1  128.14  5601.9  127.55  5631.2  130.16    5652  129.16  5682.9   131.9
#Mann= 9 ,-1 , 0
  4463.2     .08       0    4521     .16       0  4751.4     .08       0
  4879.6     .07       0  5059.2     .12       0  5121.3     .08       0
  5274.8     .12       0  5382.4     .08       0  5502.7      .1       0
Bank Sta=4873.4,5059.2
XS Rating Curve= 0 ,0
Exp/Cntr=0.3,0.1

Type RM Length L Ch R = 1 ,20541   ,335,335,335
BEGIN DESCRIPTION:
Mapping XS 5cd0a97a
END DESCRIPTION:
XS GIS Cut Line= 3
      2342537.51     13233451.92      2342159.04     13233722.75
      2341738.87     13234135.97
#Sta/Elev= 30
  4702.4  129.47  4713.9  129.23    4720  127.05  4740.9  122.34  4755.7  120.12
  4776.5  118.86  4808.7  113.84  4820.8  111.77  4841.7  110.43  4862.5  110.65
  4906.8  113.04  4912.9  112.91  4927.7  112.44  4942.4  110.65  4998.7  106.82
  5043.1  110.05  5093.5  109.61  5129.1  110.57    5150  109.51  5249.4  108.81
  5277.7  109.38  5320.1  113.04  5476.2  116.86  5525.2  120.45  5546.4  120.05
  5560.6   121.2  5666.6   123.6  5687.9  125.44  5723.2  130.23  5757.1  128.81
#Mann= 5 ,-1 , 0
  4702.4     .16       0  4808.7     .12       0  4912.9     .07       0
  5320.1     .12       0  5476.2     .05       0
Bank Sta=4906.8,5320.1
XS Rating Curve= 0 ,0
Exp/Cntr=0.3,0.1