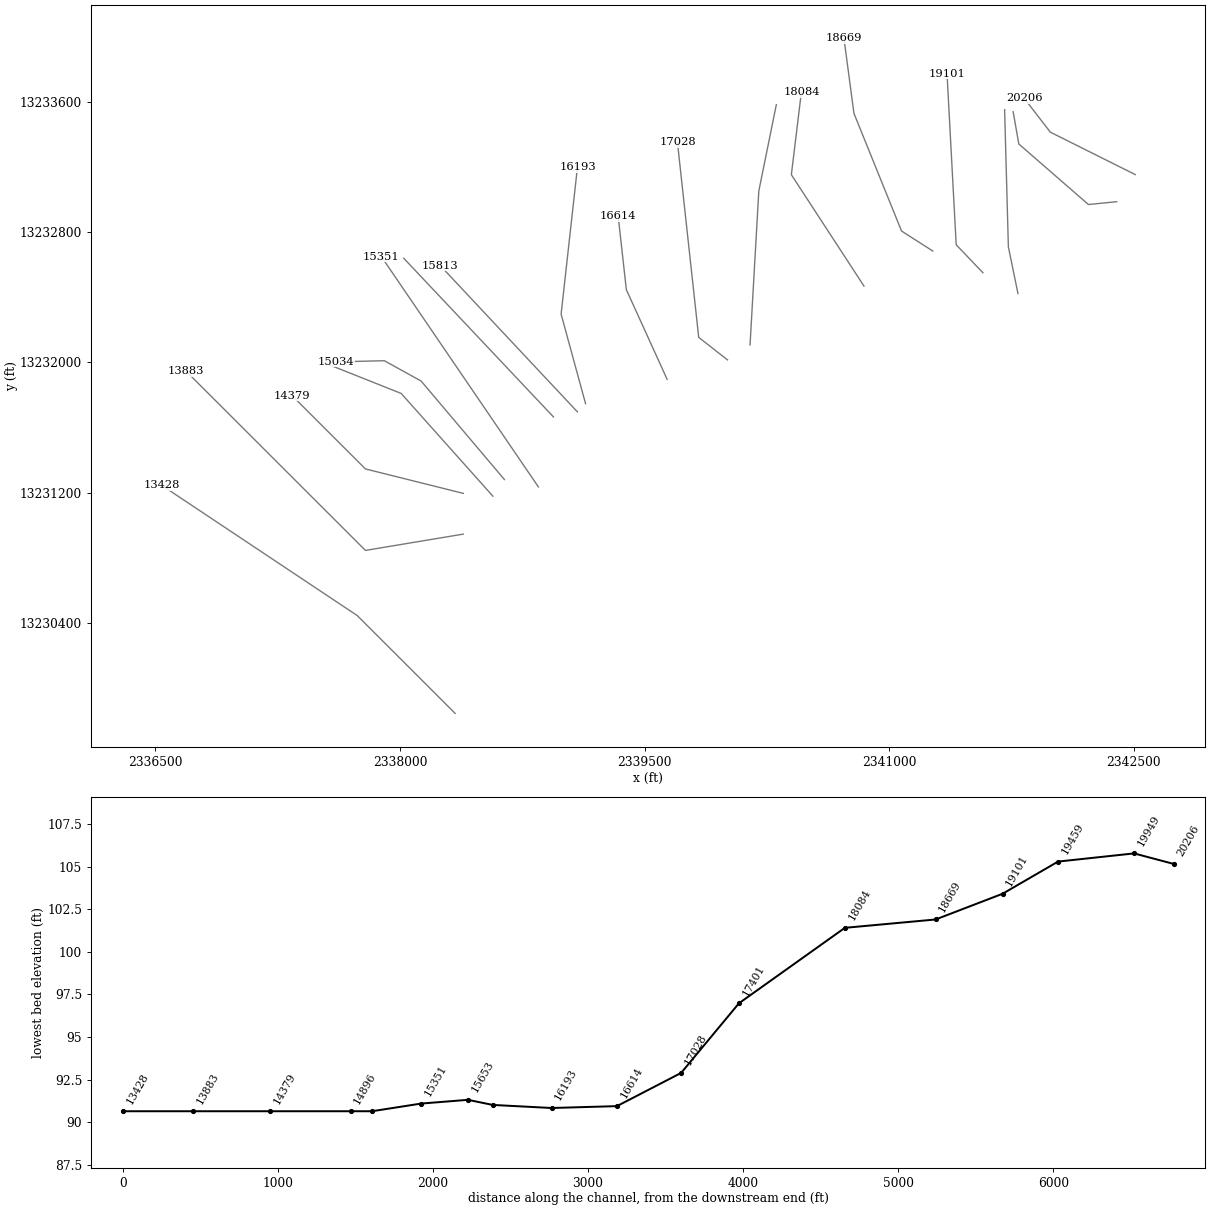
HEC-RAS study UNT020 IN PECR.prj: UNT020 IN PECR Base Level Engineering

--- UNT020 IN PECR.g01 (geometry) --- (continued)

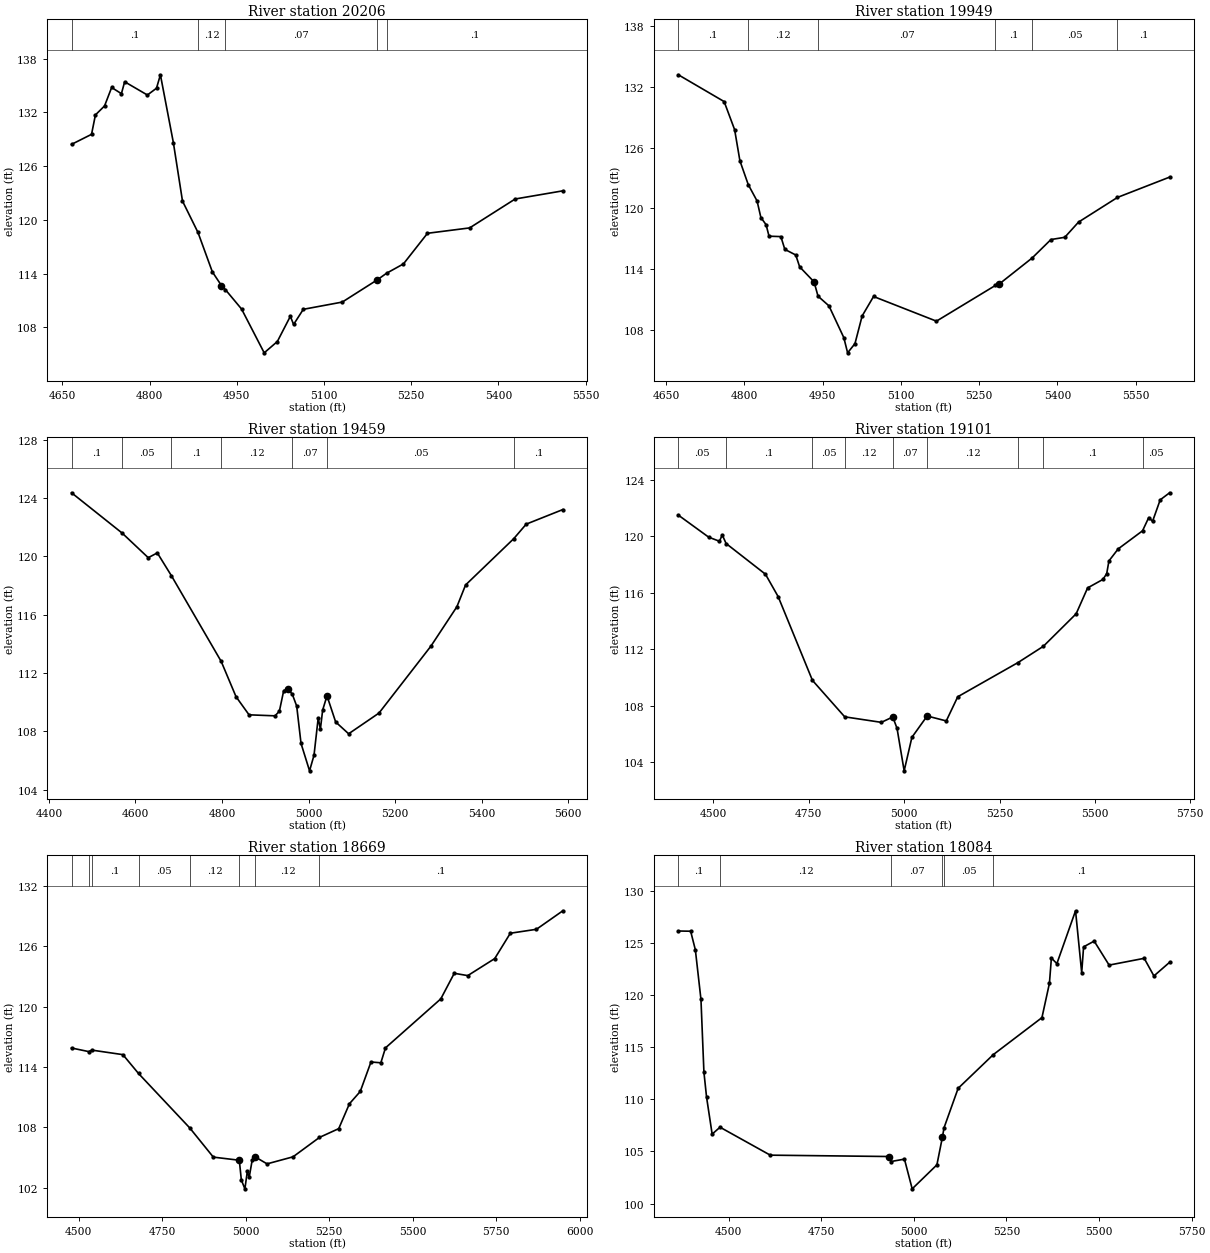
Type RM Length L Ch R = 1 ,20206   ,257,257,257
BEGIN DESCRIPTION:
UNT020 IN PECR 40.0
END DESCRIPTION:
XS GIS Cut Line= 3
      2342508.49     13233153.01      2341987.61     13233413.45
      2341827.02     13233621.79
#Sta/Elev= 30
  4665.6  128.44    4700  129.56  4706.7  131.73  4722.4  132.73  4734.6  134.79
  4751.4   134.1    4757  135.43  4796.1  133.95  4811.8  134.71  4818.5  136.21
  4840.8  128.64  4856.5  122.11  4883.2   118.6  4907.9   114.2  4923.6  112.67
  4930.3  112.22  4958.2  110.05  4997.1  105.16  5019.7  106.42  5042.1  109.24
  5047.7  108.33  5064.4  110.02  5131.5  110.83  5191.9  113.32  5207.7  114.05
  5236.7  115.09  5278.1  118.51  5350.6  119.11    5429  122.34    5511  123.25
#Mann= 5 ,-1 , 0
  4665.6      .1       0  4883.2     .12       0  4930.3     .07       0
  5191.9     .12       0  5207.7      .1       0
Bank Sta=4923.6,5191.9
XS Rating Curve= 0 ,0
Exp/Cntr=0.3,0.1

Type RM Length L Ch R = 1 ,19949   ,490,490,490
BEGIN DESCRIPTION:
UNT020 IN PECR 39.0
END DESCRIPTION:
XS GIS Cut Line= 4
       2342395.1     13232986.64      2342221.54     13232969.28
      2341794.45     13233340.81      2341759.74     13233538.68
#Sta/Elev= 30
  4673.6  133.17  4761.4  130.53  4781.5  127.76  4791.6   124.7  4807.6  122.35
  4824.5  120.74  4831.8  119.11  4841.8   118.4  4847.4  117.27  4870.1  117.23
  4877.7  115.97  4898.6  115.42  4906.1  114.25  4933.7  112.77  4941.3  111.36
  4962.2  110.41  4990.7  107.28    4998  105.78  5012.1  106.69  5025.8  109.41
  5047.7  111.33  5168.2   108.9  5281.2  112.42  5288.8  112.57  5351.5  115.12
  5387.6  116.94  5414.1  117.16  5440.5  118.66  5515.1  121.09    5615  123.09
#Mann= 6 ,-1 , 0
  4673.6      .1       0  4807.6     .12       0  4941.3     .07       0
  5281.2      .1       0  5351.5     .05       0  5515.1      .1       0
Bank Sta=4933.7,5288.8
XS Rating Curve= 0 ,0
Exp/Cntr=0.3,0.1

Type RM Length L Ch R = 1 ,19459   ,358,358,358
BEGIN DESCRIPTION:
UNT020 IN PECR 38.0
END DESCRIPTION:
XS GIS Cut Line= 3
      2341789.29     13232422.84      2341730.43     13232709.47
       2341707.4     13233551.44
#Sta/Elev= 30
  4452.4  124.36  4569.2   121.6  4629.6  119.91  4650.5  120.24  4683.2  118.67
  4798.1   112.8  4832.4  110.38  4862.4  109.14  4922.5  109.07  4932.5  109.39
  4942.5   110.8  4952.5  110.92  4962.5  110.54  4972.5  109.74  4982.5  107.18
  5002.2   105.3  5012.5  106.37  5022.2  108.93  5027.2  108.15  5032.5  109.47
  5042.5  110.44  5062.5  108.65  5092.5  107.84  5162.6  109.26  5282.6  113.85
  5342.6  116.55  5362.6  118.04  5474.1  121.22  5502.7  122.21  5587.3  123.21
#Mann= 7 ,-1 , 0
  4452.4      .1       0  4569.2     .05       0  4683.2      .1       0
  4798.1     .12       0  4962.5     .07       0  5042.5     .05       0
  5474.1      .1       0
Bank Sta=4952.5,5042.5
XS Rating Curve= 0 ,0
Exp/Cntr=0.3,0.1

Type RM Length L Ch R = 1 ,19101   ,432,432,432
BEGIN DESCRIPTION:
UNT020 IN PECR 37.0
END DESCRIPTION:
XS GIS Cut Line= 3
      2341574.34     13232550.78      2341410.53     13232722.26
      2341354.23      13233771.5
#Sta/Elev= 30
  4407.9   121.5  4487.5  119.94  4515.8  119.65    4523   120.1  4533.2  119.49
  4636.3  117.32  4669.7  115.73  4759.5  109.81  4844.1  107.23  4940.1  106.84
  4970.1  107.22  4981.3  106.41  4999.9  103.41  5020.2  105.78  5060.2  107.29
  5110.3  106.94  5140.4  108.65  5298.4  111.07  5364.8  112.22  5450.8  114.52
  5480.8  116.35  5520.9  116.95  5530.9  117.36  5536.7  118.26    5561  119.11
  5624.8  120.39  5641.1  121.33  5651.1  121.06  5671.1  122.58  5695.8  123.08
#Mann= 9 ,-1 , 0
  4407.9     .05       0  4533.2      .1       0  4759.5     .05       0
  4844.1     .12       0  4970.1     .07       0  5060.2     .12       0
  5298.4     .05       0  5364.8      .1       0  5624.8     .05       0
Bank Sta=4970.1,5060.2
XS Rating Curve= 0 ,0
Exp/Cntr=0.3,0.1

Type RM Length L Ch R = 1 ,18669   ,585,585,585
BEGIN DESCRIPTION:
UNT020 IN PECR 36.0
END DESCRIPTION:
XS GIS Cut Line= 4
      2341267.19     13232683.89      2341075.28     13232806.71
      2340783.54      13233528.4      2340722.12     13233989.05
#Sta/Elev= 30
  4478.3  115.89  4530.1  115.53  4539.1  115.68    4632  115.23  4678.8  113.36
  4832.5  107.94  4902.8  105.05  4980.6  104.74  4986.7  102.78  4997.3   101.9
  5004.7  103.65  5010.1  103.03  5019.1  104.74  5028.8  105.06  5063.7  104.38
  5141.5  105.08  5220.7  107.01  5278.3  107.88  5310.3  110.35  5342.7  111.57
  5374.8   114.5  5404.4  114.42  5418.2   115.9  5583.9  120.77  5624.2  123.31
  5664.6  123.08  5745.3  124.77  5792.1  127.29  5870.2  127.68  5949.3  129.52
#Mann= 8 ,-1 , 0
  4478.3      .1       0  4530.1     .05       0  4539.1      .1       0
  4678.8     .05       0  4832.5     .12       0  4980.6     .07       0
  5028.8     .12       0  5220.7      .1       0
Bank Sta=4980.6,5028.8
XS Rating Curve= 0 ,0
Exp/Cntr=0.3,0.1

Type RM Length L Ch R = 1 ,18084   ,683,683,683
BEGIN DESCRIPTION:
UNT020 IN PECR 35.0
END DESCRIPTION:
XS GIS Cut Line= 3
      2340844.94     13232468.94      2340399.66      13233152.2
      2340461.09     13233658.94
#Sta/Elev= 30
  4364.5  126.14  4397.8  126.12  4410.5  124.33  4425.6  119.58  4433.6   112.6
  4440.7  110.21  4455.8  106.66  4477.1  107.32  4612.7  104.64  4932.7  104.51
  4938.6  104.03  4974.8  104.26  4995.7  101.41  5062.4  103.71  5077.5  106.41
  5081.6  107.26  5119.7  111.05  5214.5  114.28  5345.9  117.83  5366.1  121.12
  5371.4  123.55  5386.2  123.01  5436.6  128.08  5453.2  122.14  5458.3  124.62
  5486.9  125.17  5527.2  122.87  5621.9  123.52  5648.1  121.83  5690.5  123.14
#Mann= 6 ,-1 , 0
  4364.5      .1       0  4477.1     .12       0  4938.6     .07       0
  5077.5     .12       0  5081.6     .05       0  5214.5      .1       0
Bank Sta=4932.7,5077.5
XS Rating Curve= 0 ,0
Exp/Cntr=0.3,0.1

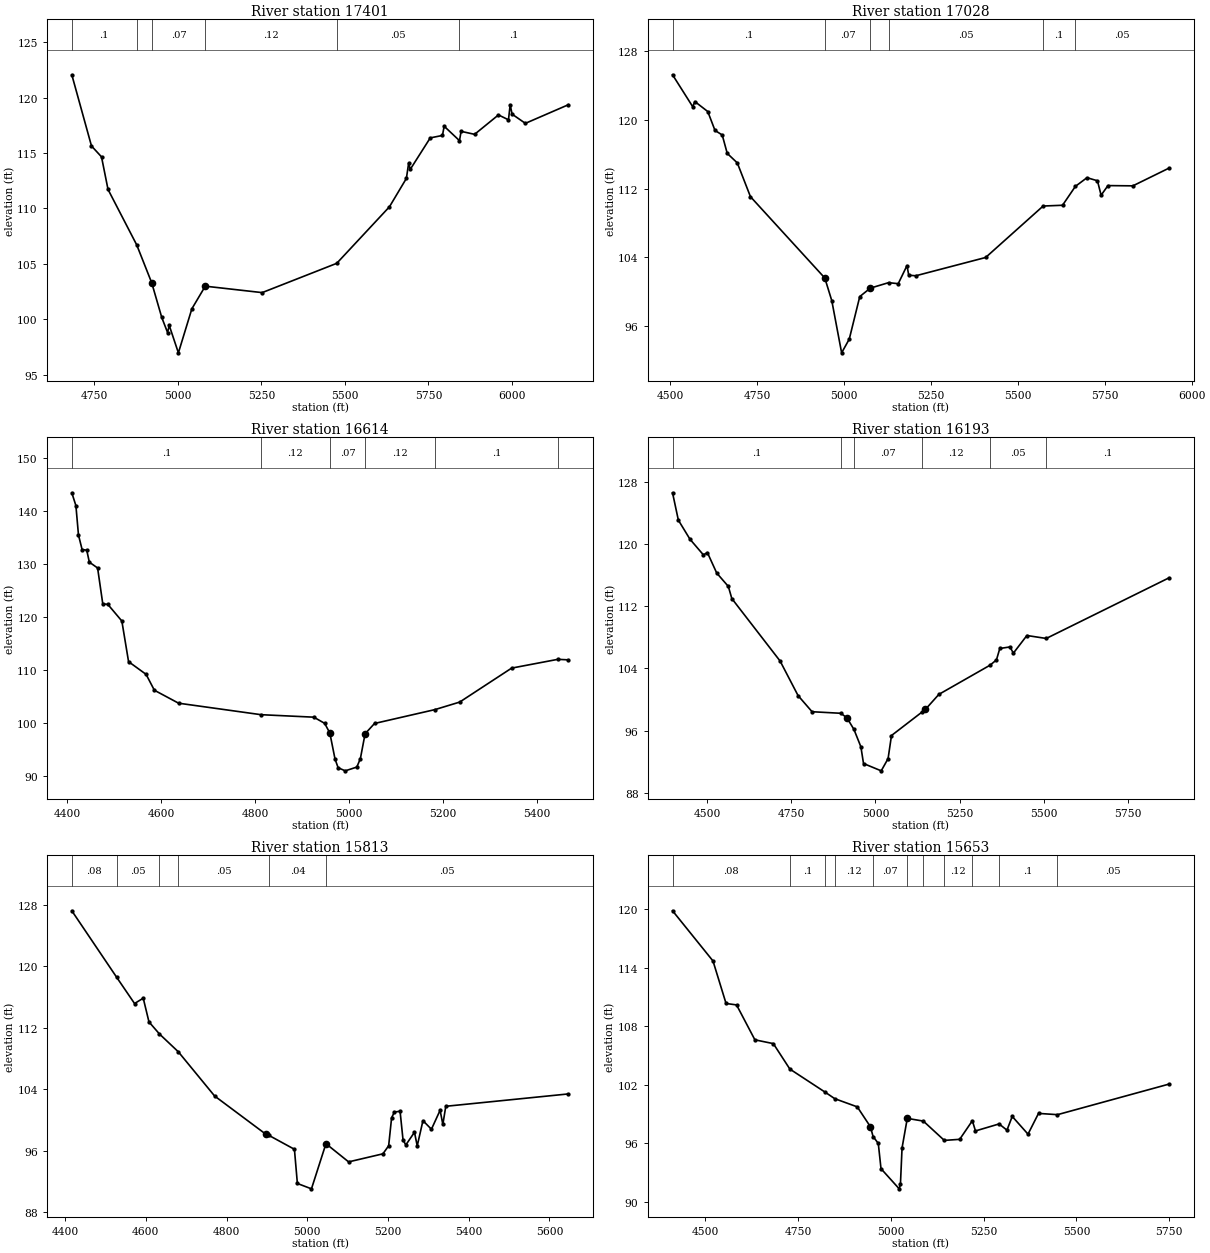
Type RM Length L Ch R = 1 ,17401   ,373,373,373
BEGIN DESCRIPTION:
UNT020 IN PECR 34.0
END DESCRIPTION:
XS GIS Cut Line= 3
      2340146.31     13232108.09      2340200.05     13233052.39
       2340307.5     13233581.97
#Sta/Elev= 30
  4682.5  122.05  4741.4  115.63  4771.4  114.65  4790.9  111.71  4876.8  106.71
  4921.7  103.29  4951.7  100.17  4969.1   98.81  4974.1   99.45  5001.5   96.98
  5041.8  100.95  5081.9  102.99  5252.2  102.41  5475.4  105.05  5633.2  110.15
  5683.9  112.71  5690.5  114.06  5695.6  113.53  5755.3  116.36  5791.8  116.58
  5796.9  117.41  5842.8  116.11  5847.6  116.95    5888  116.68  5959.4  118.43
  5989.4  117.99  5994.5  119.35  6000.2   118.5    6040  117.67  6168.7  119.35
#Mann= 6 ,-1 , 0
  4682.5      .1       0  4876.8     .12       0  4921.7     .07       0
  5081.9     .12       0  5475.4     .05       0  5842.8      .1       0
Bank Sta=4921.7,5081.9
XS Rating Curve= 0 ,0
Exp/Cntr=0.3,0.1

Type RM Length L Ch R = 1 ,17028   ,414,414,414
BEGIN DESCRIPTION:
UNT020 IN PECR 33.0
END DESCRIPTION:
XS GIS Cut Line= 3
      2340008.12     13232015.92      2339831.53     13232154.13
      2339701.01     13233351.79
#Sta/Elev= 30
  4506.1  125.26  4564.1  121.55  4570.4  122.14  4607.5  120.98  4628.3  118.78
  4649.1  118.25  4663.5  116.11  4692.5     115  4730.3  111.07  4944.3   101.6
  4964.4   98.96  4992.7   92.89  5014.7   94.49  5044.9   99.44  5075.1  100.42
  5127.8  101.06  5155.6  100.94  5180.8  103.05  5185.8  101.93  5205.9  101.86
  5407.1  103.99  5572.6  109.98  5628.4  110.07  5665.4  112.27  5698.8  113.28
  5728.9  112.92  5739.4  111.24  5759.1  112.36  5830.8  112.33  5935.1   114.4
#Mann= 6 ,-1 , 0
  4506.1      .1       0  4944.3     .07       0  5075.1     .12       0
  5127.8     .05       0  5572.6      .1       0  5665.4     .05       0
Bank Sta=4944.3,5075.1
XS Rating Curve= 0 ,0
Exp/Cntr=0.3,0.1

Type RM Length L Ch R = 1 ,16614   ,421,421,421
BEGIN DESCRIPTION:
UNT020 IN PECR 32.0
END DESCRIPTION:
XS GIS Cut Line= 3
       2339637.7      13231896.9      2339387.72     13232446.85
      2339337.72     13232896.88
#Sta/Elev= 30
    4410  143.48  4418.7  141.06  4424.2  135.49  4431.9  132.76  4441.8  132.63
  4447.3  130.37  4464.9  129.27  4475.9   122.5  4486.8  122.38  4516.5  119.25
  4530.8  111.57  4568.1  109.17  4585.7  106.17  4637.3  103.72  4812.7  101.55
  4925.1  101.08  4948.2   99.91  4959.2   98.08  4970.2   93.18  4976.8   91.53
  4991.9   90.94  5016.6   91.65  5024.2   93.25  5034.2   97.94  5054.3   99.89
  5182.9  102.51  5235.5  103.93  5346.1  110.35  5444.5  112.01  5466.9  111.91
#Mann= 6 ,-1 , 0
    4410      .1       0  4812.7     .12       0  4959.2     .07       0
  5034.2     .12       0  5182.9      .1       0  5444.5     .05       0
Bank Sta=4959.2,5034.2
XS Rating Curve= 0 ,0
Exp/Cntr=0.3,0.1

Type RM Length L Ch R = 1 ,16193   ,380,380,380
BEGIN DESCRIPTION:
UNT020 IN PECR 31.0
END DESCRIPTION:
XS GIS Cut Line= 3
      2339137.72     13231746.86      2338987.72     13232296.85
      2339087.72     13233196.83
#Sta/Elev= 30
  4396.9  126.58  4414.2  123.06  4448.7  120.61  4488.5   118.6  4500.5  118.89
  4528.2  116.26  4562.7  114.54  4573.1  112.98  4716.5  104.95    4770   100.5
  4811.5   98.43  4897.1   98.23  4915.2   97.64  4935.9   96.16  4956.6   93.92
  4964.4   91.77    5017   90.83  5037.4    92.4  5047.5   95.37    5138   98.38
  5148.1   98.72  5188.3  100.66  5340.3  104.41  5359.4  105.09  5369.4  106.56
  5399.6  106.76  5409.7  105.96  5449.9  108.23  5507.4  107.85  5872.5  115.65
#Mann= 6 ,-1 , 0
  4396.9      .1       0  4897.1     .12       0  4935.9     .07       0
    5138     .12       0  5340.3     .05       0  5507.4      .1       0
Bank Sta=4915.2,5148.1
XS Rating Curve= 0 ,0
Exp/Cntr=0.3,0.1

Type RM Length L Ch R = 1 ,15813   ,160,160,160
BEGIN DESCRIPTION:
UNT020 IN PECR 30.0
END DESCRIPTION:
XS GIS Cut Line= 2
       2339087.7     13231696.88      2338246.29     13232594.88
#Sta/Elev= 30
  4416.5  127.22  4527.9  118.54    4572  115.14  4593.5  115.84  4607.7  112.75
  4633.8  111.17  4680.4  108.86  4770.4   103.1  4897.4   98.12  4904.7   97.98
  4968.2   96.16  4975.5   91.71  5010.4   91.01  5046.3   96.89  5102.5   94.52
  5187.5   95.57  5201.7   96.62    5209  100.26  5215.8     101    5230  101.12
  5237.3    97.4  5244.2   96.72  5265.7   98.38  5272.5    96.6  5286.7   99.89
  5307.7   98.77  5329.2  101.24    5336    99.4  5343.3  101.76  5647.1  103.37
#Mann= 6 ,-1 , 0
  4416.5     .08       0  4527.9     .05       0  4633.8     .08       0
  4680.4     .05       0  4904.7     .04       0  5046.3     .05       0
Bank Sta=4897.4,5046.3
XS Rating Curve= 0 ,0
Exp/Cntr=0.3,0.1

Type RM Length L Ch R = 1 ,15653   ,302,302,302
BEGIN DESCRIPTION:
Mapping XS 12516243
END DESCRIPTION:
XS GIS Cut Line= 2
      2338940.77     13231666.02      2338022.74      13232639.4
#Sta/Elev= 30
  4411.7  119.84  4520.7  114.69  4555.9  110.33  4584.2  110.18  4633.6   106.6
  4683.3  106.21  4727.8   103.6  4823.2  101.22  4848.8  100.56  4909.5   99.72
  4945.1   97.67    4952   96.68  4966.1   95.97  4973.4   93.38  5022.5   91.31
  5025.8   91.81  5030.1    95.5  5044.2   98.54  5087.5   98.26    5144   96.28
  5185.4   96.39  5219.6    98.3  5227.9   97.25  5291.6   97.97  5312.8   97.33
    5327   98.74  5369.5   96.92  5397.8   99.05  5448.9   98.92  5749.7  102.06
#Mann= 11 ,-1 , 0
  4411.7     .08       0  4727.8      .1       0  4823.2     .08       0
  4848.8     .12       0    4952     .07       0  5044.2     .12       0
  5087.5     .08       0    5144     .12       0  5219.6     .08       0
  5291.6      .1       0  5448.9     .05       0
Bank Sta=4945.1,5044.2
XS Rating Curve= 0 ,0
Exp/Cntr=0.3,0.1

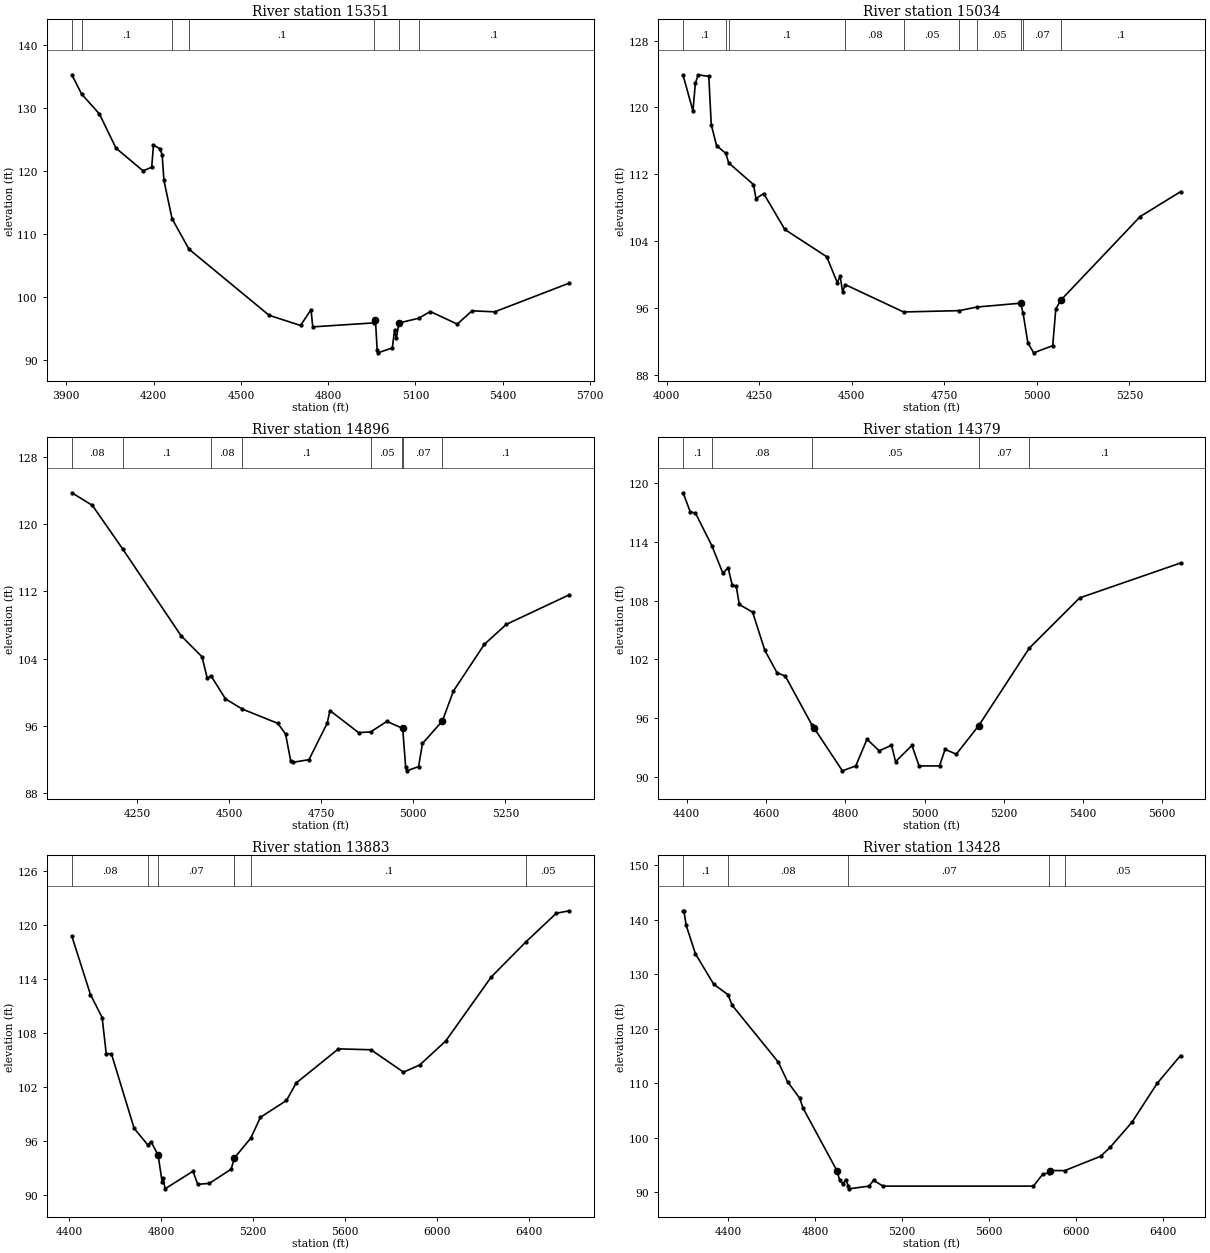
Type RM Length L Ch R = 1 ,15351   ,317,317,317
BEGIN DESCRIPTION:
Mapping XS 21298d9a
END DESCRIPTION:
XS GIS Cut Line= 2
       2338848.3      13231236.5      2337885.59     13232649.52
#Sta/Elev= 30
    3919   135.3  3952.7  132.23  4013.9  129.06  4070.8  123.63  4163.6  120.03
  4193.5  120.59  4199.5  124.12  4221.9  123.54  4229.4  122.56  4235.5  118.51
  4263.4  112.42  4321.5  107.58    4597   97.06  4705.1   95.44    4741   97.95
  4747.1   95.22  4956.5   95.85  4962.6   96.25  4968.4   91.59  4971.2   91.09
  5020.6   91.88  5028.3   94.73  5034.4   93.38  5043.3   95.84  5111.3   96.59
    5151   97.66  5243.8   95.66  5294.6   97.77  5372.5   97.61  5628.8  102.18
#Mann= 7 ,-1 , 0
    3919     .05       0  3952.7      .1       0  4263.4     .08       0
  4321.5      .1       0  4956.5     .07       0  5043.3     .12       0
  5111.3      .1       0
Bank Sta=4962.6,5043.3
XS Rating Curve= 0 ,0
Exp/Cntr=0.3,0.1

Type RM Length L Ch R = 1 ,15034   ,138,138,138
BEGIN DESCRIPTION:
UNT020 IN PECR 29.0
END DESCRIPTION:
XS GIS Cut Line= 4
      2338639.95     13231281.67      2338129.54     13231885.82
      2337903.85     13232010.82      2337608.72     13232003.87
#Sta/Elev= 30
  4044.2  123.85  4070.8  119.57  4077.3  122.92  4085.1  123.91  4113.6  123.71
  4120.2  117.96  4134.5  115.44  4159.7   114.5  4167.3  113.37  4234.3  110.78
  4241.1   109.1  4261.9   109.7  4319.1   105.4  4432.2  102.14  4460.8   99.04
  4468.6   99.81  4475.1   97.94  4482.4    98.8  4639.9   95.53  4790.6   95.69
  4837.8   96.12  4956.1   96.58  4962.9   95.37  4975.7   91.84  4991.5   90.64
  5042.9    91.5  5051.3   95.91  5065.8   96.99  5279.3  106.95  5388.3  109.92
#Mann= 10 ,-1 , 0
  4044.2      .1       0  4159.7     .08       0  4167.3      .1       0
  4482.4     .08       0  4639.9     .05       0  4790.6      .1       0
  4837.8     .05       0  4956.1      .1       0  4962.9     .07       0
  5065.8      .1       0
Bank Sta=4956.1,5065.8
XS Rating Curve= 0 ,0
Exp/Cntr=0.3,0.1

Type RM Length L Ch R = 1 ,14896   ,517,517,517
BEGIN DESCRIPTION:
UNT020 IN PECR 28.0
END DESCRIPTION:
XS GIS Cut Line= 3
      2338569.21     13231179.66      2338006.88     13231810.09
      2337537.68     13231996.87
#Sta/Elev= 30
  4073.7  123.73  4129.4  122.23  4211.2  117.07  4370.2  106.71    4427  104.21
  4441.2  101.63  4451.2  101.96  4490.6    99.2  4535.7      98  4632.7   96.29
  4653.6   95.02  4667.8   91.78  4674.5   91.66  4717.1   91.97  4766.7   96.32
    4774   97.82  4851.7   95.19  4884.2   95.27  4928.5   96.52  4970.8   95.71
  4971.4    95.7  4979.4   91.14  4982.2   90.64  5014.5   91.14  5025.2    93.9
    5079   96.56  5109.2  100.14  5192.8  105.68  5252.2  108.06  5423.5  111.59
#Mann= 8 ,-1 , 0
  4073.7     .08       0  4211.2      .1       0  4451.2     .08       0
  4535.7      .1       0  4884.2     .05       0  4970.8     .07       0
  4971.4     .07       0    5079      .1       0
Bank Sta=4971.4,5079
XS Rating Curve= 0 ,0
Exp/Cntr=0.3,0.1

Type RM Length L Ch R = 1 ,14379   ,496,496,496
BEGIN DESCRIPTION:
UNT020 IN PECR 27.0
END DESCRIPTION:
XS GIS Cut Line= 3
      2338387.76     13231196.84      2337787.72     13231346.85
      2337337.72     13231796.85
#Sta/Elev= 30
    4391  118.99  4409.1  117.03    4422  116.93  4463.3  113.61  4491.5  110.77
  4504.4  111.37  4514.7   109.6    4525  109.44  4532.8   107.6  4566.3  106.82
  4597.2  102.92  4628.1  100.63  4648.7  100.31  4715.8   95.33  4720.9   95.04
  4792.8   90.64  4826.5   91.14  4854.9   93.86  4885.8   92.68  4916.7   93.25
    4927   91.58  4968.3   93.23  4986.3   91.14  5037.8   91.14  5051.9   92.83
  5080.2   92.34  5136.8   95.25  5264.1  103.14  5391.3  108.27  5645.9  111.83
#Mann= 5 ,-1 , 0
    4391      .1       0  4463.3     .08       0  4715.8     .05       0
  5136.8     .07       0  5264.1      .1       0
Bank Sta=4720.9,5136.8
XS Rating Curve= 0 ,0
Exp/Cntr=0.3,0.1

Type RM Length L Ch R = 1 ,13883   ,455,455,455
BEGIN DESCRIPTION:
UNT020 IN PECR 26.0
END DESCRIPTION:
XS GIS Cut Line= 3
      2338387.67     13230946.85      2337787.72     13230846.85
      2336687.69     13231946.88
#Sta/Elev= 30
  4412.5  118.78  4493.6  112.27  4544.2  109.72    4562  105.71  4584.8  105.66
  4683.6   97.37  4742.9   95.53  4757.1   95.89  4787.6    94.4  4805.3    91.4
  4810.4   91.82  4817.7   90.64  4939.6    92.6  4959.9   91.14  5010.6   91.25
  5105.6   92.83  5119.7   94.08  5191.1    96.3  5232.9   98.61    5346  100.48
  5388.4  102.43  5572.3  106.23  5713.7  106.13  5855.1  103.64  5925.8  104.43
    6039  107.11    6237  114.24    6388  118.15  6519.8  121.33  6576.4  121.61
#Mann= 6 ,-1 , 0
  4412.5     .08       0  4742.9     .07       0  4787.6     .07       0
  5119.7     .07       0  5191.1      .1       0    6388     .05       0
Bank Sta=4787.6,5119.7
XS Rating Curve= 0 ,0
Exp/Cntr=0.3,0.1

Type RM Length L Ch R = 1 ,13428   ,491,491,491
BEGIN DESCRIPTION:
UNT020 IN PECR 25.0
END DESCRIPTION:
XS GIS Cut Line= 3
      2338337.72     13229846.85      2337737.72     13230446.85
      2336537.68     13231246.88
#Sta/Elev= 30
  4191.2  141.61  4194.7  141.61  4205.3  138.96  4247.8  133.73  4332.6  128.12
  4397.5  126.25  4417.5  124.27  4629.6  113.87    4672  110.29  4728.6  107.22
  4742.7   105.5 4900.39   93.91  4912.5   92.17  4926.6   91.56  4940.7   92.32
  4951.9   91.14  4954.6   90.64  5047.2   91.14  5068.3    92.2  5111.8   91.14
  5804.4   91.14  5846.5   93.28  5876.5   93.62  5882.5      94  5948.5   93.98
  6113.9   96.61  6157.5   98.24  6258.1  102.84  6373.8  109.95    6482  115.08
#Mann= 5 ,-1 , 0
  4191.2      .1       0  4397.5     .08       0  4951.9     .07       0
  5876.5     .07       0  5948.5     .05       0
Bank Sta=4900.39,5882.5
XS Rating Curve= 0 ,0
Exp/Cntr=0.3,0.1