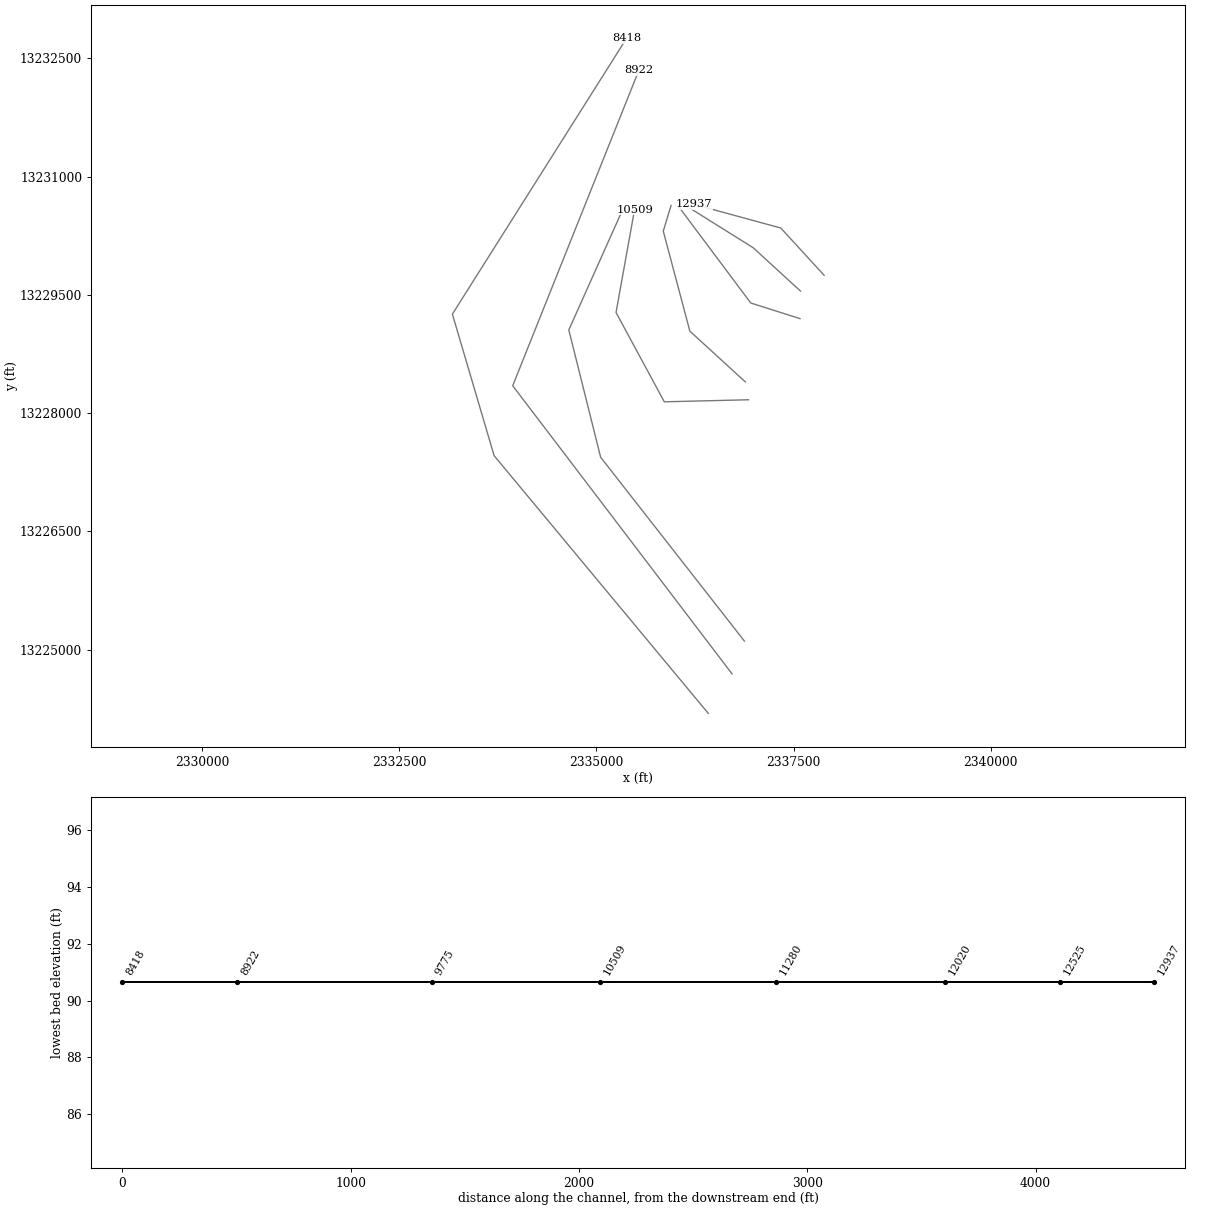
HEC-RAS study UNT020 IN PECR.prj: UNT020 IN PECR Base Level Engineering

--- UNT020 IN PECR.g01 (geometry) --- (continued)

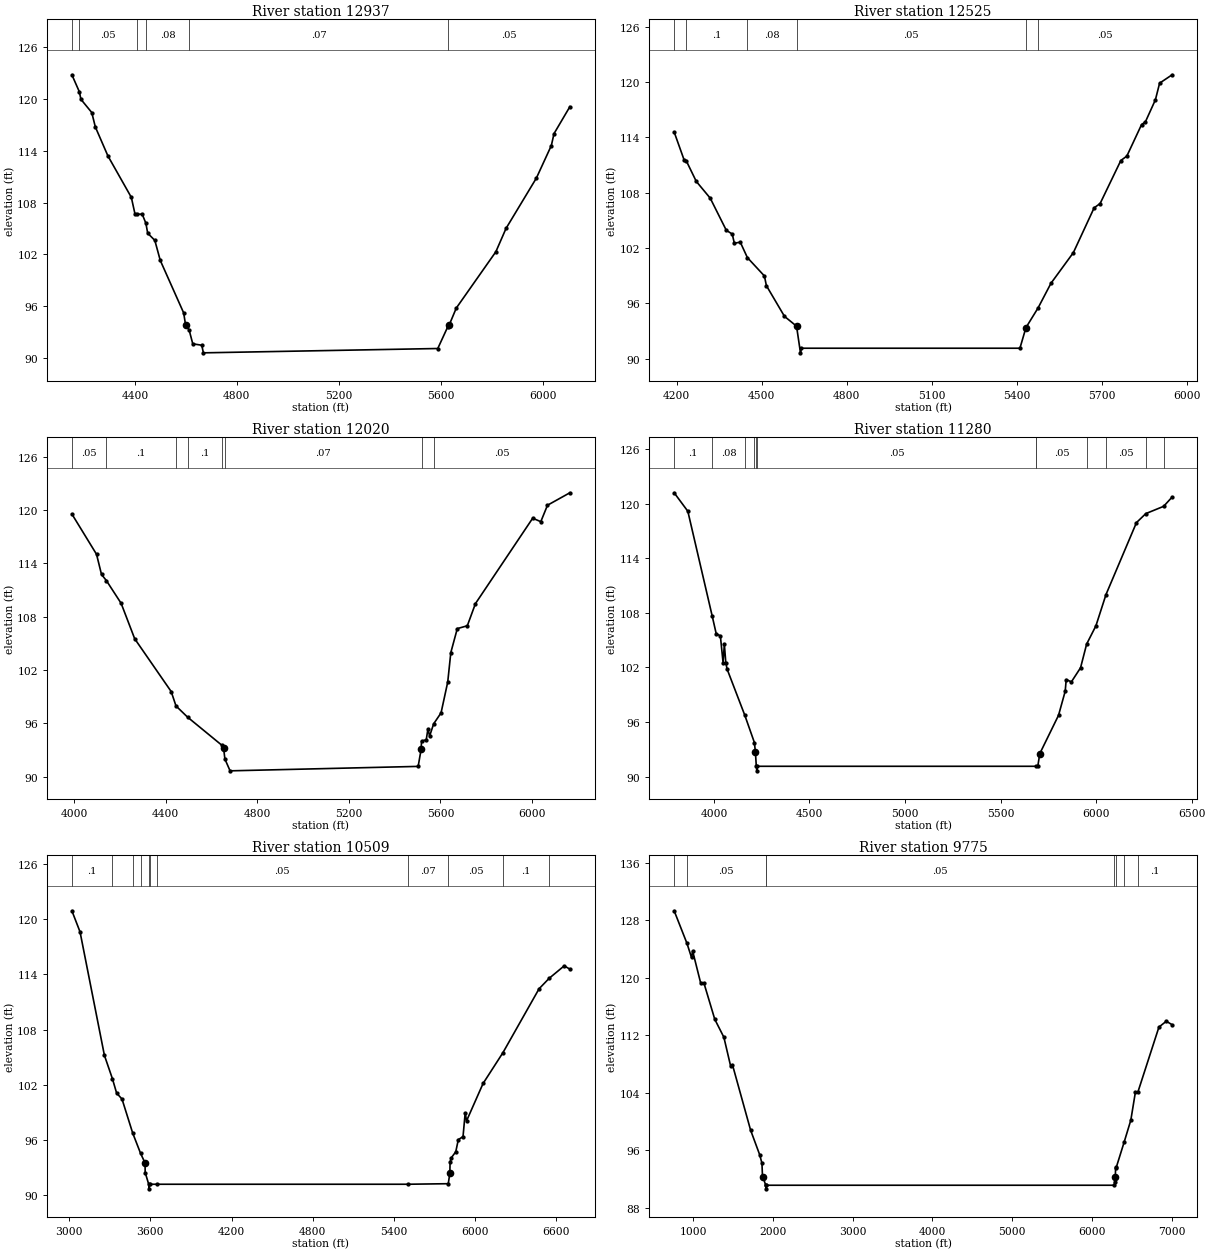
Type RM Length L Ch R = 1 ,12937   ,412,412,412
BEGIN DESCRIPTION:
UNT020 IN PECR 24.0
END DESCRIPTION:
XS GIS Cut Line= 3
      2337887.69     13229746.89      2337337.72     13230346.85
      2336237.69     13230646.86
#Sta/Elev= 30
  4152.9  122.76  4182.3  120.79  4188.3  119.93  4230.9   118.4    4245  116.73
  4294.4  113.38  4386.2   108.6  4400.4   106.7  4408.9  106.65  4428.8  106.66
  4443.3  105.61  4450.4  104.46  4478.4  103.63  4499.7  101.32  4591.6   95.25
    4599   93.87  4613.2   93.26  4627.3   91.68  4662.5   91.52    4669   90.64
  5588.7   91.14  5628.4   93.68  5633.6   93.86  5661.3   95.81  5816.7  102.32
  5856.5  105.01  5975.7  110.83  6034.4  114.59  6044.8  115.96    6107  119.07
#Mann= 6 ,-1 , 0
  4152.9      .1       0  4182.3     .05       0  4408.9      .1       0
  4443.3     .08       0  4613.2     .07       0  5628.4     .05       0
Bank Sta=4599,5633.6
XS Rating Curve= 0 ,0
Exp/Cntr=0.3,0.1

Type RM Length L Ch R = 1 ,12525   ,505,505,505
BEGIN DESCRIPTION:
UNT020 IN PECR 23.0
END DESCRIPTION:
XS GIS Cut Line= 3
       2337587.7     13229546.88      2336987.72     13230096.85
      2336187.72     13230596.85
#Sta/Elev= 30
  4191.2  114.57  4226.6  111.52  4233.8  111.46  4269.2  109.22  4318.5   107.4
  4375.2  103.92  4396.2  103.51  4403.6  102.52  4424.6  102.63  4449.6  100.96
  4509.7   98.97  4516.7   97.92  4580.6   94.59  4623.1   93.53    4637   90.64
  4640.3   91.14  5411.4   91.14  5432.6   93.37  5475.3    95.5    5521   98.18
    5600   101.5  5673.2  106.35  5694.4  106.82  5767.5  111.48  5788.7  111.96
  5840.6  115.37  5854.2  115.67  5889.5  118.06  5904.3  119.86  5948.5  120.77
#Mann= 6 ,-1 , 0
  4191.2     .05       0  4233.8      .1       0  4449.6     .08       0
  4623.1     .05       0  5432.6     .07       0  5475.3     .05       0
Bank Sta=4623.1,5432.6
XS Rating Curve= 0 ,0
Exp/Cntr=0.3,0.1

Type RM Length L Ch R = 1 ,12020   ,740,740,740
BEGIN DESCRIPTION:
UNT020 IN PECR 22.0
END DESCRIPTION:
XS GIS Cut Line= 3
      2337581.05     13229197.88      2336956.93     13229396.02
      2336046.53     13230613.19
#Sta/Elev= 30
  3990.3  119.53    4098     115  4119.7  112.73  4140.8  112.05  4205.3  109.49
  4264.6   105.5    4424   99.56    4445   97.94  4495.6   96.68  4645.7   93.51
 4652.95   93.16  4658.7   91.96  4681.2   90.64  5502.6   91.14 5515.77   93.09
  5517.2   93.97    5538   94.14  5545.3   95.36  5552.6   94.55  5570.3   95.93
  5602.6   97.16  5631.8  100.64  5645.2  103.94  5673.5  106.64  5717.3  106.96
  5752.7  109.45  6002.8  119.06  6038.2  118.67  6067.4  120.52  6165.1  121.92
#Mann= 8 ,-1 , 0
  3990.3     .05       0  4140.8      .1       0    4445     .08       0
  4495.6      .1       0  4645.7     .07       0  4658.7     .07       0
  5517.2     .07       0  5570.3     .05       0
Bank Sta=4652.95,5515.77
XS Rating Curve= 0 ,0
Exp/Cntr=0.3,0.1

Type RM Length L Ch R = 1 ,11280   ,771,771,771
BEGIN DESCRIPTION:
UNT020 IN PECR 20.0
END DESCRIPTION:
XS GIS Cut Line= 4
      2336887.62     13228395.44      2336184.24     13229039.39
      2335847.42      13230307.4      2335946.11     13230633.06
#Sta/Elev= 30
  3791.9   121.2  3863.5  119.17  3991.5  107.61  4012.1   105.7  4033.7  105.48
  4047.9  102.54  4054.6  104.56  4062.1  102.54  4068.8  101.83  4161.4   96.76
  4211.8   93.75 4217.16    92.7  4221.8   91.14  4224.6   90.64  4227.8   91.14
  5686.4   91.14  5694.8   91.14  5705.2   92.53  5803.3   96.74  5838.3   99.39
  5843.5  100.67  5870.7  100.42  5918.6  101.97  5950.4  104.57    5999  106.58
  6051.8  110.02  6211.1  117.92    6260  118.91  6353.3  119.71  6397.8  120.73
#Mann= 12 ,-1 , 0
  3791.9      .1       0  3991.5     .08       0  4161.4     .05       0
  4211.8     .12       0  4221.8    .033       0  4227.8     .05       0
  5686.4     .07       0  5686.4     .05       0  5950.4      .1       0
  6051.8     .05       0    6260      .1       0  6353.3     .05       0
Bank Sta=4217.16,5705.2
XS Rating Curve= 0 ,0
Exp/Cntr=0.3,0.1

Type RM Length L Ch R = 1 ,10509   ,734,734,734
BEGIN DESCRIPTION:
UNT020 IN PECR 18.0
END DESCRIPTION:
XS GIS Cut Line= 4
      2336928.01     13228168.95      2335860.27      13228142.9
      2335248.29     13229275.72      2335482.67     13230577.79
#Sta/Elev= 30
  3020.5  120.94  3080.8  118.64  3260.9  105.18  3319.5  102.66  3350.9  101.08
  3390.9  100.42  3469.7   96.72  3527.6   94.52  3560.9   93.46 3562.02   92.42
    3588   91.14  3590.7   90.64    3594   91.14  3649.9   91.14    5500   91.14
  5800.8    91.2 5812.64   92.34  5814.2   93.55  5824.3   94.04  5856.3   94.68
  5875.1      96  5909.9   96.33  5925.9   98.91  5936.1   98.05    6058  102.12
  6204.4  105.47  6471.6  112.44  6546.2  113.58  6657.5  114.94  6699.1  114.58
#Mann= 11 ,-1 , 0
  3020.5      .1       0  3319.5     .08       0  3469.7      .1       0
  3527.6     .08       0    3588    .033       0    3594     .08       0
  3649.9     .05       0    5500     .07       0  5800.8     .05       0
  6204.4      .1       0  6546.2     .05       0
Bank Sta=3560.9,5812.64
XS Rating Curve= 0 ,0
Exp/Cntr=0.3,0.1

Type RM Length L Ch R = 1 ,9775    ,853,853,853
BEGIN DESCRIPTION:
UNT020 IN PECR 16.0
END DESCRIPTION:
XS GIS Cut Line= 5
      2336875.87     13225109.08      2335052.98     13227439.78
      2334792.56     13228481.45      2334649.34     13229054.36
      2335313.06     13230537.99
#Sta/Elev= 30
     759   129.3   920.1  124.76   976.7  122.81   991.2   123.7  1090.7   119.3
  1134.1   119.2  1268.8  114.21  1382.8  111.72  1467.8   107.7  1490.4   107.9
  1718.2    98.8  1832.2   95.38  1860.7    94.2  1867.5   92.34  1873.8   92.27
  1907.8   91.14  1910.6   90.64  1913.8   91.14  6283.2   91.14 6291.73    92.3
  6292.6   91.56  6298.1   93.54  6308.5   93.69  6405.8   97.15  6489.2  100.19
  6546.5  104.08  6576.3  104.04  6841.9  113.13  6934.1  113.94  7007.5  113.46
#Mann= 8 ,-1 , 0
     759      .1       0   920.1     .05       0  1907.8    .033       0
  1913.8     .05       0  6283.2     .07       0  6308.5      .1       0
  6405.8     .05       0  6576.3      .1       0
Bank Sta=1873.8,6291.73
XS Rating Curve= 0 ,0
Exp/Cntr=0.3,0.1

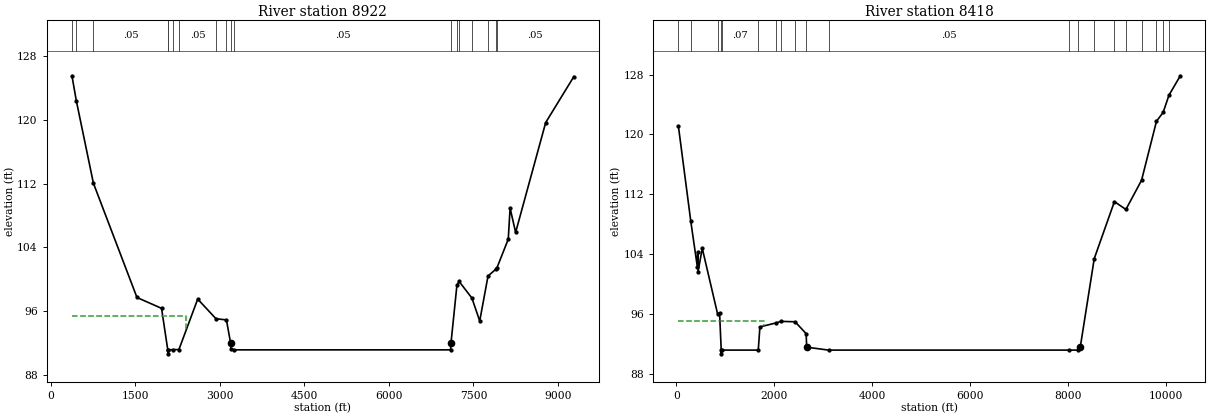
Type RM Length L Ch R = 1 ,8922    ,504,504,504
BEGIN DESCRIPTION:
UNT020 IN PECR 15.0
END DESCRIPTION:
XS GIS Cut Line= 3
      2336719.64      13224692.4      2333937.72     13228346.85
      2335537.73     13232346.89
#Sta/Elev= 30
   379.4  125.53   456.8   122.4   759.9  112.05  1532.5   97.71  1968.5   96.35
  2078.7   91.14  2081.4   90.64  2084.7   91.14    2166   91.16  2276.5   91.18
  2609.5   97.51  2934.3   95.04    3119    94.9 3193.05   91.99  3199.9   91.24
  3259.2   91.14    7094   91.14 7102.05   92.03  7206.5   99.24  7244.6   99.73
  7472.4   97.64    7611   94.76    7758   100.4    7905  101.31  7914.3  101.39
  8117.2  105.03  8149.5  108.92  8247.8  105.88  8780.9  119.66  9280.4  125.43
#Mann= 18 ,-1 , 0
   379.4     .05       0   456.8      .1       0   759.9     .05       0
  2078.7    .033       0  2084.7     .05       0    2166     .07       0
  2276.5     .05       0  2934.3     .08       0    3119     .07       0
  3199.9     .05       0  3259.2     .05       0    7094     .07       0
  7206.5      .1       0  7244.6     .08       0  7472.4     .07       0
    7758      .1       0    7905     .08       0  7914.3     .05       0
#XS Ineff= 2 , 0
         2405.14   95.34
Permanent Ineff=
       F       F
Bank Sta=3193.05,7102.05
XS Rating Curve= 0 ,0
Exp/Cntr=0.3,0.1

Type RM Length L Ch R = 1 ,8418    ,0,0,0
BEGIN DESCRIPTION:
UNT020 IN PECR 1.0
END DESCRIPTION:
XS GIS Cut Line= 4
      2336417.85     13224191.73      2333702.11     13227459.83
      2333172.77     13229254.98      2335381.76     13232752.54
#Sta/Elev= 30
    41.4  121.08     294  108.38   428.3  102.27   436.1  104.29   442.6  101.62
   528.6  104.75   842.7   95.96   882.7   96.11   916.2   91.14   918.9   90.64
   922.2   91.14  1673.3   91.14  1706.9   94.24  2027.8   94.76  2140.3   94.98
  2425.6   94.93  2651.8   93.34 2662.72   91.53    3111   91.14  8022.9   91.14
  8215.7   91.14  8253.9   91.53  8539.5  103.37  8951.8     111  9186.7  109.95
  9506.6  113.85  9811.9  121.75  9948.3  122.94 10067.4  125.24 10298.9  127.83
#Mann= 20 ,-1 , 0
    41.4      .1       0     294     .05       0   842.7     .07       0
   916.2    .033       0   922.2     .07       0  1673.3     .05       0
  2027.8     .08       0  2140.3     .05       0  2425.6     .08       0
  2651.8     .07       0    3111     .05       0  8022.9     .07       0
  8215.7     .05       0  8539.5     .08       0  8951.8     .05       0
  9186.7     .08       0  9506.6     .05       0  9811.9     .08       0
  9948.3     .08       0 10067.4     .05       0
#XS Ineff= 2 , 0
         1786.36   94.97
Permanent Ineff=
       F       F
Bank Sta=2662.72,8253.9
XS Rating Curve= 0 ,0
Exp/Cntr=0.3,0.1

Chan Stop Cuts=-1
Use User Specified Reach Order=0
Composite Channel Slope=5