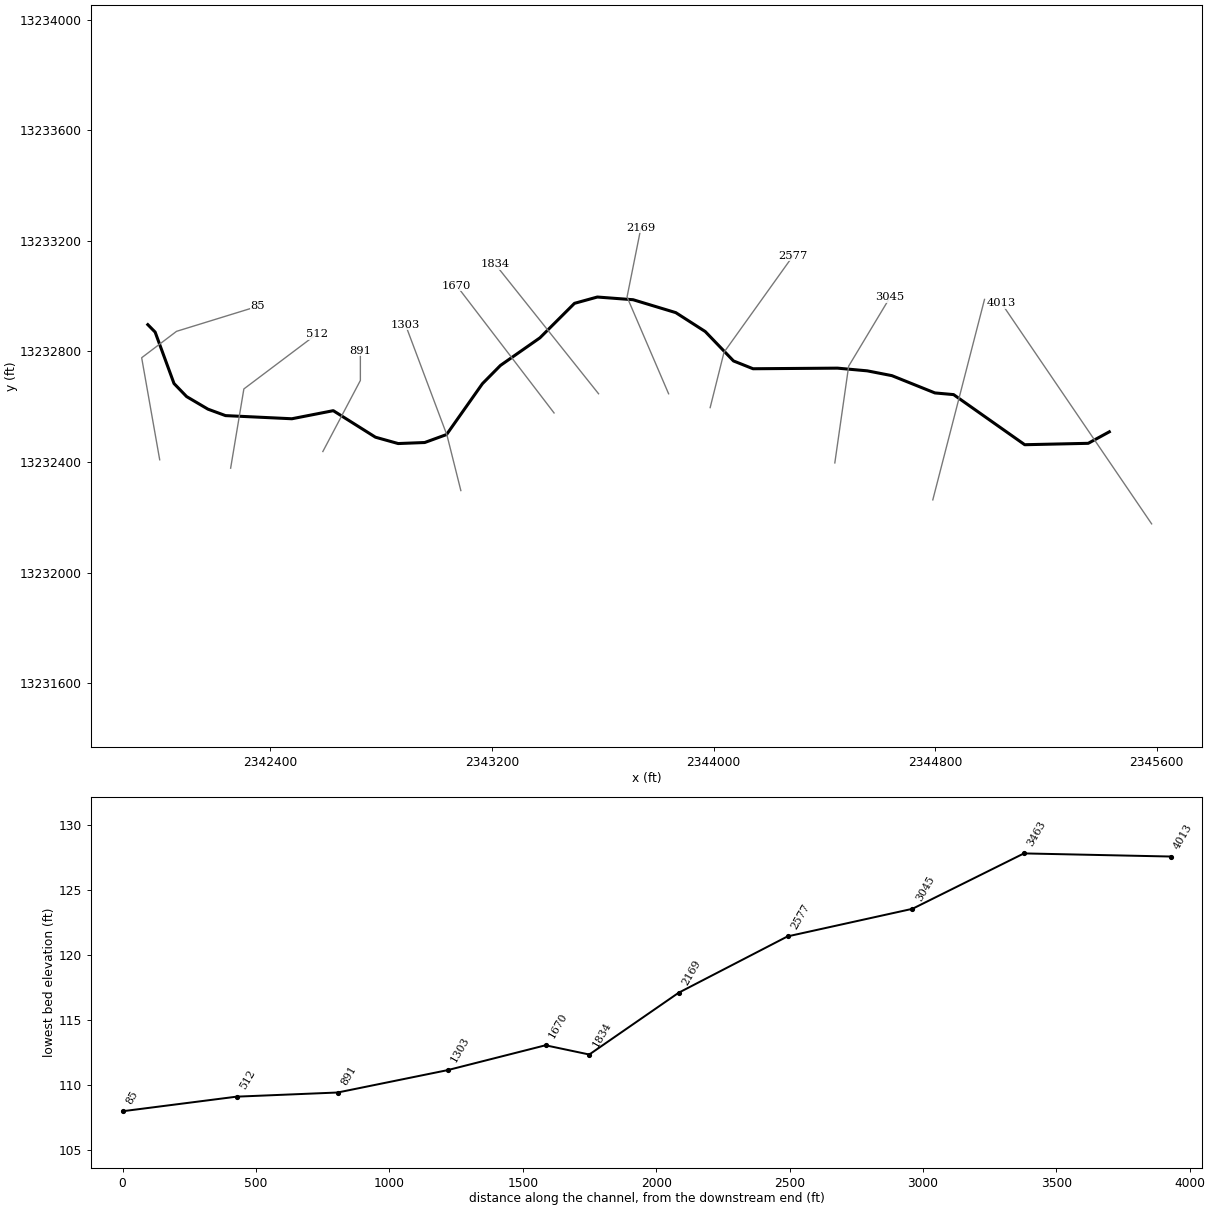
--- UNT021 IN PECR.prj (project) ---

Proj Title=UNT021 IN PECR Base Level Engineering
Current Plan=p01
Default Exp/Contr=0.3,0.1
English Units
Geom File=g01
Flow File=f01
Plan File=p01
Y Axis Title=Elevation
X Axis Title(PF)=Main Channel Distance
X Axis Title(XS)=Station
BEGIN DESCRIPTION:
UNT021 IN PECR
END DESCRIPTION:
DSS Export Rating Curves= 0
DSS Export Rating Curve Sorted= 0
DSS Export Volume Flow Curves= 0
DXF OffsetX= 0
DXF OffsetY= 0
DXF ScaleX= 1
DXF ScaleY= 10

--- UNT021 IN PECR.p01 (plan) ---

Plan Title=Multiple Run
Short Identifier=Multiple
Geom File=g01
Flow File=f01
Subcritical Flow
K Sum by GR= 0
Std Step Tol= 0.01
Critical Tol= 0.01
Num of Std Step Trials= 20
Max Error Tol= 0.3
Flow Tol Ratio= 0.001
Split Flow NTrial= 30
Split Flow Tol= 0.02
Split Flow Ratio= 0.02
Log Output Level= 0
Friction Slope Method= 1
Unsteady Friction Slope Method= 2
Unsteady Bridges Friction Slope Method= 1
Parabolic Critical Depth
Global Vel Dist=  1 , 1 , 1
Global Log Level= 0
CheckData=True
Encroach Param= -1, 0, 0, 0
BEGIN DESCRIPTION:
Multiple Run
END DESCRIPTION:

--- UNT021 IN PECR.f01 (steady flow) ---

Flow Title=Multiple
Program Version=4.10
Number of Profiles= 7
Profile Names=10-year,25-year,50-year,1pct_min,100-year,1pct_plu,500-year
River Rch & RM=UNT021 IN PECR,Reach-1         ,4013
     399     533     637     556     752    1017    1051
River Rch & RM=UNT021 IN PECR,Reach-1         ,3463
     571     784     956     850    1150    1555    1671
Boundary for River Rch & Prof#=UNT021 IN PECR,Reach-1         , 1
Up Type= 0
Dn Type= 3
Dn Slope=0.005
Boundary for River Rch & Prof#=UNT021 IN PECR,Reach-1         , 2
Up Type= 0
Dn Type= 3
Dn Slope=0.005
Boundary for River Rch & Prof#=UNT021 IN PECR,Reach-1         , 3
Up Type= 0
Dn Type= 3
Dn Slope=0.005
Boundary for River Rch & Prof#=UNT021 IN PECR,Reach-1         , 4
Up Type= 0
Dn Type= 3
Dn Slope=0.005
Boundary for River Rch & Prof#=UNT021 IN PECR,Reach-1         , 5
Up Type= 0
Dn Type= 3
Dn Slope=0.005
Boundary for River Rch & Prof#=UNT021 IN PECR,Reach-1         , 6
Up Type= 0
Dn Type= 3
Dn Slope=0.005
Boundary for River Rch & Prof#=UNT021 IN PECR,Reach-1         , 7
Up Type= 0
Dn Type= 3
Dn Slope=0.005
DSS Import GetInterval= 0
DSS Import GetPeak= 0
DSS Import FillOption= 0

--- UNT021 IN PECR.g01 (geometry) ---

Geom Title=Existing Conditions
Program Version=4.10

River Reach=UNT021 IN PECR  ,Reach-1
Reach XY= 30
      2345428.61     13232509.33      2345352.44     13232467.72
      2345123.31     13232462.66      2344866.48     13232643.87
        2344799.     13232649.95       2344643.8     13232712.42
      2344554.82     13232729.78       2344447.4     13232739.55
       2344142.5     13232737.38      2344071.97     13232765.59
      2343969.97     13232871.93      2343863.63     13232940.29
      2343709.55     13232986.95      2343580.43     13232996.71
      2343497.97     13232973.92      2343373.18     13232849.14
      2343230.61     13232749.31      2343165.64     13232683.38
      2343036.15     13232499.42      2342957.26     13232470.61
      2342861.51     13232466.88      2342779.55      13232489.8
      2342627.19     13232585.77      2342477.77     13232556.54
      2342238.17     13232567.94      2342174.82     13232591.26
      2342097.77     13232636.74      2342052.31     13232683.91
      2341984.16     13232869.93      2341957.72     13232896.85

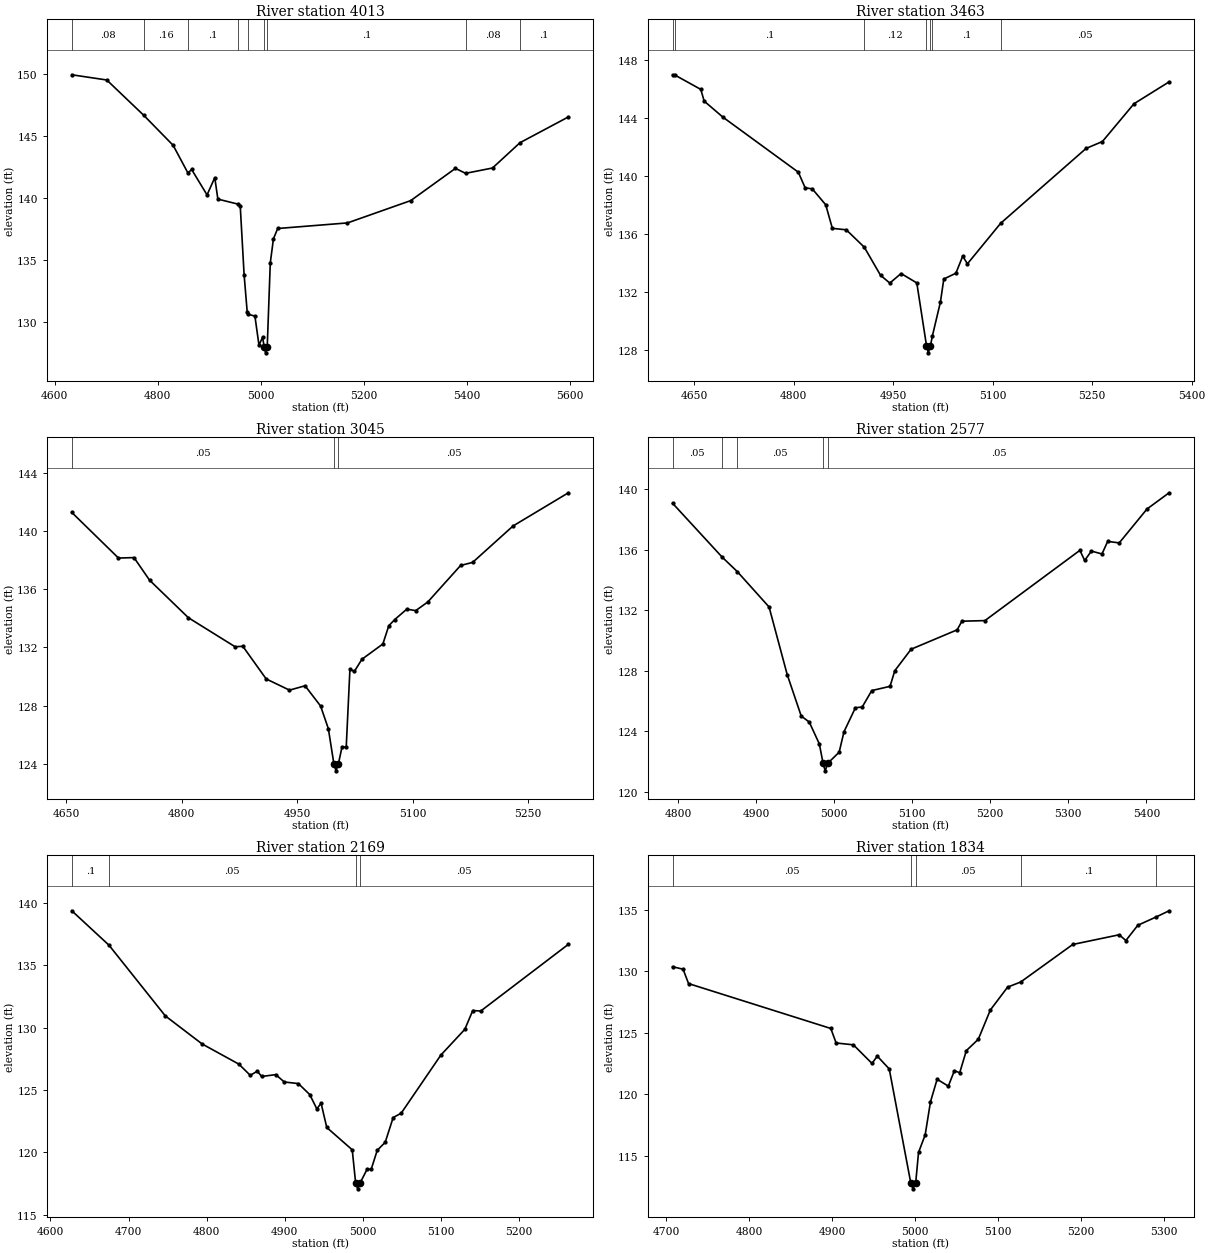
Type RM Length L Ch R = 1 ,4013    ,550,550,550
BEGIN DESCRIPTION:
Mapping XS 7b75daad
END DESCRIPTION:
XS GIS Cut Line= 2
      2345581.34      13232176.5      2345039.91     13232973.49
#Sta/Elev= 30
  4633.3  149.97  4701.1  149.55  4772.9   146.7  4829.9  144.28  4858.6  142.05
  4865.8  142.33  4895.7  140.28  4910.7  141.67  4916.7  139.94  4955.4  139.54
  4960.1   139.4  4967.6  133.85  4973.6  130.84  4975.7  130.65  4988.6   130.5
  4996.4  128.17  5003.5  128.79  5006.5  128.04  5009.3  127.54  5012.5  128.04
  5018.4  134.79  5024.5  136.73  5032.7  137.57  5168.2  138.02  5290.9  139.82
  5377.7  142.42  5397.4  142.02  5449.6  142.45  5502.9  144.49  5596.8  146.57
#Mann= 9 ,-1 , 0
  4633.3     .08       0  4772.9     .16       0  4858.6      .1       0
  4955.4     .16       0  4975.7      .1       0  5006.5     .07       0
  5012.5      .1       0  5397.4     .08       0  5502.9      .1       0
Bank Sta=5006.5,5012.5
XS Rating Curve= 0 ,0
Exp/Cntr=0.3,0.1

Type RM Length L Ch R = 1 ,3463    ,418,418,418
BEGIN DESCRIPTION:
UNT021 IN PECR 8.0
END DESCRIPTION:
XS GIS Cut Line= 2
      2344791.43     13232263.25      2344978.07     13232988.11
#Sta/Elev= 30
  4617.4  146.99  4620.6  146.98    4660  145.98  4665.1  145.17  4693.4  144.06
    4807  140.26  4817.3  139.18    4828  139.11  4848.3  138.01  4858.3  136.38
  4879.3  136.28  4906.4  135.08  4930.9  133.14  4944.9   132.6  4961.9  133.26
  4985.6  132.61  5000.2  128.28  5002.9  127.78  5006.2  128.28  5009.2  128.97
  5021.2  131.29  5026.3  132.88  5044.5  133.28  5054.8  134.46  5061.9  133.93
    5112  136.73  5240.7   141.9  5265.4  142.38    5313  144.99  5365.9   146.5
#Mann= 7 ,-1 , 0
  4617.4     .05       0  4620.6      .1       0  4906.4     .12       0
  5000.2     .07       0  5006.2     .12       0  5009.2      .1       0
    5112     .05       0
Bank Sta=5000.2,5006.2
XS Rating Curve= 0 ,0
Exp/Cntr=0.3,0.1

Type RM Length L Ch R = 1 ,3045    ,468,468,468
BEGIN DESCRIPTION:
UNT021 IN PECR 7.0
END DESCRIPTION:
XS GIS Cut Line= 3
      2344437.72     13232396.87      2344487.72     13232746.85
      2344637.73     13232996.87
#Sta/Elev= 30
  4657.4  141.26    4718  138.13  4738.2  138.16  4758.4  136.61  4808.9  134.03
  4869.5  132.04  4879.6  132.07  4909.9  129.83  4940.2  129.06  4960.4  129.36
  4980.6  127.97  4990.7  126.41  4997.8  124.02  5000.6  123.52  5003.8  124.02
  5008.4  125.15  5013.9  125.15  5018.7  130.48  5024.5  130.35  5034.3  131.18
  5061.5  132.23  5069.2  133.48    5077  133.91  5092.6  134.62  5104.2  134.52
  5119.8  135.11  5162.5  137.62  5178.1  137.83  5230.6  140.33  5302.5  142.61
#Mann= 3 ,-1 , 0
  4657.4     .05       0  4997.8     .03       0  5003.8     .05       0
Bank Sta=4997.8,5003.8
XS Rating Curve= 0 ,0
Exp/Cntr=0.3,0.1

Type RM Length L Ch R = 1 ,2577    ,408,408,408
BEGIN DESCRIPTION:
UNT021 IN PECR 6.0
END DESCRIPTION:
XS GIS Cut Line= 3
      2343987.72     13232596.84      2344037.72     13232796.85
      2344287.73     13233146.87
#Sta/Elev= 30
  4792.9  139.07  4856.5  135.51  4875.8  134.56  4916.6  132.22  4939.8  127.76
  4957.8  125.02  4968.1  124.62    4981  123.18  4985.8   121.9  4988.5   121.4
  4991.8   121.9  5006.4  122.63  5012.6  123.98  5027.3  125.57  5035.9  125.61
  5048.2   126.7  5071.6  126.98  5077.7  128.01  5098.6  129.43  5157.6  130.71
  5163.7  131.28  5193.2  131.32  5314.9  135.96    5321  135.29  5329.6  135.91
  5343.2  135.72  5350.5  136.55  5365.3  136.45  5400.9  138.69  5429.2  139.76
#Mann= 5 ,-1 , 0
  4792.9     .05       0  4856.5      .1       0  4875.8     .05       0
  4985.8     .03       0  4991.8     .05       0
Bank Sta=4985.8,4991.8
XS Rating Curve= 0 ,0
Exp/Cntr=0.3,0.1

Type RM Length L Ch R = 1 ,2169    ,335,335,335
BEGIN DESCRIPTION:
UNT021 IN PECR 5.0
END DESCRIPTION:
XS GIS Cut Line= 3
      2343837.71     13232646.87      2343687.72     13232996.85
      2343737.72     13233246.84
#Sta/Elev= 30
  4627.4  139.37    4675  136.61  4747.1  130.94  4794.2  128.69  4841.3  127.07
  4855.9  126.17  4864.9  126.51  4870.4  126.08  4888.5  126.23  4899.4  125.64
  4917.5  125.51    4932  124.63  4941.1  123.48  4946.5  123.94  4953.8  121.99
  4986.4   120.2  4990.7  117.57  4993.4  117.07  4996.7  117.57  5005.4  118.64
  5010.7  118.64  5018.4  120.16  5028.6   120.8  5038.8  122.79    5049  123.13
  5099.9   127.8  5130.5  129.86  5140.7  131.37  5150.9  131.33  5263.1  136.68
#Mann= 4 ,-1 , 0
  4627.4      .1       0    4675     .05       0  4990.7     .03       0
  4996.7     .05       0
Bank Sta=4990.7,4996.7
XS Rating Curve= 0 ,0
Exp/Cntr=0.3,0.1

Type RM Length L Ch R = 1 ,1834    ,164,164,164
BEGIN DESCRIPTION:
Mapping XS 87398c92
END DESCRIPTION:
XS GIS Cut Line= 2
      2343584.86     13232646.92      2343212.17     13233114.96
#Sta/Elev= 30
  4707.8  130.38  4720.5  130.18  4727.1  129.01  4898.5  125.36  4904.9  124.18
  4925.7  124.03  4948.1  122.52  4954.5  123.11  4968.9  122.07  4994.8  112.82
  4997.5  112.32  5000.8  112.82  5004.2  115.28  5012.2  116.71  5018.6   119.4
  5026.6  121.23  5040.1  120.67  5047.4  121.93  5053.8  121.76  5061.8  123.56
  5076.2  124.48  5090.7  126.86  5111.5  128.72  5127.3  129.14    5190  132.19
    5246  132.98    5254  132.51  5268.4  133.75  5290.9  134.44  5306.1  134.93
#Mann= 5 ,-1 , 0
  4707.8     .05       0  4994.8     .04       0  5000.8     .05       0
  5127.3      .1       0  5290.9     .05       0
Bank Sta=4994.8,5000.8
XS Rating Curve= 0 ,0
Exp/Cntr=0.3,0.1

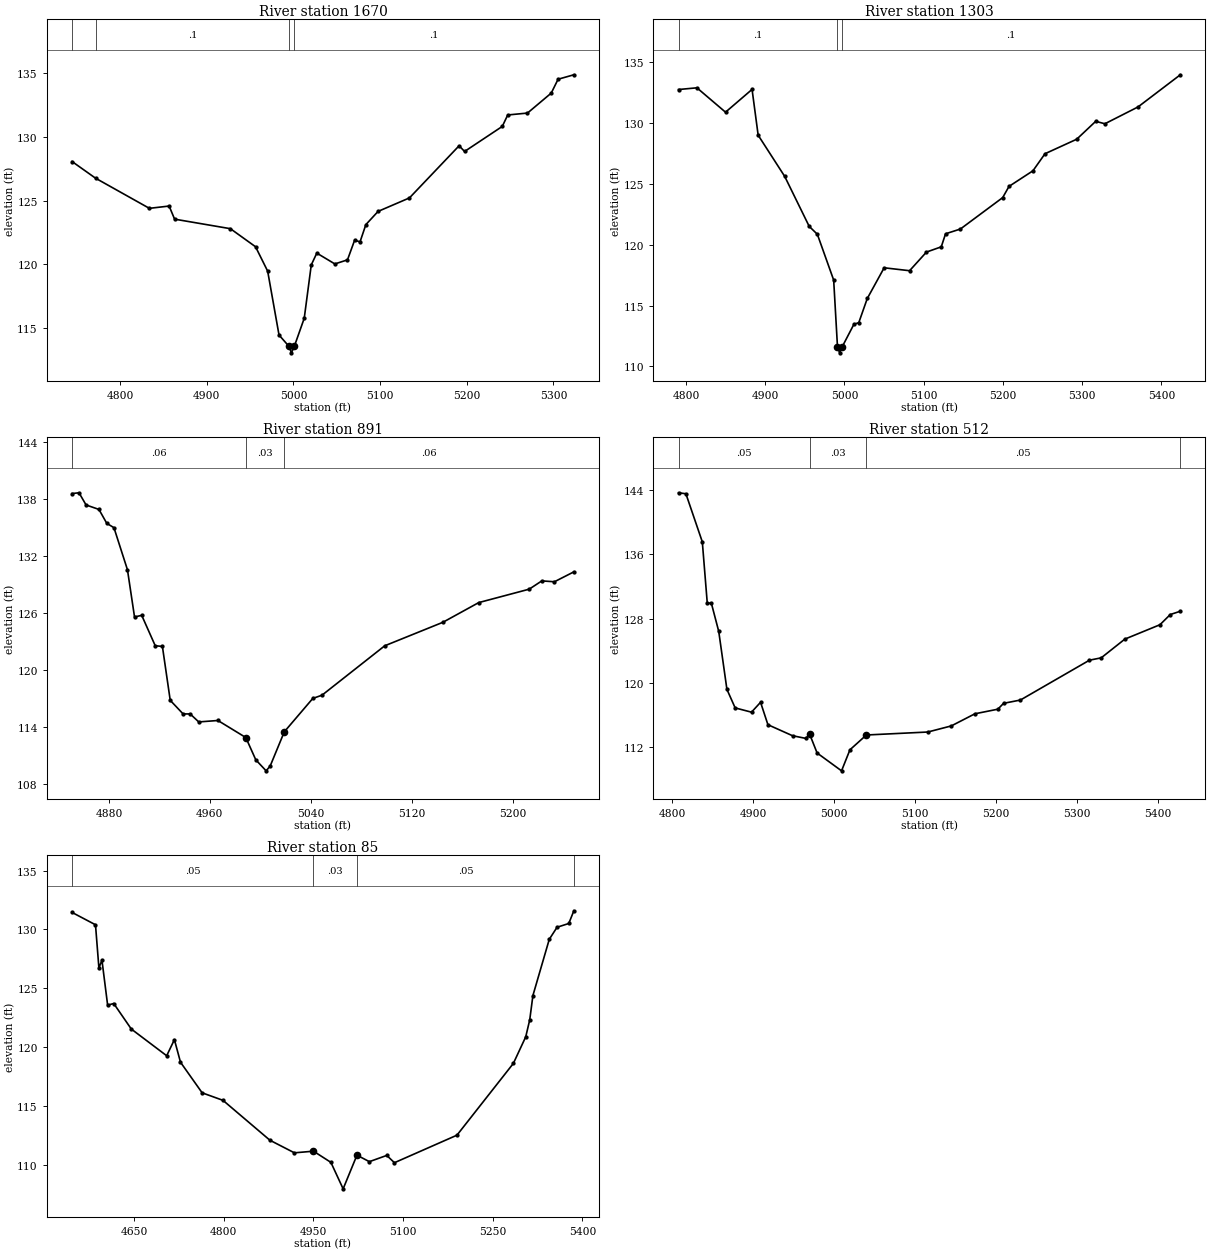
Type RM Length L Ch R = 1 ,1670    ,367,367,367
BEGIN DESCRIPTION:
UNT021 IN PECR 4.0
END DESCRIPTION:
XS GIS Cut Line= 2
      2343424.24     13232577.52      2343072.69     13233037.57
#Sta/Elev= 30
  4744.6  128.07  4771.7  126.76  4833.8  124.39  4856.6  124.57  4862.9  123.54
  4927.3  122.79  4956.3  121.37  4970.3  119.45  4983.4  114.43    4995  113.53
  4997.7  113.03    5001  113.53  5012.5  115.75  5020.6  119.94    5027  120.87
  5047.8  120.02  5062.4  120.34  5070.6  121.88  5076.9  121.76  5083.6  123.11
  5097.7  124.15  5133.9  125.21  5191.2  129.31  5197.5  128.86    5241  130.83
  5247.3  131.73  5270.1  131.88  5297.5  133.45  5305.4  134.54  5323.6  134.89
#Mann= 4 ,-1 , 0
  4744.6     .05       0  4771.7      .1       0    4995     .07       0
    5001      .1       0
Bank Sta=4995,5001
XS Rating Curve= 0 ,0
Exp/Cntr=0.3,0.1

Type RM Length L Ch R = 1 ,1303    ,412,412,412
BEGIN DESCRIPTION:
UNT021 IN PECR 3.0
END DESCRIPTION:
XS GIS Cut Line= 3
      2343087.72     13232296.87      2343037.72     13232496.85
      2342887.73     13232896.82
#Sta/Elev= 30
  4790.6  132.73  4813.8  132.87  4849.9  130.87  4883.4  132.74  4891.1  128.98
  4924.6   125.6  4955.5   121.5  4965.8  120.85  4986.4  117.09  4991.2  111.62
  4993.9  111.12  4997.2  111.62  5011.9  113.46  5018.1   113.6  5028.8  115.58
  5050.1   118.1  5082.2  117.86  5103.5  119.39  5122.2  119.82  5127.6  120.89
  5146.3  121.28  5199.7  123.86  5207.7  124.78  5237.9  126.06  5253.1  127.46
  5293.1  128.65  5317.1  130.12  5328.7  129.92  5370.5   131.3  5423.9  133.94
#Mann= 3 ,-1 , 0
  4790.6      .1       0  4991.2     .07       0  4997.2      .1       0
Bank Sta=4991.2,4997.2
XS Rating Curve= 0 ,0
Exp/Cntr=0.3,0.1

Type RM Length L Ch R = 1 ,891     ,379,379,379
BEGIN DESCRIPTION:
UNT021 IN PECR 2.0
END DESCRIPTION:
XS GIS Cut Line= 3
       2342589.6     13232438.05      2342725.01     13232694.98
      2342725.01     13232802.26
#Sta/Elev= 30
  4850.8  138.54  4856.3  138.62  4861.9  137.34  4872.1  136.87  4878.3  135.41
    4884  134.95  4894.7  130.53  4900.3  125.57    4906  125.74  4916.7  122.55
  4922.4  122.47  4928.6  116.81  4938.8  115.38  4944.4  115.38  4951.2  114.54
  4966.4  114.69  4988.5   112.9  4996.4  110.56  5004.6   109.4  5007.8   109.9
    5019   113.5  5041.6  117.01  5048.9  117.35  5098.6  122.54  5144.7  125.01
  5173.1  127.08  5213.1  128.49  5223.1  129.36  5233.1  129.27  5248.5  130.31
#Mann= 3 , 0 , 0
  4850.8     .06       0  4988.5     .03       0    5019     .06       0
Bank Sta=4988.5,5019
XS Rating Curve= 0 ,0
Exp/Cntr=0.3,0.1

Type RM Length L Ch R = 1 ,512     ,427,427,427
BEGIN DESCRIPTION:
Mapping XS 73df963b
END DESCRIPTION:
XS GIS Cut Line= 3
      2342256.71     13232377.86      2342304.45     13232664.32
      2342567.84     13232862.94
#Sta/Elev= 30
  4807.7  143.68  4816.8  143.56  4837.1  137.57  4843.2  129.97  4848.3  129.93
  4857.4  126.43  4867.5  119.22  4877.7  116.91  4897.9  116.38  4909.1  117.61
  4918.2  114.82  4948.6  113.45  4964.9  113.12  4969.9  113.61    4979   111.3
  5009.2  109.08  5019.6   111.7  5039.9  113.54  5115.8  113.91  5144.9  114.67
  5174.1  116.18  5202.4  116.75  5209.5  117.48  5230.3  117.89  5315.7  122.85
  5330.2  123.14  5359.4  125.47  5402.8  127.26  5415.6  128.53    5428  128.94
#Mann= 4 ,-1 , 0
  4807.7     .05       0  4969.9     .03       0  5039.9     .05       0
    5428      .1       0
Bank Sta=4969.9,5039.9
XS Rating Curve= 0 ,0
Exp/Cntr=0.3,0.1

Type RM Length L Ch R = 1 ,85      ,0,0,0
BEGIN DESCRIPTION:
UNT021 IN PECR 1.0
END DESCRIPTION:
XS GIS Cut Line= 4
      2342000.64     13232408.21      2341935.53     13232777.17
       2342061.4     13232872.65      2342354.59      13232963.2
#Sta/Elev= 30
  4546.3  131.45  4585.5   130.4  4591.2  126.73  4596.3  127.39  4605.8  123.57
    4616  123.71  4645.4  121.54  4704.6  119.27  4717.5  120.64  4727.7  118.72
  4763.9  116.12  4798.8  115.48  4877.3  112.09  4918.3  111.02  4950.2  111.16
  4979.3  110.21  4999.8  107.96  5022.9  110.82  5043.7  110.27  5072.8   110.8
  5085.6  110.18  5190.2  112.52  5284.6  118.62  5305.3  120.88    5312  122.33
  5317.3  124.39  5344.7  129.17  5357.7  130.19  5377.3  130.51  5385.8  131.59
#Mann= 4 ,-1 , 0
  4546.3     .05       0  4950.2     .03       0  5022.9     .05       0
  5385.8      .1       0
Bank Sta=4950.2,5022.9
XS Rating Curve= 0 ,0
Exp/Cntr=0.3,0.1

Chan Stop Cuts=-1
Use User Specified Reach Order=0
Composite Channel Slope=5