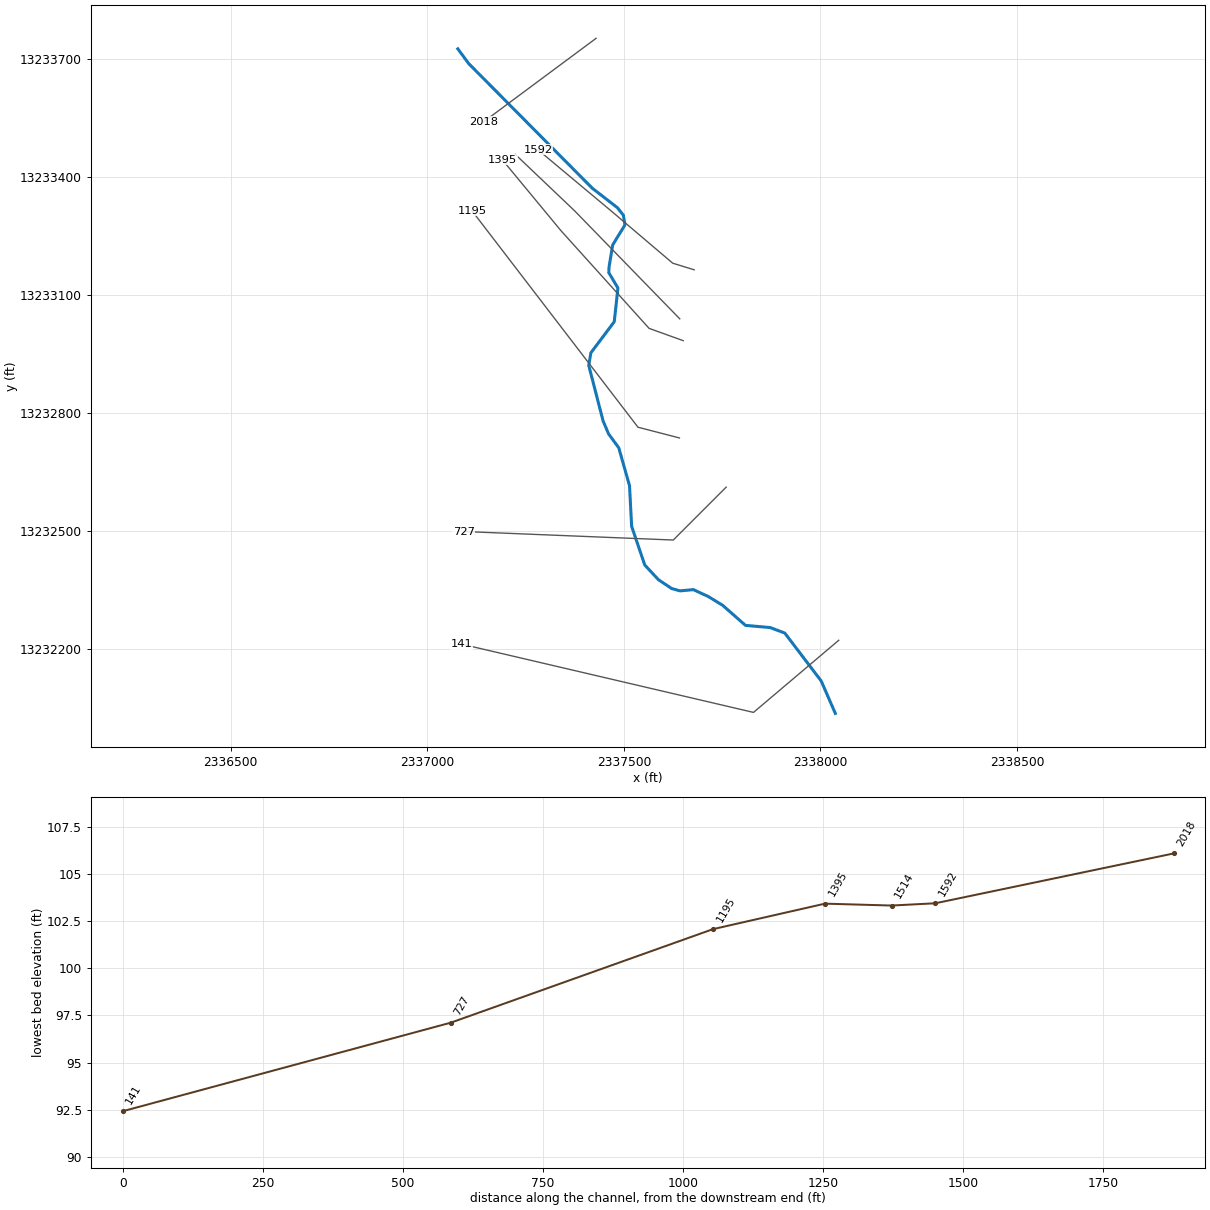
--- UNT022 IN PECR.prj (project) ---

Proj Title=UNT022 IN PECR Base Level Engineering
Current Plan=p01
Default Exp/Contr=0.3,0.1
English Units
Geom File=g01
Flow File=f01
Plan File=p01
Y Axis Title=Elevation
X Axis Title(PF)=Main Channel Distance
X Axis Title(XS)=Station
BEGIN DESCRIPTION:
UNT022 IN PECR
END DESCRIPTION:
DSS Export Rating Curves= 0
DSS Export Rating Curve Sorted= 0
DSS Export Volume Flow Curves= 0
DXF OffsetX= 0
DXF OffsetY= 0
DXF ScaleX= 1
DXF ScaleY= 10

--- UNT022 IN PECR.p01 (plan) ---

Plan Title=Multiple Run
Short Identifier=Multiple
Geom File=g01
Flow File=f01
Subcritical Flow
K Sum by GR= 0
Std Step Tol= 0.01
Critical Tol= 0.01
Num of Std Step Trials= 20
Max Error Tol= 0.3
Flow Tol Ratio= 0.001
Split Flow NTrial= 30
Split Flow Tol= 0.02
Split Flow Ratio= 0.02
Log Output Level= 0
Friction Slope Method= 1
Unsteady Friction Slope Method= 2
Unsteady Bridges Friction Slope Method= 1
Parabolic Critical Depth
Global Vel Dist=  1 , 1 , 1
Global Log Level= 0
CheckData=True
Encroach Param= -1, 0, 0, 0
BEGIN DESCRIPTION:
Multiple Run
END DESCRIPTION:

--- UNT022 IN PECR.f01 (steady flow) ---

Flow Title=Multiple
Program Version=4.10
Number of Profiles= 7
Profile Names=10-year,25-year,50-year,1pct_min,100-year,1pct_plu,500-year
River Rch & RM=UNT022 IN PECR,Reach-1         ,2018
     412     559     676     597     807    1092    1156
River Rch & RM=UNT022 IN PECR,Reach-1         ,1592
     460     630     767     682     922    1247    1338
Boundary for River Rch & Prof#=UNT022 IN PECR,Reach-1         , 1
Up Type= 0
Dn Type= 3
Dn Slope=0.0079
Boundary for River Rch & Prof#=UNT022 IN PECR,Reach-1         , 2
Up Type= 0
Dn Type= 3
Dn Slope=0.0079
Boundary for River Rch & Prof#=UNT022 IN PECR,Reach-1         , 3
Up Type= 0
Dn Type= 3
Dn Slope=0.0079
Boundary for River Rch & Prof#=UNT022 IN PECR,Reach-1         , 4
Up Type= 0
Dn Type= 3
Dn Slope=0.0079
Boundary for River Rch & Prof#=UNT022 IN PECR,Reach-1         , 5
Up Type= 0
Dn Type= 3
Dn Slope=0.0079
Boundary for River Rch & Prof#=UNT022 IN PECR,Reach-1         , 6
Up Type= 0
Dn Type= 3
Dn Slope=0.0079
Boundary for River Rch & Prof#=UNT022 IN PECR,Reach-1         , 7
Up Type= 0
Dn Type= 3
Dn Slope=0.0079
DSS Import GetInterval= 0
DSS Import GetPeak= 0
DSS Import FillOption= 0

--- UNT022 IN PECR.g01 (geometry) ---

Geom Title=Existing Conditions
Program Version=4.10

River Reach=UNT022 IN PECR  ,Reach-1
Reach XY= 30
      2337077.72     13233726.85      2337105.19     13233689.53
      2337419.49     13233372.58      2337483.55     13233322.84
      2337498.74     13233303.74      2337502.65       13233279.
      2337471.57     13233228.13      2337462.31     13233172.37
      2337461.62     13233157.79      2337484.86     13233118.63
       2337475.5     13233032.82      2337416.08      13232953.8
      2337410.67      13232921.7      2337447.09     13232780.74
      2337460.98     13232747.75      2337487.03     13232712.16
      2337514.35     13232615.77      2337519.72     13232512.68
      2337553.06     13232414.22      2337587.63     13232377.04
      2337621.43     13232354.33      2337642.74     13232348.43
      2337676.74     13232351.56      2337714.37     13232334.14
      2337751.09     13232311.81      2337809.27     13232260.64
      2337872.08     13232255.08      2337909.21     13232241.13
      2338001.89     13232119.16      2338037.72     13232036.85

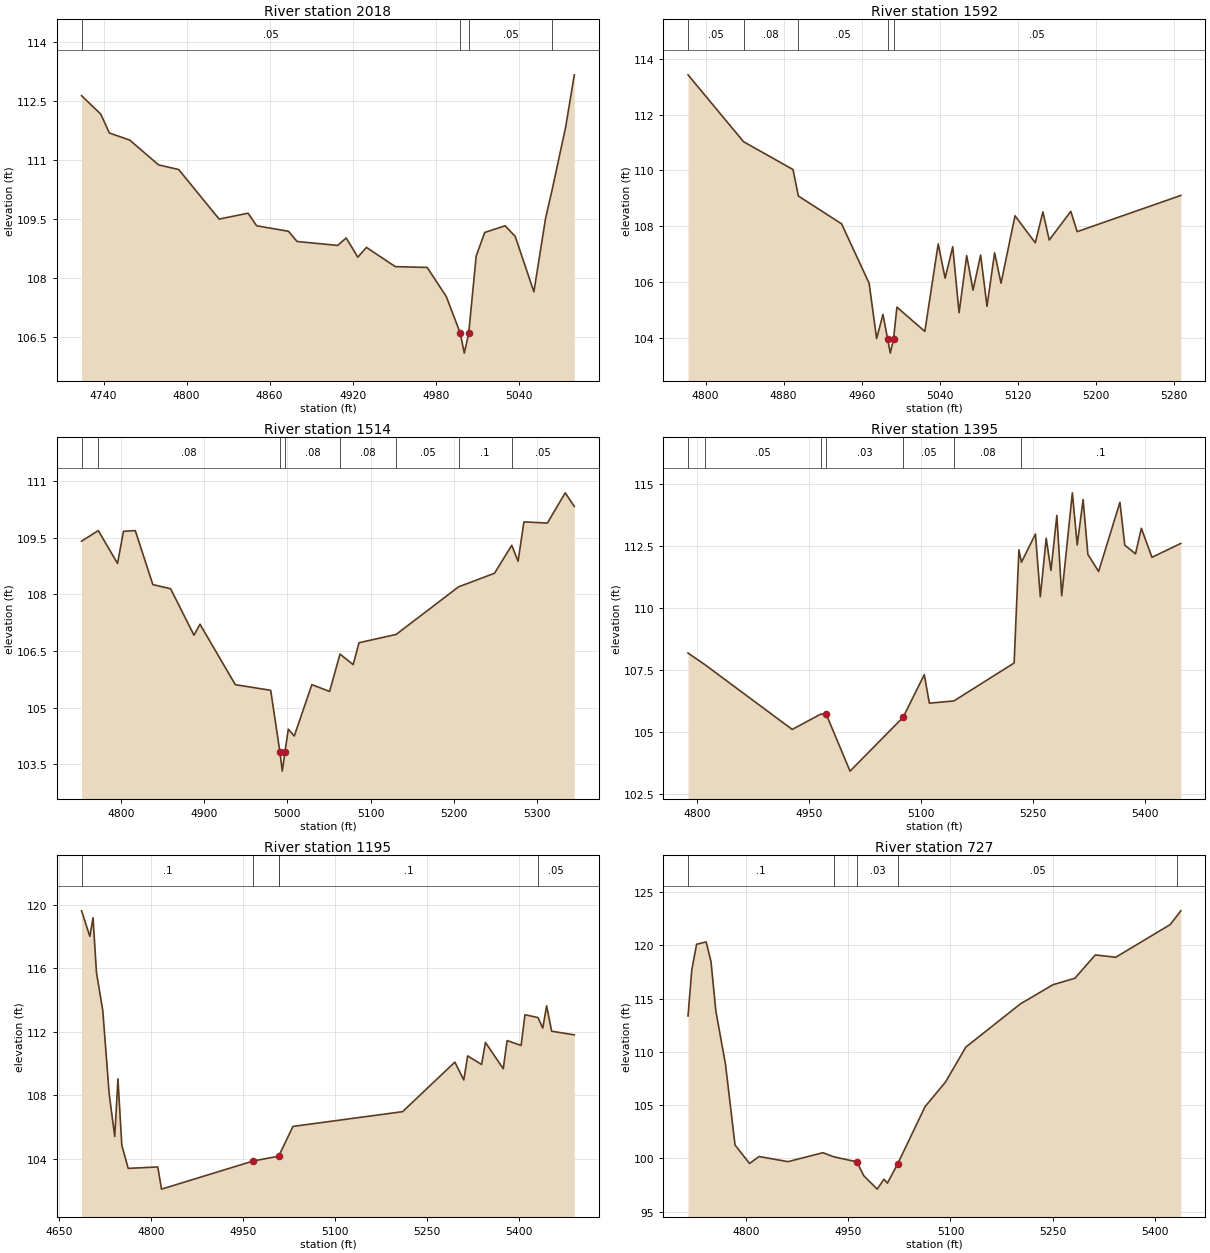
Type RM Length L Ch R = 1 ,2018    ,426,426,426
BEGIN DESCRIPTION:
UNT022 IN PECR 4.0
END DESCRIPTION:
XS GIS Cut Line= 2
      2337429.26     13233753.59      2337143.42     13233541.38
#Sta/Elev= 30
  4724.1  112.63    4738  112.16  4744.2  111.68  4758.9   111.5  4779.7  110.87
  4794.3  110.75  4823.5  109.49  4844.4  109.64  4850.6  109.32  4873.6  109.18
  4879.8  108.92  4909.1  108.82  4915.3  109.01  4923.7  108.52  4929.9  108.77
  4950.8  108.28  4973.8  108.26  4987.6  107.52  4997.8  106.58  5000.6  106.08
  5003.8  106.58  5009.2  108.55  5015.4  109.15  5030.1  109.32  5037.4  109.05
  5050.9  107.64  5059.3   109.5  5064.3  110.27  5073.9  111.84  5080.1  113.16
#Mann= 4 ,-1 , 0
  4724.1     .05       0  4997.8     .03       0  5003.8     .05       0
  5064.3      .1       0
Bank Sta=4997.8,5003.8
XS Rating Curve= 0 ,0
Exp/Cntr=0.3,0.1

Type RM Length L Ch R = 1 ,1592    ,78,78,78
BEGIN DESCRIPTION:
Mapping XS d8a2abed
END DESCRIPTION:
XS GIS Cut Line= 4
      2337678.78     13233164.94      2337624.21     13233181.75
      2337471.87     13233311.11      2337281.52     13233470.15
#Sta/Elev= 30
    4782  113.43  4838.9  111.03  4889.6  110.03  4895.1  109.08  4939.4  108.08
  4967.6  105.95  4975.3  103.96  4981.8  104.83  4986.6  103.94  4989.3  103.44
  4992.6  103.94  4996.1  105.09  5024.7  104.22  5038.4  107.36  5045.5  106.13
  5053.3  107.26  5059.8  104.89  5067.6  106.94  5074.1   105.7  5081.9  106.96
  5088.4  105.12  5096.2  107.04  5102.8  105.95  5117.1  108.37  5137.9   107.4
  5145.7  108.51  5152.2   107.5  5174.3  108.53  5180.8   107.8    5287   109.1
#Mann= 5 ,-1 , 0
    4782     .05       0  4838.9     .08       0  4895.1     .05       0
  4986.6     .04       0  4992.6     .05       0
Bank Sta=4986.6,4992.6
XS Rating Curve= 0 ,0
Exp/Cntr=0.3,0.1

Type RM Length L Ch R = 1 ,1514    ,119,119,119
BEGIN DESCRIPTION:
Mapping XS f422b8e9
END DESCRIPTION:
XS GIS Cut Line= 3
      2337642.12     13233040.18      2337374.29     13233315.35
      2337223.86     13233458.43
#Sta/Elev= 30
  4752.9  109.41    4773  109.69  4796.1  108.82  4803.2  109.67  4817.4  109.69
  4838.5  108.26  4859.8  108.15  4887.9  106.92  4895.1  107.21  4937.5  105.61
    4980  105.46  4991.1  103.82  4993.9  103.32  4997.1  103.82  5001.1  104.43
  5008.3  104.25  5029.4  105.61  5050.7  105.43  5063.2  106.42    5079  106.14
    5086  106.72  5130.6  106.94  5205.5   108.2  5248.7  108.56  5269.4   109.3
    5277  108.88    5284  109.92  5312.2  109.89  5333.6  110.69  5344.5  110.33
#Mann= 8 ,-1 , 0
  4752.9     .05       0    4773     .08       0  4991.1     .04       0
  4997.1     .08       0  5063.2     .08       0  5130.6     .05       0
  5205.5      .1       0  5269.4     .05       0
Bank Sta=4991.1,4997.1
XS Rating Curve= 0 ,0
Exp/Cntr=0.3,0.1

Type RM Length L Ch R = 1 ,1395    ,200,200,200
BEGIN DESCRIPTION:
UNT022 IN PECR 3.0
END DESCRIPTION:
XS GIS Cut Line= 4
      2337650.89     13232984.73      2337564.12     13233015.97
      2337340.16     13233264.23      2337190.83     13233444.81
#Sta/Elev= 30
  4787.3  108.18  4809.6  107.72  4927.1   105.1  4965.3  105.72 4972.73  105.71
  5004.6  103.42  5075.8  105.59  5104.2  107.31    5111  106.16  5143.9  106.25
  5224.7  107.78  5231.1  112.34  5234.5  111.84  5253.3  112.98  5259.8  110.45
  5267.7  112.81  5274.1  111.51    5282  113.73  5288.5  110.49  5302.8  114.64
  5309.3  112.54  5317.2  114.37  5323.6  112.16    5338  111.47  5366.6  114.26
  5373.1  112.53  5387.5  112.18  5395.3  113.21  5409.6  112.04  5448.2   112.6
#Mann= 7 ,-1 , 0
  4787.3     .08       0  4809.6     .05       0  4965.3     .08       0
 4972.73     .03       0  5075.8     .05       0  5143.9     .08       0
  5234.5      .1       0
Bank Sta=4972.73,5075.8
XS Rating Curve= 0 ,0
Exp/Cntr=0.3,0.1

Type RM Length L Ch R = 1 ,1195    ,468,468,468
BEGIN DESCRIPTION:
UNT022 IN PECR 2.0
END DESCRIPTION:
XS GIS Cut Line= 3
      2337641.26      13232737.3      2337535.87      13232764.6
      2337113.51     13233315.32
#Sta/Elev= 30
  4686.8  119.64  4700.3  118.03  4705.5   119.2  4711.1  115.75  4721.4  113.34
  4731.8  108.09  4740.9  105.39  4746.1  109.03  4752.4  104.84  4762.8  103.38
    4811  103.47  4817.1  102.07  4966.9  103.85    5008  104.15  5031.3  106.03
  5209.9  106.96  5295.1  110.09  5309.6  108.96  5315.9  110.48  5338.6  109.94
  5344.9  111.33  5373.9  109.67  5380.2  111.45    5403  111.14  5409.3  113.08
  5430.6   112.9  5438.3  112.24  5444.6  113.64  5452.8  112.04  5489.7  111.81
#Mann= 5 ,-1 , 0
  4686.8      .1       0  4966.9     .03       0    5008     .05       0
    5008      .1       0  5430.6     .05       0
Bank Sta=4966.9,5008
XS Rating Curve= 0 ,0
Exp/Cntr=0.3,0.1

Type RM Length L Ch R = 1 ,727     ,586,586,586
BEGIN DESCRIPTION:
Mapping XS 1c384d68
END DESCRIPTION:
XS GIS Cut Line= 3
      2337760.15     13232612.21      2337625.63     13232477.69
      2337092.22     13232499.37
#Sta/Elev= 30
  4714.3  113.38  4719.8  117.68  4726.9  120.11    4741  120.33  4748.1  118.47
  4755.2  113.84  4769.3  108.87  4783.4  101.26  4804.7   99.53  4818.8  100.18
  4861.2    99.7  4912.5  100.54  4928.2  100.16  4962.5   99.68  4972.5   98.38
  4992.3   97.12  5002.3   98.05  5007.3   97.68  5022.6   99.52  5062.6  104.86
  5092.6  107.17  5122.6  110.46  5202.7  114.51  5250.5  116.31  5282.8  116.92
  5312.8  119.11  5342.8  118.89  5422.9  121.96  5433.1   122.8  5438.4  123.25
#Mann= 5 ,-1 , 0
  4714.3      .1       0  4928.2     .05       0  4962.5     .03       0
  5022.6     .05       0  5433.1      .1       0
Bank Sta=4962.5,5022.6
XS Rating Curve= 0 ,0
Exp/Cntr=0.3,0.1

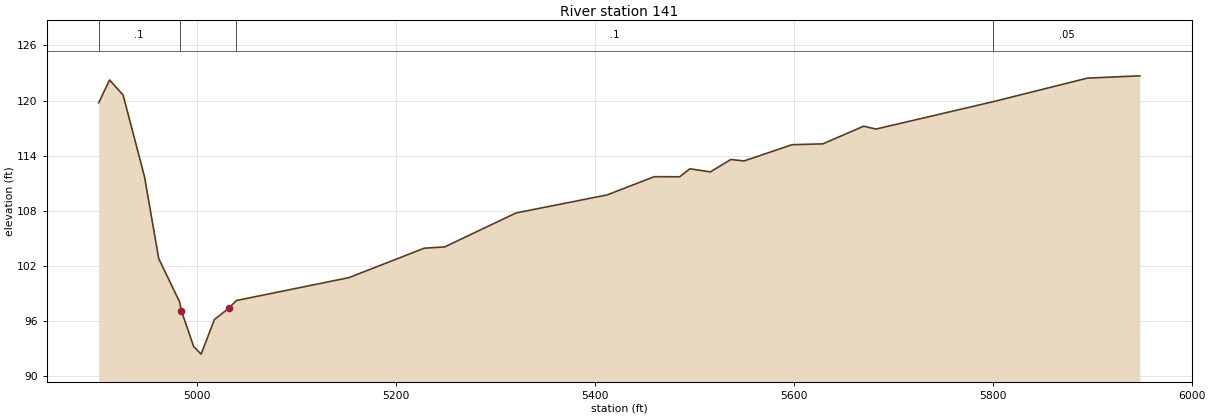
Type RM Length L Ch R = 1 ,141     ,0,0,0
BEGIN DESCRIPTION:
UNT022 IN PECR 1.0
END DESCRIPTION:
XS GIS Cut Line= 3
      2338046.45     13232222.77      2337829.63     13232039.32
      2337087.48     13232212.92
#Sta/Elev= 30
  4901.7  119.77  4912.6  122.25  4926.2  120.61  4947.7  111.73    4962  102.82
  4982.9   98.13 4984.77   97.14  4997.1   93.26  5004.6   92.43    5018    96.2
  5032.3   97.41    5040   98.26  5153.1  100.75  5228.8  103.95  5249.3  104.09
  5321.2  107.79  5412.4  109.74    5460  111.73  5485.5  111.72  5495.8  112.59
  5516.3  112.25  5536.9   113.6  5550.2  113.44  5598.5  115.21  5629.3   115.3
  5670.4  117.22  5682.8  116.91  5800.6  119.89  5895.2  122.45  5947.9   122.7
#Mann= 4 ,-1 , 0
  4901.7      .1       0  4982.9     .03       0    5040      .1       0
  5800.6     .05       0
Bank Sta=4984.77,5032.3
XS Rating Curve= 0 ,0
Exp/Cntr=0.3,0.1

Chan Stop Cuts=-1
Use User Specified Reach Order=0
Composite Channel Slope=5