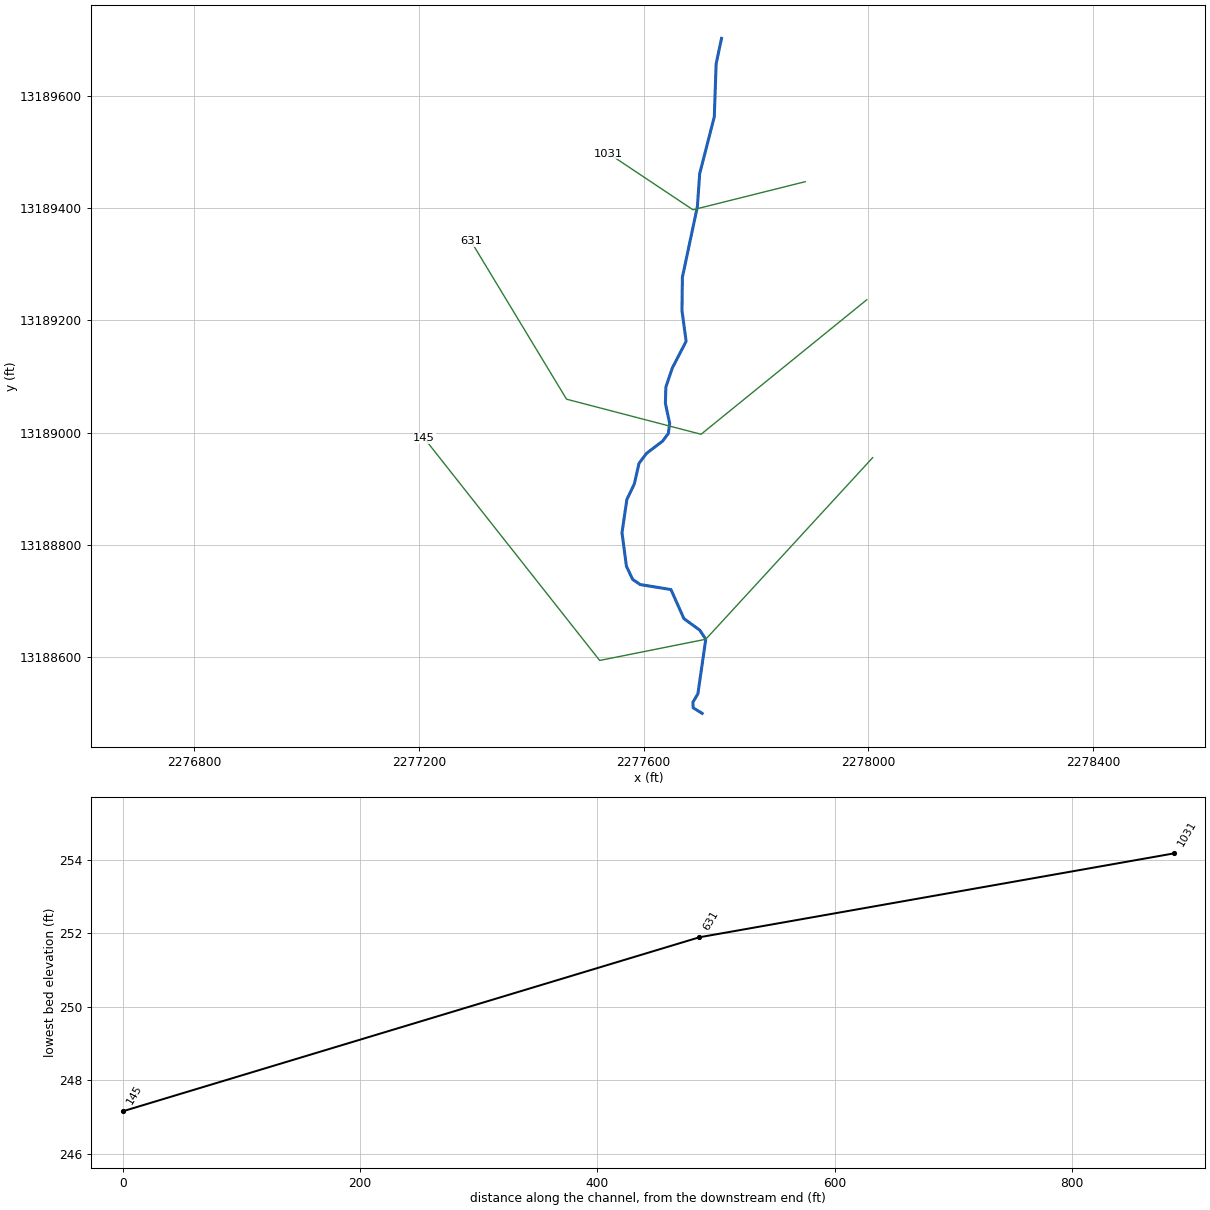
--- UNT025 IN PECR.prj (project) ---

Proj Title=UNT025 IN PECR Base Level Engineering
Current Plan=p01
Default Exp/Contr=0.3,0.1
English Units
Geom File=g01
Flow File=f01
Plan File=p01
Y Axis Title=Elevation
X Axis Title(PF)=Main Channel Distance
X Axis Title(XS)=Station
BEGIN DESCRIPTION:
UNT025 IN PECR
END DESCRIPTION:
DSS Export Rating Curves= 0
DSS Export Rating Curve Sorted= 0
DSS Export Volume Flow Curves= 0
DXF OffsetX= 0
DXF OffsetY= 0
DXF ScaleX= 1
DXF ScaleY= 10

--- UNT025 IN PECR.p01 (plan) ---

Plan Title=Multiple Run
Short Identifier=Multiple
Geom File=g01
Flow File=f01
Subcritical Flow
K Sum by GR= 0
Std Step Tol= 0.01
Critical Tol= 0.01
Num of Std Step Trials= 20
Max Error Tol= 0.3
Flow Tol Ratio= 0.001
Split Flow NTrial= 30
Split Flow Tol= 0.02
Split Flow Ratio= 0.02
Log Output Level= 0
Friction Slope Method= 1
Unsteady Friction Slope Method= 2
Unsteady Bridges Friction Slope Method= 1
Parabolic Critical Depth
Global Vel Dist=  1 , 1 , 1
Global Log Level= 0
CheckData=True
Encroach Param= -1, 0, 0, 0
BEGIN DESCRIPTION:
Multiple Run
END DESCRIPTION:

--- UNT025 IN PECR.f01 (steady flow) ---

Flow Title=Multiple
Program Version=4.10
Number of Profiles= 7
Profile Names=10-year,25-year,50-year,1pct_min,100-year,1pct_plu,500-year
River Rch & RM=UNT025 IN PECR,Reach-1         ,1031
     144     191     228     200     271     367     388
Boundary for River Rch & Prof#=UNT025 IN PECR,Reach-1         , 1
Up Type= 0
Dn Type= 3
Dn Slope=0.009
Boundary for River Rch & Prof#=UNT025 IN PECR,Reach-1         , 2
Up Type= 0
Dn Type= 3
Dn Slope=0.009
Boundary for River Rch & Prof#=UNT025 IN PECR,Reach-1         , 3
Up Type= 0
Dn Type= 3
Dn Slope=0.009
Boundary for River Rch & Prof#=UNT025 IN PECR,Reach-1         , 4
Up Type= 0
Dn Type= 3
Dn Slope=0.009
Boundary for River Rch & Prof#=UNT025 IN PECR,Reach-1         , 5
Up Type= 0
Dn Type= 3
Dn Slope=0.009
Boundary for River Rch & Prof#=UNT025 IN PECR,Reach-1         , 6
Up Type= 0
Dn Type= 3
Dn Slope=0.009
Boundary for River Rch & Prof#=UNT025 IN PECR,Reach-1         , 7
Up Type= 0
Dn Type= 3
Dn Slope=0.009
DSS Import GetInterval= 0
DSS Import GetPeak= 0
DSS Import FillOption= 0

--- UNT025 IN PECR.g01 (geometry) ---

Geom Title=Existing Conditions
Program Version=4.10

River Reach=UNT025 IN PECR  ,Reach-1
Reach XY= 30
      2277738.65     13189702.13      2277729.02     13189656.76
      2277725.75     13189562.45      2277699.71     13189461.02
      2277695.65     13189402.63      2277668.87     13189276.42
      2277668.25     13189217.02      2277675.59     13189162.56
      2277651.15     13189115.43      2277639.47     13189081.03
      2277638.64      13189052.1      2277646.29     13189016.28
      2277643.88     13188998.49      2277633.71     13188984.87
      2277604.96     13188962.96      2277591.66      13188945.3
      2277583.35     13188908.68      2277570.04     13188880.81
      2277561.39     13188821.79      2277569.21     13188762.22
      2277580.37     13188738.56      2277593.88     13188729.38
      2277648.57     13188720.48      2277671.67     13188668.69
       2277699.8      13188648.3      2277710.56     13188631.98
       2277696.5     13188534.67      2277687.65     13188519.83
      2277688.17     13188509.93      2277704.11       13188500.

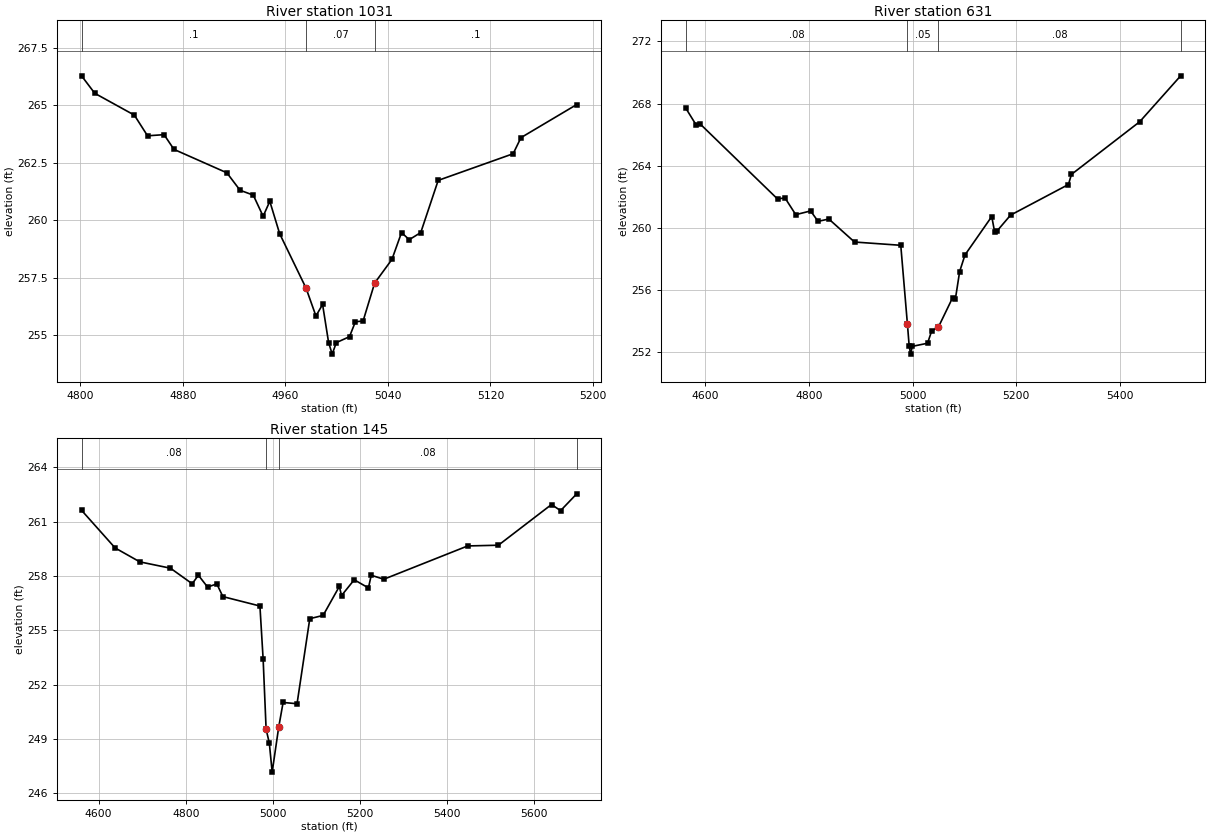
Type RM Length L Ch R = 1 ,1031    ,400,400,400
BEGIN DESCRIPTION:
UNT025 IN PECR 2.0
END DESCRIPTION:
XS GIS Cut Line= 3
      2277887.71     13189446.85      2277687.72     13189396.85
      2277537.74     13189496.84
#Sta/Elev= 30
  4800.9  266.28  4811.2  265.52  4842.1  264.57  4852.4  263.67  4865.3  263.72
    4873  263.08  4914.3  262.06  4924.6   261.3  4934.9  261.09  4942.6  260.17
  4947.8  260.82  4955.5  259.41  4976.1  257.04  4983.8  255.83    4989  256.33
  4993.7  254.67  4996.5  254.17  4999.7  254.67    5010  254.93  5014.6  255.58
  5020.6  255.61  5029.6  257.26  5043.1  258.29  5050.6  259.46  5056.6  259.15
  5065.6  259.46  5079.2  261.73  5137.7  262.89  5143.8  263.59  5187.3  265.03
#Mann= 3 , 0 , 0
  4800.9      .1       0  4976.1     .07       0  5029.6      .1       0
Bank Sta=4976.1,5029.6
XS Rating Curve= 0 ,0
Exp/Cntr=0.3,0.1

Type RM Length L Ch R = 1 ,631     ,486,486,486
BEGIN DESCRIPTION:
Mapping XS 2949d286
END DESCRIPTION:
XS GIS Cut Line= 4
      2277997.29      13189236.6      2277702.17     13188997.03
      2277462.59     13189059.53      2277292.57     13189340.59
#Sta/Elev= 30
  4561.5  267.74  4582.6   266.6    4589  266.72  4739.2  261.87  4753.6  261.94
  4774.4  260.86  4803.1   261.1  4817.5  260.43  4838.3  260.58  4887.9   259.1
  4977.2  258.89    4990  253.84  4993.5  252.39  4996.3  251.89  4999.5  252.39
  5028.9  252.59    5037  253.39  5049.6  253.61  5077.5  255.53  5082.7  255.44
  5090.9   257.2  5101.2  258.27  5152.9  260.74  5158.4  259.76  5163.6  259.83
  5189.2  260.83    5301   262.8  5306.8  263.45  5438.7  266.84  5517.7  269.79
#Mann= 4 ,-1 , 0
  4561.5     .08       0    4990     .05       0  5049.6     .08       0
  5517.7      .1       0
Bank Sta=4990,5049.6
XS Rating Curve= 0 ,0
Exp/Cntr=0.3,0.1

Type RM Length L Ch R = 1 ,145     ,0,0,0
BEGIN DESCRIPTION:
UNT025 IN PECR 1.0
END DESCRIPTION:
XS GIS Cut Line= 4
      2278007.74     13188955.38      2277710.56     13188631.98
      2277521.61     13188594.25      2277209.11     13188990.09
#Sta/Elev= 30
  4560.8  261.63  4637.8  259.55  4694.5  258.78  4764.8  258.43  4814.7  257.57
  4828.9  258.04  4849.9  257.39  4871.2  257.56  4885.1  256.86  4970.1  256.34
  4977.5  253.39  4984.3  249.53  4991.7  248.76  4998.2  247.16  5013.1  249.63
  5023.3  251.01  5055.3  250.94  5084.5  255.64  5115.1  255.82  5152.3  257.42
  5157.4  256.92  5186.5  257.79  5219.1  257.34  5225.5  258.04  5254.4  257.82
  5446.8  259.66  5517.3   259.7  5639.2  261.95    5660  261.61    5697  262.54
#Mann= 4 ,-1 , 0
  4560.8     .08       0  4984.3     .05       0  5013.1     .08       0
    5697      .1       0
Bank Sta=4984.3,5013.1
XS Rating Curve= 0 ,0
Exp/Cntr=0.3,0.1

Chan Stop Cuts=-1
Use User Specified Reach Order=0
Composite Channel Slope=5