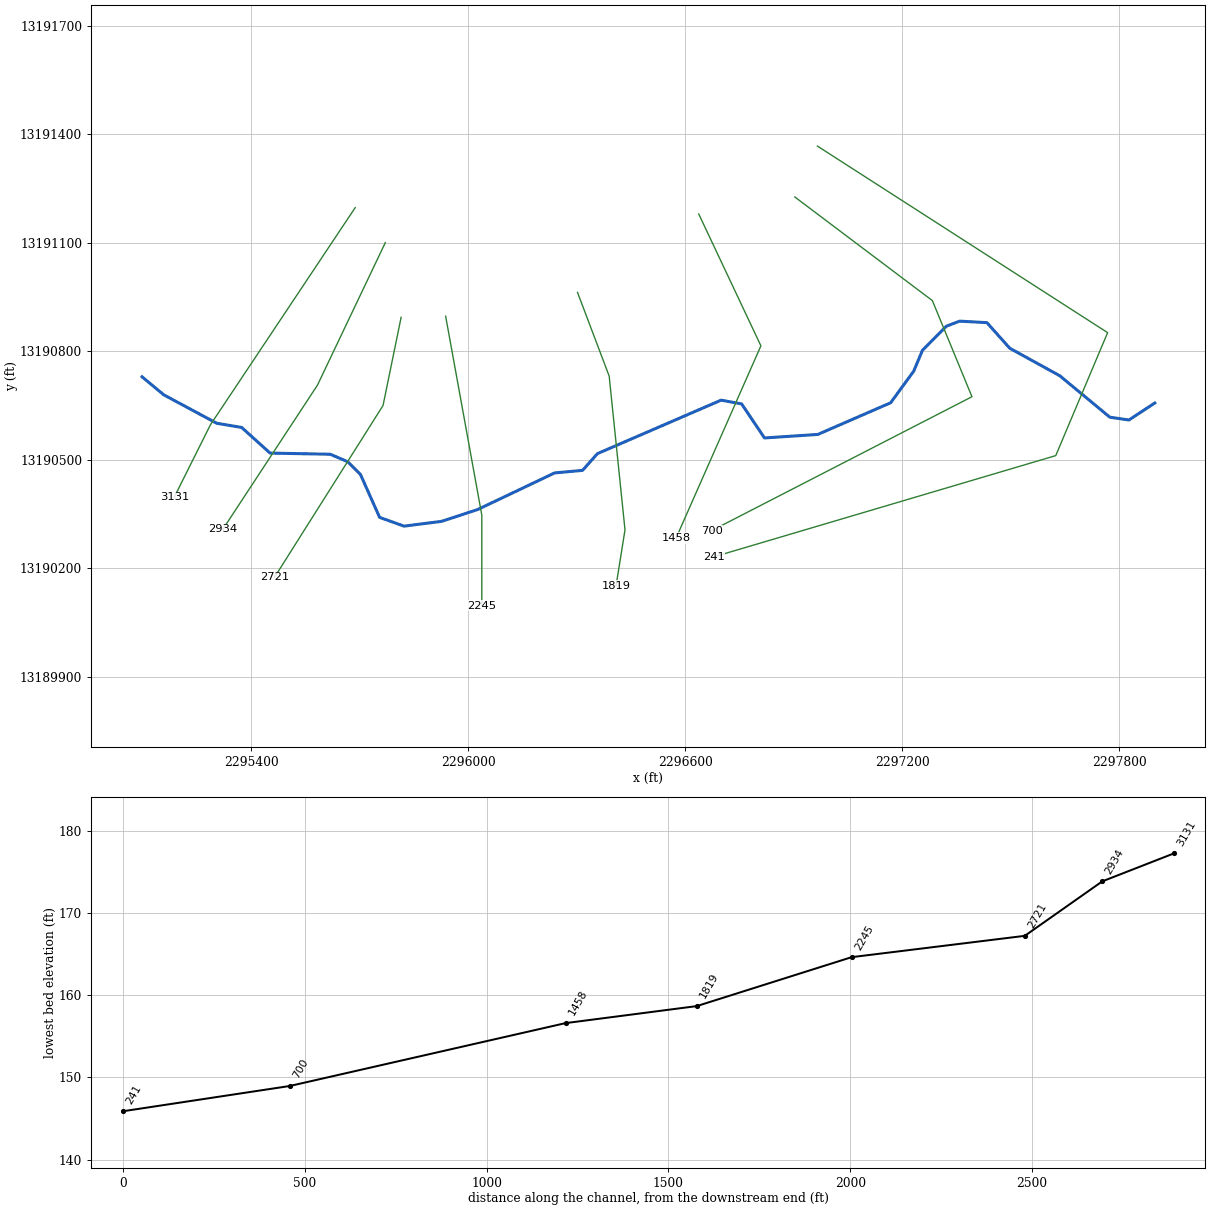
--- UNT026 IN PECR.prj (project) ---

Proj Title=UNT026 IN PECR Base Level Engineering
Current Plan=p01
Default Exp/Contr=0.3,0.1
English Units
Geom File=g01
Flow File=f01
Plan File=p01
Y Axis Title=Elevation
X Axis Title(PF)=Main Channel Distance
X Axis Title(XS)=Station
BEGIN DESCRIPTION:
UNT026 IN PECR
END DESCRIPTION:
DSS Export Rating Curves= 0
DSS Export Rating Curve Sorted= 0
DSS Export Volume Flow Curves= 0
DXF OffsetX= 0
DXF OffsetY= 0
DXF ScaleX= 1
DXF ScaleY= 10

--- UNT026 IN PECR.p01 (plan) ---

Plan Title=Multiple Run
Short Identifier=Multiple
Geom File=g01
Flow File=f01
Subcritical Flow
K Sum by GR= 0
Std Step Tol= 0.01
Critical Tol= 0.01
Num of Std Step Trials= 20
Max Error Tol= 0.3
Flow Tol Ratio= 0.001
Split Flow NTrial= 30
Split Flow Tol= 0.02
Split Flow Ratio= 0.02
Log Output Level= 0
Friction Slope Method= 1
Unsteady Friction Slope Method= 2
Unsteady Bridges Friction Slope Method= 1
Parabolic Critical Depth
Global Vel Dist=  1 , 1 , 1
Global Log Level= 0
CheckData=True
Encroach Param= -1, 0, 0, 0
BEGIN DESCRIPTION:
Multiple Run
END DESCRIPTION:

--- UNT026 IN PECR.f01 (steady flow) ---

Flow Title=Multiple
Program Version=4.10
Number of Profiles= 7
Profile Names=10-year,25-year,50-year,1pct_min,100-year,1pct_plu,500-year
River Rch & RM=UNT026 IN PECR,Reach-1         ,3131
     395     548     675     608     823    1112    1231
Boundary for River Rch & Prof#=UNT026 IN PECR,Reach-1         , 1
Up Type= 0
Dn Type= 3
Dn Slope=0.005
Boundary for River Rch & Prof#=UNT026 IN PECR,Reach-1         , 2
Up Type= 0
Dn Type= 3
Dn Slope=0.005
Boundary for River Rch & Prof#=UNT026 IN PECR,Reach-1         , 3
Up Type= 0
Dn Type= 3
Dn Slope=0.005
Boundary for River Rch & Prof#=UNT026 IN PECR,Reach-1         , 4
Up Type= 0
Dn Type= 3
Dn Slope=0.005
Boundary for River Rch & Prof#=UNT026 IN PECR,Reach-1         , 5
Up Type= 0
Dn Type= 3
Dn Slope=0.005
Boundary for River Rch & Prof#=UNT026 IN PECR,Reach-1         , 6
Up Type= 0
Dn Type= 3
Dn Slope=0.005
Boundary for River Rch & Prof#=UNT026 IN PECR,Reach-1         , 7
Up Type= 0
Dn Type= 3
Dn Slope=0.005
DSS Import GetInterval= 0
DSS Import GetPeak= 0
DSS Import FillOption= 0

--- UNT026 IN PECR.g01 (geometry) ---

Geom Title=Existing Conditions

River Reach=UNT026 IN PECR,Reach-1
Reach XY= 30
      2295098.63     13190729.22      2295158.80     13190679.42
      2295304.93     13190600.96      2295373.98     13190589.30
      2295452.49     13190518.45      2295618.81     13190515.27
      2295666.97     13190494.71      2295702.31     13190459.40
      2295755.25     13190340.77      2295822.65     13190316.52
      2295926.52     13190329.82      2296025.93     13190362.31
      2296239.04     13190463.67      2296316.13     13190470.69
      2296357.22     13190516.92      2296699.10     13190664.73
      2296755.83     13190654.41      2296819.01     13190560.29
      2296966.41     13190570.04      2297167.65     13190657.53
      2297231.49     13190744.95      2297255.61     13190802.65
      2297321.62     13190869.13      2297358.28     13190883.14
      2297433.81     13190878.99      2297496.85     13190808.31
      2297635.12     13190732.21      2297773.37     13190617.77
      2297826.15     13190609.88      2297897.72     13190656.86

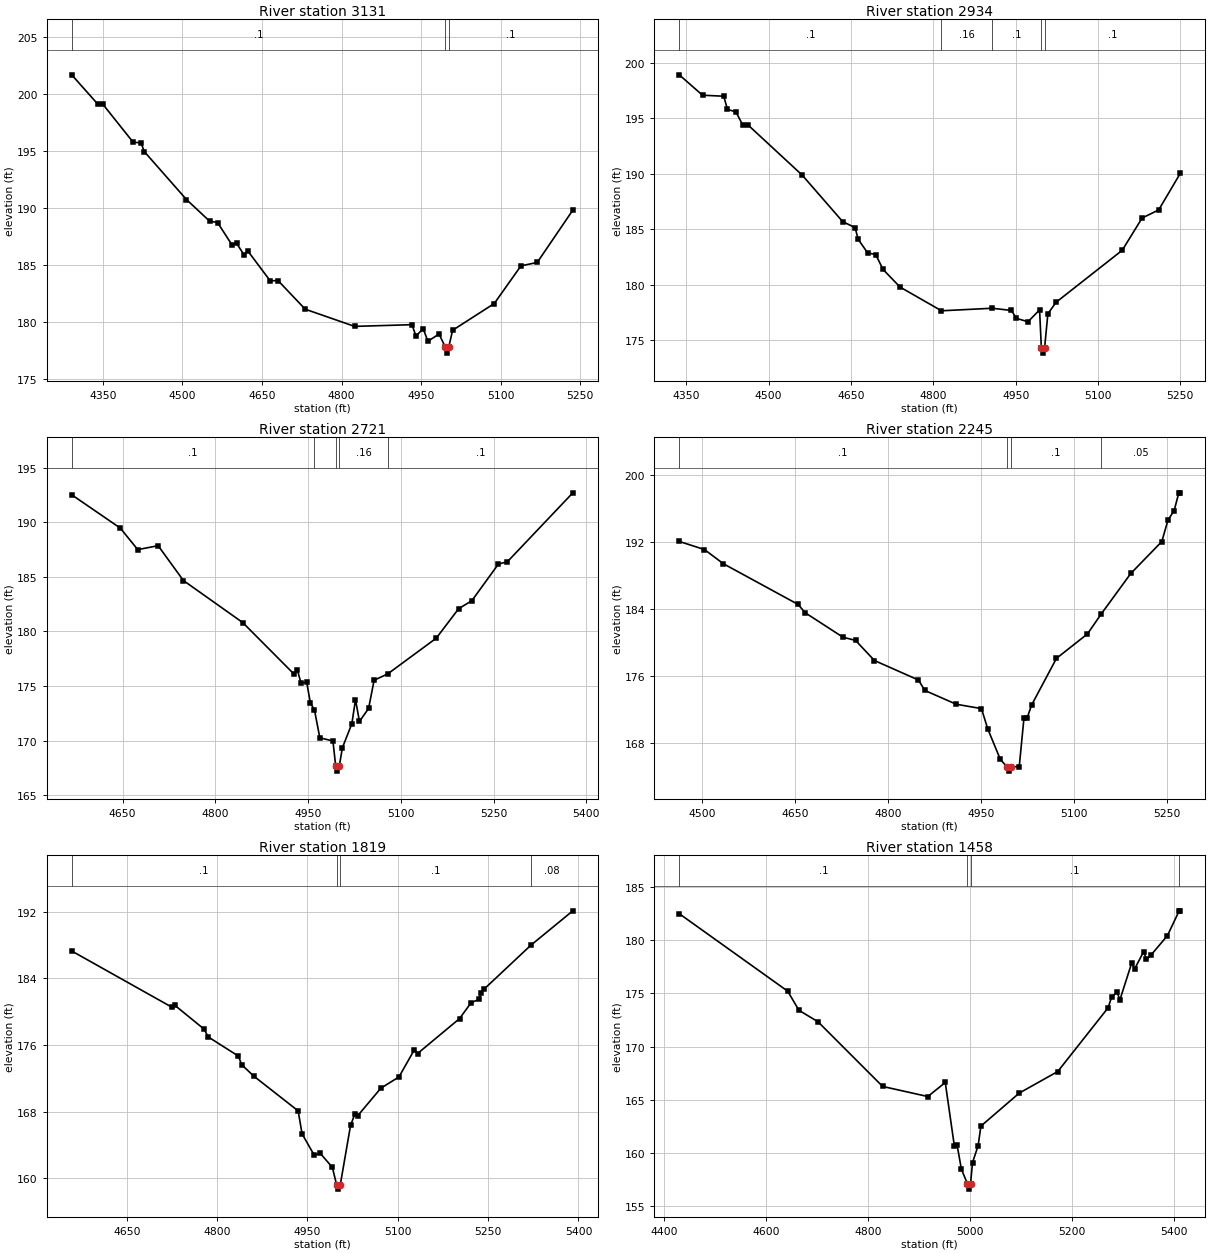
Type RM Length L Ch R = 1,3131,197,197,197
BEGIN DESCRIPTION:
UNT026 IN PECR 5.0
END DESCRIPTION:
XS GIS Cut Line= 3
      2295687.71     13191196.83      2295287.72     13190596.85
      2295187.72     13190396.85
#Sta/Elev= 30
  4291.4  201.69  4341.0  199.09  4350.0  199.11  4407.1  195.77  4422.1  195.71
  4428.1  194.95  4507.7  190.73  4551.3  188.83  4566.3  188.71  4593.3  186.76
  4602.4  186.87  4615.9  185.89  4623.4  186.21  4665.5  183.59  4680.5  183.60
  4731.6  181.09  4824.7  179.58  4932.9  179.73  4940.4  178.72  4953.9  179.39
  4962.9  178.27  4983.9  178.91  4996.0  177.73  4998.7  177.23  5002.0  177.73
  5009.5  179.24  5088.0  181.59  5138.3  184.90  5169.0  185.20  5236.1  189.80
#Mann=3,-1,0
  4291.4     0.1       0  4996.0    0.07       0  5002.0     0.1       0
Bank Sta=4996,5002
Exp/Cntr=0.3,0.1

Type RM Length L Ch R = 1,2934,213,213,213
BEGIN DESCRIPTION:
Mapping XS 3b02a085
END DESCRIPTION:
XS GIS Cut Line= 3
      2295770.96     13191100.06      2295583.46     13190706.30
      2295321.81     13190307.61
#Sta/Elev= 30
  4337.1  198.94  4379.5  197.10  4418.2  197.01  4424.9  195.82  4440.3  195.60
  4453.1  194.38  4462.5  194.41  4561.1  189.89  4634.8  185.70  4657.5  185.15
  4663.0  184.11  4680.2  182.88  4695.1  182.72  4708.4  181.38  4739.4  179.79
  4814.9  177.65  4907.2  177.88  4942.3  177.68  4951.4  176.97  4972.5  176.66
  4993.6  177.73  4996.8  174.33  4999.6  173.83  5002.8  174.33  5008.7  177.38
  5023.7  178.42  5144.2  183.11  5180.4  186.02  5210.6  186.75  5250.1  190.06
#Mann=5,-1,0
  4337.1     0.1       0  4814.9    0.16       0  4907.2     0.1       0
  4996.8    0.07       0  5002.8     0.1       0
Bank Sta=4996.8,5002.8
Exp/Cntr=0.3,0.1

Type RM Length L Ch R = 1,2721,476,476,476
BEGIN DESCRIPTION:
UNT026 IN PECR 4.0
END DESCRIPTION:
XS GIS Cut Line= 3
      2295814.71     13190893.82      2295764.71     13190650.05
      2295464.68     13190175.01
#Sta/Elev= 30
  4567.6  192.51  4646.2  189.46  4674.4  187.49  4707.4  187.85  4748.3  184.66
  4844.3  180.81  4926.6  176.13  4932.6  176.47  4938.5  175.28  4947.8  175.34
  4953.8  173.42  4960.2  172.84  4969.0  170.26  4990.2  169.97  4994.6  167.71
  4997.4  167.21  5000.6  167.71  5005.5  169.35  5020.8  171.55  5026.7  173.75
  5033.1  171.76  5047.9  172.95  5056.8  175.53  5078.8  176.11  5157.3  179.38
  5193.7  182.09  5214.9  182.81  5257.8  186.16  5272.6  186.39  5378.3  192.69
#Mann=5,-1,0
  4567.6     0.1       0  4960.2    0.16       0  4994.6    0.07       0
  5000.6    0.16       0  5078.8     0.1       0
Bank Sta=4994.6,5000.6
Exp/Cntr=0.3,0.1

Type RM Length L Ch R = 1,2245,426,426,426
BEGIN DESCRIPTION:
UNT026 IN PECR 3.0
END DESCRIPTION:
XS GIS Cut Line= 3
      2295937.72     13190896.86      2296037.72     13190346.85
      2296037.72     13190096.88
#Sta/Elev= 30
  4463.1  192.03  4503.8  191.06  4534.3  189.37  4655.0  184.51  4666.4  183.52
  4727.4  180.60  4747.7  180.22  4778.2  177.82  4849.3  175.49  4859.5  174.25
  4910.3  172.60  4951.0  172.08  4961.1  169.67  4981.5  166.01  4992.4  165.12
  4995.2  164.62  4998.4  165.12  5012.0  165.17  5019.6  170.95  5024.6  170.95
  5032.1  172.53  5072.1  178.08  5122.1  180.99  5144.4  183.38  5192.1  188.21
  5242.1  192.01  5252.1  194.57  5262.1  195.72  5269.6  197.83  5272.1  197.83
#Mann=4,-1,0
  4463.1     0.1       0  4992.4    0.07       0  4998.4     0.1       0
  5144.4    0.05       0
Bank Sta=4992.4,4998.4
Exp/Cntr=0.3,0.1

Type RM Length L Ch R = 1,1819,361,361,361
BEGIN DESCRIPTION:
UNT026 IN PECR 2.0
END DESCRIPTION:
XS GIS Cut Line= 4
      2296302.20     13190962.58      2296389.71     13190731.30
      2296433.46     13190306.30      2296408.59     13190150.91
#Sta/Elev= 30
  4558.7  187.30  4724.8  180.55  4730.1  180.76  4778.7  177.89  4785.1  176.98
  4835.5  174.66  4840.6  173.65  4860.7  172.27  4934.6  168.08  4941.1  165.32
  4961.2  162.76  4971.3  162.97  4991.4  161.29  4998.5  159.17  5001.2  158.67
  5004.5  159.17  5021.6  166.33  5028.7  167.70  5033.7  167.51  5071.8  170.80
  5102.0  172.16  5127.7  175.45  5132.8  174.97  5202.5  179.17  5221.8  181.09
  5235.5  181.50  5237.8  182.30  5242.9  182.69  5320.7  187.98  5390.6  192.13
#Mann=4,-1,0
  4558.7     0.1       0  4998.5    0.07       0  5004.5     0.1       0
  5320.7    0.08       0
Bank Sta=4998.5,5004.5
Exp/Cntr=0.3,0.1

Type RM Length L Ch R = 1,1458,758,758,758
BEGIN DESCRIPTION:
Mapping XS 2dbd5aed
END DESCRIPTION:
XS GIS Cut Line= 3
      2296637.21     13191179.42      2296809.06     13190814.88
      2296574.68     13190283.60
#Sta/Elev= 30
  4429.1  182.48  4642.0  175.20  4664.1  173.40  4701.4  172.33  4828.3  166.25
  4917.0  165.30  4951.3  166.62  4969.1  160.67  4974.6  160.72  4983.0  158.46
  4994.9  157.10  4997.7  156.60  5000.9  157.10  5004.8  159.10  5015.8  160.68
  5021.2  162.52  5096.7  165.63  5172.1  167.65  5270.8  173.63  5278.1  174.67
  5288.7  175.10  5294.1  174.38  5317.4  177.87  5322.9  177.28  5340.8  178.92
  5346.2  178.18  5354.6  178.56  5387.4  180.42  5410.5  182.75  5412.8  182.75
#Mann=4,-1,0
  4429.1     0.1       0  4994.9    0.07       0  5000.9     0.1       0
  5410.5    0.08       0
Bank Sta=4994.9,5000.9
Exp/Cntr=0.3,0.1

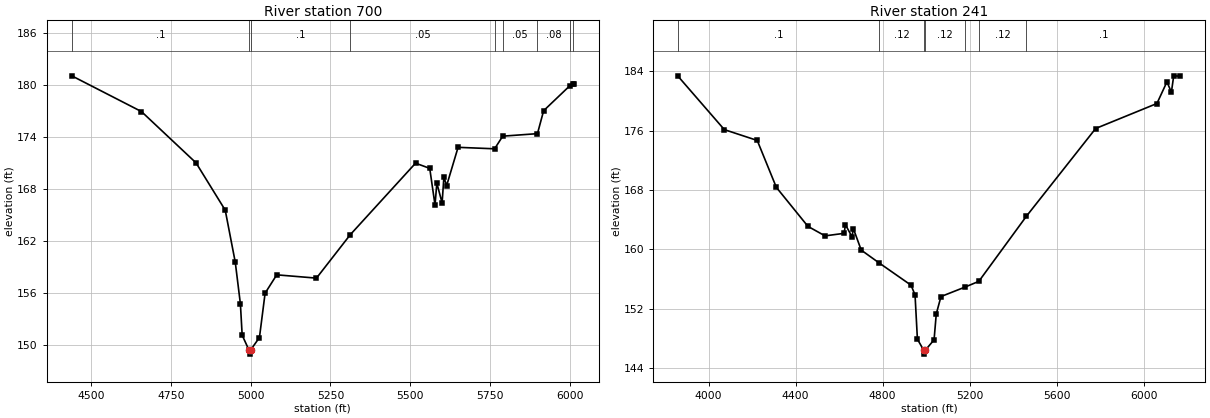
Type RM Length L Ch R = 1,700,459,459,459
BEGIN DESCRIPTION:
Mapping XS a22a2ae3
END DESCRIPTION:
XS GIS Cut Line= 4
      2296902.77     13191226.36      2297283.02     13190939.88
      2297392.40     13190674.25      2296673.60     13190304.44
#Sta/Elev= 30
  4440.3  181.11  4658.5  176.98  4829.2  171.06  4920.7  165.59  4952.1  159.58
  4968.2  154.76  4973.7  151.15  4994.6  149.46  4997.3  148.96  5000.6  149.46
  5027.8  150.88  5045.5  156.00  5081.9  158.12  5206.3  157.74  5312.2  162.76
  5516.5  171.02  5560.9  170.42  5577.4  166.18  5583.1  168.71  5599.6  166.43
  5605.2  169.41  5613.8  168.43  5649.6  172.85  5763.9  172.68  5789.4  174.14
  5898.1  174.43  5917.4  177.08  5999.9  179.98  6008.9  180.18  6012.0  180.18
#Mann=9,-1,0
  4440.3     0.1       0  4994.6    0.07       0  5000.6     0.1       0
  5312.2    0.05       0  5763.9     0.1       0  5789.4    0.05       0
  5898.1    0.08       0  5999.9     0.1       0  6008.9    0.08       0
Bank Sta=4994.6,5000.6
Exp/Cntr=0.3,0.1

Type RM Length L Ch R = 1,241,0,0,0
BEGIN DESCRIPTION:
UNT026 IN PECR 1.0
END DESCRIPTION:
XS GIS Cut Line= 4
      2296965.29     13191366.98      2297767.40     13190851.33
      2297624.01     13190511.48      2296678.69     13190231.61
#Sta/Elev= 30
  3860.3  183.31  4072.2  176.15  4223.5  174.69  4311.3  168.37  4456.6  163.11
  4535.2  161.83  4623.0  162.17  4629.0  163.33  4659.4  161.70  4665.3  162.82
  4701.6  159.91  4783.5  158.19  4930.7  155.18  4949.0  153.87  4959.9  147.90
  4989.4  146.39  4992.1  145.89  4995.4  146.39  5036.5  147.82  5046.6  151.31
  5068.3  153.65  5178.2  154.92  5242.3  155.70  5461.4  164.49  5779.4  176.30
  6061.1  179.67  6107.0  182.58  6127.6  181.20  6138.3  183.40  6168.6  183.35
#Mann=7,-1,0
  3860.3     0.1       0  4783.5    0.12       0  4989.4    0.07       0
  4995.4    0.12       0  5178.2    0.05       0  5242.3    0.12       0
  5461.4     0.1       0
Bank Sta=4989.4,4995.4
Exp/Cntr=0.3,0.1

Chan Stop Cuts=-1