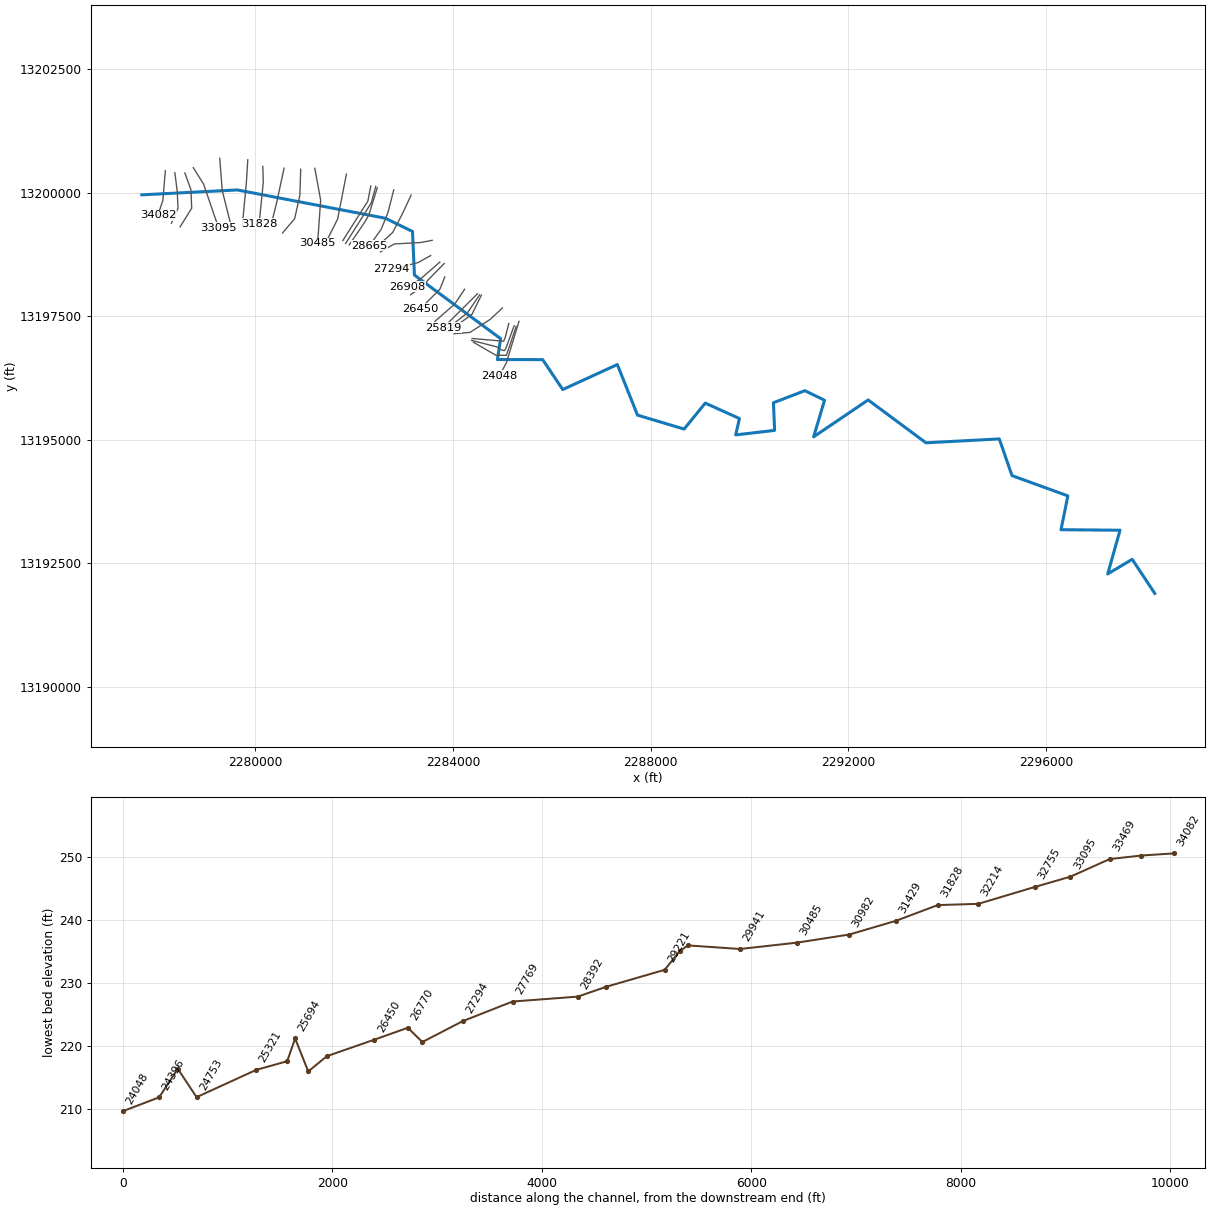
--- UNT027 IN PECR.prj (project) ---

Proj Title=UNT027 IN PECR Base Level Engineering
Current Plan=p01
Default Exp/Contr=0.3,0.1
English Units
Geom File=g01
Flow File=f01
Plan File=p01
Y Axis Title=Elevation
X Axis Title(PF)=Main Channel Distance
X Axis Title(XS)=Station
BEGIN DESCRIPTION:
UNT027 IN PECR
END DESCRIPTION:
DSS Export Rating Curves= 0
DSS Export Rating Curve Sorted= 0
DSS Export Volume Flow Curves= 0
DXF OffsetX= 0
DXF OffsetY= 0
DXF ScaleX= 1
DXF ScaleY= 10

--- UNT027 IN PECR.p01 (plan) ---

Plan Title=Multiple Run
Short Identifier=Multiple
Geom File=g01
Flow File=f01
Subcritical Flow
K Sum by GR= 0
Std Step Tol= 0.01
Critical Tol= 0.01
Num of Std Step Trials= 20
Max Error Tol= 0.3
Flow Tol Ratio= 0.001
Split Flow NTrial= 30
Split Flow Tol= 0.02
Split Flow Ratio= 0.02
Log Output Level= 0
Friction Slope Method= 1
Unsteady Friction Slope Method= 2
Unsteady Bridges Friction Slope Method= 1
Parabolic Critical Depth
Global Vel Dist=  1 , 1 , 1
Global Log Level= 0
CheckData=True
Encroach Param= -1, 0, 0, 0
BEGIN DESCRIPTION:
Multiple Run
END DESCRIPTION:

--- UNT027 IN PECR.f01 (steady flow) ---

Flow Title=Multiple
Program Version=4.10
Number of Profiles= 7
Profile Names=10-year,25-year,50-year,1pct_min,100-year,1pct_plu,500-year
River Rch & RM=UNT027 IN PECR,Reach-1         ,34082
     190     255     308     274     370     500     541
River Rch & RM=UNT027 IN PECR,Reach-1         ,33095
     215     291     353     315     425     575     626
River Rch & RM=UNT027 IN PECR,Reach-1         ,29364
     266     364     444     399     539     729     805
River Rch & RM=UNT027 IN PECR,Reach-1         ,24048
     432     606     752     684     925    1252    1424
River Rch & RM=UNT027 IN PECR,Reach-1         ,19297
     639     909    1138    1043    1411    1908    2200
River Rch & RM=UNT027 IN PECR,Reach-1         ,7271
     781    1118    1405    1292    1747    2363    2738
Boundary for River Rch & Prof#=UNT027 IN PECR,Reach-1         , 1
Up Type= 0
Dn Type= 3
Dn Slope=0.0014
Boundary for River Rch & Prof#=UNT027 IN PECR,Reach-1         , 2
Up Type= 0
Dn Type= 3
Dn Slope=0.0014
Boundary for River Rch & Prof#=UNT027 IN PECR,Reach-1         , 3
Up Type= 0
Dn Type= 3
Dn Slope=0.0014
Boundary for River Rch & Prof#=UNT027 IN PECR,Reach-1         , 4
Up Type= 0
Dn Type= 3
Dn Slope=0.0014
Boundary for River Rch & Prof#=UNT027 IN PECR,Reach-1         , 5
Up Type= 0
Dn Type= 3
Dn Slope=0.0014
Boundary for River Rch & Prof#=UNT027 IN PECR,Reach-1         , 6
Up Type= 0
Dn Type= 3
Dn Slope=0.0014
Boundary for River Rch & Prof#=UNT027 IN PECR,Reach-1         , 7
Up Type= 0
Dn Type= 3
Dn Slope=0.0014
DSS Import GetInterval= 0
DSS Import GetPeak= 0
DSS Import FillOption= 0

--- UNT027 IN PECR.g01 (geometry) ---

Geom Title=Existing Conditions
Program Version=4.10

River Reach=UNT027 IN PECR  ,Reach-1
Reach XY= 30
      2277711.78     13199957.35       2279642.4     13200056.32
      2282636.24     13199483.73      2283184.76     13199215.85
      2283223.78     13198333.84      2284967.07     13197046.97
      2284901.49     13196624.68      2285815.98      13196623.1
      2286222.84     13196017.91      2287326.34     13196523.35
      2287734.26     13195500.07      2288676.34     13195218.02
      2289104.38     13195743.42      2289795.74     13195431.44
      2289719.14     13195100.02      2290506.71     13195191.44
      2290482.37     13195750.45      2291117.89     13195994.99
      2291515.94     13195801.17      2291294.96     13195060.41
      2292397.69     13195806.88      2293566.07      13194940.1
      2295049.11      13195018.7      2295305.88     13194276.68
      2296435.57     13193866.07      2296296.94     13193181.83
      2297490.38     13193171.37      2297241.23     13192286.39
      2297736.59     13192582.86      2298192.78     13191892.44

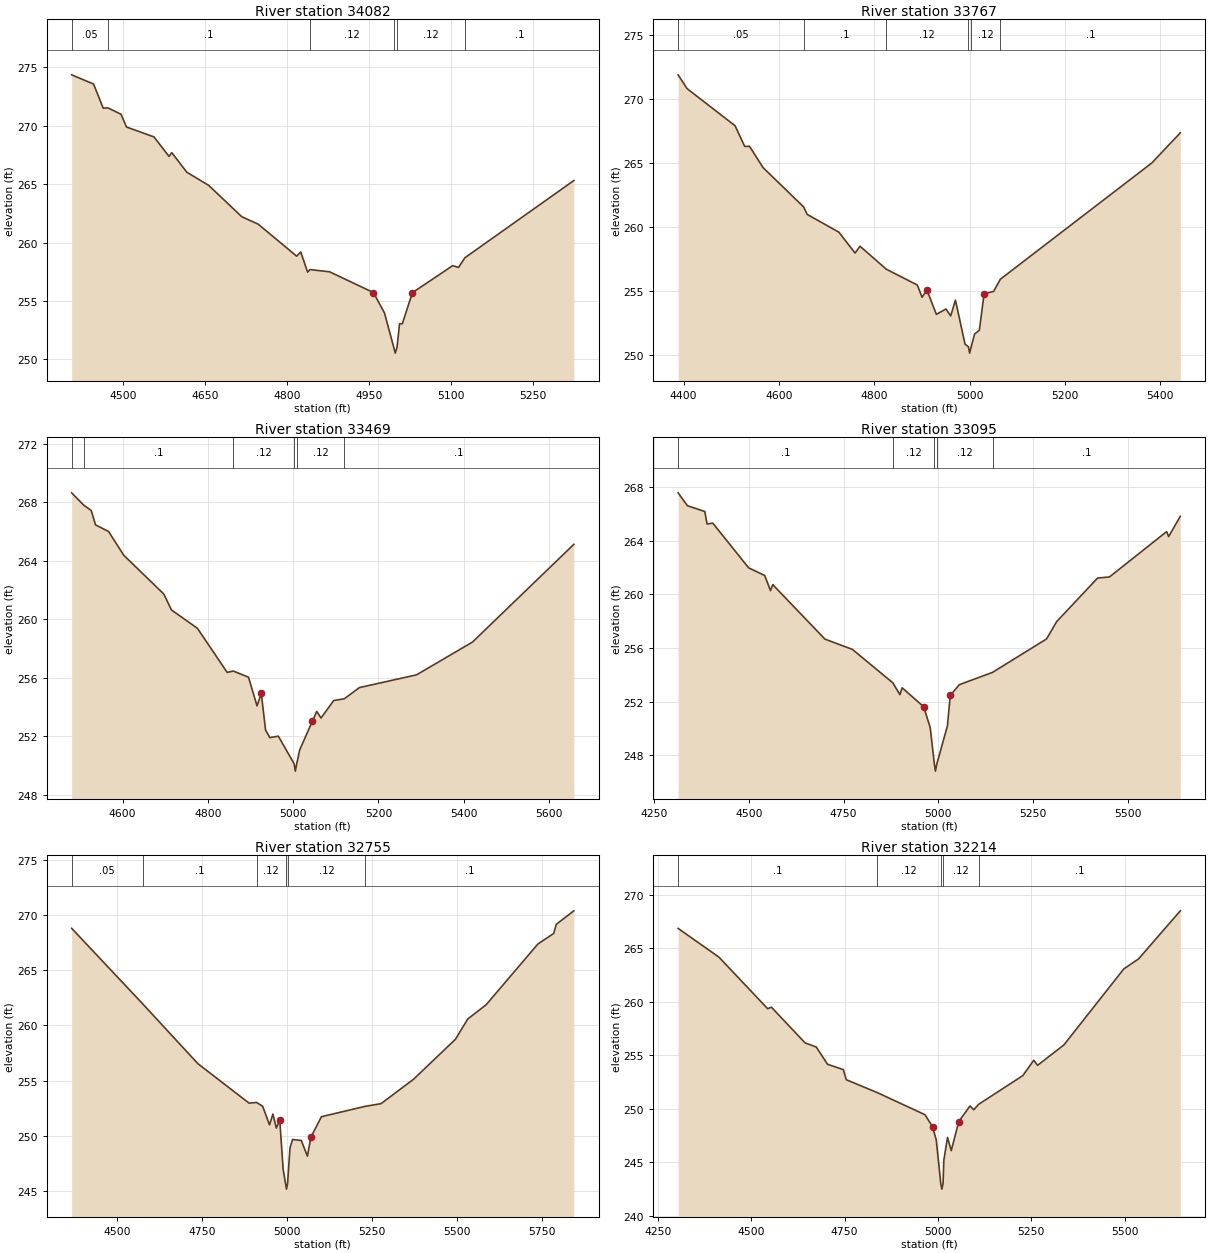
Type RM Length L Ch R = 1 ,34082   ,315,315,315
BEGIN DESCRIPTION:
UNT027 IN PECR 63.0
END DESCRIPTION:
XS GIS Cut Line= 3
      2278187.72     13200446.84      2278137.72     13199846.85
      2278037.72     13199546.84
#Sta/Elev= 30
  4406.5  274.37  4446.6  273.58  4464.2  271.51  4472.8  271.54  4496.8  270.99
  4506.8   269.9    4557  269.05  4584.6  267.38  4589.6   267.7  4617.2  266.02
  4657.3  264.89  4717.6  262.21  4747.7  261.57  4817.9  258.83  4825.4  259.19
    4838  257.46  4842.3  257.68  4878.1  257.49  4958.4  255.71  4978.5  253.97
  4995.5  251.02  4998.3  250.52  5001.5  251.02  5006.1  253.04  5011.2  253.04
  5029.6   255.7  5103.4  258.02    5114  257.86  5125.5  258.69  5324.8  265.31
#Mann= 6 ,-1 , 0
  4406.5     .05       0  4472.8      .1       0  4842.3     .12       0
  4995.5     .07       0  5001.5     .12       0  5125.5      .1       0
Bank Sta=4958.4,5029.6
XS Rating Curve= 0 ,0
Exp/Cntr=0.3,0.1

Type RM Length L Ch R = 1 ,33767   ,298,298,298
BEGIN DESCRIPTION:
Mapping XS 381c01b5
END DESCRIPTION:
XS GIS Cut Line= 4
      2278379.59     13200405.41      2278427.51     13200032.73
      2278443.48      13199686.7      2278310.39     13199383.25
#Sta/Elev= 30
  4388.5  271.87  4407.2   270.8    4508   267.9  4528.2  266.29  4538.3   266.3
  4566.7  264.64  4651.9  261.57  4659.3  260.99  4725.7  259.61  4759.7  257.98
  4770.1  258.51  4825.3  256.72  4890.3  255.49  4900.3  254.53  4910.3  255.11
  4930.3   253.2  4950.3  253.62  4960.3  253.08  4970.3  254.31  4990.4  250.88
  4997.4  250.68  5000.1  250.18  5003.4  250.68  5010.4  251.67  5020.4  251.96
  5030.4  254.81  5050.4  254.99  5064.5  255.94  5382.2     265    5442  267.35
#Mann= 6 ,-1 , 0
  4388.5     .05       0  4651.9      .1       0  4825.3     .12       0
  4997.4     .07       0  5003.4     .12       0  5064.5      .1       0
Bank Sta=4910.3,5030.4
XS Rating Curve= 0 ,0
Exp/Cntr=0.3,0.1

Type RM Length L Ch R = 1 ,33469   ,374,374,374
BEGIN DESCRIPTION:
UNT027 IN PECR 62.0
END DESCRIPTION:
XS GIS Cut Line= 4
       2278581.9     13200400.02      2278704.34     13200064.67
      2278720.31      13199686.7      2278487.06     13199310.33
#Sta/Elev= 30
  4480.3  268.64  4508.6   267.8  4526.3  267.43  4536.3  266.45  4566.8     266
  4602.7  264.37  4696.6  261.72  4714.3  260.64  4775.4  259.38  4845.1  256.37
  4859.5  256.46  4895.2  256.04  4915.2  254.08  4925.2  254.93  4935.2  252.43
  4945.2  251.91  4965.2  252.01  5002.3  250.12    5005  249.62  5008.3  250.12
  5015.3  251.07  5045.3  253.05  5055.3   253.7  5065.3  253.25  5095.3  254.45
  5119.7  254.56  5155.4  255.33  5289.4   256.2  5420.6  258.44  5658.4  265.12
#Mann= 6 ,-1 , 0
  4480.3     .05       0  4508.6      .1       0  4859.5     .12       0
  5002.3     .07       0  5008.3     .12       0  5119.7      .1       0
Bank Sta=4925.2,5045.3
XS Rating Curve= 0 ,0
Exp/Cntr=0.3,0.1

Type RM Length L Ch R = 1 ,33095   ,340,340,340
BEGIN DESCRIPTION:
UNT027 IN PECR 61.0
END DESCRIPTION:
XS GIS Cut Line= 4
      2278752.22     13200506.56      2278959.87     13200176.46
      2279156.84     13199601.52        2279263.     13199293.63
#Sta/Elev= 30
    4314  267.57  4338.5  266.61  4384.3  266.18  4390.3  265.25  4405.5  265.31
  4499.8  261.98  4542.2  261.41  4557.5  260.28  4563.4  260.73  4700.8  256.67
  4773.4   255.9  4879.9  253.41  4898.5  252.53  4904.4  253.04  4961.1  251.63
  4978.4  250.07  4989.4  247.33  4992.1  246.83  4995.4  247.33  5023.6  250.19
  5031.2  252.47  5054.9  253.27  5142.6  254.19  5284.9  256.68  5311.5  257.97
  5419.5  261.22  5450.7   261.3  5601.4  264.68  5606.7  264.31  5637.4  265.82
#Mann= 5 ,-1 , 0
    4314      .1       0  4879.9     .12       0  4989.4     .07       0
  4995.4     .12       0  5142.6      .1       0
Bank Sta=4961.1,5031.2
XS Rating Curve= 0 ,0
Exp/Cntr=0.3,0.1

Type RM Length L Ch R = 1 ,32755   ,541,541,541
BEGIN DESCRIPTION:
UNT027 IN PECR 60.0
END DESCRIPTION:
XS GIS Cut Line= 3
      2279287.72      13200696.9      2279337.72     13200046.85
      2279537.72     13199246.84
#Sta/Elev= 30
  4367.4  268.79  4576.2  261.96  4738.5  256.55    4889  252.98  4911.3  253.04
  4929.1  252.69  4949.2  251.01  4959.2  251.99  4969.2  250.72  4979.2  251.49
  4989.3     247  4996.3   245.7  4999.1   245.2  5002.3   245.7  5009.3  248.92
  5016.9  249.69  5042.6   249.6  5060.6  248.18  5070.9   249.9  5101.8  251.75
  5230.9  252.69  5277.1  252.93  5372.4  255.13  5496.1  258.76  5532.2  260.59
  5586.3  261.88  5738.3  267.37  5784.7  268.32  5792.4  269.15    5844  270.37
#Mann= 6 ,-1 , 0
  4367.4     .05       0  4576.2      .1       0  4911.3     .12       0
  4996.3     .07       0  5002.3     .12       0  5230.9      .1       0
Bank Sta=4979.2,5070.9
XS Rating Curve= 0 ,0
Exp/Cntr=0.3,0.1

Type RM Length L Ch R = 1 ,32214   ,386,386,386
BEGIN DESCRIPTION:
UNT027 IN PECR 59.0
END DESCRIPTION:
XS GIS Cut Line= 3
      2279854.22     13200666.18       2279827.6     13200224.37
      2279742.58      13199326.3
#Sta/Elev= 30
  4304.3  266.86  4413.8  264.17  4544.1  259.36  4554.1   259.5  4644.2  256.17
  4674.3  255.78  4704.4  254.17  4746.9  253.67  4754.5  252.73  4837.2  251.53
  4965.4  249.46  4985.5  248.34  4995.5  247.11  5007.7  243.01  5010.5  242.51
  5013.7  243.01  5015.8  245.21  5025.7  247.34  5035.7  246.11  5055.8  248.82
  5085.9  250.28    5096  249.92  5108.9  250.43  5227.3  253.11  5256.7  254.55
  5266.7  254.07  5337.1  255.97  5497.8  263.08  5537.2  264.01    5649   268.5
#Mann= 5 ,-1 , 0
  4304.3      .1       0  4837.2     .12       0  5007.7     .07       0
  5013.7     .12       0  5108.9      .1       0
Bank Sta=4985.5,5055.8
XS Rating Curve= 0 ,0
Exp/Cntr=0.3,0.1

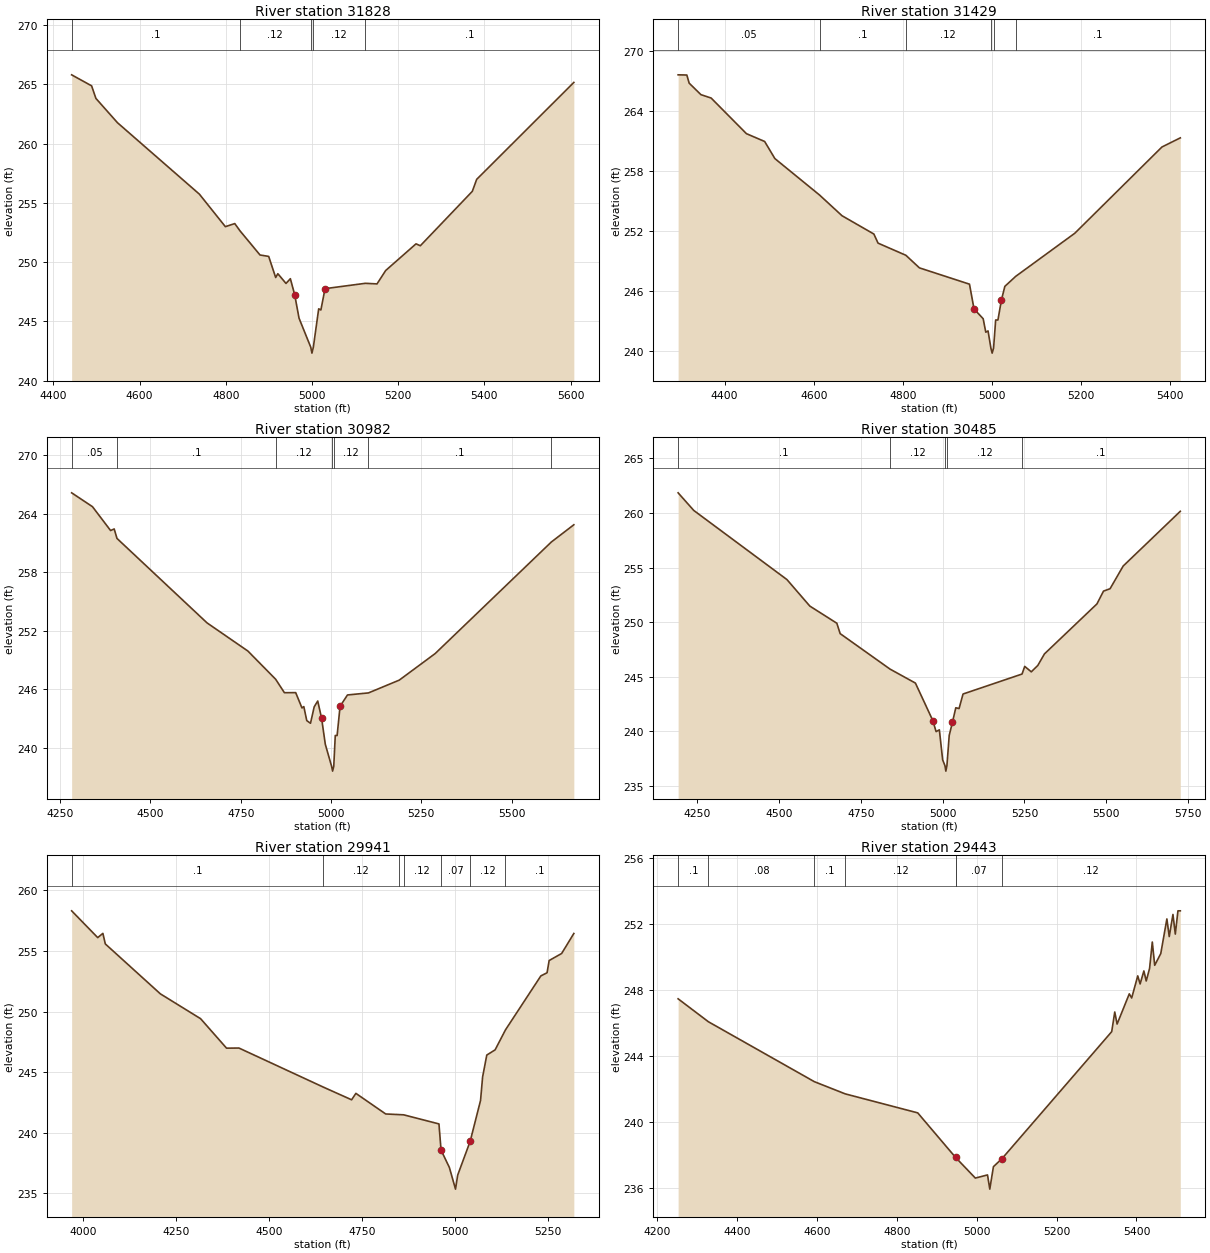
Type RM Length L Ch R = 1 ,31828   ,399,399,399
BEGIN DESCRIPTION:
UNT027 IN PECR 58.0
END DESCRIPTION:
XS GIS Cut Line= 3
      2280157.66     13200533.12      2280168.31     13200213.73
      2280083.13      13199372.6
#Sta/Elev= 30
  4442.5   265.8  4488.8  264.87  4498.8  263.81  4548.8  261.76  4738.9  255.73
  4799.1  252.99  4820.9  253.25    4833  252.64  4879.5   250.6  4899.6  250.48
  4915.8   248.7  4920.8  249.02  4939.8   248.2  4949.9   248.6  4959.9  247.25
    4970  245.27  4997.2  242.82  4999.9  242.32  5003.2  242.82  5015.6  246.06
  5020.7  245.96  5030.3  247.76  5123.9  248.21  5150.9  248.16    5171  249.29
  5241.4  251.54  5251.4  251.38    5372  255.97  5382.1  256.98  5607.5  265.16
#Mann= 5 ,-1 , 0
  4442.5      .1       0    4833     .12       0  4997.2     .07       0
  5003.2     .12       0  5123.9      .1       0
Bank Sta=4959.9,5030.3
XS Rating Curve= 0 ,0
Exp/Cntr=0.3,0.1

Type RM Length L Ch R = 1 ,31429   ,447,447,447
BEGIN DESCRIPTION:
UNT027 IN PECR 57.0
END DESCRIPTION:
XS GIS Cut Line= 3
      2280587.73      13200496.9      2280437.72     13199796.85
      2280337.73      13199396.9
#Sta/Elev= 30
  4295.4  267.63    4315  267.61  4320.2   266.8  4346.6  265.65  4369.6  265.31
  4448.9  261.75  4489.8  260.97  4512.8  259.26  4613.1  255.62  4663.6  253.55
  4735.2  251.72  4744.6  250.81    4807   249.6  4837.5  248.34    4950  246.71
  4960.2  244.23  4980.7  243.26  4986.6  241.91  4991.7  242.04  4998.1  240.32
  5000.9  239.82  5004.1  240.32  5008.8  243.13  5013.9  243.13  5021.6  245.09
  5029.4  246.49  5053.8  247.49  5186.6   251.8  5382.4  260.42  5423.6  261.33
#Mann= 6 ,-1 , 0
  4295.4     .05       0  4613.1      .1       0    4807     .12       0
  4998.1     .07       0  5004.1     .12       0  5053.8      .1       0
Bank Sta=4960.2,5021.6
XS Rating Curve= 0 ,0
Exp/Cntr=0.3,0.1

Type RM Length L Ch R = 1 ,30982   ,497,497,497
BEGIN DESCRIPTION:
UNT027 IN PECR 56.0
END DESCRIPTION:
XS GIS Cut Line= 4
      2280924.25     13200474.58      2280908.28     13199952.87
      2280801.81     13199473.75      2280556.92     13199186.27
#Sta/Elev= 30
  4281.9  266.14  4339.6  264.72  4389.7  262.28  4399.7  262.44  4407.4  261.47
  4656.8  252.82  4769.8  249.94  4846.7  247.05    4871  245.67  4902.2  245.68
  4919.6  244.11  4924.7  244.25  4932.9  242.81  4943.2  242.54  4953.4  244.22
  4963.2  244.82  4973.9  243.06  4984.2  240.39  5001.6  238.14  5004.4  237.64
  5007.6  238.14  5011.8  241.29  5016.9  241.29  5025.1  244.28  5045.6  245.44
  5103.7  245.65    5189  246.96  5288.4  249.68  5609.9   261.1  5672.3  262.87
#Mann= 7 ,-1 , 0
  4281.9     .05       0  4407.4      .1       0  4846.7     .12       0
  5001.6     .07       0  5007.6     .12       0  5103.7      .1       0
  5609.9     .05       0
Bank Sta=4973.9,5025.1
XS Rating Curve= 0 ,0
Exp/Cntr=0.3,0.1

Type RM Length L Ch R = 1 ,30485   ,544,544,544
BEGIN DESCRIPTION:
UNT027 IN PECR 55.0
END DESCRIPTION:
XS GIS Cut Line= 3
      2281209.66     13200493.74      2281327.73     13199847.86
      2281265.23     13198972.87
#Sta/Elev= 30
  4192.1  261.84  4239.8  260.23  4524.4   253.9  4594.4  251.47  4676.9   249.9
    4687  248.95  4839.4   245.7  4916.9  244.42    4970  240.99    4980  239.98
    4990  240.14  5000.1  237.39  5007.1  236.86  5009.8  236.36  5013.1  236.86
  5020.1  239.63  5030.1  240.85  5040.2  242.16  5050.2  242.09  5062.3  243.42
  5242.6  245.25  5250.7  245.95  5270.8  245.45  5290.8  246.04  5310.9  247.09
  5471.3  251.67  5491.3  252.84  5511.4  253.06  5551.5  255.14  5725.9  260.15
#Mann= 5 ,-1 , 0
  4192.1      .1       0  4839.4     .12       0  5007.1     .07       0
  5013.1     .12       0  5242.6      .1       0
Bank Sta=4970,5030.1
XS Rating Curve= 0 ,0
Exp/Cntr=0.3,0.1

Type RM Length L Ch R = 1 ,29941   ,498,498,498
BEGIN DESCRIPTION:
UNT027 IN PECR 54.0
END DESCRIPTION:
XS GIS Cut Line= 3
      2281848.57     13200375.67      2281671.48     13199469.39
      2281480.53     13199087.49
#Sta/Elev= 30
  3968.9  258.31    4039   256.1  4052.9  256.45  4059.4  255.58  4207.5  251.46
  4315.7  249.41  4385.4  246.98  4418.8  246.99  4644.7  243.78  4721.7  242.72
  4733.2  243.25  4813.4  241.55  4848.7   241.5  4861.7  241.48  4956.6  240.73
  4962.2  238.57  4984.6  237.14  5001.1  235.35    5007  236.51  5040.5  239.29
  5068.4  242.66    5074  244.61  5085.2  246.41  5107.6  246.84  5135.5  248.49
  5230.6  252.94  5247.3   253.2  5252.9  254.21  5286.5  254.79  5319.3  256.44
#Mann= 7 ,-1 , 0
  3968.9      .1       0  4644.7     .12       0  4848.7      .1       0
  4861.7     .12       0  4962.2     .07       0  5040.5     .12       0
  5135.5      .1       0
Bank Sta=4962.2,5040.5
XS Rating Curve= 0 ,0
Exp/Cntr=0.3,0.1

Type RM Length L Ch R = 1 ,29443   ,79,79,79
BEGIN DESCRIPTION:
UNT027 IN PECR 53.0
END DESCRIPTION:
XS GIS Cut Line= 3
      2282341.62     13200136.07      2282282.59      13199830.5
      2281775.66     13199031.92
#Sta/Elev= 30
  4252.7  247.45  4328.5  246.06  4593.7  242.43  4671.1  241.69  4852.5  240.54
  4947.3  237.84  4996.7  236.59  5027.2  236.78  5032.9  235.92    5042  237.28
  5063.6  237.77  5338.1  245.46  5345.7  246.65  5351.6  245.92  5382.1  247.75
  5388.1   247.5  5403.3  248.84  5409.2  248.35  5418.6  249.14  5424.5  248.53
  5432.9  249.29  5439.7  250.89  5445.7  249.48  5460.9  250.19  5476.2  252.29
  5482.1  251.22  5491.4  252.56  5497.3  251.37  5503.9  252.78  5509.8  252.78
#Mann= 7 ,-1 , 0
  4252.7      .1       0  4328.5     .08       0  4593.7      .1       0
  4671.1     .12       0  4947.3     .08       0  4947.3     .07       0
  5063.6     .12       0
Bank Sta=4947.3,5063.6
XS Rating Curve= 0 ,0
Exp/Cntr=0.3,0.1

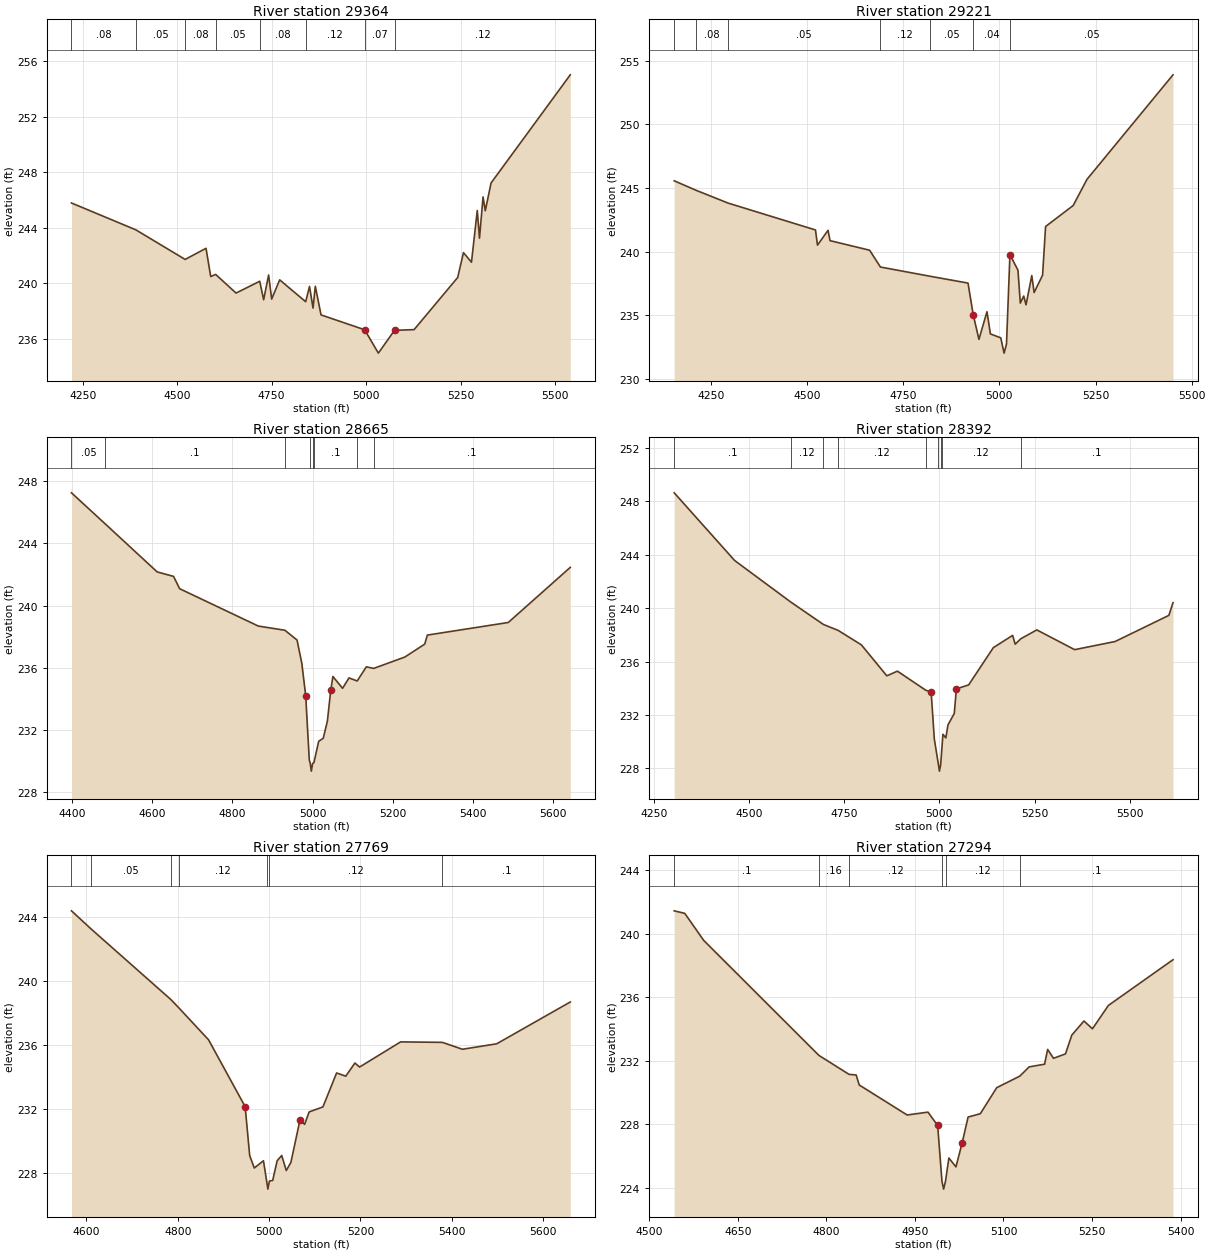
Type RM Length L Ch R = 1 ,29364   ,143,143,143
BEGIN DESCRIPTION:
UNT027 IN PECR 52.0
END DESCRIPTION:
XS GIS Cut Line= 3
      2282442.32     13200129.15      2282352.03     13199795.78
      2281832.75     13198971.85
#Sta/Elev= 30
  4220.5  245.79  4390.7  243.86  4521.1  241.73  4576.4  242.53  4588.8   240.5
  4601.9  240.65  4655.8  239.31  4718.4  240.16  4728.8  238.83  4741.9  240.61
    4750  238.88  4771.2  240.26    4840  238.69  4850.1  239.79  4859.4  238.23
  4865.4   239.8  4880.6  237.74    4996  236.67  5032.2  234.99  5074.9  236.63
  5126.7  236.68    5242  240.43  5257.3  242.22  5278.5  241.53  5293.8  245.25
  5299.7  243.26  5309.1  246.23    5315  245.23  5330.3  247.23  5539.8  255.01
#Mann= 8 ,-1 , 0
  4220.5     .08       0  4390.7     .05       0  4521.1     .08       0
  4601.9     .05       0  4718.4     .08       0    4840     .12       0
    4996     .07       0  5074.9     .12       0
Bank Sta=4996,5074.9
XS Rating Curve= 0 ,0
Exp/Cntr=0.3,0.1

Type RM Length L Ch R = 1 ,29221   ,556,556,556
BEGIN DESCRIPTION:
Mapping XS d0a25309
END DESCRIPTION:
XS GIS Cut Line= 4
      2282472.49     13200099.79      2282302.35     13199551.15
      2282215.54     13199398.38       2281906.5     13198946.96
#Sta/Elev= 30
  4154.3  245.57  4210.7  244.83  4294.5  243.82  4521.7  241.71    4527  240.52
  4554.3  241.68  4559.6  240.87  4662.5  240.12  4690.6   238.8  4818.8  238.08
  4918.4  237.54  4931.8  235.07  4946.8  233.12  4967.7  235.29  4976.6  233.55
  5003.6  233.24  5012.2  232.04  5018.5  232.76  5027.4  239.78  5048.3  238.55
  5054.4  235.97  5063.3  236.52  5069.3  235.83  5084.2  238.13  5090.3   236.8
  5112.3  238.16  5120.1  241.98  5191.9  243.63  5227.7  245.68  5451.5  253.89
#Mann= 7 ,-1 , 0
  4154.3     .05       0  4210.7     .08       0  4294.5     .05       0
  4690.6     .12       0  4818.8     .05       0  4931.8     .04       0
  5027.4     .05       0
Bank Sta=4931.8,5027.4
XS Rating Curve= 0 ,0
Exp/Cntr=0.3,0.1

Type RM Length L Ch R = 1 ,28665   ,273,273,273
BEGIN DESCRIPTION:
UNT027 IN PECR 51.0
END DESCRIPTION:
XS GIS Cut Line= 4
      2282805.82     13200058.11      2282687.76     13199596.29
      2282552.35     13199262.96      2282317.01     13198930.72
#Sta/Elev= 30
  4398.6  247.24  4482.9  245.24  4612.2  242.16  4653.1  241.87  4668.3  241.08
  4864.4  238.68  4930.8  238.41    4961  237.78  4972.8   236.3  4982.6  234.21
  4991.5  230.08  4993.9  229.86  4996.6  229.36  4999.9  229.86    5003   229.9
    5015  231.28  5026.3  231.47  5036.6  232.57    5045  234.55  5050.4  235.44
  5074.5  234.68  5090.5  235.35  5110.9  235.15  5133.7  236.06  5152.1  235.96
  5229.8  236.69  5279.3  237.52  5285.9   238.1  5487.6  238.91  5642.2  242.45
#Mann= 8 ,-1 , 0
  4398.6     .05       0  4482.9      .1       0  4930.8     .12       0
  4993.9     .07       0  4999.9     .12       0    5003      .1       0
  5110.9     .12       0  5152.1      .1       0
Bank Sta=4982.6,5045
XS Rating Curve= 0 ,0
Exp/Cntr=0.3,0.1

Type RM Length L Ch R = 1 ,28392   ,623,623,623
BEGIN DESCRIPTION:
UNT027 IN PECR 50.0
END DESCRIPTION:
XS GIS Cut Line= 4
      2283156.51     13199950.45      2282975.96     13199565.04
      2282784.99     13199196.99      2282438.22     13198881.43
#Sta/Elev= 30
    4304  248.64  4462.6  243.57  4610.3  240.45  4695.5  238.78  4734.5  238.33
  4795.2  237.25    4862  234.93  4889.8  235.28  4964.8  233.84  4978.3  233.73
  4986.7  230.19  4997.4  228.29  5000.1  227.79  5003.4  228.29  5006.4  229.46
  5009.2  230.55  5016.9  230.28  5022.5  231.25    5039  232.11  5044.6  233.95
  5076.8  234.25  5141.5  237.04  5192.2  237.96  5198.9   237.3  5213.8  237.71
  5255.7  238.37    5355  236.89  5461.1   237.5  5602.3  239.46  5613.1  240.41
#Mann= 9 ,-1 , 0
    4304      .1       0  4610.3     .12       0  4695.5      .1       0
  4734.5     .12       0  4964.8     .16       0  4997.4     .07       0
  5003.4     .16       0  5006.4     .12       0  5213.8      .1       0
Bank Sta=4978.3,5044.6
XS Rating Curve= 0 ,0
Exp/Cntr=0.3,0.1

Type RM Length L Ch R = 1 ,27769   ,475,475,475
BEGIN DESCRIPTION:
UNT027 IN PECR 49.0
END DESCRIPTION:
XS GIS Cut Line= 4
      2283583.57     13199037.26      2283347.49     13198992.13
      2282819.71     13198964.35      2282538.47     13198804.63
#Sta/Elev= 30
  4567.3  244.38  4609.8  243.26  4784.7  238.85  4802.2  238.33  4867.5  236.33
  4947.6  232.16  4957.6   229.1  4967.6  228.33  4987.7  228.78  4994.7  227.51
  4997.4  227.01  5000.7  227.51  5007.9  227.55  5017.7  228.78  5027.7  229.11
  5037.7  228.17  5047.8  228.68  5067.8  231.34  5077.8  231.05  5087.8  231.83
  5117.9  232.14  5147.9  234.26  5167.9  234.06    5188  234.88  5198.2  234.63
  5288.1   236.2  5379.5  236.17  5423.5  235.74  5498.5  236.08  5659.6  238.69
#Mann= 7 ,-1 , 0
  4567.3      .1       0  4609.8     .05       0  4784.7      .1       0
  4802.2     .12       0  4994.7     .07       0  5000.7     .12       0
  5379.5      .1       0
Bank Sta=4947.6,5067.8
XS Rating Curve= 0 ,0
Exp/Cntr=0.3,0.1

Type RM Length L Ch R = 1 ,27294   ,386,386,386
BEGIN DESCRIPTION:
UNT027 IN PECR 48.0
END DESCRIPTION:
XS GIS Cut Line= 3
      2283552.39     13198728.26       2283295.4     13198585.88
      2282761.71     13198447.25
#Sta/Elev= 30
  4542.1  241.43    4560  241.27    4592  239.57  4787.4  232.32  4838.3  231.13
  4850.4  231.09  4855.6  230.46  4936.8  228.57  4972.1  228.75  4988.5  227.91
  4995.8   224.4  4998.6   223.9  5001.8   224.4  5007.5  225.86  5019.5   225.3
  5029.8  226.78  5040.1  228.44  5060.8  228.65  5088.6  230.29  5127.8  231.02
  5143.5   231.6  5169.7  231.77  5174.9   232.7  5184.8  232.14  5205.1  232.42
  5215.8   233.6  5236.4  234.49  5250.8     234  5277.8  235.47  5387.3  238.35
#Mann= 6 ,-1 , 0
  4542.1      .1       0  4787.4     .16       0  4838.3     .12       0
  4995.8     .07       0  5001.8     .12       0  5127.8      .1       0
Bank Sta=4988.5,5029.8
XS Rating Curve= 0 ,0
Exp/Cntr=0.3,0.1

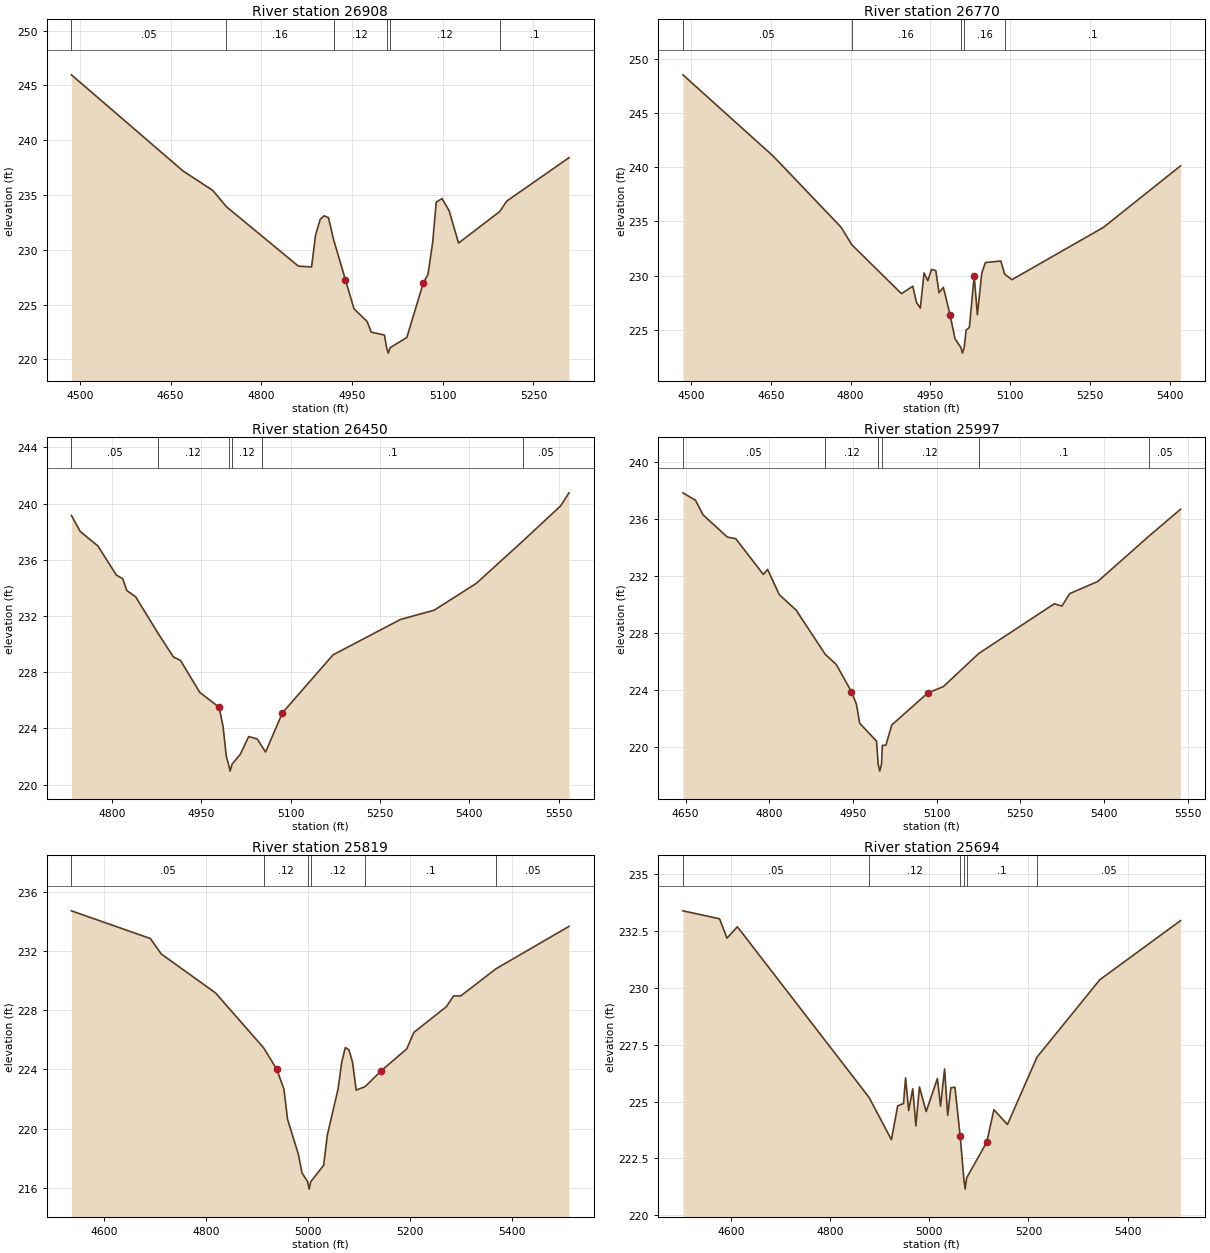
Type RM Length L Ch R = 1 ,26908   ,138,138,138
BEGIN DESCRIPTION:
UNT027 IN PECR 47.0
END DESCRIPTION:
XS GIS Cut Line= 3
      2283737.69     13198596.83      2283337.72     13198246.85
      2283087.73     13198096.86
#Sta/Elev= 30
  4485.9  245.97  4670.5   237.2  4719.8  235.42  4742.2  233.94  4861.2  228.52
  4883.1  228.44  4889.7  231.34  4897.3  232.78  4903.9  233.11  4911.1  232.93
  4919.5  230.94  4939.1  227.28  4953.3  224.62  4975.1  223.46  4981.8  222.49
  5003.6  222.23  5007.2  221.08    5010  220.58  5013.2  221.08  5040.7  222.01
  5067.9  226.98  5075.7  227.77  5083.5  230.72  5089.3  234.36    5099  234.68
  5110.7  233.56  5126.2  230.62  5194.4   233.5  5205.9  234.45  5308.9  238.41
#Mann= 6 ,-1 , 0
  4485.9     .05       0  4742.2     .16       0  4919.5     .12       0
  5007.2     .07       0  5013.2     .12       0  5194.4      .1       0
Bank Sta=4939.1,5067.9
XS Rating Curve= 0 ,0
Exp/Cntr=0.3,0.1

Type RM Length L Ch R = 1 ,26770   ,320,320,320
BEGIN DESCRIPTION:
Mapping XS 4af06c68
END DESCRIPTION:
XS GIS Cut Line= 4
      2283826.68     13198568.54      2283496.79     13198231.71
      2283441.24     13198148.38       2283146.1     13197936.57
#Sta/Elev= 30
  4485.1   248.5  4655.3  240.98  4782.5  234.44    4802  232.86  4895.7  228.33
  4916.9  229.02  4923.9  227.52  4931.1     227  4938.1  230.24  4945.2  229.52
  4952.2  230.57  4960.2  230.45  4966.2  228.42  4974.4  228.91  4987.2  226.34
  4996.2  224.18  5007.5  223.35  5010.2  222.85  5013.5  223.35  5017.2  224.97
  5023.3  225.22  5032.3  229.97  5038.3  226.39  5046.5   230.2  5053.3   231.2
  5082.3  231.34  5089.6  230.12  5103.2  229.62  5275.1  234.44    5420  240.11
#Mann= 5 ,-1 , 0
  4485.1     .05       0    4802     .16       0  5007.5     .07       0
  5013.5     .16       0  5089.6      .1       0
Bank Sta=4987.2,5032.3
XS Rating Curve= 0 ,0
Exp/Cntr=0.3,0.1

Type RM Length L Ch R = 1 ,26450   ,453,453,453
BEGIN DESCRIPTION:
UNT027 IN PECR 46.0
END DESCRIPTION:
XS GIS Cut Line= 3
      2283837.71     13198296.84      2283737.72     13198046.85
      2283337.74     13197646.87
#Sta/Elev= 30
  4732.3  239.15  4747.1  238.01  4776.7  236.98  4807.7  234.91  4818.4  234.65
  4825.2  233.81    4840  233.37  4877.9  230.75  4903.3  229.09  4915.4  228.83
  4947.7  226.56    4980  225.51  4986.7  224.15  4992.1  222.03  4995.9  221.46
  4998.6  220.96  5001.9  221.46  5015.7  222.16  5029.8  223.42    5044  223.25
  5052.5  222.69  5058.1  222.32  5086.4  225.11  5171.2  229.23  5284.4  231.75
    5341  232.41  5411.7  234.32  5489.5  237.32  5553.1  239.83  5567.2  240.76
#Mann= 6 ,-1 , 0
  4732.3     .05       0  4877.9     .12       0  4995.9     .07       0
  5001.9     .12       0  5052.5      .1       0  5489.5     .05       0
Bank Sta=4980,5086.4
XS Rating Curve= 0 ,0
Exp/Cntr=0.3,0.1

Type RM Length L Ch R = 1 ,25997   ,178,178,178
BEGIN DESCRIPTION:
UNT027 IN PECR 45.0
END DESCRIPTION:
XS GIS Cut Line= 3
       2284237.7     13198046.82      2284037.72     13197746.85
      2283637.74     13197396.87
#Sta/Elev= 30
  4645.3  237.83  4667.8  237.31  4681.3  236.29  4724.9  234.73  4739.9  234.62
  4789.5  232.11    4797  232.47    4818   230.7  4848.1  229.62  4900.6  226.51
  4920.2  225.81  4947.2  223.91  4956.2  223.04  4962.2  221.69  4992.3  220.44
  4995.3  218.84  4998.1  218.34  5001.3  218.84  5002.8  220.15  5009.1  220.15
  5019.6  221.57  5084.1  223.81  5112.1  224.26  5175.9  226.59    5311  230.06
  5324.7   229.9  5338.5  230.77  5388.8  231.62  5481.1  234.81  5537.3  236.68
#Mann= 6 ,-1 , 0
  4645.3     .05       0  4900.6     .12       0  4995.3     .07       0
  5001.3     .12       0  5175.9      .1       0  5481.1     .05       0
Bank Sta=4947.2,5084.1
XS Rating Curve= 0 ,0
Exp/Cntr=0.3,0.1

Type RM Length L Ch R = 1 ,25819   ,125,125,125
BEGIN DESCRIPTION:
Mapping XS fab47697
END DESCRIPTION:
XS GIS Cut Line= 2
      2284497.86      13197955.5      2283806.91     13197268.02
#Sta/Elev= 30
  4536.4   234.7  4691.1  232.83  4712.3  231.79  4818.4  229.17  4912.8  225.46
  4938.6  224.01  4952.7  222.66  4959.8  220.63    4981  218.27  4988.1  217.01
  4999.2  216.42    5002  215.92  5005.2  216.42  5030.5  217.53  5037.6  219.55
  5058.8  222.69  5065.9  224.49  5072.9  225.47    5080  225.33  5087.1  224.48
  5094.2   222.6  5111.8  222.84  5143.6  223.92  5193.2  225.38  5207.3   226.5
  5270.9  228.23  5285.1  228.96  5299.2  228.96  5368.1  230.79  5511.1  233.65
#Mann= 6 ,-1 , 0
  4536.4     .05       0  4912.8     .12       0  4999.2     .07       0
  5005.2     .12       0  5111.8      .1       0  5368.1     .05       0
Bank Sta=4938.6,5143.6
XS Rating Curve= 0 ,0
Exp/Cntr=0.3,0.1

Type RM Length L Ch R = 1 ,25694   ,76,76,76
BEGIN DESCRIPTION:
UNT027 IN PECR 44.0
END DESCRIPTION:
XS GIS Cut Line= 3
      2284543.01     13197934.67        2284293.     13197566.61
       2283852.4     13197223.15
#Sta/Elev= 30
  4503.1  233.38  4576.9  233.03  4591.9  232.18  4612.9  232.68  4878.5  225.18
  4923.6  223.32  4936.2  224.81    4948  224.91  4952.1  226.04  4958.4   224.6
  4966.6  225.56  4972.9  223.93  4980.1  225.64  4993.7  224.56  5016.3  226.01
  5022.7   224.8  5030.8  226.43  5037.1  224.39  5043.5   225.6  5051.6  225.63
  5062.3  223.48  5069.4  221.65  5072.2  221.15  5075.4  221.65  5115.8  223.21
  5130.3  224.64  5157.6  223.99  5217.2  226.95  5343.8  230.35  5506.7  232.95
#Mann= 6 ,-1 , 0
  4503.1     .05       0  4878.5     .12       0  5062.3      .1       0
  5069.4     .07       0  5075.4      .1       0  5217.2     .05       0
Bank Sta=5062.3,5115.8
XS Rating Curve= 0 ,0
Exp/Cntr=0.3,0.1

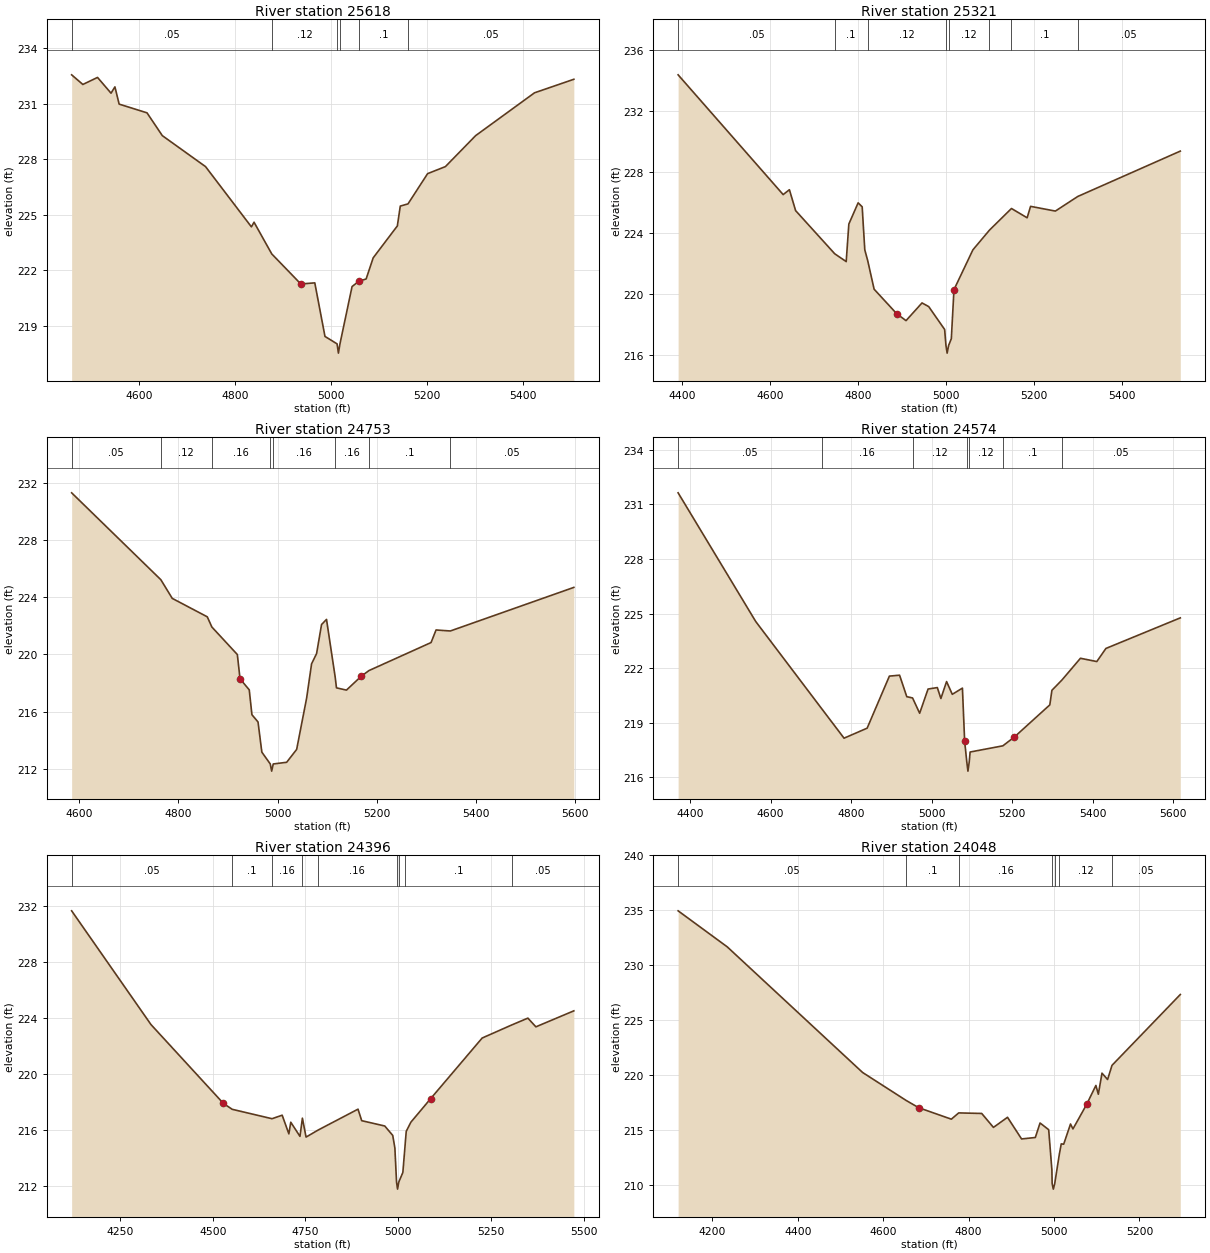
Type RM Length L Ch R = 1 ,25618   ,297,297,297
BEGIN DESCRIPTION:
Mapping XS 7f880980
END DESCRIPTION:
XS GIS Cut Line= 3
      2284577.73     13197927.73      2284386.75     13197538.83
      2283891.45     13197178.61
#Sta/Elev= 30
  4460.4  232.55  4483.7  232.03  4514.3  232.41  4542.4  231.56  4550.5   231.9
  4559.3  230.97  4617.3   230.5  4649.2  229.27  4739.2   227.6  4834.7  224.35
  4840.2   224.6  4877.1  222.89  4937.6  221.27  4966.7  221.33  4987.9  218.44
  5013.1  218.04  5015.9  217.54  5019.1  218.04  5044.3  221.13    5058  221.41
  5073.6  221.54  5088.3  222.68  5138.6   224.4  5144.7  225.47  5160.8  225.59
  5201.6  227.22  5238.7   227.6  5301.6  229.27  5424.2  231.58  5506.1  232.31
#Mann= 6 ,-1 , 0
  4460.4     .05       0  4877.1     .12       0  5013.1     .07       0
  5019.1     .12       0    5058      .1       0  5160.8     .05       0
Bank Sta=4937.6,5058
XS Rating Curve= 0 ,0
Exp/Cntr=0.3,0.1

Type RM Length L Ch R = 1 ,25321   ,568,568,568
BEGIN DESCRIPTION:
UNT027 IN PECR 43.0
END DESCRIPTION:
XS GIS Cut Line= 4
      2285002.93     13197668.68      2284759.54     13197440.04
        2284349.     13197174.54       2284032.3     13197147.54
#Sta/Elev= 30
  4391.6  234.39  4630.2  226.54  4644.4  226.86  4658.5  225.49  4747.4  222.66
  4773.4  222.15  4779.4  224.61  4800.5     226  4809.7  225.74  4815.6  222.92
  4822.1  222.23  4836.8  220.34  4888.2  218.73  4909.3  218.28  4945.6  219.44
  4960.8   219.2    4997   217.7    5000  216.65  5002.7  216.15    5006  216.65
  5012.2   217.1  5018.2  220.31  5061.2  222.92  5098.8  224.21  5148.8  225.63
  5184.4  225.02  5192.2  225.77  5248.5  225.46  5299.6  226.42  5532.3  229.39
#Mann= 8 ,-1 , 0
  4391.6     .05       0  4747.4      .1       0  4822.1     .12       0
    5000     .07       0    5006     .12       0  5098.8     .05       0
  5148.8      .1       0  5299.6     .05       0
Bank Sta=4888.2,5018.2
XS Rating Curve= 0 ,0
Exp/Cntr=0.3,0.1

Type RM Length L Ch R = 1 ,24753   ,179,179,179
BEGIN DESCRIPTION:
Mapping XS ff6e9015
END DESCRIPTION:
XS GIS Cut Line= 4
      2285132.21     13197353.25      2285059.29     13197071.99
      2285028.04      13196995.6      2284390.94       13197051.
#Sta/Elev= 30
  4584.8  231.31  4764.6  225.23  4787.7  223.92  4858.3  222.63  4867.5  221.92
  4918.9  219.99  4924.3  218.29  4942.9  217.52  4948.3  215.78  4960.6  215.27
  4968.3  213.16  4985.3  212.33  4988.1  211.83  4991.3  212.33  5018.4  212.45
  5038.5  213.35  5058.6  216.94  5068.6  219.34  5078.7  220.06  5088.7  222.09
  5098.7  222.45    5116  218.46  5118.8  217.66  5138.9   217.5    5169  218.48
  5184.4  218.87  5309.5  220.83  5319.6  221.71  5348.4  221.64  5597.4  224.69
#Mann= 8 ,-1 , 0
  4584.8     .05       0  4764.6     .12       0  4867.5     .16       0
  4985.3     .07       0  4991.3     .16       0    5116     .16       0
  5184.4      .1       0  5348.4     .05       0
Bank Sta=4924.3,5169
XS Rating Curve= 0 ,0
Exp/Cntr=0.3,0.1

Type RM Length L Ch R = 1 ,24574   ,178,178,178
BEGIN DESCRIPTION:
UNT027 IN PECR 42.0
END DESCRIPTION:
XS GIS Cut Line= 6
      2285239.86     13197308.13      2285066.24     13196835.88
      2285038.46     13196804.63      2284944.71      13196832.4
      2284903.04     13196877.54      2284378.73     13197012.96
#Sta/Elev= 30
  4370.1  231.63    4563  224.56  4726.6  219.78  4782.5  218.15  4839.9   218.7
  4895.2  221.56  4920.5  221.61  4938.4  220.43  4952.8  220.36  4970.4  219.52
  4991.3  220.85  5014.3  220.93  5023.2  220.33  5037.3  221.26  5051.5  220.56
  5076.7   220.9  5082.2  217.99  5087.6  216.84  5090.4  216.34  5093.6  216.84
  5095.8  217.39  5177.2  217.73  5206.1  218.22  5293.9  219.98  5299.1  220.78
  5323.8  221.34    5370  222.54  5410.7  222.36  5433.3  223.08  5618.2  224.76
#Mann= 7 ,-1 , 0
  4370.1     .05       0  4726.6     .16       0  4952.8     .12       0
  5087.6     .07       0  5093.6     .12       0  5177.2      .1       0
  5323.8     .05       0
Bank Sta=5082.2,5206.1
XS Rating Curve= 0 ,0
Exp/Cntr=0.3,0.1

Type RM Length L Ch R = 1 ,24396   ,348,348,348
BEGIN DESCRIPTION:
Mapping XS cff1edc0
END DESCRIPTION:
XS GIS Cut Line= 4
      2285281.52     13197294.22       2285083.6     13196710.88
      2284871.79     13196710.88      2284416.92     13196974.77
#Sta/Elev= 30
  4119.8  231.65  4333.7  223.54  4528.9  217.92  4552.6   217.5  4659.9  216.83
  4687.3  217.08  4705.3  215.75  4710.5  216.58  4735.3  215.57  4741.8  216.87
  4751.7  215.52  4784.1  216.02  4891.7  217.51  4901.7  216.69  4963.8  216.31
  4985.3  215.64  4991.1  214.74  4995.6  212.31  4998.3  211.81  5001.6  212.31
  5012.6     213  5018.7  214.96  5021.7  215.93  5034.2  216.58  5087.2  218.25
  5226.3  222.58  5305.8  223.51  5349.6     224  5371.2  223.38  5473.5  224.52
#Mann= 9 ,-1 , 0
  4119.8     .05       0  4552.6      .1       0  4659.9     .16       0
  4741.8      .1       0  4784.1     .16       0  4995.6     .07       0
  5001.6     .16       0  5018.7      .1       0  5305.8     .05       0
Bank Sta=4528.9,5087.2
XS Rating Curve= 0 ,0
Exp/Cntr=0.3,0.1

Type RM Length L Ch R = 1 ,24048   ,279,279,279
BEGIN DESCRIPTION:
UNT027 IN PECR 41.0
END DESCRIPTION:
XS GIS Cut Line= 3
      2285337.73      13197396.9      2285081.91      13196554.9
      2284937.72     13196296.85
#Sta/Elev= 30
    4120  234.94    4235  231.66  4551.9  220.22  4654.4  217.66  4683.4  217.01
  4759.6  215.97  4776.9  216.54  4830.7  216.49  4858.2  215.22  4891.1  216.14
    4924  214.17  4956.2   214.3  4967.3  215.62  4987.5  215.01    4995  211.34
  4995.6   210.1  4998.4   209.6  5001.6   210.1  5012.1   212.7  5016.9  213.72
  5022.6  213.69  5038.6  215.53  5044.3  215.08  5076.3  217.31    5098  219.04
  5103.7  218.24  5112.3  220.16  5125.4  219.58  5135.7  220.87  5295.6  227.32
#Mann= 7 ,-1 , 0
    4120     .05       0  4654.4      .1       0  4776.9     .16       0
  4995.6     .07       0  5001.6     .16       0  5012.1     .12       0
  5135.7     .05       0
Bank Sta=4683.4,5076.3
XS Rating Curve= 0 ,0
Exp/Cntr=0.3,0.1