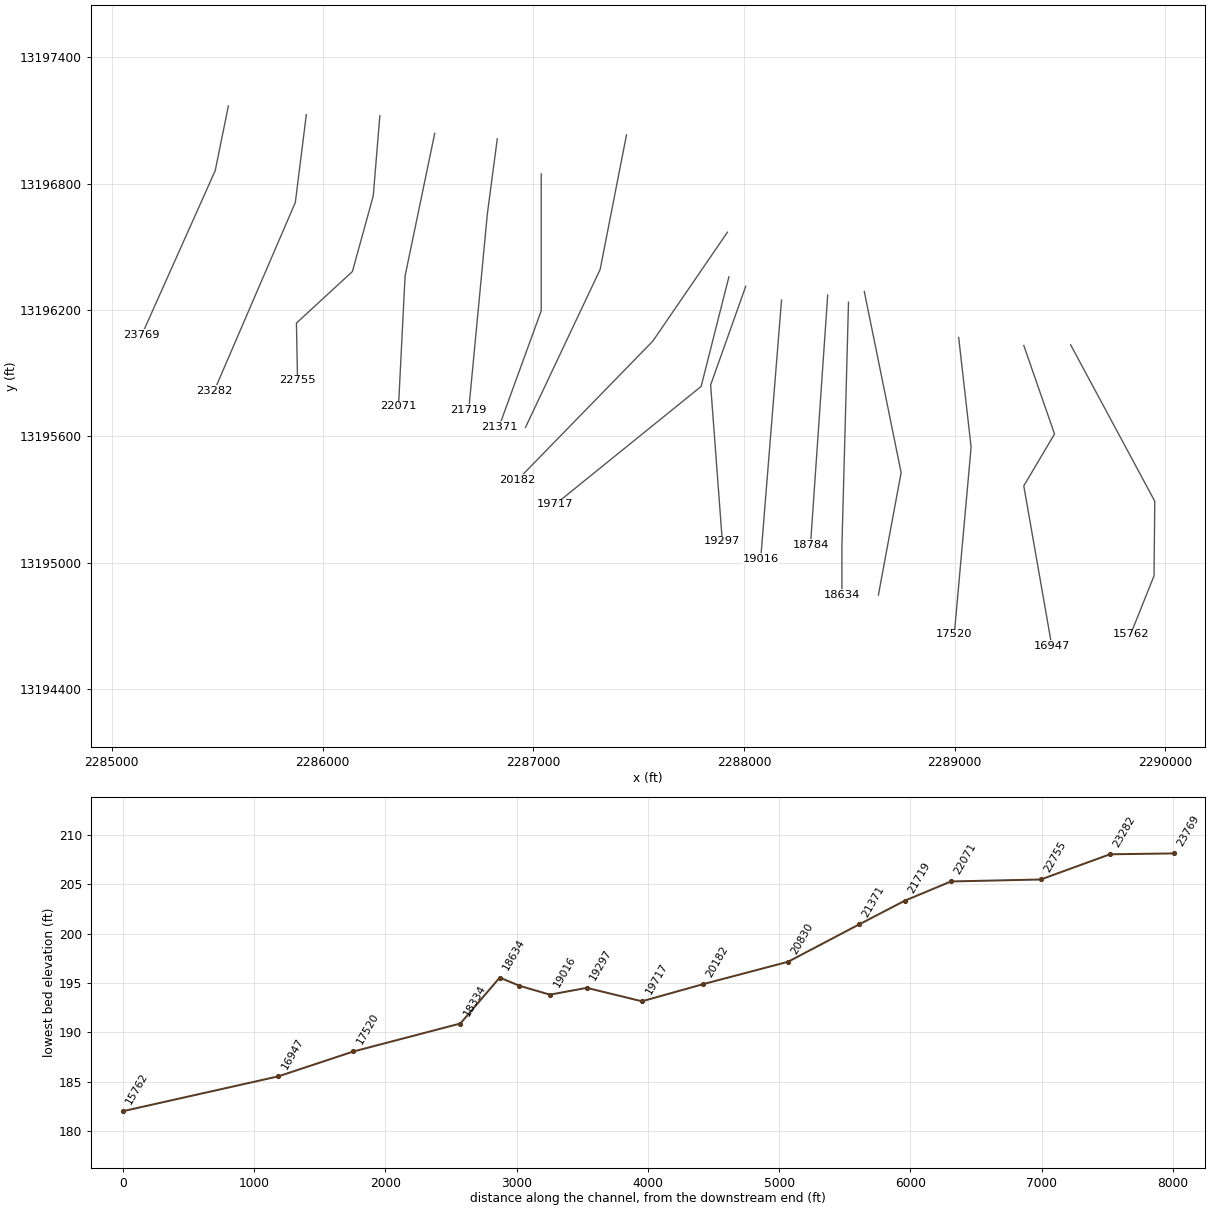
HEC-RAS study UNT027 IN PECR.prj: UNT027 IN PECR Base Level Engineering

--- UNT027 IN PECR.g01 (geometry) --- (continued)

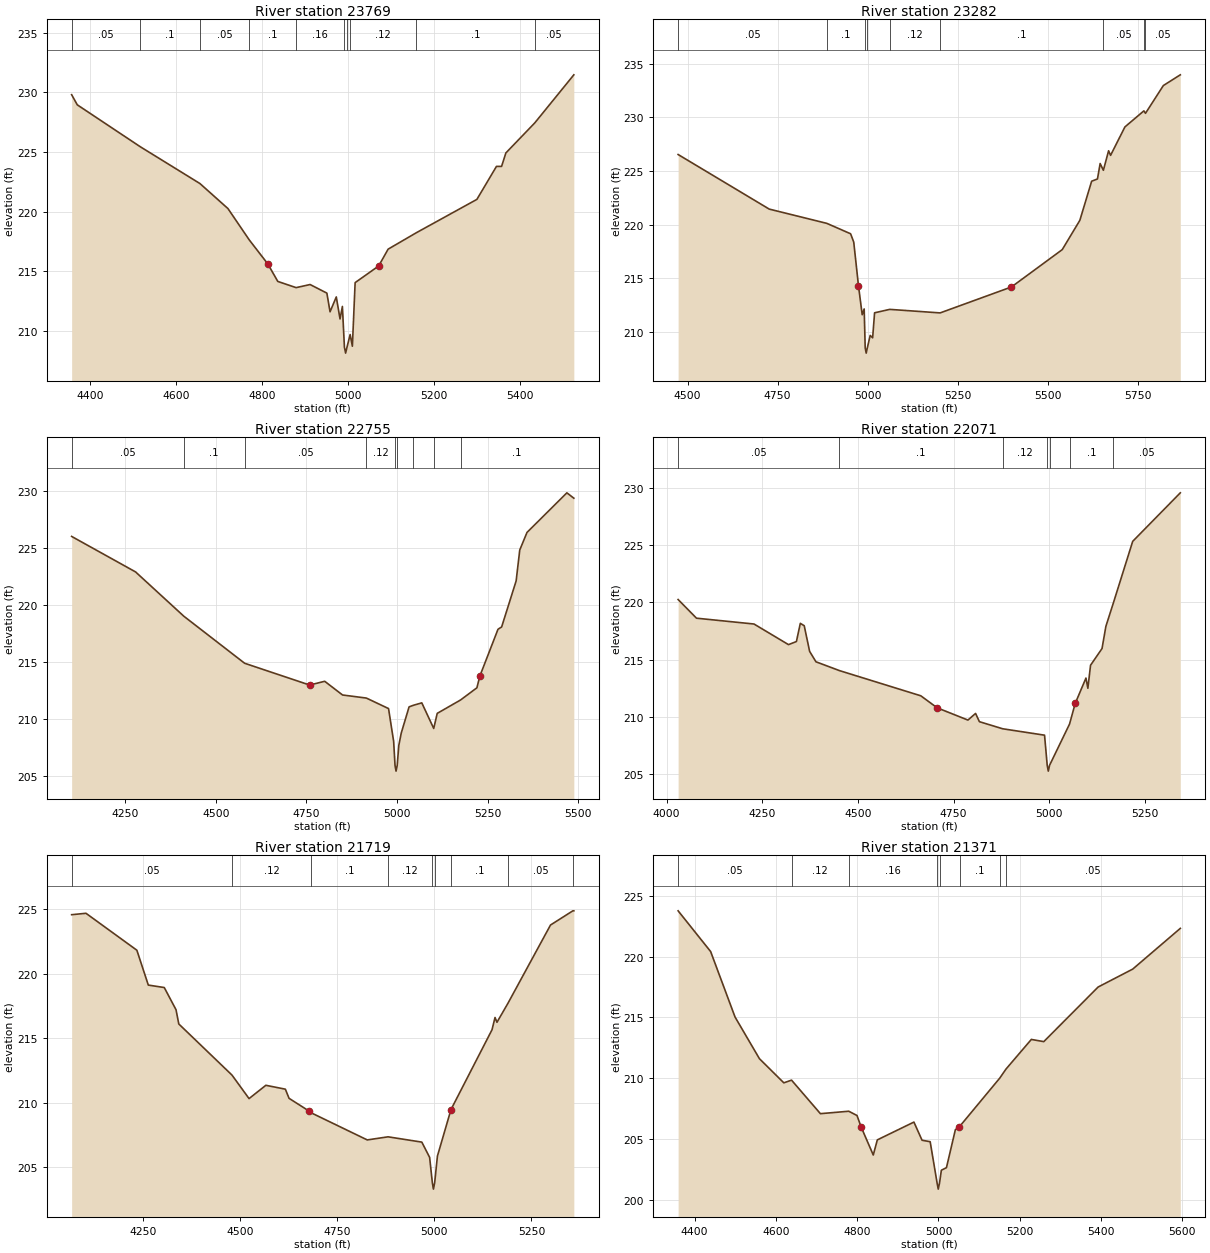
Type RM Length L Ch R = 1 ,23769   ,487,487,487
BEGIN DESCRIPTION:
UNT027 IN PECR 40.0
END DESCRIPTION:
XS GIS Cut Line= 3
      2285553.16     13197169.66      2285490.67      13196862.4
      2285142.36      13196082.6
#Sta/Elev= 30
  4356.7  229.81  4369.8  228.96  4516.3  225.44    4655  222.35  4720.1  220.25
  4769.6  217.62  4812.8   215.6    4836  214.13  4878.6  213.61  4911.1  213.87
  4950.1  213.15  4957.5  211.58    4972  212.83  4980.7  210.98  4986.2  212.03
  4990.9  208.61  4993.7  208.11  4996.9  208.61  5004.2  209.67  5009.4  208.69
  5015.8  214.03  5070.6  215.43  5092.5  216.84  5158.1  218.22  5298.9  221.02
  5344.4  223.79  5356.3  223.79  5366.3  224.92  5433.4  227.44  5524.3  231.48
#Mann= 10 ,-1 , 0
  4356.7     .05       0  4516.3      .1       0    4655     .05       0
  4769.6      .1       0  4878.6     .16       0  4990.9     .07       0
  4996.9     .16       0  5004.2     .12       0  5158.1      .1       0
  5433.4     .05       0
Bank Sta=4812.8,5070.6
XS Rating Curve= 0 ,0
Exp/Cntr=0.3,0.1

Type RM Length L Ch R = 1 ,23282   ,527,527,527
BEGIN DESCRIPTION:
UNT027 IN PECR 39.0
END DESCRIPTION:
XS GIS Cut Line= 3
      2285922.95     13197127.98      2285870.87     13196711.36
      2285485.46     13195815.52
#Sta/Elev= 30
  4473.7  226.54  4726.8  221.45  4886.8  220.12  4952.9  219.15  4961.6  218.37
  4974.7  214.32  4985.1   211.6  4990.6  212.14  4993.4  208.52  4996.2  208.02
  4999.4  208.52  5007.3  209.67  5014.1  209.45  5019.5  211.78  5061.6   212.1
  5201.6  211.77  5399.8  214.19  5540.8  217.67  5589.7   220.4  5622.5  224.05
  5638.7  224.26  5646.1   225.7  5655.1  225.07  5669.6  226.89  5675.1  226.46
  5714.9  229.11  5767.6  230.61  5772.1  230.38  5821.7  232.97  5868.8  233.97
#Mann= 9 ,-1 , 0
  4473.7     .05       0  4886.8      .1       0  4993.4     .07       0
  4999.4      .1       0  5061.6     .12       0  5201.6      .1       0
  5655.1     .05       0  5767.6      .1       0  5772.1     .05       0
Bank Sta=4974.7,5399.8
XS Rating Curve= 0 ,0
Exp/Cntr=0.3,0.1

Type RM Length L Ch R = 1 ,22755   ,684,684,684
BEGIN DESCRIPTION:
UNT027 IN PECR 38.0
END DESCRIPTION:
XS GIS Cut Line= 5
      2286271.91     13197122.79      2286240.67     13196742.61
      2286141.71     13196383.23      2285876.08     13196138.44
      2285881.29     13195867.63
#Sta/Elev= 30
    4102  226.03  4278.5  222.92  4411.7  219.04  4579.5  214.92  4759.1  213.01
  4800.6  213.34  4849.8  212.14  4915.6  211.87  4976.8  210.95  4990.9  208.07
  4994.7  205.97  4997.5  205.47  5000.7  205.97  5005.1  207.72  5011.9  208.81
  5033.5   211.1  5045.6  211.24  5068.6  211.45  5101.5  209.21  5111.2  210.53
  5175.5   211.7  5220.7  212.77    5229  213.81    5279   217.9    5289   218.1
    5329  222.13    5339  224.84    5359  226.38  5469.1  229.85  5488.3  229.38
#Mann= 9 ,-1 , 0
    4102     .05       0  4411.7      .1       0  4579.5     .05       0
  4915.6     .12       0  4994.7     .07       0  5000.7     .12       0
  5045.6     .16       0  5101.5     .12       0  5175.5      .1       0
Bank Sta=4759.1,5229
XS Rating Curve= 0 ,0
Exp/Cntr=0.3,0.1

Type RM Length L Ch R = 1 ,22071   ,352,352,352
BEGIN DESCRIPTION:
UNT027 IN PECR 37.0
END DESCRIPTION:
XS GIS Cut Line= 3
      2286532.33     13197039.48      2286391.71      13196362.4
      2286360.46     13195742.62
#Sta/Elev= 30
  4030.2  220.26  4078.2  218.63  4228.5  218.12  4318.6  216.32  4339.3  216.59
  4349.5  218.18  4359.7  217.97  4373.8  215.73  4390.4  214.82  4451.8  214.05
  4664.3  211.85    4707   210.8  4787.4  209.73  4807.4  210.31  4817.4  209.59
  4878.1  208.97  4987.6  208.41  4994.6  205.77  4997.4  205.27  5000.6  205.77
  5052.9  209.38  5067.7  211.18  5095.8   213.4  5100.8  212.51  5107.8  214.52
  5137.8  215.98  5147.8  217.91  5167.5  219.97  5217.9  225.34  5342.3  229.58
#Mann= 7 ,-1 , 0
  4030.2     .05       0  4451.8      .1       0  4878.1     .12       0
  4994.6     .07       0  5000.6     .12       0  5052.9      .1       0
  5167.5     .05       0
Bank Sta=4707,5067.7
XS Rating Curve= 0 ,0
Exp/Cntr=0.3,0.1

Type RM Length L Ch R = 1 ,21719   ,348,348,348
BEGIN DESCRIPTION:
UNT027 IN PECR 36.0
END DESCRIPTION:
XS GIS Cut Line= 3
       2286829.2     13197013.41      2286782.33     13196659.27
      2286693.79       13195727.
#Sta/Elev= 30
  4065.5  224.57  4102.4  224.68  4233.5  221.82    4263  219.12  4304.1  218.93
  4334.4  217.21  4341.5  216.11  4478.6  212.15  4522.5  210.33  4565.8  211.36
    4616  211.06  4625.6  210.35  4676.3  209.38  4681.8  209.24    4827  207.13
  4880.6  207.37  4967.6  206.96  4987.7  205.78  4994.7  203.82  4997.5  203.32
  5000.7  203.82  5007.8  205.88  5042.7  209.48  5148.4  215.66  5156.2  216.61
  5161.2  216.24  5189.8  217.73  5299.1  223.77  5356.7  224.87  5359.2  224.87
#Mann= 9 ,-1 , 0
  4065.5     .05       0  4478.6     .12       0  4681.8      .1       0
  4880.6     .12       0  4994.7     .07       0  5000.7     .12       0
  5042.7      .1       0  5189.8     .05       0  5356.7      .1       0
Bank Sta=4676.3,5042.7
XS Rating Curve= 0 ,0
Exp/Cntr=0.3,0.1

Type RM Length L Ch R = 1 ,21371   ,541,541,541
BEGIN DESCRIPTION:
UNT027 IN PECR 35.0
END DESCRIPTION:
XS GIS Cut Line= 3
      2287037.72     13196846.87      2287037.72     13196196.85
      2286837.74      13195646.9
#Sta/Elev= 30
  4359.7  223.75  4439.7  220.41  4499.7  215.04  4559.7  211.62  4619.7  209.64
  4638.7  209.86  4709.7  207.11  4779.4  207.31  4799.7  206.96  4809.7  206.03
  4839.7  203.72  4849.7  204.96  4939.7  206.42  4959.7  204.93  4979.7  204.81
  4996.7  201.42  4999.5  200.92  5002.7  201.42  5007.2  202.47  5019.7  202.68
  5041.6  205.79  5050.3  206.03  5051.9  206.05  5150.9  210.03  5166.2  210.77
  5228.5   213.2  5259.1  213.02  5392.8   217.5  5477.9  218.97  5594.9  222.31
#Mann= 8 ,-1 , 0
  4359.7     .05       0  4638.7     .12       0  4779.4     .16       0
  4996.7     .07       0  5002.7     .16       0  5051.9      .1       0
  5150.9     .12       0  5166.2     .05       0
Bank Sta=4809.7,5050.3
XS Rating Curve= 0 ,0
Exp/Cntr=0.3,0.1

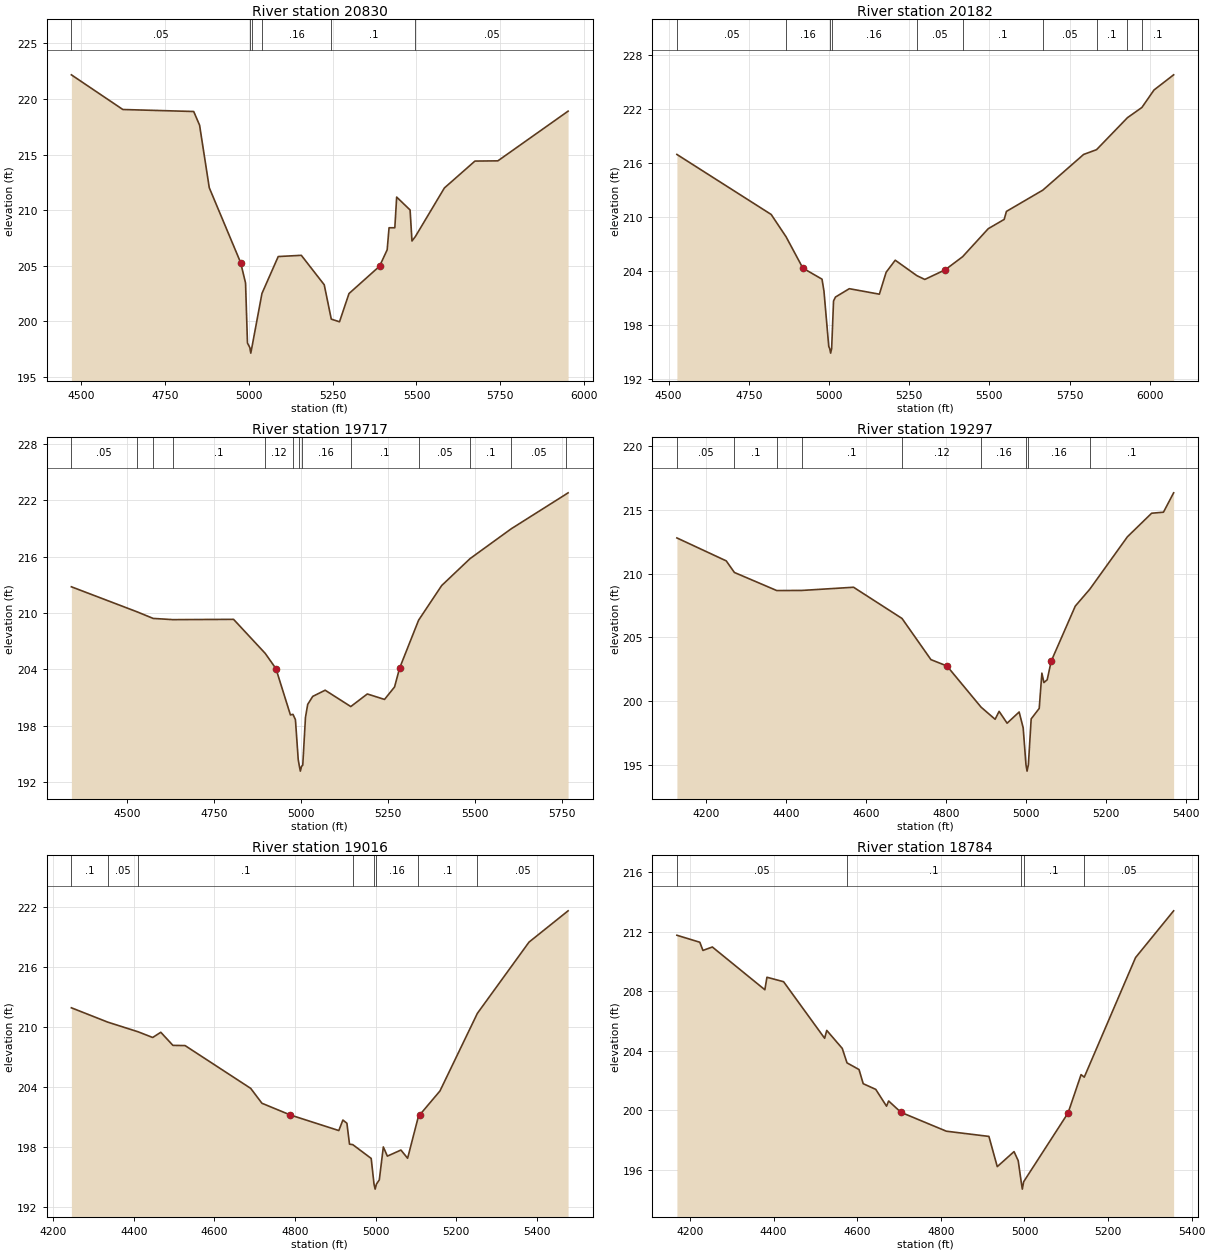
Type RM Length L Ch R = 1 ,20830   ,648,648,648
BEGIN DESCRIPTION:
UNT027 IN PECR 34.0
END DESCRIPTION:
XS GIS Cut Line= 3
       2287442.3     13197031.84      2287317.31       13196393.
      2286963.13     13195642.98
#Sta/Elev= 30
  4471.5  222.18  4624.9  219.06  4836.1  218.88  4853.6  217.65  4882.5  212.02
  4975.9  205.29  4990.6  203.45  4996.3  198.05  5003.4  197.64  5006.2  197.14
  5009.4  197.64  5039.5  202.51    5088  205.83  5156.8  205.94  5225.1  203.29
  5246.1   200.2  5270.6  199.96  5298.9   202.5    5390  204.96  5412.7  206.44
  5418.3  208.42  5435.5  208.42    5441  211.18    5481  210.02  5486.6  207.23
  5496.3  207.61  5583.2     212  5674.3  214.42  5742.6  214.44  5951.9  218.91
#Mann= 6 ,-1 , 0
  4471.5     .05       0  5003.4     .03       0  5009.4     .05       0
  5039.5     .16       0  5246.1      .1       0  5496.3     .05       0
Bank Sta=4975.9,5390
XS Rating Curve= 0 ,0
Exp/Cntr=0.3,0.1

Type RM Length L Ch R = 1 ,20182   ,465,465,465
BEGIN DESCRIPTION:
Mapping XS 5b463697
END DESCRIPTION:
XS GIS Cut Line= 3
      2287921.49     13196570.11      2287567.31     13196052.72
      2286924.95       13195393.
#Sta/Elev= 30
  4526.2  216.98    4820   210.3  4866.5  207.81  4918.7  204.33  4978.4   203.1
  4984.4  201.78  4999.4  195.61  5002.4  195.37  5005.2  194.87  5008.4  195.37
  5014.3  200.68  5020.3  201.11  5063.4  202.04  5157.1  201.43  5178.2  203.87
  5206.5  205.21    5274  203.49  5298.6  203.07  5362.1  204.14  5416.5   205.6
  5496.4  208.72    5546  209.75    5553  210.64  5666.5  213.01  5793.5  216.98
  5833.8  217.51  5930.1  221.07  5975.2  222.21  6012.8  224.15    6074  225.84
#Mann= 10 ,-1 , 0
  4526.2     .05       0  4866.5     .16       0  5002.4     .07       0
  5008.4     .16       0    5274     .05       0  5416.5      .1       0
  5666.5     .05       0  5833.8      .1       0  5930.1     .05       0
  5975.2      .1       0
Bank Sta=4918.7,5362.1
XS Rating Curve= 0 ,0
Exp/Cntr=0.3,0.1

Type RM Length L Ch R = 1 ,19717   ,420,420,420
BEGIN DESCRIPTION:
UNT027 IN PECR 33.0
END DESCRIPTION:
XS GIS Cut Line= 3
      2287928.42     13196358.29      2287796.48     13195837.45
       2287105.5     13195278.41
#Sta/Elev= 30
  4340.6  212.78  4529.3  210.11  4575.4  209.41    4632  209.28  4806.3  209.31
    4897  205.69  4927.8  204.07  4969.5  199.13  4976.8  199.19  4983.9  198.62
  4991.9  194.37  4995.3  193.64    4998  193.14  5001.3  193.64  5004.9  193.77
  5012.7  198.87  5019.1  200.25  5033.5   201.1  5069.2  201.76  5142.8  200.02
  5190.2  201.36  5239.7  200.78  5268.5  202.11  5282.9  204.11  5337.5  209.22
  5403.7  212.91  5485.2  215.78  5603.1  218.95  5760.1  222.63  5766.7  222.79
#Mann= 13 ,-1 , 0
  4340.6     .05       0  4529.3      .1       0  4575.4     .05       0
    4632      .1       0    4897     .12       0  4976.8     .16       0
  4995.3     .07       0  5001.3     .16       0  5142.8      .1       0
  5337.5     .05       0  5485.2      .1       0  5603.1     .05       0
  5760.1      .1       0
Bank Sta=4927.8,5282.9
XS Rating Curve= 0 ,0
Exp/Cntr=0.3,0.1

Type RM Length L Ch R = 1 ,19297   ,281,281,281
BEGIN DESCRIPTION:
UNT027 IN PECR 32.0
END DESCRIPTION:
XS GIS Cut Line= 3
      2288008.28     13196313.13      2287841.62     13195844.39
      2287897.15     13195101.55
#Sta/Elev= 30
    4127   212.8  4250.4     211  4270.8  210.09  4376.8  208.67  4439.7  208.68
  4568.8  208.93  4690.1  206.48  4762.4  203.25  4802.5  202.75  4887.8  199.52
  4922.9  198.57  4932.9  199.19  4952.9  198.26    4983  199.14  4993.1   197.9
  5000.1     195  5002.8   194.5  5006.1     195  5013.1   198.6  5033.2  199.42
  5039.9  202.19  5044.9  201.45  5053.2  201.67  5063.2  203.13  5123.4  207.45
  5159.8  208.78  5253.8  212.89  5314.4  214.74    5344  214.82  5369.4  216.34
#Mann= 9 ,-1 , 0
    4127     .05       0  4270.8      .1       0  4376.8     .05       0
  4439.7      .1       0  4690.1     .12       0  4887.8     .16       0
  5000.1     .07       0  5006.1     .16       0  5159.8      .1       0
Bank Sta=4802.5,5063.2
XS Rating Curve= 0 ,0
Exp/Cntr=0.3,0.1

Type RM Length L Ch R = 1 ,19016   ,232,232,232
BEGIN DESCRIPTION:
Mapping XS c2ba3827
END DESCRIPTION:
XS GIS Cut Line= 2
      2288178.17     13196247.85      2288079.33     13195020.22
#Sta/Elev= 30
  4245.5  211.95  4335.4  210.52  4410.9  209.55  4447.1  208.98  4467.2   209.5
  4497.3  208.19  4527.4  208.17  4690.1  203.89    4718   202.4  4788.2  201.23
  4908.6  199.67  4918.7  200.72  4928.7   200.4  4935.1  198.31  4943.2  198.26
  4988.9  196.88  4995.9  194.31  4998.7  193.81  5001.9  194.31    5009  194.74
    5019  198.03    5029  197.11  5062.6  197.72  5079.2   196.9  5104.6  200.87
  5109.3  201.24  5159.4  203.63  5252.1  211.39  5380.2  218.52  5477.1  221.65
#Mann= 8 ,-1 , 0
  4245.5      .1       0  4335.4     .05       0  4410.9      .1       0
  4943.2     .16       0  4995.9     .07       0  5001.9     .16       0
  5104.6      .1       0  5252.1     .05       0
Bank Sta=4788.2,5109.3
XS Rating Curve= 0 ,0
Exp/Cntr=0.3,0.1

Type RM Length L Ch R = 1 ,18784   ,150,150,150
BEGIN DESCRIPTION:
UNT027 IN PECR 31.0
END DESCRIPTION:
XS GIS Cut Line= 2
      2288397.17     13196271.48      2288315.65     13195085.98
#Sta/Elev= 30
  4168.6  211.76  4223.4  211.29  4230.9  210.74  4253.4  210.97    4379   208.1
    4384  208.94  4423.8  208.64    4522  204.84  4527.1  205.37  4564.2  204.16
  4575.5  203.19  4604.3  202.74  4614.3  201.79  4644.3  201.41  4670.1  200.28
  4675.1  200.63  4704.5  199.87  4813.2   198.6    4915  198.25    4935  196.22
  4975.1  197.23  4985.1  196.62  4992.2  195.21  4994.9  194.71  4998.2  195.21
  5104.3  199.82  5135.5   202.4  5143.1  202.23  5265.8  210.26  5356.9   213.4
#Mann= 5 ,-1 , 0
  4168.6     .05       0  4575.5      .1       0  4992.2     .07       0
  4998.2      .1       0  5143.1     .05       0
Bank Sta=4704.5,5104.3
XS Rating Curve= 0 ,0
Exp/Cntr=0.3,0.1

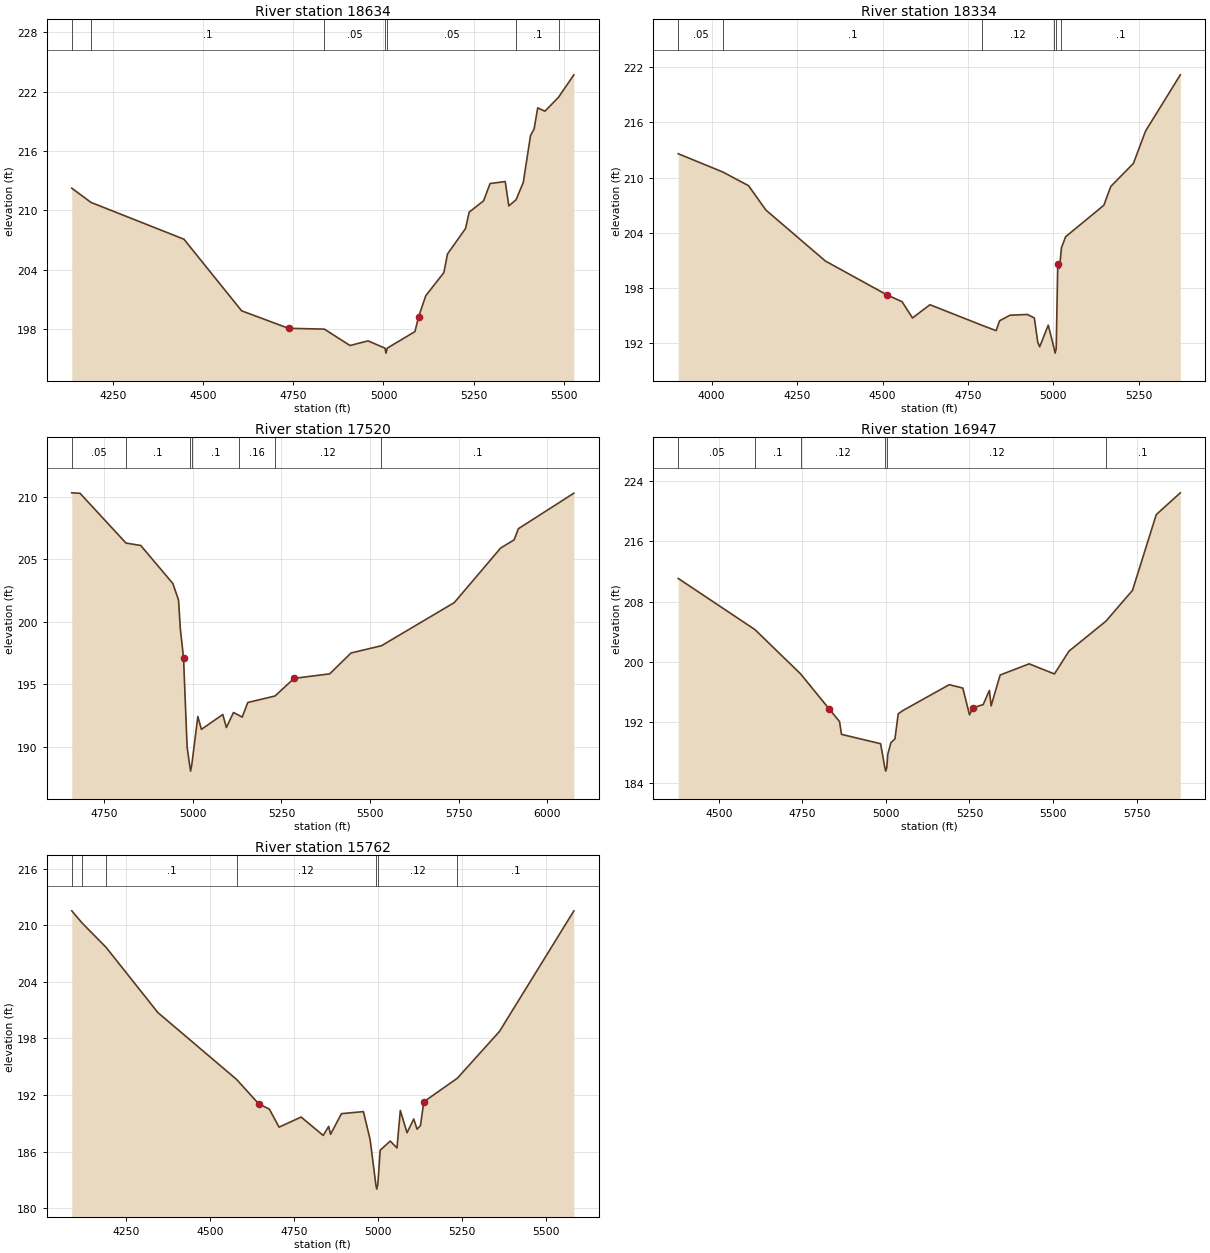
Type RM Length L Ch R = 1 ,18634   ,300,300,300
BEGIN DESCRIPTION:
Mapping XS cd6aacb3
END DESCRIPTION:
XS GIS Cut Line= 3
      2288495.88     13196237.43      2288464.62     13195075.94
      2288464.62     13194846.75
#Sta/Elev= 30
  4136.3  212.23  4189.6  210.79    4447  207.07    4607  199.82  4737.1  198.05
  4836.1  197.97  4907.2  196.31  4957.2  196.78  5004.2  196.04  5006.9  195.54
  5010.2  196.04  5087.2  197.72  5097.2  199.22  5117.2  201.35  5167.3  203.69
  5177.3  205.57  5227.3  208.15  5237.3   209.8  5277.3  210.95  5295.3   212.7
  5337.3   212.9  5347.3  210.44  5367.3  211.06  5387.3  212.81  5407.3  217.55
  5417.3  218.22  5427.3  220.36  5447.3  220.02    5485  221.43  5527.4   223.7
#Mann= 7 ,-1 , 0
  4136.3     .05       0  4189.6      .1       0  4836.1     .05       0
  5004.2     .04       0  5010.2     .05       0  5367.3      .1       0
    5485     .05       0
Bank Sta=4737.1,5097.2
XS Rating Curve= 0 ,0
Exp/Cntr=0.3,0.1

Type RM Length L Ch R = 1 ,18334   ,814,814,814
BEGIN DESCRIPTION:
UNT027 IN PECR 30.0
END DESCRIPTION:
XS GIS Cut Line= 3
      2288570.78     13196288.83      2288745.58     13195428.29
      2288637.71     13194846.82
#Sta/Elev= 30
  3902.1   212.6  4032.6  210.61  4107.9  209.12  4158.6  206.47  4332.7  200.92
    4513  197.23  4557.2  196.49  4587.8  194.72  4638.8  196.16  4791.9  193.91
  4832.5  193.34  4842.7  194.41  4873.2  195.02  4924.1   195.1  4944.4  194.72
  4954.6  192.04    4960  191.58  4985.1  193.94  5002.4  191.39  5005.2  190.89
  5008.4  191.39  5012.9  200.55  5017.9  200.11  5023.8  202.37  5035.9  203.56
  5147.8  206.99  5168.2  209.04  5234.4  211.55  5269.9  215.07  5371.6  221.19
#Mann= 6 ,-1 , 0
  3902.1     .05       0  4032.6      .1       0  4791.9     .12       0
  5002.4     .07       0  5008.4     .12       0  5023.8      .1       0
Bank Sta=4513,5012.9
XS Rating Curve= 0 ,0
Exp/Cntr=0.3,0.1

Type RM Length L Ch R = 1 ,17520   ,573,573,573
BEGIN DESCRIPTION:
UNT027 IN PECR 29.0
END DESCRIPTION:
XS GIS Cut Line= 3
       2289018.7     13196070.08      2289077.73     13195549.25
      2288997.93      13194661.1
#Sta/Elev= 30
  4658.7  210.32  4682.1  210.28  4811.7   206.3  4853.2  206.11  4943.7  203.07
  4959.8  201.75  4964.9  199.44  4973.9  197.12    4984  189.98  4991.1  188.56
  4993.8  188.06  4997.1  188.56  5014.2  192.43  5024.3   191.4  5084.6  192.59
  5094.7  191.55  5114.8  192.75  5131.6   192.5  5139.2  192.38  5155.1  193.55
  5231.9  194.07  5285.7  195.48  5386.1  195.84  5446.3  197.51  5532.1  198.09
  5737.5  201.54    5868   205.9  5906.2  206.56  5918.2  207.45  6074.6  210.29
#Mann= 7 ,-1 , 0
  4658.7     .05       0  4811.7      .1       0  4991.1     .07       0
  4997.1      .1       0  5131.6     .16       0  5231.9     .12       0
  5532.1      .1       0
Bank Sta=4973.9,5285.7
XS Rating Curve= 0 ,0
Exp/Cntr=0.3,0.1

Type RM Length L Ch R = 1 ,16947   ,1185,1185,1185
BEGIN DESCRIPTION:
UNT027 IN PECR 28.0
END DESCRIPTION:
XS GIS Cut Line= 4
      2289327.73     13196031.89      2289473.56     13195611.75
      2289327.73     13195365.22      2289460.46      13194605.9
#Sta/Elev= 30
  4378.8  211.06  4608.4  204.28  4745.1  198.41  4830.1  193.79  4861.4   192.1
  4867.2  190.41  4984.2  189.17  4996.8  186.04  4999.6  185.54  5002.8  186.04
  5005.6  187.76  5015.1  189.32  5027.1  189.81  5036.9  193.13    5050  193.54
  5189.5  196.99  5230.1  196.54  5250.2     193  5260.6  193.94    5291  194.35
  5309.7  196.23  5314.8  194.18  5341.8  198.27  5428.7  199.75  5504.2  198.41
  5547.7  201.43  5658.5  205.41  5737.7  209.48  5808.8  219.51  5880.8   222.4
#Mann= 6 ,-1 , 0
  4378.8     .05       0  4608.4      .1       0  4745.1     .12       0
  4996.8     .07       0  5002.8     .12       0  5658.5      .1       0
Bank Sta=4830.1,5260.6
XS Rating Curve= 0 ,0
Exp/Cntr=0.3,0.1

Type RM Length L Ch R = 1 ,15762   ,344,344,344
BEGIN DESCRIPTION:
UNT027 IN PECR 27.0
END DESCRIPTION:
XS GIS Cut Line= 4
      2289549.93      13196035.4      2289949.25     13195292.31
      2289945.78     13194938.14      2289834.95     13194661.07
#Sta/Elev= 30
  4087.3  211.55  4118.5  210.24  4189.7  207.67  4343.9  200.75  4578.6  193.65
    4645  191.04    4676  190.51  4705.1  188.59  4770.8  189.66  4836.6  187.71
  4852.8  188.67  4858.5  187.83    4891  190.02  4956.4  190.24  4976.4  187.27
  4993.4  182.51  4996.1  182.01  4999.4  182.51  5006.4  186.14  5036.4  187.11
  5056.4  186.38  5066.4  190.36  5086.4  187.99  5106.4  189.45  5116.4  188.37
  5126.4  188.76  5136.4  191.28  5236.6  193.79  5361.9  198.75  5583.5  211.54
#Mann= 7 ,-1 , 0
  4087.3      .1       0  4118.5     .05       0  4189.7      .1       0
  4578.6     .12       0  4993.4     .07       0  4999.4     .12       0
  5236.6      .1       0
Bank Sta=4645,5136.4
XS Rating Curve= 0 ,0
Exp/Cntr=0.3,0.1