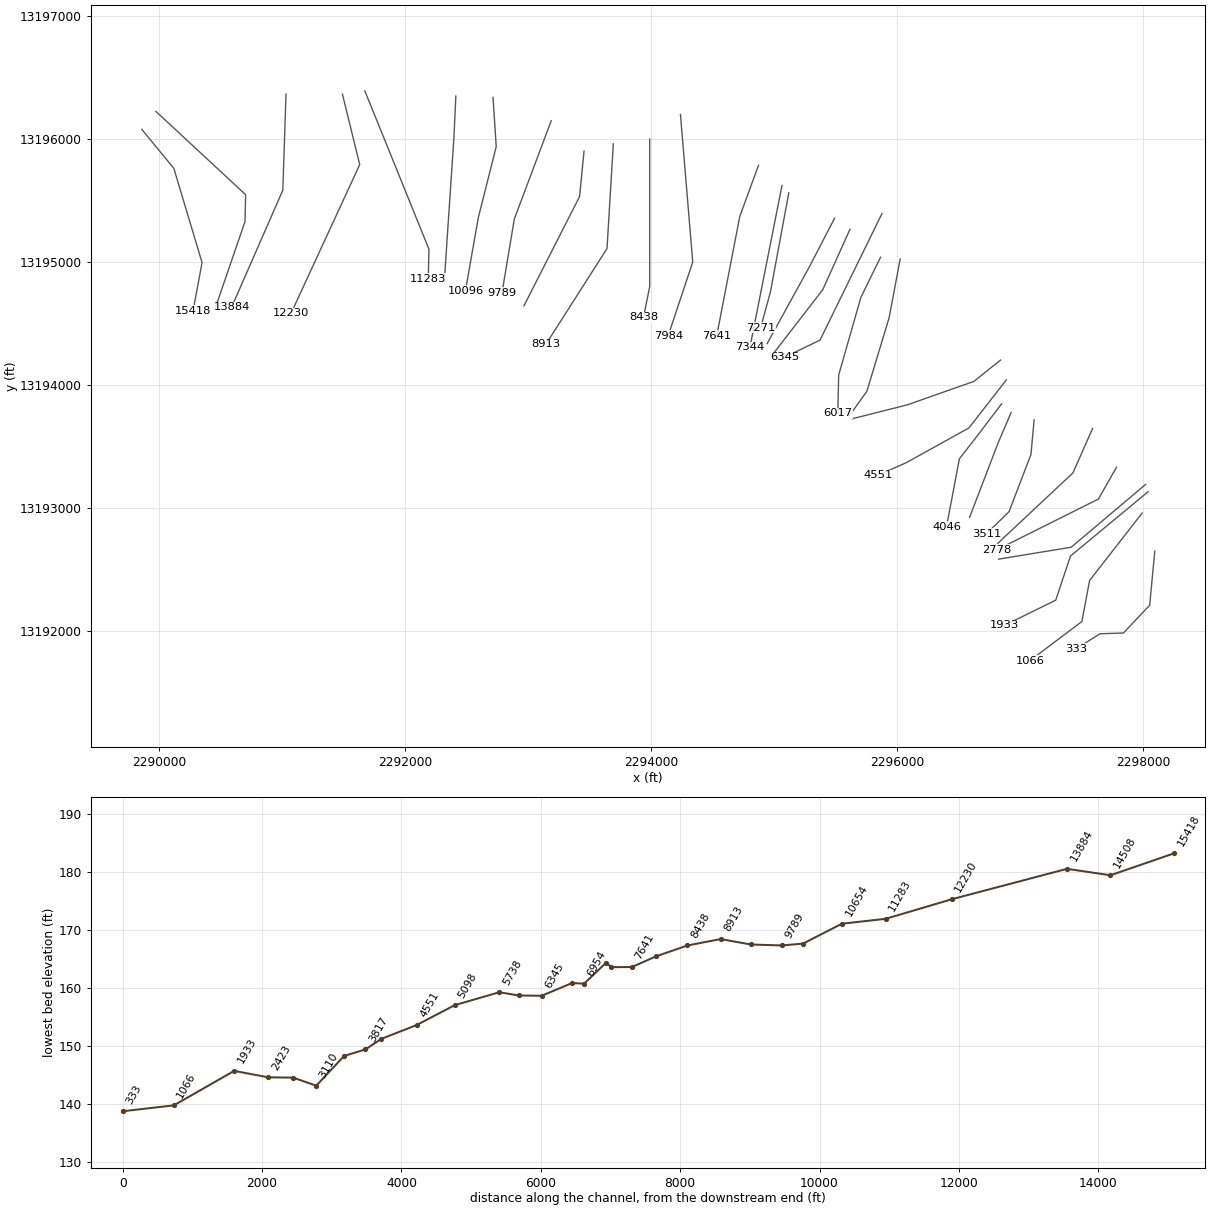
HEC-RAS study UNT027 IN PECR.prj: UNT027 IN PECR Base Level Engineering

--- UNT027 IN PECR.g01 (geometry) --- (continued)

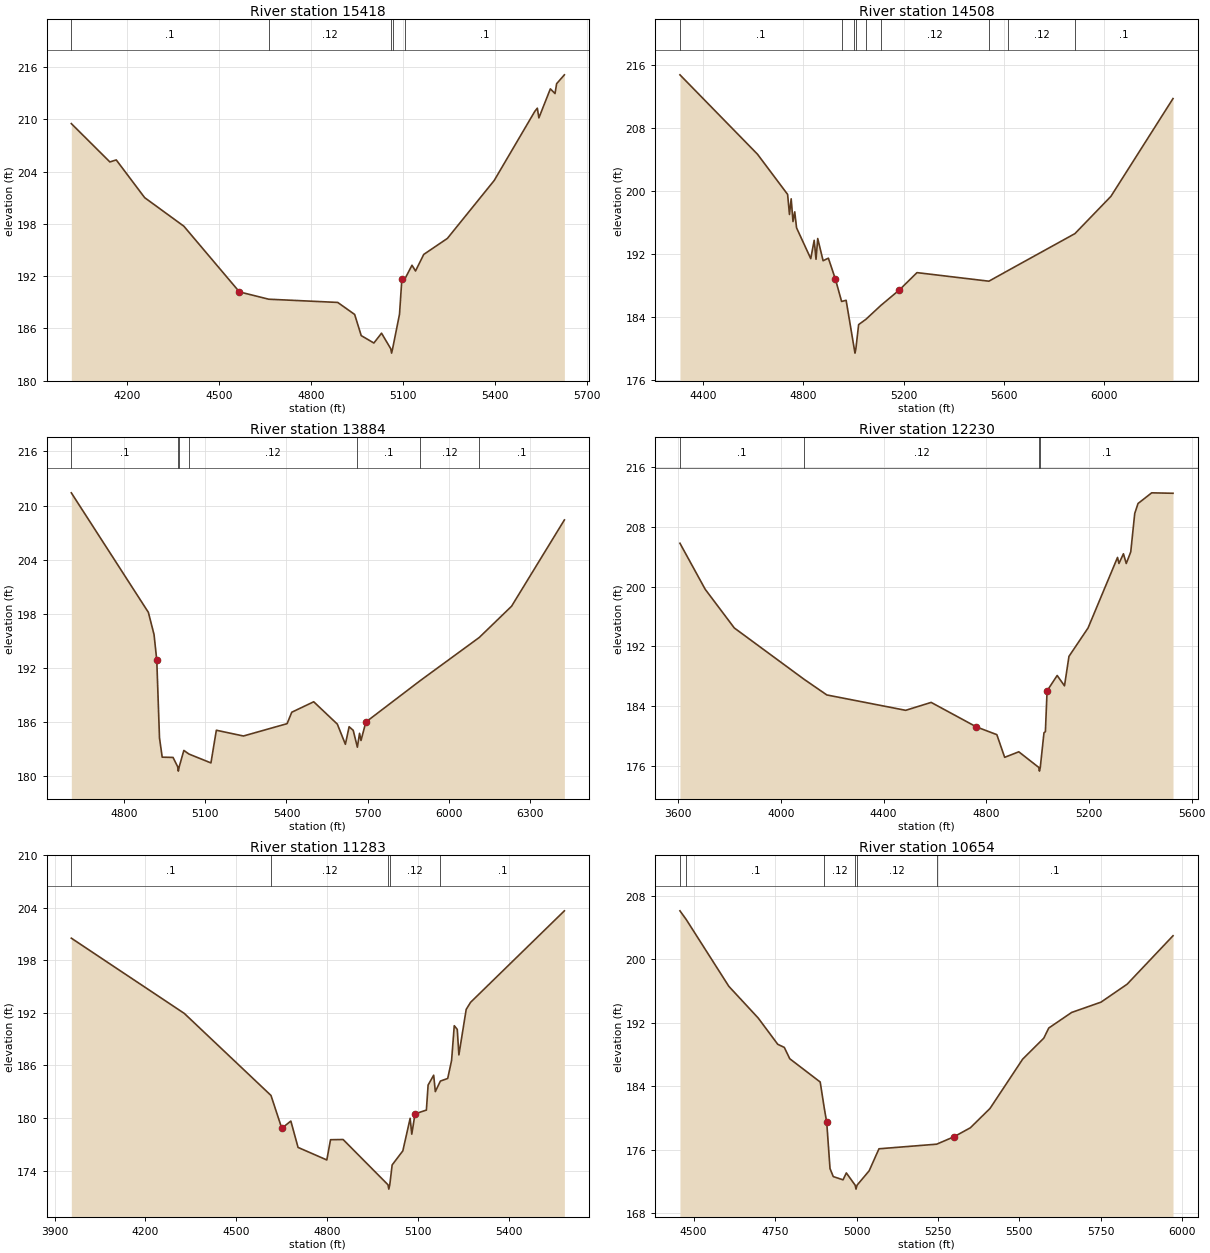
Type RM Length L Ch R = 1 ,15418   ,910,910,910
BEGIN DESCRIPTION:
UNT027 IN PECR 26.0
END DESCRIPTION:
XS GIS Cut Line= 4
      2289860.44     13196075.95      2290120.87     13195758.23
      2290350.04     13194992.61      2290277.12     13194601.96
#Sta/Elev= 30
  4017.7  209.52  4143.4  205.12  4164.2  205.35  4256.8  201.02  4384.6  197.74
  4565.7   190.2  4661.3  189.36  4886.2  188.99  4941.4  187.61  4962.8  185.18
  5004.1  184.33    5029  185.46  5059.1  183.67  5061.8  183.17  5065.1  183.67
  5087.6  187.63  5095.2  191.63  5104.4  191.64  5128.3  193.26  5139.8   192.6
  5166.6   194.5  5243.7  196.34  5396.3  202.99  5528.6  210.92  5536.9  211.29
    5542  210.18  5579.4  213.51  5594.6  212.97  5599.8   214.1  5625.1  215.12
#Mann= 5 ,-1 , 0
  4017.7      .1       0  4661.3     .12       0  5059.1     .07       0
  5065.1     .12       0  5104.4      .1       0
Bank Sta=4565.7,5095.2
XS Rating Curve= 0 ,0
Exp/Cntr=0.3,0.1

Type RM Length L Ch R = 1 ,14508   ,624,624,624
BEGIN DESCRIPTION:
UNT027 IN PECR 25.0
END DESCRIPTION:
XS GIS Cut Line= 4
      2289975.02     13196221.79      2290704.21     13195544.69
        2290699.     13195325.94      2290454.19     13194612.36
#Sta/Elev= 30
  4307.5   214.8  4617.1   204.7  4737.3  199.59  4744.7  197.04  4751.5  199.03
  4758.8  196.14  4765.7  197.37    4773  195.34  4829.7  191.42  4843.4  193.75
  4850.7  191.34  4857.5  193.98    4879  191.15    4900  191.48  4928.4  188.78
  4952.8  185.97  4970.9  186.12  5003.6   179.9  5006.3   179.4  5009.6   179.9
  5020.8  183.03  5049.8   183.7  5109.6  185.47  5183.5  187.44  5253.8  189.64
  5540.8  188.55  5618.1  189.92  5884.2   194.6  6027.9  199.34  6275.8  211.78
#Mann= 9 ,-1 , 0
  4307.5      .1       0  4952.8     .12       0  5003.6     .07       0
  5009.6     .12       0  5049.8     .16       0  5109.6     .12       0
  5540.8      .1       0  5618.1     .12       0  5884.2      .1       0
Bank Sta=4928.4,5183.5
XS Rating Curve= 0 ,0
Exp/Cntr=0.3,0.1

Type RM Length L Ch R = 1 ,13884   ,1654,1654,1654
BEGIN DESCRIPTION:
UNT027 IN PECR 24.0
END DESCRIPTION:
XS GIS Cut Line= 3
      2291032.33     13196362.43      2291006.29     13195581.15
      2290589.64     13194628.06
#Sta/Elev= 30
    4605  211.41  4889.7  198.14  4910.7  195.67  4920.8  192.81  4930.8   184.2
  4940.8  182.06  4980.8  182.03  4997.8  181.01  5000.5  180.51  5003.8  181.01
  5020.8  182.81  5039.4  182.41  5120.9  181.42  5140.9  185.05  5240.9  184.41
  5402.3  185.78  5419.6  187.05  5500.7  188.21  5587.9  185.73  5617.7  183.49
  5631.5  185.44  5646.6  185.04    5662  183.17    5670  184.71  5675.4  183.91
  5693.4  185.96  5894.8  190.57  6112.4  195.35  6231.8  198.82  6426.9   208.4
#Mann= 7 ,-1 , 0
    4605      .1       0  4997.8     .07       0  5003.8      .1       0
  5039.4     .12       0    5662      .1       0  5894.8     .12       0
  6112.4      .1       0
Bank Sta=4920.8,5693.4
XS Rating Curve= 0 ,0
Exp/Cntr=0.3,0.1

Type RM Length L Ch R = 1 ,12230   ,947,947,947
BEGIN DESCRIPTION:
UNT027 IN PECR 23.0
END DESCRIPTION:
XS GIS Cut Line= 3
      2291490.66      13196362.4      2291631.29     13195789.48
      2291074.16      13194581.5
#Sta/Elev= 30
  3607.2   205.8  3705.6  199.63  3818.8  194.45    4091  187.56  4179.2  185.47
  4486.3  183.41  4585.5  184.47  4761.5  181.19  4841.3  180.15  4871.8  177.11
  4926.8  177.85  5004.5  175.76  5007.2  175.26  5010.5  175.76  5024.9  180.41
  5030.4  180.54    5037  186.02  5076.3  188.08  5104.8  186.69  5122.2  190.64
  5196.6  194.45  5311.3   203.9  5316.9  203.09  5334.3  204.39  5345.3  203.09
  5362.8  204.64  5378.3  209.79  5391.2  211.13  5444.4  212.56  5527.4   212.5
#Mann= 4 ,-1 , 0
  3607.2      .1       0    4091     .12       0  5004.5     .07       0
  5010.5      .1       0
Bank Sta=4761.5,5037
XS Rating Curve= 0 ,0
Exp/Cntr=0.3,0.1

Type RM Length L Ch R = 1 ,11283   ,629,629,629
BEGIN DESCRIPTION:
UNT027 IN PECR 22.0
END DESCRIPTION:
XS GIS Cut Line= 4
      2291672.95     13196388.45      2291829.21     13196003.02
      2292193.79     13195101.98      2292188.58     13194862.44
#Sta/Elev= 30
  3955.5  200.53  4328.5  191.94  4614.6  182.58  4650.2  178.83  4680.1  179.66
  4703.9  176.65  4798.8  175.22  4811.1  177.53  4852.7  177.55  5000.7  172.39
  5003.5  171.89  5006.7  172.39  5014.5  174.65  5049.8  176.26  5073.9  179.97
  5079.3  178.16    5090  180.48  5127.5  180.91  5133.2  183.77  5151.6  184.89
    5157  183.02  5173.7  184.22  5197.9  184.52  5210.7  186.58  5219.5  190.54
  5229.4  190.12  5234.8  187.21  5258.9   192.4  5273.4  193.21    5583  203.65
#Mann= 5 ,-1 , 0
  3955.5      .1       0  4614.6     .12       0  5000.7     .07       0
  5006.7     .12       0  5173.7      .1       0
Bank Sta=4650.2,5090
XS Rating Curve= 0 ,0
Exp/Cntr=0.3,0.1

Type RM Length L Ch R = 1 ,10654   ,558,558,558
BEGIN DESCRIPTION:
UNT027 IN PECR 21.0
END DESCRIPTION:
XS GIS Cut Line= 4
      2292412.54     13196346.77      2292396.92     13196008.23
      2292344.83     13195232.19      2292318.79     13194836.34
#Sta/Elev= 30
    4458  206.09  4477.2     205  4608.1  196.58  4698.2  192.59  4758.2  189.28
  4778.3  188.89  4795.1  187.46  4888.5  184.53  4901.4  181.14  4908.5  179.46
  4918.6  173.63  4928.6  172.62  4958.6  172.21  4968.7  173.08  4995.7  171.54
  4998.5  171.04  5001.7  171.54  5038.8  173.35  5068.9  176.12    5246   176.7
  5299.4  177.64  5349.5  178.77  5409.7   181.2  5509.9  187.41  5574.7  190.05
  5590.1  191.33  5660.2  193.29  5750.4  194.59  5830.6  196.85  5971.4  202.95
#Mann= 6 ,-1 , 0
    4458     .05       0  4477.2      .1       0  4901.4     .12       0
  4995.7     .07       0  5001.7     .12       0    5246      .1       0
Bank Sta=4908.5,5299.4
XS Rating Curve= 0 ,0
Exp/Cntr=0.3,0.1

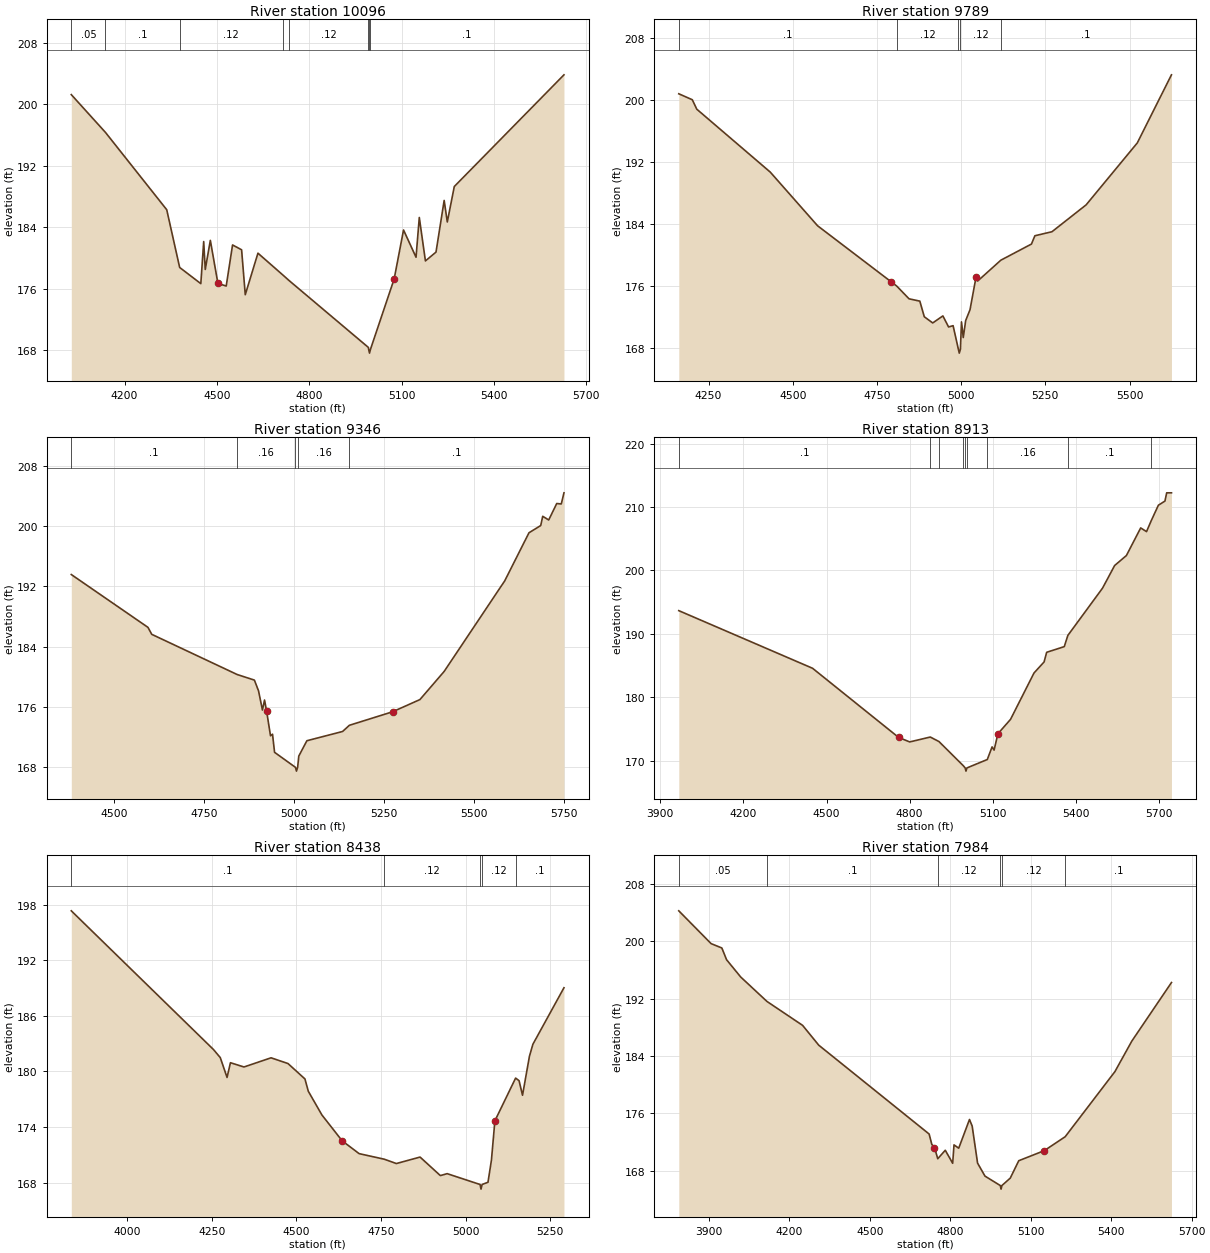
Type RM Length L Ch R = 1 ,10096   ,307,307,307
BEGIN DESCRIPTION:
UNT027 IN PECR 20.0
END DESCRIPTION:
XS GIS Cut Line= 4
      2292714.63     13196336.31      2292740.67     13195935.31
      2292594.83     13195357.19      2292490.66     13194763.43
#Sta/Elev= 30
  4026.8  201.28  4137.8  196.36  4336.9  186.29  4378.9  178.77  4447.7  176.66
    4457  182.14  4462.1  178.51  4478.6   182.3  4503.2  176.69  4530.2  176.35
  4550.8   181.7  4580.2  181.07  4592.1  175.22  4633.3  180.63  4713.6  177.81
  4734.6  177.06  4992.2  168.35    4993  168.11  4995.8  167.61    4999  168.11
    5076  177.28  5106.4  183.65    5147   180.1  5157.6  185.28  5177.5  179.62
  5211.9  180.77  5238.4   187.5  5248.6  184.69  5271.3  189.31  5627.7  203.86
#Mann= 8 ,-1 , 0
  4026.8     .05       0  4137.8      .1       0  4378.9     .12       0
  4713.6      .1       0  4734.6     .12       0  4992.2      .1       0
    4993     .07       0    4999      .1       0
Bank Sta=4503.2,5076
XS Rating Curve= 0 ,0
Exp/Cntr=0.3,0.1

Type RM Length L Ch R = 1 ,9789    ,443,443,443
BEGIN DESCRIPTION:
UNT027 IN PECR 19.0
END DESCRIPTION:
XS GIS Cut Line= 3
      2293187.73     13196146.88      2292887.72     13195346.85
      2292787.72     13194746.86
#Sta/Elev= 30
  4161.7  200.81  4201.8  200.04  4215.1  198.82  4433.2  190.69  4573.8  183.75
  4791.9  176.52  4808.9  175.95  4845.3  174.31  4877.3  174.01  4890.6  171.99
  4915.6  171.19  4945.8   172.1  4962.7  170.67  4976.1  170.84  4991.8  167.79
  4994.5  167.29  4997.8  167.79    5001  171.33  5006.3   169.3  5013.5  171.51
  5026.3  172.89    5044  177.07  5049.1  176.61  5117.8   179.3  5208.8  181.39
  5218.9  182.46  5269.6  182.98    5371  186.45    5523  194.46  5624.4  203.26
#Mann= 5 ,-1 , 0
  4161.7      .1       0  4808.9     .12       0  4991.8     .07       0
  4997.8     .12       0  5117.8      .1       0
Bank Sta=4791.9,5044
XS Rating Curve= 0 ,0
Exp/Cntr=0.3,0.1

Type RM Length L Ch R = 1 ,9346    ,433,433,433
BEGIN DESCRIPTION:
UNT027 IN PECR 18.0
END DESCRIPTION:
XS GIS Cut Line= 3
      2293454.21     13195898.86      2293417.75     13195529.06
      2292965.51     13194640.18
#Sta/Elev= 30
  4381.2  193.59  4594.2  186.57  4604.8  185.64  4842.1   180.3  4889.9  179.56
  4901.5  178.12  4912.3  175.58  4918.1  176.91  4923.7  175.49  4934.7  172.16
  4940.3  172.37    4946  169.96  5004.1  167.96  5006.8  167.46  5010.1  167.96
  5013.3  169.46  5035.8   171.5    5135  172.73  5153.8  173.55    5274  175.35
  5349.9  176.97  5417.2  180.71  5585.5  192.75  5652.9  199.14  5685.5   200.1
  5691.1  201.33  5707.7  200.84    5730  203.03  5742.6  202.97  5750.1  204.45
#Mann= 5 ,-1 , 0
  4381.2      .1       0  4842.1     .16       0  5004.1     .07       0
  5010.1     .16       0  5153.8      .1       0
Bank Sta=4923.7,5274
XS Rating Curve= 0 ,0
Exp/Cntr=0.3,0.1

Type RM Length L Ch R = 1 ,8913    ,475,475,475
BEGIN DESCRIPTION:
UNT027 IN PECR 17.0
END DESCRIPTION:
XS GIS Cut Line= 3
      2293692.31     13195958.98      2293641.05     13195106.85
      2293143.69     13194327.02
#Sta/Elev= 30
  3966.6  193.67  4449.6  184.59  4760.2   173.7  4800.2  172.99  4874.5  173.76
  4905.9  173.05    4994  169.23  5000.6  168.89  5003.4  168.39  5006.6  168.89
  5080.4  170.22  5097.6  172.21  5104.9   171.7  5118.7  174.28  5164.2  176.54
    5249  183.85  5285.4  185.59  5294.7  187.11  5358.2     188  5371.2  189.77
  5496.3  197.21  5540.1  200.78  5582.5  202.35  5634.1   206.7  5655.2  206.12
  5672.3  207.85    5698  210.28  5721.7  210.93    5728  212.23  5745.2  212.23
#Mann= 9 ,-1 , 0
  3966.6      .1       0  4874.5     .12       0  4905.9     .16       0
    4994     .12       0  5000.6     .07       0  5006.6     .12       0
  5080.4     .16       0  5371.2      .1       0  5672.3     .05       0
Bank Sta=4760.2,5118.7
XS Rating Curve= 0 ,0
Exp/Cntr=0.3,0.1

Type RM Length L Ch R = 1 ,8438    ,454,454,454
BEGIN DESCRIPTION:
UNT027 IN PECR 16.0
END DESCRIPTION:
XS GIS Cut Line= 3
      2293987.72      13195996.9      2293987.72     13194796.85
      2293937.72     13194546.85
#Sta/Elev= 30
  3835.5  197.32  4255.5  182.35  4275.5  181.48  4295.5  179.34  4305.5  180.93
  4345.5  180.47  4425.5  181.46  4475.5  180.84  4525.5  179.18  4535.5  177.85
  4575.5   175.3  4635.5   172.5  4685.5  171.12  4759.7  170.52  4795.5  170.05
  4865.5  170.75  4925.5  168.75  4945.5  168.96  5042.7  167.79  5045.5  167.29
  5048.7  167.79  5066.1  168.03  5076.3  170.42  5086.5  174.66  5147.7  179.27
  5157.9  178.99  5168.1  177.42  5188.5  181.62  5198.7  182.92  5290.5  189.02
#Mann= 5 ,-1 , 0
  3835.5      .1       0  4759.7     .12       0  5042.7     .07       0
  5048.7     .12       0  5147.7      .1       0
Bank Sta=4635.5,5086.5
XS Rating Curve= 0 ,0
Exp/Cntr=0.3,0.1

Type RM Length L Ch R = 1 ,7984    ,343,343,343
BEGIN DESCRIPTION:
UNT027 IN PECR 15.0
END DESCRIPTION:
XS GIS Cut Line= 3
      2294237.72     13196196.81      2294337.72     13194996.85
      2294137.71     13194396.82
#Sta/Elev= 30
  3788.1  204.28  3908.5   199.7  3948.6  199.09  3966.2  197.45  4018.8  195.04
  4116.8  191.62  4249.6  188.28  4309.9  185.51  4721.3   173.1  4731.3  171.65
  4741.3  171.21  4753.5  169.65  4781.5  170.83  4809.1  169.01  4814.1  171.58
  4831.7  171.12  4871.8  175.13  4881.8  174.21  4901.9  169.04  4929.5  167.22
  4986.7   165.9  4989.5   165.4  4992.7   165.9  5023.8  166.94  5055.5  169.37
  5150.3  170.77  5228.5  172.72  5413.8  181.81  5477.1  186.09  5624.7  194.26
#Mann= 6 ,-1 , 0
  3788.1     .05       0  4116.8      .1       0  4753.5     .12       0
  4986.7     .07       0  4992.7     .12       0  5228.5      .1       0
Bank Sta=4741.3,5150.3
XS Rating Curve= 0 ,0
Exp/Cntr=0.3,0.1

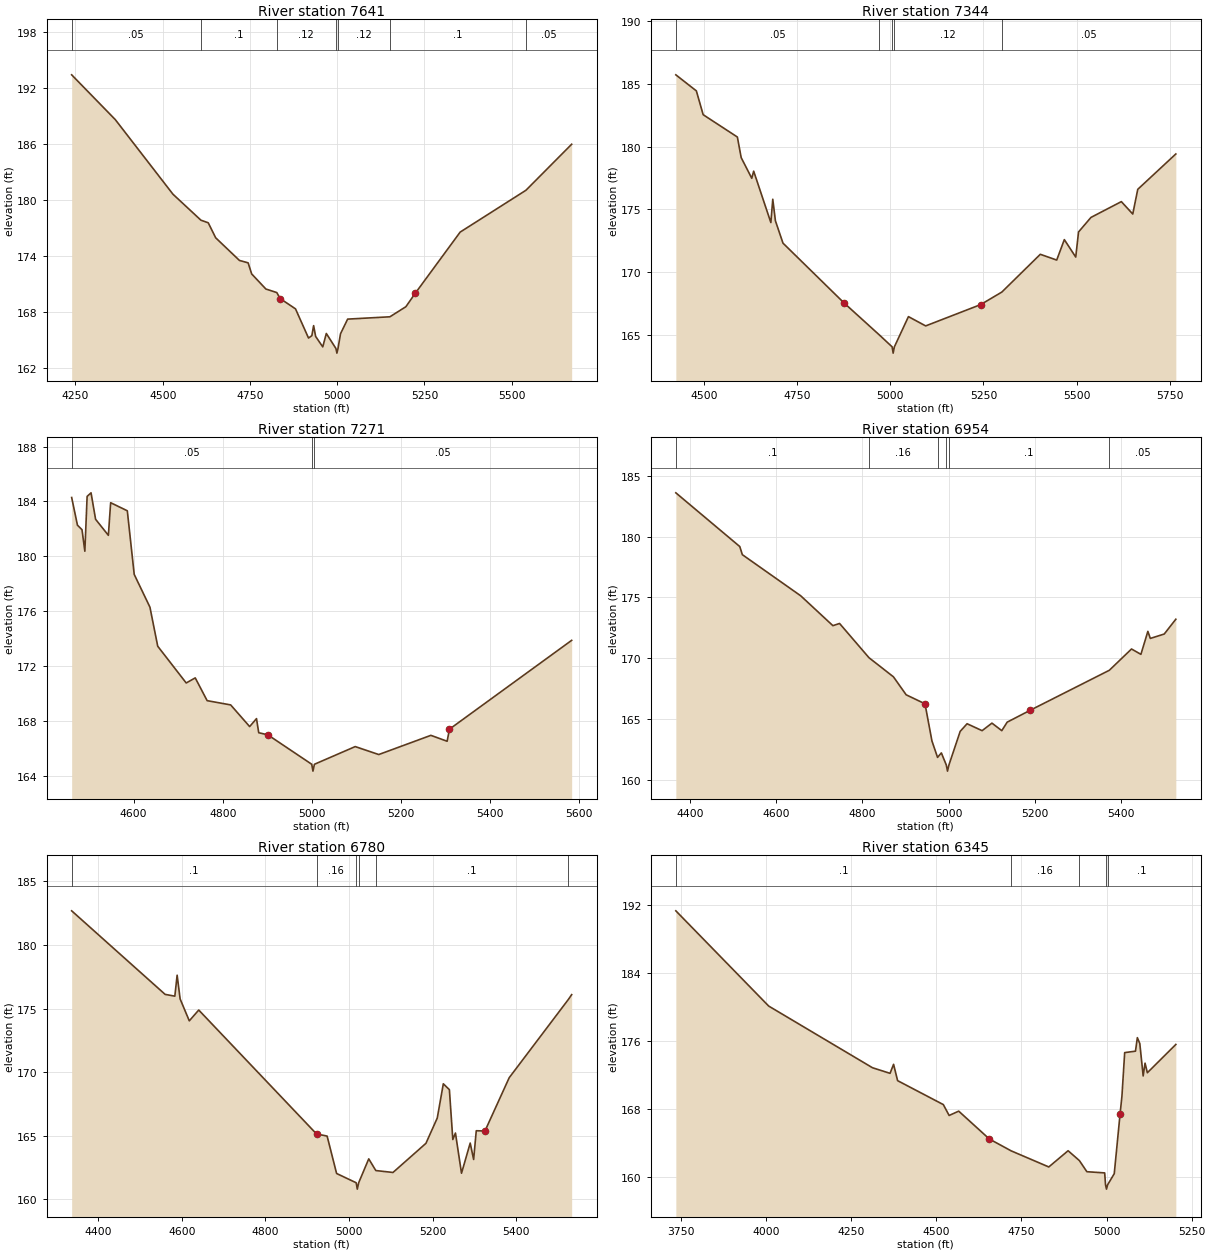
Type RM Length L Ch R = 1 ,7641    ,297,297,297
BEGIN DESCRIPTION:
UNT027 IN PECR 14.0
END DESCRIPTION:
XS GIS Cut Line= 3
      2294872.62      13195784.3      2294719.83     13195367.61
      2294532.53     13194396.43
#Sta/Elev= 30
  4239.1  193.44  4364.2  188.63  4529.3  180.63  4609.5  177.84  4630.5  177.56
  4651.8  175.95  4719.9  173.52  4744.8  173.26    4755  172.07  4795.7  170.45
    4827  170.07  4836.5  169.43  4880.6  168.32  4917.9  165.19  4927.4  165.44
  4932.5  166.52  4938.3  165.36  4958.7  164.24  4968.9  165.68  4996.4  164.07
  4999.2  163.57  5002.4  164.07  5009.6  165.65    5030  167.22  5151.1  167.47
  5196.9  168.55  5223.5  169.98  5352.5  176.56    5541  181.05    5672  185.99
#Mann= 7 ,-1 , 0
  4239.1     .05       0  4609.5      .1       0    4827     .12       0
  4996.4     .07       0  5002.4     .12       0  5151.1      .1       0
    5541     .05       0
Bank Sta=4836.5,5223.5
XS Rating Curve= 0 ,0
Exp/Cntr=0.3,0.1

Type RM Length L Ch R = 1 ,7344    ,73,73,73
BEGIN DESCRIPTION:
Mapping XS fb27bb74
END DESCRIPTION:
XS GIS Cut Line= 2
       2295062.8     13195618.73      2294802.54     13194303.54
#Sta/Elev= 30
  4425.2  185.73  4480.2  184.45  4498.5  182.55  4590.2  180.77  4600.4  179.13
  4628.8  177.48  4633.9  178.05    4680  173.95  4685.1  175.81  4692.2  174.09
  4712.5  172.31  4875.6  167.56  4970.9  164.99  5005.2  164.04  5007.9  163.54
  5011.2  164.04  5048.9  166.45  5095.1  165.71  5242.6  167.41  5299.4  168.41
  5402.5  171.42  5446.5  170.96  5466.9  172.59  5497.5   171.2    5505   173.2
  5538.3  174.36  5619.8  175.62  5650.4  174.63  5663.8   176.6  5765.9  179.42
#Mann= 5 ,-1 , 0
  4425.2     .05       0  4970.9     .12       0  5005.2     .07       0
  5011.2     .12       0  5299.4     .05       0
Bank Sta=4875.6,5242.6
XS Rating Curve= 0 ,0
Exp/Cntr=0.3,0.1

Type RM Length L Ch R = 1 ,7271    ,317,317,317
BEGIN DESCRIPTION:
UNT027 IN PECR 13.0
END DESCRIPTION:
XS GIS Cut Line= 3
      2295118.35     13195559.65      2294969.05     13194754.11
      2294889.24     13194461.76
#Sta/Elev= 30
  4460.9  184.29  4473.9  182.27  4484.1  181.94  4490.5  180.37  4495.6  184.37
  4504.4  184.63  4514.6   182.7  4543.3  181.53  4548.4  183.91  4585.8  183.32
  4601.3  178.68  4636.6  176.29  4654.1  173.44    4718  170.76  4738.3  171.13
    4765  169.47  4817.8  169.16  4860.4  167.58  4875.8  168.16  4880.8  167.13
  4901.1  166.98  4999.8  164.83  5002.5  164.33  5005.8  164.83  5097.4  166.12
  5150.2  165.54  5267.2  166.94  5303.7  166.51  5308.9  167.39  5583.2  173.87
#Mann= 3 ,-1 , 0
  4460.9     .05       0  4999.8     .03       0  5005.8     .05       0
Bank Sta=4901.1,5308.9
XS Rating Curve= 0 ,0
Exp/Cntr=0.3,0.1

Type RM Length L Ch R = 1 ,6954    ,174,174,174
BEGIN DESCRIPTION:
Mapping XS 64e6bd72
END DESCRIPTION:
XS GIS Cut Line= 3
      2295490.66      13195353.7      2295289.28     13194964.83
      2294942.38     13194333.47
#Sta/Elev= 30
  4367.8   183.6  4515.9  179.18  4521.9  178.51    4657  175.13  4731.6  172.67
  4747.1  172.85  4815.3  170.03  4871.9  168.46  4901.4  166.98    4945  166.24
  4961.1  163.18  4974.1  161.83  4982.9   162.2  4994.4   161.2  4997.1   160.7
  5000.4   161.2  5026.5  163.97  5042.5   164.6  5077.3  164.03  5100.1  164.65
  5122.9  164.03  5135.4  164.73  5189.4  165.72  5372.1     169  5423.4  170.75
  5445.2  170.31  5461.3   172.2    5467  171.62  5499.2  171.98  5526.1   173.2
#Mann= 6 ,-1 , 0
  4367.8      .1       0  4815.3     .16       0  4974.1      .1       0
  4994.4     .07       0  5000.4      .1       0  5372.1     .05       0
Bank Sta=4945,5189.4
XS Rating Curve= 0 ,0
Exp/Cntr=0.3,0.1

Type RM Length L Ch R = 1 ,6780    ,435,435,435
BEGIN DESCRIPTION:
Mapping XS 2c4bc6db
END DESCRIPTION:
XS GIS Cut Line= 3
      2295615.66     13195263.43      2295393.44     13194770.38
      2294992.57     13194252.01
#Sta/Elev= 30
  4336.8  182.68  4560.4  176.11  4583.6  175.97  4589.1  177.62  4596.3  175.75
  4618.2  174.03  4640.8  174.88  4922.5  165.14  4947.9  164.97  4970.6  162.03
  5017.4   161.3  5020.1   160.8  5023.4   161.3  5047.5  163.18  5064.4  162.26
  5105.5  162.11  5184.3   164.4  5211.4  166.39  5225.9  169.08  5240.4  168.62
  5248.6   164.7  5254.9  165.21  5269.4  162.05  5290.2  164.42  5298.4  163.13
  5304.7  165.39  5325.5  165.37  5383.5  169.56  5525.2  175.72  5532.9  176.09
#Mann= 6 ,-1 , 0
  4336.8      .1       0  4922.5     .16       0  5017.4     .07       0
  5023.4     .16       0  5064.4      .1       0  5525.2     .05       0
Bank Sta=4922.5,5325.5
XS Rating Curve= 0 ,0
Exp/Cntr=0.3,0.1

Type RM Length L Ch R = 1 ,6345    ,328,328,328
BEGIN DESCRIPTION:
UNT027 IN PECR 12.0
END DESCRIPTION:
XS GIS Cut Line= 3
      2295875.83     13195391.71      2295371.82     13194361.75
      2295082.47     13194221.99
#Sta/Elev= 30
  3735.4  191.37    4008  180.16  4312.7   172.9  4364.3  172.24  4374.7   173.3
  4386.5  171.38  4520.8  168.56  4537.8  167.28  4565.9  167.79  4655.9  164.51
  4720.2  163.11  4830.4  161.22  4887.1  163.13  4920.2  161.97  4942.2  160.66
  4994.5  160.52    4997  159.11  4999.8  158.61    5003  159.11  5022.6  160.43
  5039.7  167.46  5045.2  169.57  5053.2  174.68  5084.9  174.85  5090.4  176.44
  5097.6  175.75  5107.5  171.93    5113  173.44  5119.8  172.31  5203.4  175.64
#Mann= 5 ,-1 , 0
  3735.4      .1       0  4720.2     .16       0  4920.2      .1       0
    4997     .07       0    5003      .1       0
Bank Sta=4655.9,5039.7
XS Rating Curve= 0 ,0
Exp/Cntr=0.3,0.1

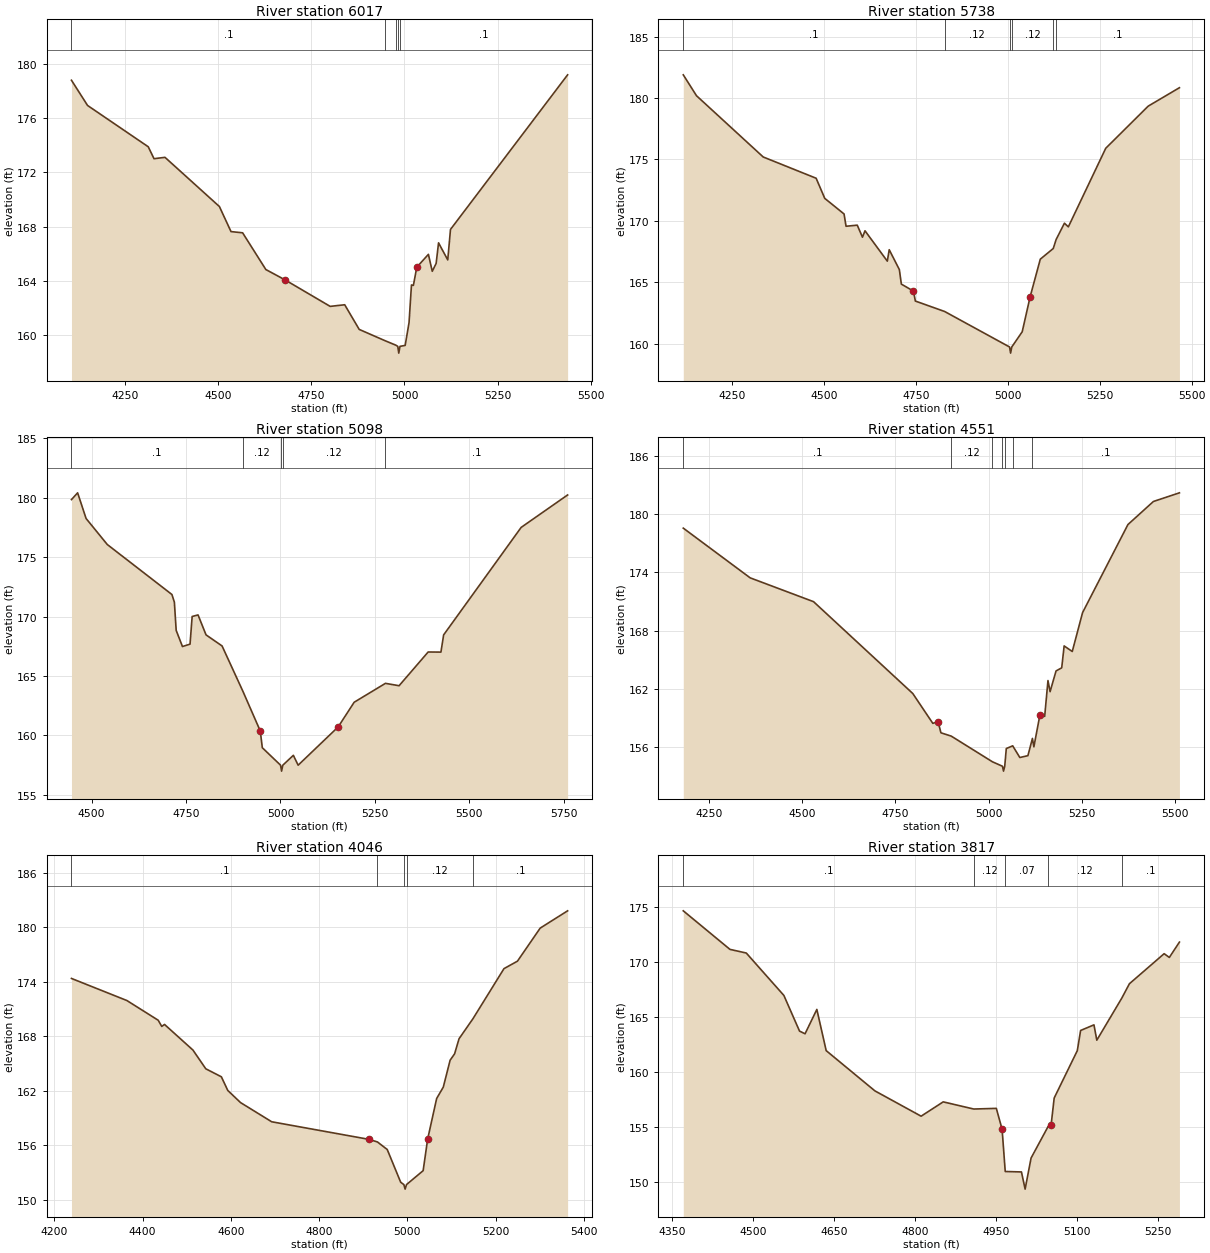
Type RM Length L Ch R = 1 ,6017    ,279,279,279
BEGIN DESCRIPTION:
UNT027 IN PECR 11.0
END DESCRIPTION:
XS GIS Cut Line= 4
      2295863.95     13195036.05      2295704.21     13194709.62
      2295523.65     13194077.67      2295516.71      13193765.2
#Sta/Elev= 30
  4105.2   178.8  4148.4  176.94  4311.5  173.89    4327  173.01  4356.5  173.11
  4502.7  169.48  4533.9  167.63  4565.1  167.54  4627.5  164.83  4679.5  164.06
  4800.4  162.11  4839.4  162.23  4878.4  160.41  4948.4  159.57  4976.5  159.25
    4982  159.16  4984.7  158.66    4988  159.16  5001.9  159.23  5012.3  160.91
  5018.8  163.69    5024  163.66  5033.1     165  5064.3  165.95  5074.7   164.7
  5085.1  165.28  5091.6   166.8  5116.3  165.54  5123.7  167.79  5438.4   179.2
#Mann= 5 ,-1 , 0
  4105.2      .1       0  4948.4     .16       0  4976.5      .1       0
    4982     .07       0    4988      .1       0
Bank Sta=4679.5,5033.1
XS Rating Curve= 0 ,0
Exp/Cntr=0.3,0.1

Type RM Length L Ch R = 1 ,5738    ,640,640,640
BEGIN DESCRIPTION:
UNT027 IN PECR 10.0
END DESCRIPTION:
XS GIS Cut Line= 4
      2296023.65     13195022.11      2295933.37     13194542.95
      2295752.82     13193945.73      2295614.14     13193751.58
#Sta/Elev= 30
  4116.7  181.88  4152.6  180.18  4334.2  175.19  4478.2  173.46  4501.7  171.82
  4554.2  170.55  4559.6  169.55  4590.1  169.64  4604.3  168.66  4611.2  169.18
  4671.9  166.71  4677.1  167.64  4704.7  166.02  4710.1  164.84    4743  164.27
  4748.2  163.46  4827.9  162.61  5004.6  159.72  5007.4  159.22  5010.6  159.72
    5039  160.96  5060.4  163.79  5088.2  166.87  5123.5  167.74  5131.3  168.47
  5153.9   169.8  5164.5   169.5  5266.3   175.9  5381.8  179.33  5466.8  180.83
#Mann= 6 ,-1 , 0
  4116.7      .1       0  4827.9     .12       0  5004.6     .07       0
  5010.6     .12       0  5123.5     .16       0  5131.3      .1       0
Bank Sta=4743,5060.4
XS Rating Curve= 0 ,0
Exp/Cntr=0.3,0.1

Type RM Length L Ch R = 1 ,5098    ,547,547,547
BEGIN DESCRIPTION:
UNT027 IN PECR 9.0
END DESCRIPTION:
XS GIS Cut Line= 4
      2296838.79      13194199.4      2296621.74     13194025.77
      2296079.21     13193834.79      2295632.44     13193722.02
#Sta/Elev= 30
  4446.6  179.85  4462.9  180.42  4485.3  178.26  4541.4  176.07  4712.6  171.86
  4719.1  171.22  4723.9  168.84  4740.5  167.48  4760.6  167.68  4766.2  170.01
  4781.8  170.14    4803  168.46  4845.4  167.53  4900.9  163.69  4946.6  160.37
    4952  158.96  5000.3  157.49    5003  156.99  5006.3  157.49  5034.2  158.32
  5046.9  157.49  5152.8  160.71  5195.3  162.79  5278.1  164.38  5314.2  164.18
  5391.2  167.02    5425  167.01  5432.2  168.46  5637.5  177.51  5760.5  180.24
#Mann= 5 ,-1 , 0
  4446.6      .1       0  4900.9     .12       0  5000.3     .07       0
  5006.3     .12       0  5278.1      .1       0
Bank Sta=4946.6,5152.8
XS Rating Curve= 0 ,0
Exp/Cntr=0.3,0.1

Type RM Length L Ch R = 1 ,4551    ,505,505,505
BEGIN DESCRIPTION:
UNT027 IN PECR 8.0
END DESCRIPTION:
XS GIS Cut Line= 4
       2296886.5     13194038.79      2296582.68     13193648.16
      2296074.87     13193366.04      2295841.56     13193262.35
#Sta/Elev= 30
    4181  178.54  4360.4  173.43  4530.5  170.98  4796.7  161.54  4850.5  158.47
  4864.6  158.66  4872.2   157.5  4899.9  157.16  5010.4  154.52  5037.4  154.06
  5040.2  153.56  5043.4  154.06  5047.6  155.88  5064.8  156.16  5083.9  154.96
  5105.6  155.15  5117.7  156.92  5121.6  156.06  5137.6  159.29  5150.6  159.19
  5159.4  162.87  5165.1  161.73  5181.1  163.86  5196.3  164.18  5202.8  166.43
  5224.6  165.86  5252.3  169.86    5374  178.91  5442.3  181.28  5512.1  182.17
#Mann= 7 ,-1 , 0
    4181      .1       0  4899.9     .12       0  5010.4     .16       0
  5037.4     .07       0  5043.4     .16       0  5064.8     .12       0
  5117.7      .1       0
Bank Sta=4864.6,5137.6
XS Rating Curve= 0 ,0
Exp/Cntr=0.3,0.1

Type RM Length L Ch R = 1 ,4046    ,229,229,229
BEGIN DESCRIPTION:
UNT027 IN PECR 7.0
END DESCRIPTION:
XS GIS Cut Line= 4
      2296847.42     13193843.46      2296656.46     13193591.74
      2296504.55     13193396.42      2296400.38     13192845.17
#Sta/Elev= 30
  4238.9  174.36  4364.5  171.93  4435.5  169.76  4443.5  169.08  4449.8   169.3
  4514.2  166.48  4543.3  164.42  4578.6  163.54  4593.1  162.04  4622.1   160.7
  4692.7  158.59  4913.8  156.65  4932.3  156.37  4954.5  155.54    4985  151.94
  4992.2  151.68    4995  151.18  4998.2  151.68  5035.9  153.21  5046.1  156.68
  5066.5  161.15  5081.6  162.41    5097  165.36  5107.2  166.07  5117.3  167.73
  5148.8  169.93  5219.1  175.44  5249.6  176.26  5301.2   179.9  5363.3   181.8
#Mann= 5 ,-1 , 0
  4238.9      .1       0  4932.3     .12       0  4992.2     .07       0
  4998.2     .12       0  5148.8      .1       0
Bank Sta=4913.8,5046.1
XS Rating Curve= 0 ,0
Exp/Cntr=0.3,0.1

Type RM Length L Ch R = 1 ,3817    ,306,306,306
BEGIN DESCRIPTION:
UNT027 IN PECR 6.0
END DESCRIPTION:
XS GIS Cut Line= 3
      2296925.58     13193774.06       2296821.4     13193530.97
      2296587.56      13192920.4
#Sta/Elev= 30
  4371.4  174.62  4457.8  171.12    4488  170.79  4557.6  166.94  4586.6   163.7
  4596.8  163.46  4618.6  165.67  4635.9  161.93    4726  158.28  4811.6  155.98
  4852.5  157.28    4909  156.63  4950.8  156.69  4961.5  154.79  4967.3  150.96
  4997.3  150.92  5004.1  149.36  5015.1  152.18  5046.7  155.05  5052.1  155.14
  5057.9  157.63  5100.7  161.93  5106.8  163.76  5131.5  164.27  5136.8  162.88
  5183.2  166.71  5197.1     168  5261.4  170.73    5271  170.39  5289.7  171.78
#Mann= 5 ,-1 , 0
  4371.4      .1       0    4909     .12       0  4967.3     .07       0
  5046.7     .12       0  5183.2      .1       0
Bank Sta=4961.5,5052.1
XS Rating Curve= 0 ,0
Exp/Cntr=0.3,0.1

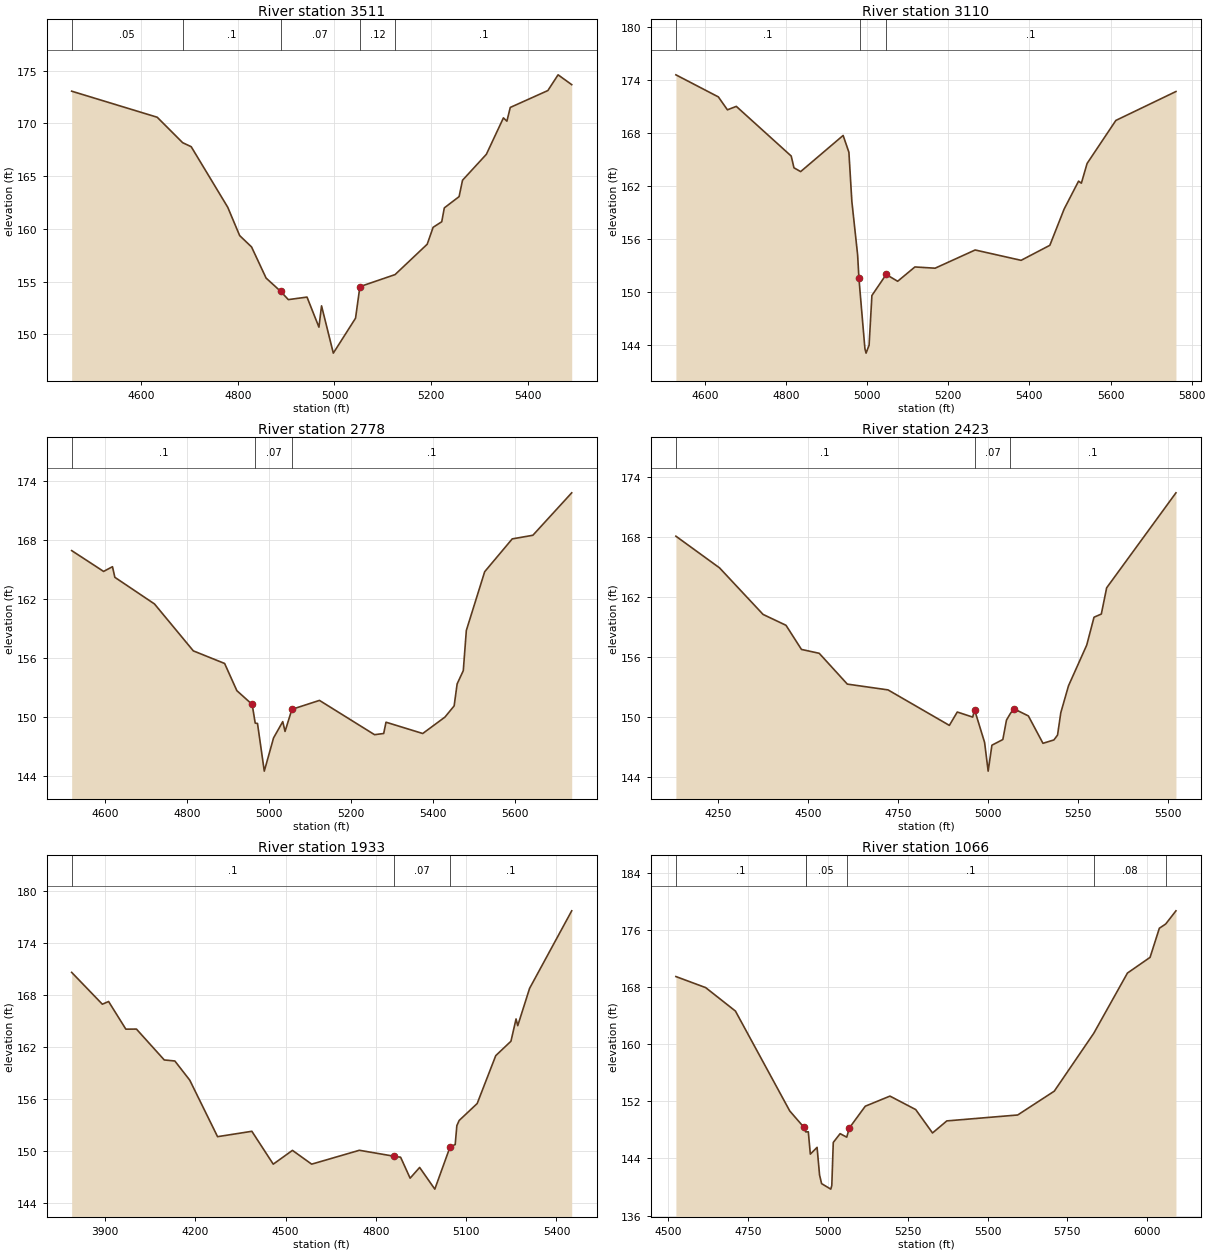
Type RM Length L Ch R = 1 ,3511    ,401,401,401
BEGIN DESCRIPTION:
UNT027 IN PECR 5.0
END DESCRIPTION:
XS GIS Cut Line= 4
       2297112.2      13193713.3      2297086.15     13193431.15
       2296908.2     13192966.74      2296725.94     13192788.81
#Sta/Elev= 30
  4455.9  173.05  4633.1  170.58  4685.7  168.17  4703.4  167.79  4779.1  162.05
  4803.7  159.37  4828.4  158.29  4858.5  155.34  4888.5  154.09  4904.5   153.3
  4943.2  153.54  4967.9  150.69  4973.3  152.71  4997.7  148.23  5043.7  151.54
  5052.7  154.53  5125.5  155.67  5192.1  158.55  5204.3  160.15  5222.2  160.68
  5227.5  161.99  5258.1  163.06  5265.2  164.61  5314.6  167.07  5349.9  170.52
  5357.1  170.21  5364.1  171.51  5441.9  173.11  5463.1   174.6  5491.3  173.67
#Mann= 5 ,-1 , 0
  4455.9     .05       0  4685.7      .1       0  4888.5     .07       0
  5052.7     .12       0  5125.5      .1       0
Bank Sta=4888.5,5052.7
XS Rating Curve= 0 ,0
Exp/Cntr=0.3,0.1

Type RM Length L Ch R = 1 ,3110    ,332,332,332
BEGIN DESCRIPTION:
Mapping XS 26c961d2
END DESCRIPTION:
XS GIS Cut Line= 3
      2297587.11     13193643.01      2297427.38     13193281.89
      2296816.29       13192709.
#Sta/Elev= 30
  4528.8  174.59  4633.5  172.09  4655.8  170.63  4677.7  171.02    4813   165.4
  4819.8  164.07  4836.3  163.64    4941  167.73  4955.2  165.83  4962.5  160.26
  4976.7  154.22 4979.89  151.61  4983.5  149.62  4994.7   143.6  4997.5   143.1
    5005     144  5011.9  149.62  5047.1     152  5075.4  151.23  5117.9  152.85
  5167.7  152.71  5266.4  154.77  5379.7   153.6  5450.5   155.3  5485.7   159.4
  5521.3  162.56  5528.2  162.33  5542.3  164.56  5613.2  169.43  5761.3   172.7
#Mann= 3 ,-1 , 0
  4528.8      .1       0  4983.5     .07       0  5047.1      .1       0
Bank Sta=4979.89,5047.1
XS Rating Curve= 0 ,0
Exp/Cntr=0.3,0.1

Type RM Length L Ch R = 1 ,2778    ,355,355,355
BEGIN DESCRIPTION:
Mapping XS 9bce3ece
END DESCRIPTION:
XS GIS Cut Line= 3
      2297781.76     13193328.34      2297634.69     13193069.42
      2296811.53     13192657.84
#Sta/Elev= 30
  4519.5  166.94  4597.3  164.82  4618.9   165.3  4624.7  164.22  4721.2  161.51
  4815.9  156.73  4892.1  155.45  4921.9  152.68  4959.2  151.28  4966.6  149.38
  4972.2  149.34  4988.7  144.49  5011.3  147.87  5033.7  149.53  5039.3  148.53
    5056  150.78  5123.1  151.69  5257.3   148.2  5279.6  148.32  5285.2  149.47
  5374.7  148.32  5428.8  149.99  5451.2  151.13  5458.5  153.37  5473.5  154.72
  5480.9  158.81  5525.6  164.79  5592.7  168.13    5643   168.5  5737.6  172.82
#Mann= 3 ,-1 , 0
  4519.5      .1       0  4966.6     .07       0    5056      .1       0
Bank Sta=4959.2,5056
XS Rating Curve= 0 ,0
Exp/Cntr=0.3,0.1

Type RM Length L Ch R = 1 ,2423    ,490,490,490
BEGIN DESCRIPTION:
UNT027 IN PECR 4.0
END DESCRIPTION:
XS GIS Cut Line= 3
      2298017.68     13193188.16      2297413.49     13192677.72
      2296823.19      13192580.5
#Sta/Elev= 30
  4132.3  168.11  4253.6  164.93  4374.5  160.26  4438.2  159.17  4481.1  156.75
  4530.5  156.36  4608.5  153.27  4721.6  152.69    4892  149.13    4914  150.47
  4956.9  149.96    4962   150.7  4989.9  147.42  4999.8  144.54  5010.2  147.14
  5040.6  147.71  5050.7  149.66  5060.8  150.28    5071   150.8  5111.5  150.08
  5152.1  147.33  5182.5  147.67  5192.6  148.16  5201.6   150.4    5223   153.1
  5273.7  157.19  5293.9  159.98  5314.2   160.3    5329  162.93  5521.5  172.46
#Mann= 3 ,-1 , 0
  4132.3      .1       0    4962     .07       0  5060.8      .1       0
Bank Sta=4962,5071
XS Rating Curve= 0 ,0
Exp/Cntr=0.3,0.1

Type RM Length L Ch R = 1 ,1933    ,867,867,867
BEGIN DESCRIPTION:
UNT027 IN PECR 3.0
END DESCRIPTION:
XS GIS Cut Line= 4
      2298038.48      13193129.1      2297407.34      13192605.7
      2297287.72     13192246.85      2296872.24     13192042.51
#Sta/Elev= 30
  3789.5  170.65  3891.4  166.98  3912.2  167.29  3969.5   164.1  4004.7  164.11
  4097.1  160.55  4132.3  160.43  4181.8  158.22  4274.2   151.7  4388.1  152.32
  4459.2  148.53    4523  150.12  4586.8  148.53  4745.3  150.13  4861.2  149.44
  4882.3  149.33  4913.9  146.91  4945.5  148.15  4995.9  145.65  5046.7  150.53
  5063.6  150.79  5069.1  152.97  5076.8  153.57  5136.6  155.52  5198.4  161.05
  5248.9  162.71  5265.8  165.28  5271.4   164.5  5310.8  168.81  5450.7  177.75
#Mann= 3 , 0 , 0
  3789.5      .1       0  4861.2     .07       0  5046.7      .1       0
Bank Sta=4861.2,5046.7
XS Rating Curve= 0 ,0
Exp/Cntr=0.3,0.1

Type RM Length L Ch R = 1 ,1066    ,733,733,733
BEGIN DESCRIPTION:
UNT027 IN PECR 2.0
END DESCRIPTION:
XS GIS Cut Line= 4
      2297989.85     13192955.47       2297562.8     13192406.89
       2297500.3     13192073.56      2297076.69     13191754.12
#Sta/Elev= 30
  4524.8  169.52  4617.9  167.97  4711.1  164.68  4881.2  150.66  4924.7  148.41
    4931  147.73  4939.2  147.74  4945.5  144.61  4966.6  145.56  4974.4  141.68
  4980.8  140.47  5009.5   139.7  5012.7   140.2  5017.3  146.25  5038.7  147.48
  5059.5  146.99  5067.6  148.28  5117.4  151.33  5194.7  152.75  5275.3  150.86
  5327.9  147.58  5372.7  149.27  5594.4   150.1  5708.9  153.44  5832.5  161.56
  5937.9  170.01  6008.7  172.21  6037.8   176.3  6057.6  176.89  6089.7  178.74
#Mann= 6 ,-1 , 0
  4524.8      .1       0    4931     .12       0    4931     .05       0
  5059.5      .1       0  5832.5     .08       0  6057.6      .1       0
Bank Sta=4924.7,5067.6
XS Rating Curve= 0 ,0
Exp/Cntr=0.3,0.1

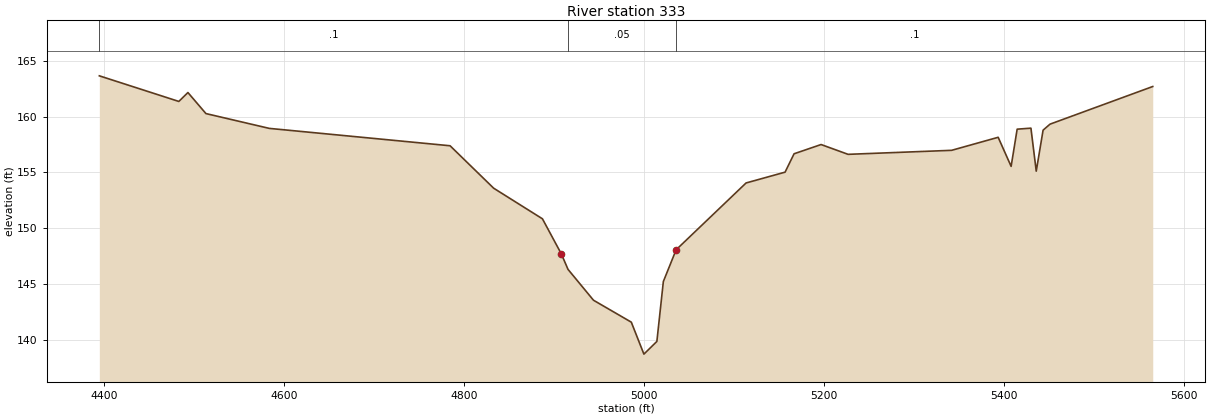
Type RM Length L Ch R = 1 ,333     ,0,0,0
BEGIN DESCRIPTION:
UNT027 IN PECR 1.0
END DESCRIPTION:
XS GIS Cut Line= 5
      2298092.48     13192644.78      2298051.05     13192205.64
      2297837.69     13191979.85      2297647.12     13191973.64
      2297454.86     13191851.66
#Sta/Elev= 30
  4394.7  163.68    4483  161.38  4493.1  162.18  4513.1  160.29  4583.5  158.96
  4784.3   157.4  4832.7  153.59  4886.9  150.84    4908  147.67  4915.3   146.3
  4943.6  143.53  4985.6  141.56  4999.6  138.69    5014  139.83  5021.2  145.21
  5035.4  148.06  5113.1  154.06  5156.4  155.03  5166.4  156.68  5196.4  157.51
  5226.4  156.63  5341.4  156.99  5393.1  158.16  5407.5  155.55  5414.2  158.89
  5429.5  158.98  5435.4  155.12    5443   158.8  5450.7  159.34  5564.8  162.72
#Mann= 3 ,-1 , 0
  4394.7      .1       0  4915.3     .05       0  5035.4      .1       0
Bank Sta=4908,5035.4
XS Rating Curve= 0 ,0
Exp/Cntr=0.3,0.1

Chan Stop Cuts=-1
Use User Specified Reach Order=0
Composite Channel Slope=5