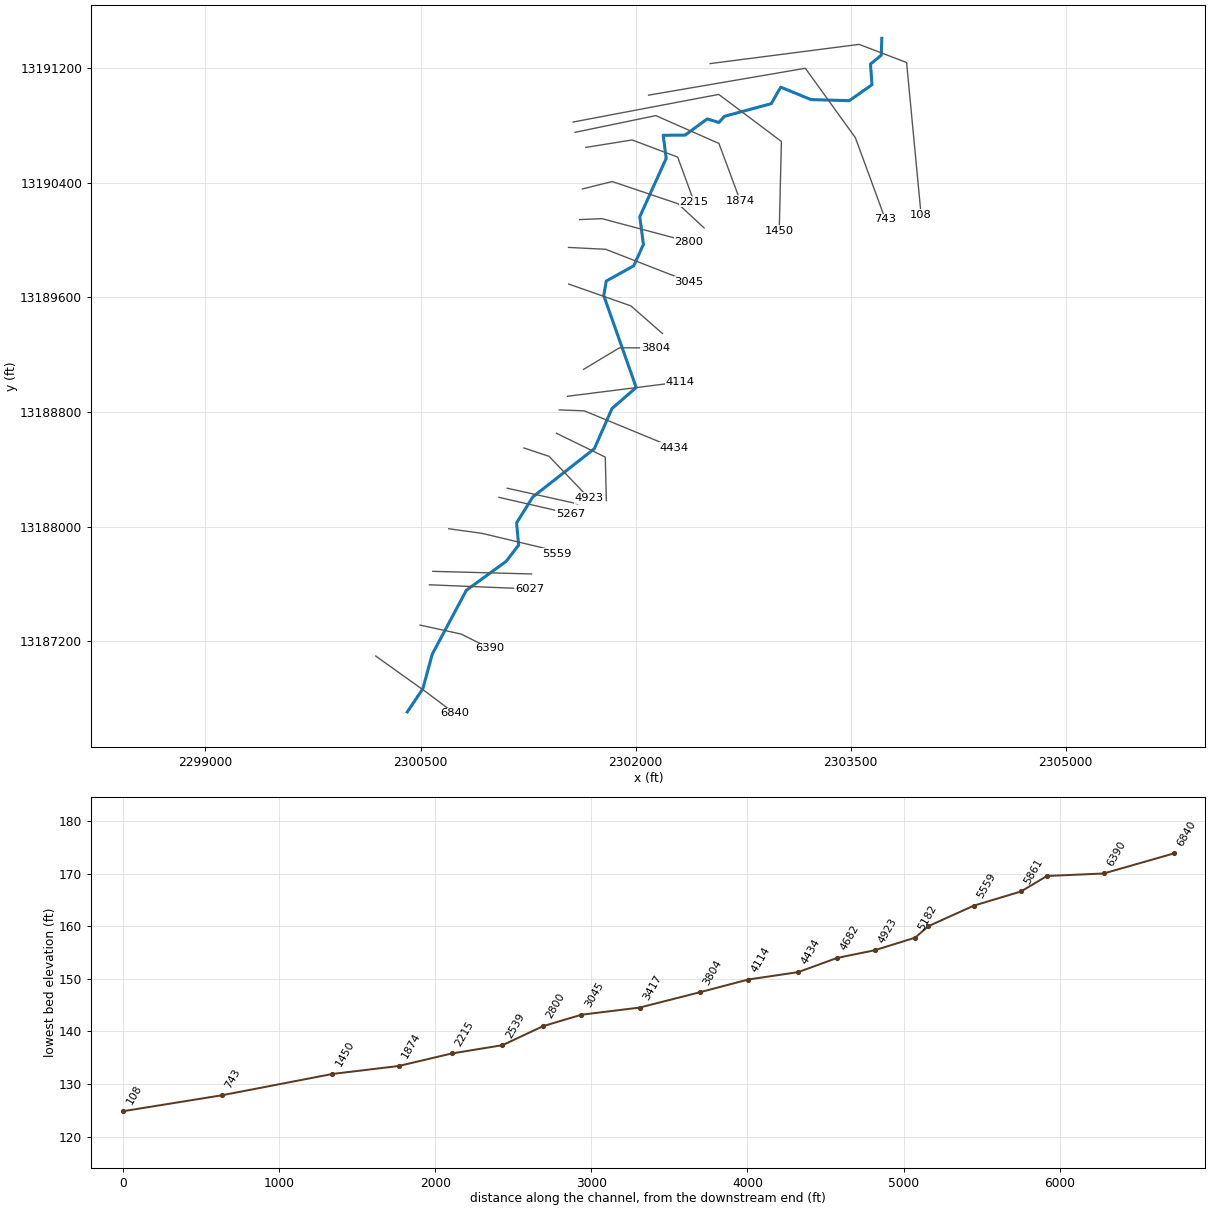
--- UNT028 IN PECR.prj (project) ---

Proj Title=UNT028 IN PECR Base Level Engineering
Current Plan=p01
Default Exp/Contr=0.3,0.1
English Units
Geom File=g01
Flow File=f01
Plan File=p01
Y Axis Title=Elevation
X Axis Title(PF)=Main Channel Distance
X Axis Title(XS)=Station
BEGIN DESCRIPTION:
UNT028 IN PECR
END DESCRIPTION:
DSS Export Rating Curves= 0
DSS Export Rating Curve Sorted= 0
DSS Export Volume Flow Curves= 0
DXF OffsetX= 0
DXF OffsetY= 0
DXF ScaleX= 1
DXF ScaleY= 10

--- UNT028 IN PECR.p01 (plan) ---

Plan Title=Multiple Run
Short Identifier=Multiple
Geom File=g01
Flow File=f01
Subcritical Flow
K Sum by GR= 0
Std Step Tol= 0.01
Critical Tol= 0.01
Num of Std Step Trials= 20
Max Error Tol= 0.3
Flow Tol Ratio= 0.001
Split Flow NTrial= 30
Split Flow Tol= 0.02
Split Flow Ratio= 0.02
Log Output Level= 0
Friction Slope Method= 1
Unsteady Friction Slope Method= 2
Unsteady Bridges Friction Slope Method= 1
Parabolic Critical Depth
Global Vel Dist=  1 , 1 , 1
Global Log Level= 0
CheckData=True
Encroach Param= -1, 0, 0, 0
BEGIN DESCRIPTION:
Multiple Run
END DESCRIPTION:

--- UNT028 IN PECR.f01 (steady flow) ---

Flow Title=Multiple
Program Version=4.10
Number of Profiles= 7
Profile Names=10-year,25-year,50-year,1pct_min,100-year,1pct_plu,500-year
River Rch & RM=UNT028 IN PECR,Reach-1         ,6840
     277     371     445     391     528     715     751
River Rch & RM=UNT028 IN PECR,Reach-1         ,6027
     549     766     946     853    1153    1559    1725
Boundary for River Rch & Prof#=UNT028 IN PECR,Reach-1         , 1
Up Type= 0
Dn Type= 3
Dn Slope=0.005
Boundary for River Rch & Prof#=UNT028 IN PECR,Reach-1         , 2
Up Type= 0
Dn Type= 3
Dn Slope=0.005
Boundary for River Rch & Prof#=UNT028 IN PECR,Reach-1         , 3
Up Type= 0
Dn Type= 3
Dn Slope=0.005
Boundary for River Rch & Prof#=UNT028 IN PECR,Reach-1         , 4
Up Type= 0
Dn Type= 3
Dn Slope=0.005
Boundary for River Rch & Prof#=UNT028 IN PECR,Reach-1         , 5
Up Type= 0
Dn Type= 3
Dn Slope=0.005
Boundary for River Rch & Prof#=UNT028 IN PECR,Reach-1         , 6
Up Type= 0
Dn Type= 3
Dn Slope=0.005
Boundary for River Rch & Prof#=UNT028 IN PECR,Reach-1         , 7
Up Type= 0
Dn Type= 3
Dn Slope=0.005
DSS Import GetInterval= 0
DSS Import GetPeak= 0
DSS Import FillOption= 0

--- UNT028 IN PECR.g01 (geometry) ---

Geom Title=Existing Conditions

River Reach=UNT028 IN PECR,Reach-1
Reach XY= 30
      2300407.72     13186706.86      2300515.93     13186867.60
      2300582.04     13187109.78      2300820.00     13187555.95
      2301097.10     13187756.97      2301184.30     13187870.46
      2301170.24     13188025.66      2301283.31     13188206.65
      2301712.90     13188543.47      2301835.67     13188823.11
      2302004.47     13188970.31      2301778.26     13189611.50
      2301795.72     13189712.73      2301987.16     13189818.75
      2302055.03     13189968.17      2302029.61     13190161.22
      2302213.76     13190568.25      2302192.97     13190729.58
      2302346.37     13190730.86      2302499.63     13190843.56
      2302581.66     13190819.00      2302620.27     13190861.89
      2302946.70     13190950.20      2303013.14     13191065.40
      2303223.25     13190978.60      2303490.75     13190970.96
      2303649.36     13191081.95      2303638.88     13191226.17
      2303714.20     13191288.20      2303717.74     13191405.84

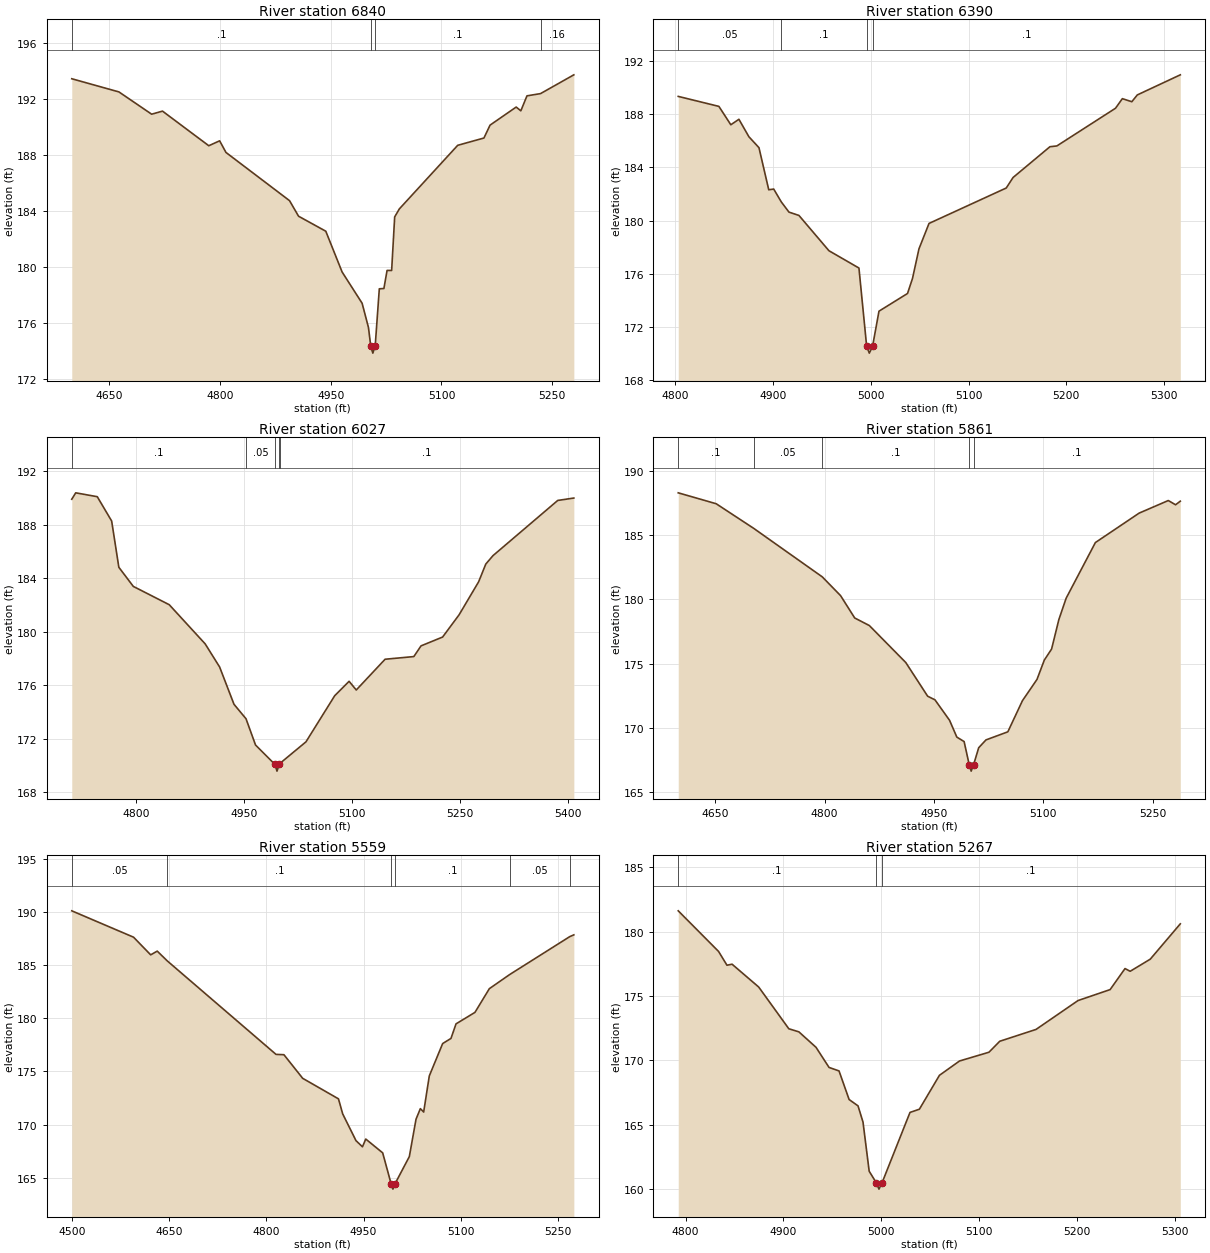
Type RM Length L Ch R = 1,6840,450,450,450
BEGIN DESCRIPTION:
UNT028 IN PECR 11.0
END DESCRIPTION:
XS GIS Cut Line= 3
      2300187.71     13187096.86      2300537.72     13186846.85
      2300737.70     13186696.87
#Sta/Elev= 30
  4599.2  193.44  4663.1  192.50  4707.4  190.91  4722.1  191.13  4784.8  188.66
  4799.5  189.01  4808.1  188.18  4894.2  184.74  4906.4  183.63  4943.3  182.56
  4965.4  179.65  4992.5  177.42  5001.1  175.69  5004.2  174.36  5007.0  173.86
  5010.2  174.36  5015.8  178.45  5022.0  178.47  5026.3  179.76  5032.5  179.76
  5036.6  183.58  5042.9  184.15  5122.0  188.69  5157.5  189.21  5165.8  190.13
  5201.2  191.42  5207.5  191.15  5215.8  192.22  5234.2  192.38  5279.3  193.72
#Mann=4,-1,0
  4599.2     0.1       0  5004.2    0.07       0  5010.2     0.1       0
  5234.2    0.16       0
Bank Sta=5004.2,5010.2
Exp/Cntr=0.3,0.1

Type RM Length L Ch R = 1,6390,363,363,363
BEGIN DESCRIPTION:
UNT028 IN PECR 10.0
END DESCRIPTION:
XS GIS Cut Line= 3
      2300497.04     13187312.63      2300783.54     13187250.12
      2300980.73     13187151.53
#Sta/Elev= 30
  4802.9  189.32  4844.5  188.57  4856.7  187.19  4865.0  187.60  4875.2  186.29
  4885.5  185.47  4895.5  182.31  4900.6  182.36  4908.4  181.39  4916.2  180.63
  4926.4  180.38  4957.1  177.73  4987.8  176.43  4995.7  170.54  4998.4  170.04
  5001.7  170.54  5008.3  173.19  5037.5  174.52  5042.6  175.65  5049.2  177.87
  5059.5  179.78  5138.5  182.44  5145.5  183.23  5183.2  185.54  5190.3  185.60
  5250.3  188.43  5257.3  189.15  5267.0  188.92  5272.6  189.43  5316.6  190.94
#Mann=4,-1,0
  4802.9    0.05       0  4908.4     0.1       0  4995.7    0.07       0
  5001.7     0.1       0
Bank Sta=4995.7,5001.7
Exp/Cntr=0.3,0.1

Type RM Length L Ch R = 1,6027,166,166,166
BEGIN DESCRIPTION:
Mapping XS bf980ddd
END DESCRIPTION:
XS GIS Cut Line= 2
      2300562.23     13187593.87      2301260.15     13187565.22
#Sta/Elev= 30
  4710.2  189.91  4715.7  190.39  4745.7  190.10  4765.7  188.28  4775.7  184.82
  4795.8  183.39  4845.8  182.02  4895.8  179.09  4915.9  177.36  4935.9  174.57
  4952.6  173.49  4965.9  171.52  4992.9  170.07  4995.7  169.57  4998.9  170.07
  4999.4  170.13  5036.0  171.76  5076.0  175.21  5096.0  176.29  5106.0  175.64
  5146.1  177.94  5186.1  178.14  5196.1  178.94  5226.1  179.60  5249.0  181.26
  5276.2  183.73  5286.2  185.06  5296.2  185.69  5386.3  189.82  5408.7  190.00
#Mann=5,-1,0
  4710.2     0.1       0  4952.6    0.05       0  4992.9    0.07       0
  4998.9    0.05       0  4999.4     0.1       0
Bank Sta=4992.9,4998.9
Exp/Cntr=0.3,0.1

Type RM Length L Ch R = 1,5861,302,302,302
BEGIN DESCRIPTION:
UNT028 IN PECR 9.0
END DESCRIPTION:
XS GIS Cut Line= 2
      2300585.66     13187687.62      2301274.22     13187669.43
#Sta/Elev= 30
  4599.2  188.29  4651.3  187.44  4702.6  185.53  4796.8  181.75  4821.9  180.29
  4841.3  178.55  4861.4  177.96  4911.4  175.08  4941.4  172.46  4951.4  172.18
  4971.4  170.59  4981.4  169.28  4991.4  168.93  4998.4  167.13  5001.1  166.63
  5004.4  167.13  5011.4  168.45  5021.4  169.06  5051.4  169.69  5071.4  172.11
  5091.4  173.77  5101.4  175.27  5111.4  176.13  5121.4  178.43  5131.4  180.09
  5171.5  184.42  5231.5  186.71  5271.5  187.69  5281.5  187.36  5288.0  187.64
#Mann=5,-1,0
  4599.2     0.1       0  4702.6    0.05       0  4796.8     0.1       0
  4998.4    0.07       0  5004.4     0.1       0
Bank Sta=4998.4,5004.4
Exp/Cntr=0.3,0.1

Type RM Length L Ch R = 1,5559,292,292,292
BEGIN DESCRIPTION:
UNT028 IN PECR 8.0
END DESCRIPTION:
XS GIS Cut Line= 4
      2300697.17     13187984.80      2300930.37     13187952.41
      2301364.29     13187848.79      2301448.49     13187809.92
#Sta/Elev= 30
  4500.0  190.10  4595.3  187.62  4621.7  185.96  4631.8  186.31  4647.5  185.38
  4815.0  176.60  4827.2  176.57  4856.1  174.35  4911.3  172.42  4917.8  171.01
  4938.3  168.49  4948.3  167.91  4953.4  168.64  4979.5  167.34  4992.5  164.43
  4995.3  163.93  4998.5  164.43  5020.6  166.99  5030.9  170.50  5037.6  171.50
  5042.7  171.18  5051.4  174.58  5072.0  177.62  5084.8  178.10  5092.6  179.47
  5121.8  180.55  5144.0  182.78  5175.4  184.11  5267.9  187.67  5274.3  187.84
#Mann=6,-1,0
  4500.0    0.05       0  4647.5     0.1       0  4992.5    0.07       0
  4998.5     0.1       0  5175.4    0.05       0  5267.9     0.1       0
Bank Sta=4992.5,4998.5
Exp/Cntr=0.3,0.1

Type RM Length L Ch R = 1,5267,85,85,85
BEGIN DESCRIPTION:
Mapping XS 3a0b8644
END DESCRIPTION:
XS GIS Cut Line= 2
      2301047.56     13188203.77      2301547.60     13188089.18
#Sta/Elev= 30
  4792.5  181.61  4833.7  178.46  4842.3  177.39  4847.5  177.47  4874.7  175.70
  4905.5  172.46  4915.8  172.22  4933.3  171.02  4946.6  169.46  4956.8  169.19
  4967.1  166.97  4976.2  166.48  4981.3  165.22  4987.6  161.41  4994.8  160.52
  4997.6  160.02  5000.8  160.52  5029.3  165.97  5038.9  166.22  5059.4  168.85
  5079.9  169.96  5110.0  170.64  5121.0  171.49  5158.1  172.41  5201.0  174.65
  5233.8  175.50  5249.0  177.13  5254.3  176.92  5274.8  177.86  5305.5  180.60
#Mann=3,-1,0
  4792.5     0.1       0  4994.8    0.07       0  5000.8     0.1       0
Bank Sta=4994.8,5000.8
Exp/Cntr=0.3,0.1

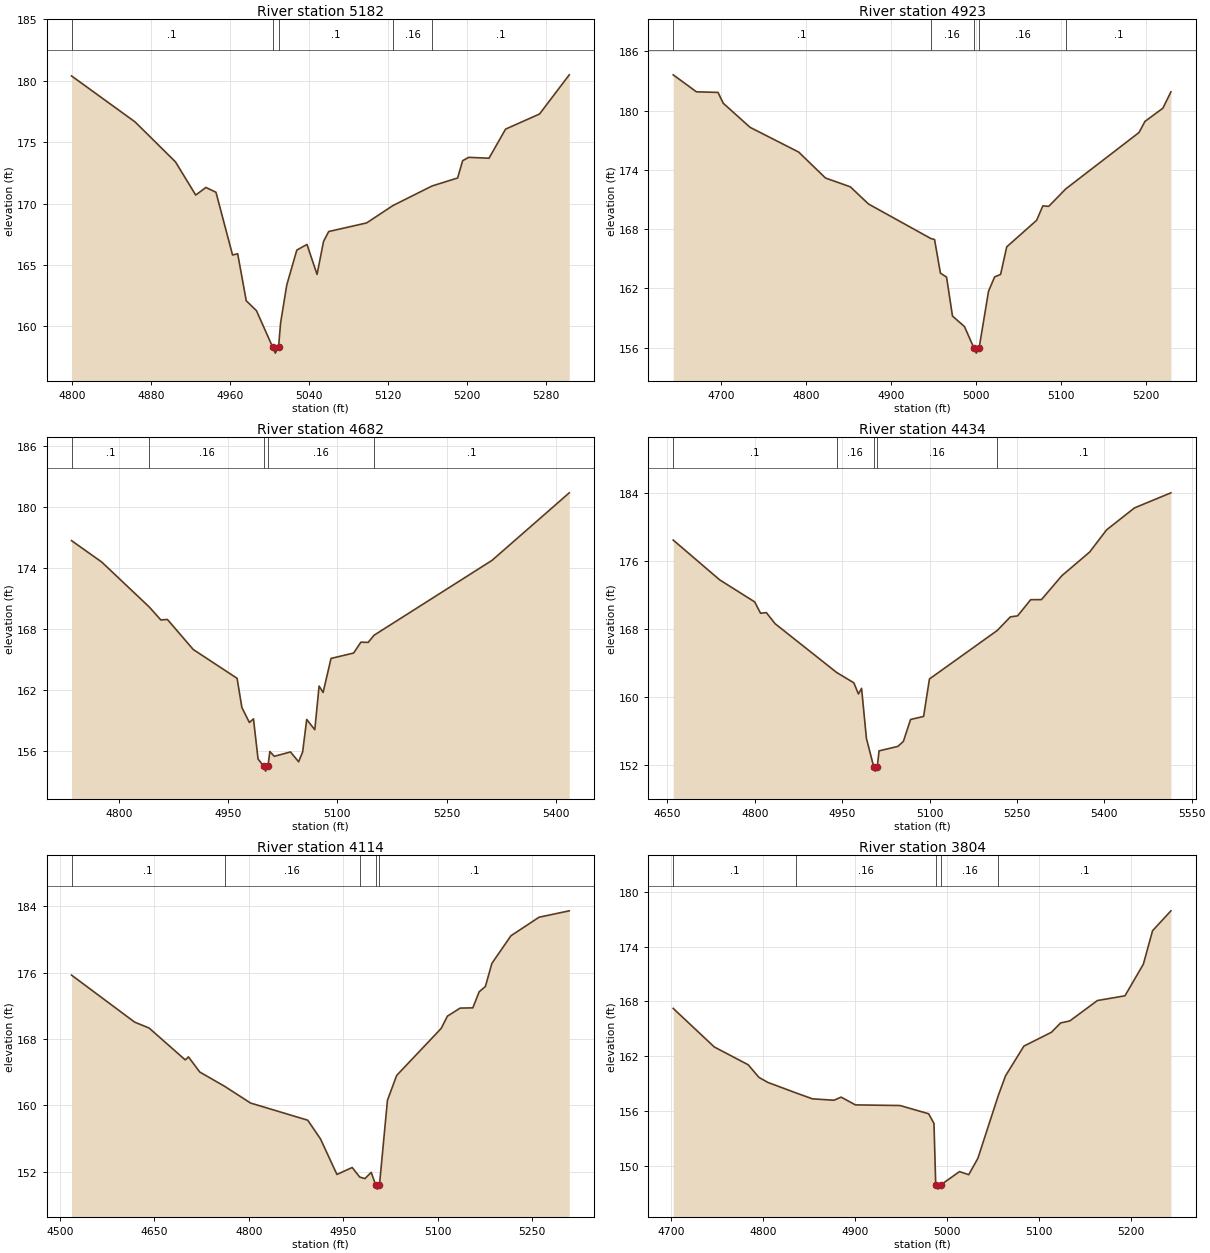
Type RM Length L Ch R = 1,5182,259,259,259
BEGIN DESCRIPTION:
UNT028 IN PECR 7.0
END DESCRIPTION:
XS GIS Cut Line= 2
      2301104.91     13188267.56      2301597.10     13188158.19
#Sta/Elev= 30
  4799.1  180.40  4863.4  176.66  4904.4  173.40  4924.9  170.70  4935.2  171.32
  4945.4  170.93  4962.2  165.82  4967.4  165.92  4976.1  162.09  4986.4  161.29
  5002.8  158.33  5005.5  157.83  5008.8  158.33  5010.9  160.30  5017.1  163.37
  5027.3  166.22  5037.6  166.68  5047.8  164.24  5054.4  166.93  5059.6  167.73
  5098.0  168.43  5124.8  169.85  5164.3  171.44  5190.2  172.09  5195.3  173.50
  5201.5  173.77  5222.0  173.70  5238.8  176.07  5273.2  177.30  5303.3  180.49
#Mann=5,-1,0
  4799.1     0.1       0  5002.8    0.07       0  5008.8     0.1       0
  5124.8    0.16       0  5164.3     0.1       0
Bank Sta=5002.8,5008.8
Exp/Cntr=0.3,0.1

Type RM Length L Ch R = 1,4923,241,241,241
BEGIN DESCRIPTION:
Mapping XS 74666bf0
END DESCRIPTION:
XS GIS Cut Line= 3
      2301221.85     13188548.23      2301396.67     13188489.96
      2301673.93     13188199.80
#Sta/Elev= 30
  4643.9  183.62  4671.2  181.90  4696.6  181.84  4702.8  180.74  4734.4  178.30
  4791.5  175.80  4823.1  173.17  4852.3  172.28  4873.7  170.54  4946.9  167.05
  4951.4  166.94  4958.3  163.54  4965.5  163.14  4972.5  159.19  4986.6  158.13
  4997.8  155.94  5000.5  155.44  5003.8  155.94  5014.9  161.71  5022.1  163.16
  5029.1  163.41  5036.3  166.20  5071.5  168.89  5078.8  170.35  5085.7  170.30
  5105.9  172.08  5192.0  177.78  5198.9  178.90  5220.0  180.24  5229.5  181.89
#Mann=5,-1,0
  4643.9     0.1       0  4946.9    0.16       0  4997.8    0.07       0
  5003.8    0.16       0  5105.9     0.1       0
Bank Sta=4997.8,5003.8
Exp/Cntr=0.3,0.1

Type RM Length L Ch R = 1,4682,248,248,248
BEGIN DESCRIPTION:
UNT028 IN PECR 6.0
END DESCRIPTION:
XS GIS Cut Line= 3
      2301447.60     13188651.16      2301788.75     13188484.49
      2301796.54     13188180.88
#Sta/Elev= 30
  4735.0  176.68  4776.5  174.57  4841.8  170.14  4857.6  168.87  4866.6  168.92
  4902.1  165.96  4962.3  163.12  4968.9  160.24  4979.2  158.77  4984.8  159.13
  4991.1  155.17  4998.7  154.48  5001.5  153.98  5004.7  154.48  5007.3  155.91
  5013.4  155.44  5035.6  155.87  5046.8  154.90  5052.3  155.87  5057.9  159.07
  5069.0  158.06  5074.9  162.36  5080.4  161.73  5091.3  165.08  5122.3  165.61
  5132.3  166.68  5142.3  166.66  5150.3  167.36  5312.4  174.74  5418.4  181.39
#Mann=5,-1,0
  4735.0     0.1       0  4841.8    0.16       0  4998.7    0.07       0
  5004.7    0.16       0  5150.3     0.1       0
Bank Sta=4998.7,5004.7
Exp/Cntr=0.3,0.1

Type RM Length L Ch R = 1,4434,320,320,320
BEGIN DESCRIPTION:
Mapping XS a175f647
END DESCRIPTION:
XS GIS Cut Line= 3
      2301467.94     13188813.78      2301642.78     13188807.30
      2302271.00     13188548.24
#Sta/Elev= 30
  4659.9  178.45  4739.7  173.77  4799.8  171.18  4809.8  169.85  4819.8  169.92
  4834.8  168.62  4940.6  162.88  4970.0  161.67  4977.9  160.36  4983.3  161.02
  4991.6  155.14  5004.2  151.79  5007.0  151.29  5010.2  151.79  5013.3  153.67
  5045.7  154.20  5055.1  154.79  5067.4  157.36  5089.8  157.72  5099.8  162.12
  5216.0  167.81  5238.8  169.42  5251.2  169.54  5273.6  171.44  5292.1  171.45
  5327.0  174.25  5374.7  177.03  5404.0  179.65  5451.9  182.23  5514.4  184.00
#Mann=5,-1,0
  4659.9     0.1       0  4940.6    0.16       0  5004.2    0.07       0
  5010.2    0.16       0  5216.0     0.1       0
Bank Sta=5004.2,5010.2
Exp/Cntr=0.3,0.1

Type RM Length L Ch R = 1,4114,310,310,310
BEGIN DESCRIPTION:
UNT028 IN PECR 5.0
END DESCRIPTION:
XS GIS Cut Line= 2
      2301525.72     13188908.97      2302309.60     13189007.93
#Sta/Elev= 30
  4518.7  175.71  4619.0  170.03  4641.7  169.33  4699.2  165.48  4704.3  165.84
  4722.3  164.01  4761.5  162.30  4802.9  160.27  4893.6  158.20  4913.8  155.95
  4940.0  151.65  4964.2  152.49  4976.1  151.34  4984.4  151.15  4994.4  151.90
  5001.5  150.38  5004.3  149.88  5007.5  150.38  5020.2  160.61  5034.8  163.60
  5105.5  169.28  5115.4  170.76  5135.6  171.73  5155.7  171.76  5165.8  173.70
  5175.6  174.33  5186.0  177.13  5216.2  180.46  5260.9  182.70  5308.8  183.47
#Mann=5,-1,0
  4518.7     0.1       0  4761.5    0.16       0  4976.1     0.1       0
  5001.5    0.07       0  5007.5     0.1       0
Bank Sta=5001.5,5007.5
Exp/Cntr=0.3,0.1

Type RM Length L Ch R = 1,3804,387,387,387
BEGIN DESCRIPTION:
UNT028 IN PECR 4.0
END DESCRIPTION:
XS GIS Cut Line= 3
      2301637.75     13189096.87      2301887.72     13189246.85
      2302137.71     13189246.85
#Sta/Elev= 30
  4702.0  167.24  4746.7  163.02  4783.6  161.07  4795.3  159.69  4805.0  159.14
  4835.9  157.98  4853.6  157.34  4876.9  157.19  4884.7  157.53  4900.2  156.68
  4948.8  156.61  4979.9  155.71  4985.7  154.65  4987.6  147.96  4990.3  147.46
  4993.6  147.96  5013.5  149.38  5023.5  149.04  5033.5  150.84  5055.7  157.71
  5063.5  159.85  5083.5  163.11  5113.5  164.63  5123.5  165.65  5133.5  165.87
  5163.5  168.10  5193.5  168.62  5213.5  172.08  5223.5  175.74  5243.5  177.92
#Mann=5,-1,0
  4702.0     0.1       0  4835.9    0.16       0  4987.6    0.07       0
  4993.6    0.16       0  5055.7     0.1       0
Bank Sta=4987.6,4993.6
Exp/Cntr=0.3,0.1

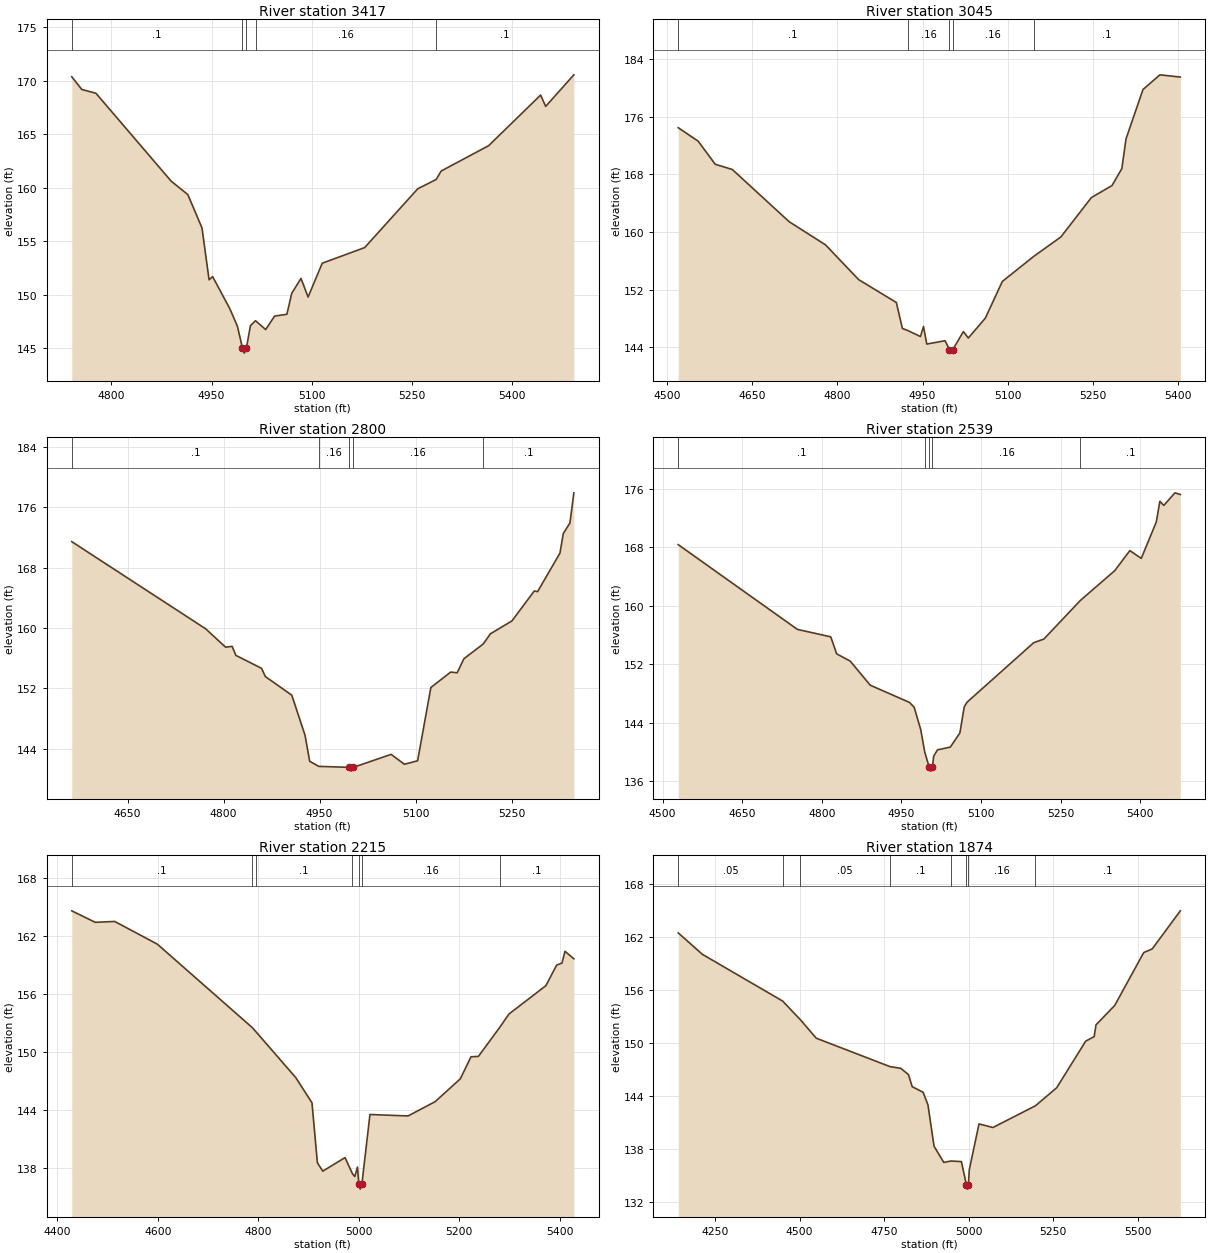
Type RM Length L Ch R = 1,3417,372,372,372
BEGIN DESCRIPTION:
UNT028 IN PECR 3.0
END DESCRIPTION:
XS GIS Cut Line= 3
      2301533.54     13189691.79      2301967.81     13189539.28
      2302187.73     13189346.85
#Sta/Elev= 30
  4740.5  170.36  4755.5  169.17  4776.7  168.82  4889.6  160.60  4914.5  159.35
  4935.7  156.23  4946.3  151.39  4951.6  151.69  4977.3  148.70  4988.7  147.06
  4996.3  145.04  4999.1  144.54  5002.3  145.04  5008.3  147.10  5015.9  147.57
  5031.1  146.74  5044.5  148.00  5062.9  148.17  5070.2  150.13  5084.1  151.52
  5094.7  149.78  5115.9  152.94  5179.5  154.40  5259.0  159.89  5286.8  160.77
  5294.1  161.55  5365.3  163.92  5443.2  168.65  5450.8  167.59  5493.0  170.54
#Mann=5,-1,0
  4740.5     0.1       0  4996.3    0.07       0  5002.3     0.1       0
  5015.9    0.16       0  5286.8     0.1       0
Bank Sta=4996.3,5002.3
Exp/Cntr=0.3,0.1

Type RM Length L Ch R = 1,3045,245,245,245
BEGIN DESCRIPTION:
Mapping XS 29f48feb
END DESCRIPTION:
XS GIS Cut Line= 3
      2301532.65     13189947.16      2301791.74     13189934.21
      2302373.67     13189707.90
#Sta/Elev= 30
  4520.0  174.47  4555.1  172.60  4585.2  169.39  4615.2  168.67  4715.3  161.42
  4779.4  158.20  4837.6  153.38  4903.9  150.21  4914.6  146.60  4924.3  146.31
  4946.4  145.48  4951.8  146.87  4957.5  144.44  4989.7  144.90  4997.4  143.68
  5000.2  143.18  5003.4  143.68  5021.9  146.17  5030.7  145.28  5060.6  148.04
  5090.5  153.13  5145.5  156.59  5193.6  159.31  5247.2  164.77  5283.6  166.44
  5300.9  168.80  5308.2  172.91  5338.1  179.77  5367.9  181.81  5403.8  181.50
#Mann=5,-1,0
  4520.0     0.1       0  4924.3    0.16       0  4997.4    0.07       0
  5003.4    0.16       0  5145.5     0.1       0
Bank Sta=4997.4,5003.4
Exp/Cntr=0.3,0.1

Type RM Length L Ch R = 1,2800,261,261,261
BEGIN DESCRIPTION:
UNT028 IN PECR 2.0
END DESCRIPTION:
XS GIS Cut Line= 3
      2301610.41     13190141.46      2301765.83     13190147.93
      2302373.65     13189986.28
#Sta/Elev= 30
  4562.8  171.43  4772.0  159.88  4803.1  157.45  4813.4  157.55  4819.2  156.36
  4859.4  154.64  4865.2  153.56  4906.6  151.08  4927.3  145.77  4934.5  142.33
  4948.7  141.65  4996.7  141.52  4999.4  141.02  5002.7  141.52  5061.8  143.24
  5082.5  141.93  5103.2  142.39  5123.9  152.10  5154.9  154.15  5165.0  154.05
  5175.6  155.92  5205.5  157.85  5217.0  159.22  5250.5  160.92  5285.5  164.89
  5290.7  164.81  5325.6  169.91  5330.8  172.50  5341.2  173.90  5347.3  177.90
#Mann=5,-1,0
  4562.8     0.1       0  4948.7    0.16       0  4996.7    0.07       0
  5002.7    0.16       0  5205.5     0.1       0
Bank Sta=4996.7,5002.7
Exp/Cntr=0.3,0.1

Type RM Length L Ch R = 1,2539,324,324,324
BEGIN DESCRIPTION:
Mapping XS e1c88803
END DESCRIPTION:
XS GIS Cut Line= 4
      2301629.87     13190355.19      2301837.07     13190406.99
      2302296.90     13190251.56      2302478.22     13190083.19
#Sta/Elev= 30
  4529.4  168.37  4754.0  156.78  4816.9  155.76  4828.1  153.43  4853.6  152.44
  4891.4  149.14  4965.3  146.79  4974.1  146.13  4986.5  143.07  4994.1  139.99
  5002.6  137.89  5005.3  137.39  5008.6  137.89  5010.8  139.42  5018.1  140.30
  5042.3  140.68  5060.3  142.61  5068.5  146.18  5073.7  146.81  5199.5  154.96
  5218.7  155.46  5287.3  160.73  5352.3  164.82  5380.7  167.56  5402.2  166.49
  5430.5  171.46  5437.3  174.30  5444.7  173.74  5465.7  175.46  5475.8  175.23
#Mann=5,-1,0
  4529.4     0.1       0  4994.1    0.16       0  5002.6    0.07       0
  5008.6    0.16       0  5287.3     0.1       0
Bank Sta=5002.6,5008.6
Exp/Cntr=0.3,0.1

Type RM Length L Ch R = 1,2215,341,341,341
BEGIN DESCRIPTION:
Mapping XS 573badcd
END DESCRIPTION:
XS GIS Cut Line= 4
      2301653.33     13190644.91      2301976.25     13190696.99
      2302293.96     13190577.20      2302408.55     13190264.68
#Sta/Elev= 30
  4428.9  164.61  4475.7  163.42  4514.4  163.51  4599.3  161.16  4787.6  152.56
  4795.6  152.10  4875.1  147.34  4907.1  144.75  4917.9  138.54  4928.6  137.68
  4972.8  139.08  4987.7  137.42  4992.3  137.12  4997.7  138.10  5000.4  136.32
  5003.1  135.82  5006.4  136.32  5022.5  143.54  5098.4  143.39  5152.3  144.87
  5202.4  147.23  5223.7  149.51  5238.4  149.55  5281.5  152.60  5299.4  153.94
  5372.8  156.87  5394.1  158.99  5404.8  159.21  5410.8  160.42  5428.4  159.65
#Mann=7,-1,0
  4428.9     0.1       0  4787.6    0.05       0  4795.6     0.1       0
  4987.7    0.16       0  5000.4    0.07       0  5006.4    0.16       0
  5281.5     0.1       0
Bank Sta=5000.4,5006.4
Exp/Cntr=0.3,0.1

Type RM Length L Ch R = 1,1874,424,424,424
BEGIN DESCRIPTION:
Mapping XS 6c274a22
END DESCRIPTION:
XS GIS Cut Line= 4
      2301577.99     13190750.24      2302141.47     13190866.82
      2302581.86     13190672.53      2302730.67     13190271.40
#Sta/Elev= 30
  4141.3  162.50  4212.5  160.07  4450.2  154.76  4502.4  152.65  4549.5  150.55
  4768.0  147.32  4799.0  147.14  4821.9  146.43  4833.2  145.05  4865.6  144.41
  4879.8  142.97  4897.7  138.30  4926.5  136.46  4948.3  136.62  4978.6  136.55
  4993.4  133.93  4996.2  133.43  4999.4  133.93  5001.9  135.62  5030.7  140.83
  5071.8  140.42  5197.4  142.88  5260.4  144.93  5346.2  150.22  5371.2  150.73
  5376.6  152.06  5432.0  154.27  5517.8  160.27  5542.8  160.68  5625.9  165.00
#Mann=8,-1,0
  4141.3    0.05       0  4450.2     0.1       0  4502.4    0.05       0
  4768.0     0.1       0  4948.3    0.16       0  4993.4    0.07       0
  4999.4    0.16       0  5197.4     0.1       0
Bank Sta=4993.4,4999.4
Exp/Cntr=0.3,0.1

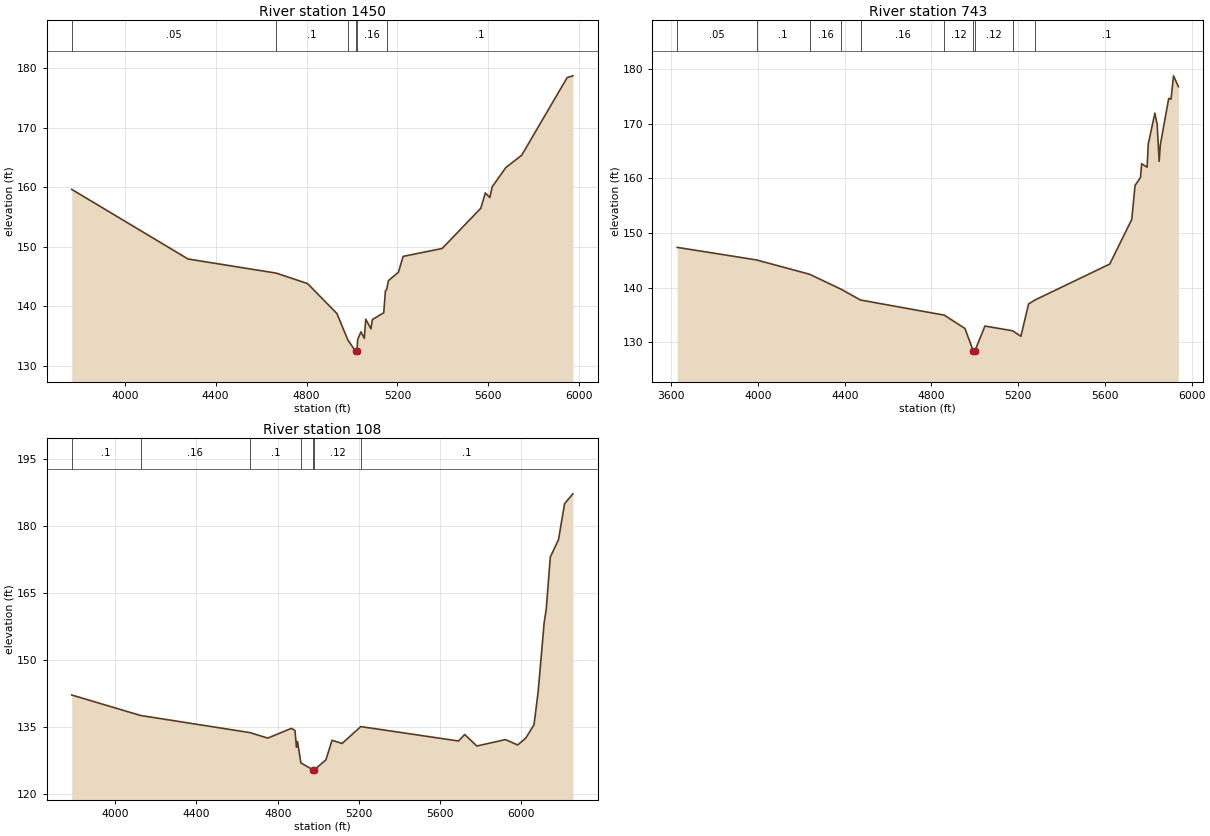
Type RM Length L Ch R = 1,1450,707,707,707
BEGIN DESCRIPTION:
Mapping XS 37f4d047
END DESCRIPTION:
XS GIS Cut Line= 4
      2301564.80     13190822.00      2302580.42     13191014.70
      2303017.53     13190686.42      2303002.30     13190061.70
#Sta/Elev= 30
  3766.7  159.63  4278.6  147.92  4666.2  145.55  4804.2  143.79  4933.4  138.76
  4982.4  134.25  5015.8  132.42  5018.5  131.92  5021.8  132.42  5025.0  134.40
  5039.6  135.67  5054.2  134.58  5060.5  137.80  5083.4  136.18  5089.6  137.73
  5139.6  138.88  5147.2  142.60  5152.2  142.76  5160.4  144.28  5204.2  145.69
  5225.0  148.36  5396.7  149.69  5566.7  156.46  5586.7  159.03  5606.7  158.25
  5616.7  160.05  5676.8  163.30  5746.8  165.38  5946.8  178.44  5972.0  178.73
#Mann=6,-1,0
  3766.7    0.05       0  4666.2     0.1       0  4982.4    0.16       0
  5015.8    0.07       0  5021.8    0.16       0  5152.2     0.1       0
Bank Sta=5015.8,5021.8
Exp/Cntr=0.3,0.1

Type RM Length L Ch R = 1,743,635,635,635
BEGIN DESCRIPTION:
Mapping XS 1a19c532
END DESCRIPTION:
XS GIS Cut Line= 4
      2302090.82     13191009.49      2303184.58     13191196.99
      2303533.54     13190712.62      2303741.87     13190144.94
#Sta/Elev= 30
  3627.5  147.40  3993.3  145.10  4238.0  142.48  4383.8  139.73  4472.9  137.77
  4859.1  135.00  4954.7  132.56  4993.5  128.37  4996.3  127.87  4999.5  128.37
  5046.8  133.01  5175.3  132.13  5212.5  131.13  5248.1  137.05  5276.9  137.76
  5622.4  144.35  5723.8  152.51  5739.0  158.73  5764.2  160.19  5769.5  162.70
  5794.6  162.06  5800.0  166.29  5830.5  171.96  5841.0  169.90  5850.3  163.14
  5855.6  166.14  5894.2  174.64  5904.9  174.52  5916.6  178.78  5938.9  176.79
#Mann=10,-1,0
  3627.5    0.05       0  3993.3     0.1       0  4238.0    0.16       0
  4383.8     0.1       0  4472.9    0.16       0  4859.1    0.12       0
  4993.5    0.07       0  4999.5    0.12       0  5175.3    0.16       0
  5276.9     0.1       0
Bank Sta=4993.5,4999.5
Exp/Cntr=0.3,0.1

Type RM Length L Ch R = 1,108,0,0,0
BEGIN DESCRIPTION:
UNT028 IN PECR 1.0
END DESCRIPTION:
XS GIS Cut Line= 4
      2302520.34     13191229.63      2303559.58     13191363.66
      2303890.74     13191237.21      2303991.88     13190176.14
#Sta/Elev= 30
  3785.6  142.11  4124.6  137.52  4663.5  133.68  4750.9  132.45  4867.7  134.64
  4885.0  134.15  4892.5  130.40  4897.8  131.67  4913.9  126.91  4974.3  125.33
  4977.1  124.83  4980.3  125.33  5037.5  127.59  5067.5  131.97  5117.0  131.25
  5209.4  135.03  5690.5  131.80  5720.7  133.26  5781.0  130.68  5921.6  132.12
  5981.9  130.91  6022.0  132.48  6062.2  135.43  6082.3  142.68  6112.4  158.37
  6122.5  161.35  6142.6  173.02  6182.8  176.89  6212.9  184.97  6253.8  187.17
#Mann=7,-1,0
  3785.6     0.1       0  4124.6    0.16       0  4663.5     0.1       0
  4913.9    0.12       0  4974.3    0.07       0  4980.3    0.12       0
  5209.4     0.1       0
Bank Sta=4974.3,4980.3
Exp/Cntr=0.3,0.1

Chan Stop Cuts=-1