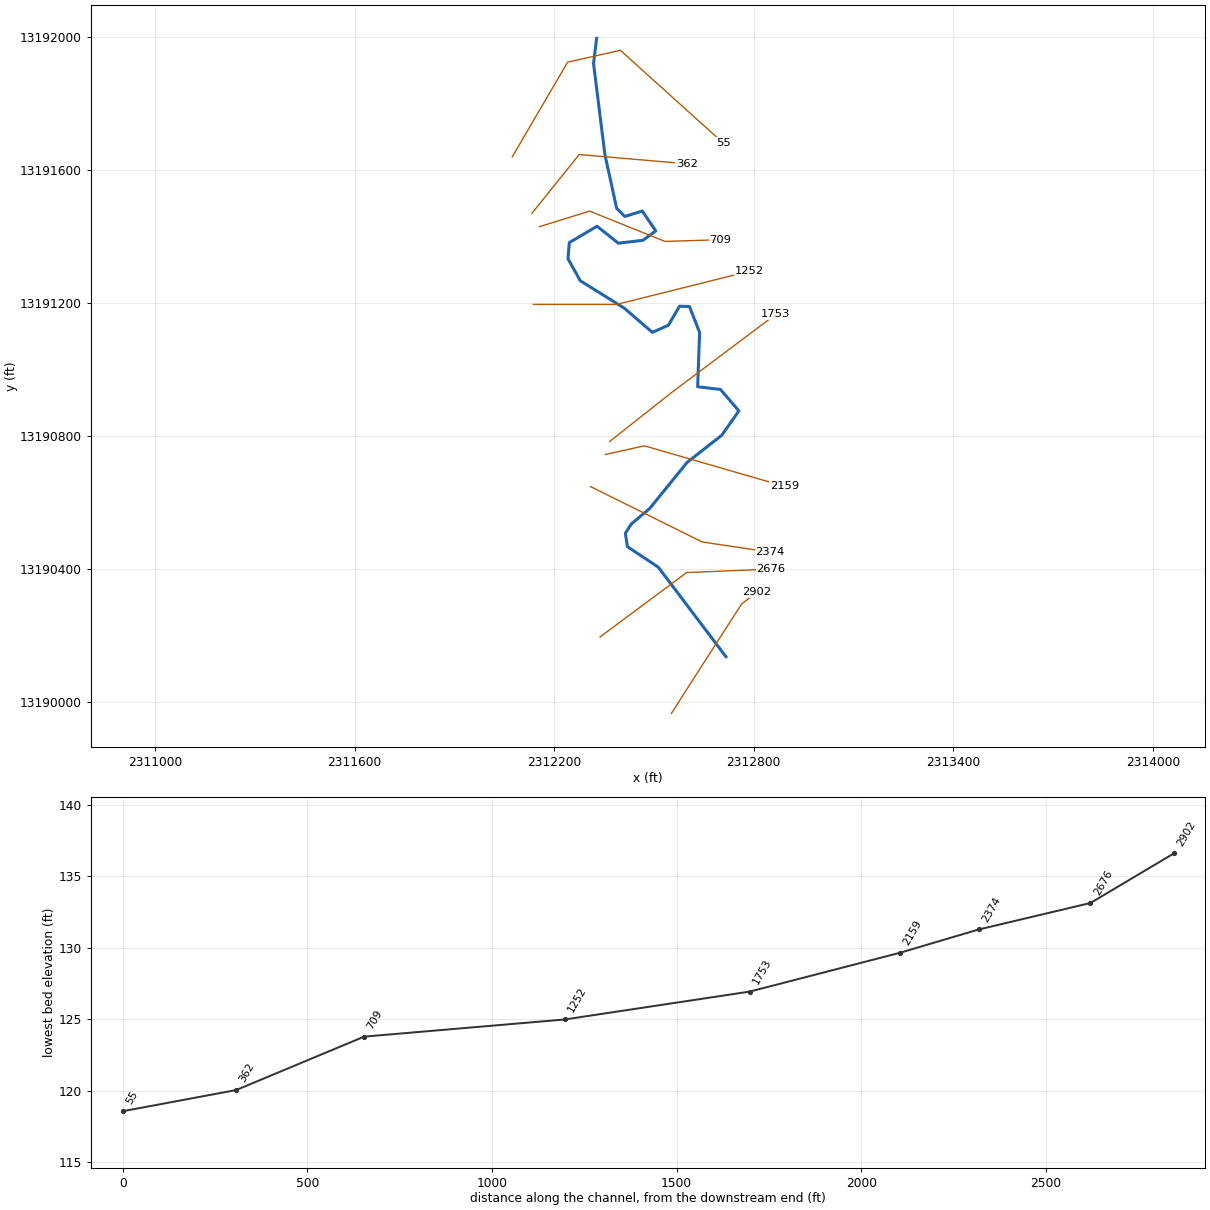
--- UNT030 IN PECR.prj (project) ---

Proj Title=UNT030 IN PECR Base Level Engineering
Current Plan=p01
Default Exp/Contr=0.3,0.1
English Units
Geom File=g01
Flow File=f01
Plan File=p01
Y Axis Title=Elevation
X Axis Title(PF)=Main Channel Distance
X Axis Title(XS)=Station
BEGIN DESCRIPTION:
UNT030 IN PECR
END DESCRIPTION:
DSS Export Rating Curves= 0
DSS Export Rating Curve Sorted= 0
DSS Export Volume Flow Curves= 0
DXF OffsetX= 0
DXF OffsetY= 0
DXF ScaleX= 1
DXF ScaleY= 10

--- UNT030 IN PECR.p01 (plan) ---

Plan Title=Multiple Run
Short Identifier=Multiple
Geom File=g01
Flow File=f01
Subcritical Flow
K Sum by GR= 0
Std Step Tol= 0.01
Critical Tol= 0.01
Num of Std Step Trials= 20
Max Error Tol= 0.3
Flow Tol Ratio= 0.001
Split Flow NTrial= 30
Split Flow Tol= 0.02
Split Flow Ratio= 0.02
Log Output Level= 0
Friction Slope Method= 1
Unsteady Friction Slope Method= 2
Unsteady Bridges Friction Slope Method= 1
Parabolic Critical Depth
Global Vel Dist=  1 , 1 , 1
Global Log Level= 0
CheckData=True
Encroach Param= -1, 0, 0, 0
BEGIN DESCRIPTION:
Multiple Run
END DESCRIPTION:

--- UNT030 IN PECR.f01 (steady flow) ---

Flow Title=Multiple
Program Version=4.10
Number of Profiles= 7
Profile Names=10-year,25-year,50-year,1pct_min,100-year,1pct_plu,500-year
River Rch & RM=UNT030 IN PECR,Reach-1         ,2902
     480     666     819     736     995    1346    1477
Boundary for River Rch & Prof#=UNT030 IN PECR,Reach-1         , 1
Up Type= 0
Dn Type= 3
Dn Slope=0.005
Boundary for River Rch & Prof#=UNT030 IN PECR,Reach-1         , 2
Up Type= 0
Dn Type= 3
Dn Slope=0.005
Boundary for River Rch & Prof#=UNT030 IN PECR,Reach-1         , 3
Up Type= 0
Dn Type= 3
Dn Slope=0.005
Boundary for River Rch & Prof#=UNT030 IN PECR,Reach-1         , 4
Up Type= 0
Dn Type= 3
Dn Slope=0.005
Boundary for River Rch & Prof#=UNT030 IN PECR,Reach-1         , 5
Up Type= 0
Dn Type= 3
Dn Slope=0.005
Boundary for River Rch & Prof#=UNT030 IN PECR,Reach-1         , 6
Up Type= 0
Dn Type= 3
Dn Slope=0.005
Boundary for River Rch & Prof#=UNT030 IN PECR,Reach-1         , 7
Up Type= 0
Dn Type= 3
Dn Slope=0.005
DSS Import GetInterval= 0
DSS Import GetPeak= 0
DSS Import FillOption= 0

--- UNT030 IN PECR.g01 (geometry) ---

Geom Title=Existing Conditions

River Reach=UNT030 IN PECR,Reach-1
Reach XY= 30
      2312716.39     13190137.58      2312513.02     13190406.85
      2312420.14     13190468.48      2312414.06     13190508.41
      2312431.42     13190536.19      2312486.98     13190583.07
      2312599.82     13190721.96      2312704.08     13190803.57
      2312755.38     13190876.70      2312700.06     13190941.16
      2312631.37     13190949.26      2312637.27     13191112.50
      2312606.82     13191190.51      2312576.78     13191191.42
      2312543.49     13191134.32      2312495.17     13191112.83
      2312410.81     13191185.57      2312278.52     13191267.92
      2312241.55     13191334.27      2312245.43     13191382.54
      2312328.82     13191431.91      2312392.74     13191381.00
      2312467.09     13191389.59      2312505.53     13191417.87
      2312464.78     13191477.61      2312412.45     13191461.19
      2312387.83     13191485.98      2312352.43     13191647.82
      2312318.30     13191921.17      2312327.72     13191996.86

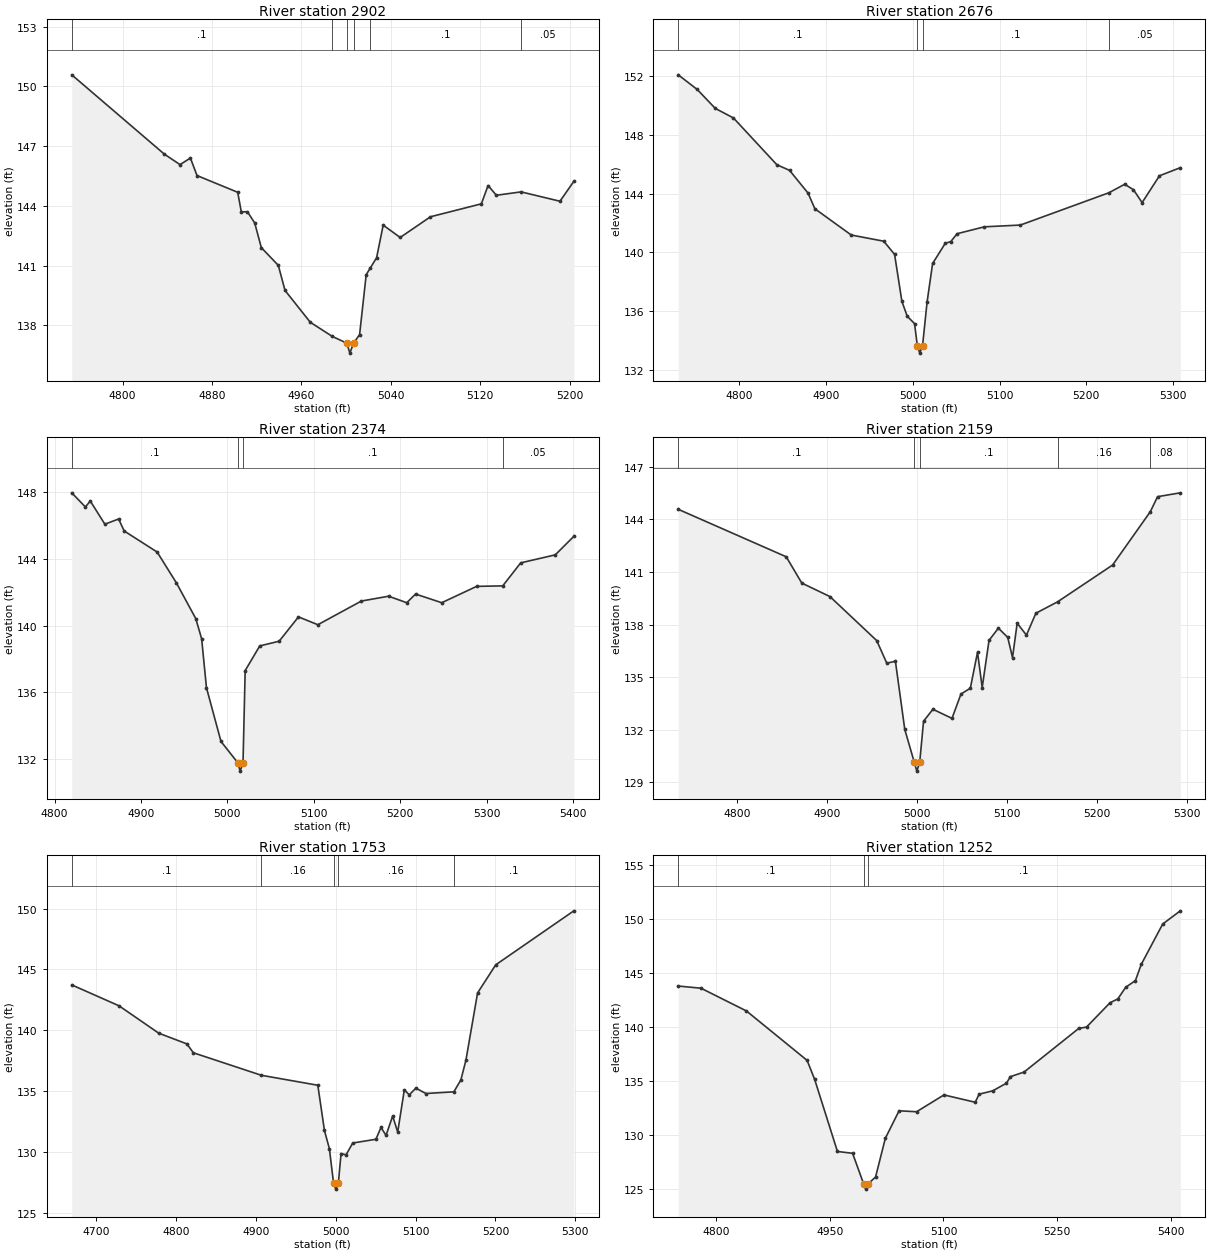
Type RM Length L Ch R = 1,2902,226,226,226
BEGIN DESCRIPTION:
Mapping XS 5a3a6179
END DESCRIPTION:
XS GIS Cut Line= 4
      2312552.55     13189967.21      2312635.66     13190097.21
      2312763.52     13190296.10      2312809.70     13190331.62
#Sta/Elev= 30
  4754.6  150.58  4837.3  146.60  4851.4  146.07  4860.7  146.40  4866.6  145.52
  4903.0  144.68  4906.2  143.70  4911.7  143.70  4918.2  143.14  4924.1  141.90
  4939.3  141.01  4945.3  139.75  4967.9  138.15  4987.6  137.44  5000.6  137.10
  5003.3  136.60  5006.6  137.10  5012.0  137.53  5017.9  140.54  5021.6  140.88
  5027.2  141.39  5033.1  143.03  5048.3  142.41  5075.4  143.45  5120.9  144.10
  5126.9  145.02  5134.3  144.53  5156.4  144.70  5191.2  144.23  5203.6  145.23
#Mann=6,-1,0
  4754.6     0.1       0  4987.6    0.05       0  5000.6    0.04       0
  5006.6    0.05       0  5021.6     0.1       0  5156.4    0.05       0
Bank Sta=5000.6,5006.6
Exp/Cntr=0.3,0.1

Type RM Length L Ch R = 1,2676,302,302,302
BEGIN DESCRIPTION:
UNT030 IN PECR 5.0
END DESCRIPTION:
XS GIS Cut Line= 3
      2312337.75     13190196.88      2312598.21     13190390.56
      2312851.72     13190400.98
#Sta/Elev= 30
  4729.9  152.10  4751.8  151.10  4772.6  149.81  4793.5  149.16  4843.5  145.97
  4858.1  145.59  4879.4  144.04  4887.3  142.97  4929.2  141.18  4966.6  140.76
  4979.1  139.86  4987.5  136.66  4993.7  135.64  5002.1  135.14  5005.3  133.63
  5008.1  133.13  5011.3  133.63  5016.5  136.60  5022.9  139.24  5037.5  140.62
  5043.8  140.73  5051.1  141.27  5082.5  141.74  5124.0  141.86  5225.9  144.06
  5244.1  144.64  5254.2  144.27  5264.2  143.39  5284.2  145.22  5308.2  145.77
#Mann=4,-1,0
  4729.9     0.1       0  5005.3    0.07       0  5011.3     0.1       0
  5225.9    0.05       0
Bank Sta=5005.3,5011.3
Exp/Cntr=0.3,0.1

Type RM Length L Ch R = 1,2374,215,215,215
BEGIN DESCRIPTION:
UNT030 IN PECR 4.0
END DESCRIPTION:
XS GIS Cut Line= 3
      2312309.18     13190649.22      2312645.09     13190482.57
      2312848.95     13190452.08
#Sta/Elev= 30
  4819.9  147.97  4835.7  147.12  4841.3  147.48  4858.2  146.09  4874.1  146.40
  4880.6  145.68  4918.7  144.42  4941.1  142.56  4963.4  140.43  4970.2  139.22
  4975.8  136.28  4992.6  133.06  5012.1  131.78  5014.8  131.28  5018.1  131.78
  5020.6  137.31  5037.5  138.79  5059.9  139.07  5082.3  140.53  5104.7  140.06
  5155.1  141.48  5186.6  141.77  5207.6  141.38  5217.8  141.90  5248.1  141.38
  5288.5  142.36  5318.7  142.39  5339.5  143.77  5379.5  144.25  5401.0  145.36
#Mann=4,-1,0
  4819.9     0.1       0  5012.1    0.07       0  5018.1     0.1       0
  5318.7    0.05       0
Bank Sta=5012.1,5018.1
Exp/Cntr=0.3,0.1

Type RM Length L Ch R = 1,2159,406,406,406
BEGIN DESCRIPTION:
Mapping XS 821aeee1
END DESCRIPTION:
XS GIS Cut Line= 3
      2312353.82     13190745.60      2312471.02     13190771.64
      2312892.07     13190650.10
#Sta/Elev= 30
  4734.8  144.58  4854.9  141.87  4872.2  140.37  4903.5  139.60  4955.5  137.09
  4966.7  135.80  4976.3  135.91  4986.7  132.02  4997.3  130.14  5000.1  129.64
  5003.3  130.14  5007.6  132.49  5018.0  133.17  5039.2  132.65  5049.2  134.04
  5059.6  134.37  5067.6  136.42  5072.8  134.41  5080.4  137.10  5090.8  137.80
  5101.2  137.27  5106.5  136.12  5111.7  138.08  5122.0  137.40  5132.5  138.65
  5156.6  139.30  5217.8  141.40  5259.7  144.44  5267.8  145.30  5293.1  145.52
#Mann=5,-1,0
  4734.8     0.1       0  4997.3    0.07       0  5003.3     0.1       0
  5156.6    0.16       0  5259.7    0.08       0
Bank Sta=4997.3,5003.3
Exp/Cntr=0.3,0.1

Type RM Length L Ch R = 1,1753,501,501,501
BEGIN DESCRIPTION:
UNT030 IN PECR 3.0
END DESCRIPTION:
XS GIS Cut Line= 3
      2312366.86     13190784.67      2312553.49     13190932.23
      2312865.96     13191166.58
#Sta/Elev= 30
  4669.7  143.72  4728.9  142.00  4778.6  139.75  4813.8  138.87  4821.9  138.14
  4907.0  136.29  4977.7  135.47  4986.0  131.75  4992.2  130.25  4997.4  127.43
  5000.2  126.93  5003.4  127.43  5006.8  129.85  5013.1  129.75  5021.4  130.72
  5050.4  131.03  5056.8  132.00  5063.1  131.35  5071.4  132.94  5077.7  131.62
  5086.0  135.09  5092.2  134.68  5100.4  135.23  5113.1  134.79  5148.0  134.93
  5156.8  135.91  5163.1  137.53  5177.7  143.06  5200.4  145.37  5298.2  149.81
#Mann=5,-1,0
  4669.7     0.1       0  4907.0    0.16       0  4997.4    0.07       0
  5003.4    0.16       0  5148.0     0.1       0
Bank Sta=4997.4,5003.4
Exp/Cntr=0.3,0.1

Type RM Length L Ch R = 1,1252,543,543,543
BEGIN DESCRIPTION:
UNT030 IN PECR 2.0
END DESCRIPTION:
XS GIS Cut Line= 3
      2312137.70     13191196.85      2312387.72     13191196.85
      2312787.69     13191296.85
#Sta/Elev= 30
  4750.1  143.80  4780.1  143.60  4840.1  141.49  4920.1  136.91  4930.1  135.14
  4960.1  128.47  4980.1  128.30  4994.6  125.48  4997.4  124.98  5000.6  125.48
  5010.4  126.10  5023.3  129.69  5041.4  132.24  5064.5  132.15  5100.6  133.71
  5141.9  133.03  5147.0  133.78  5165.0  134.09  5183.1  134.80  5188.2  135.40
  5206.3  135.83  5278.4  139.87  5288.7  140.00  5319.7  142.25  5330.0  142.61
  5340.3  143.68  5353.2  144.31  5360.9  145.81  5389.2  149.55  5412.4  150.77
#Mann=3,-1,0
  4750.1     0.1       0  4994.6    0.07       0  5000.6     0.1       0
Bank Sta=4994.6,5000.6
Exp/Cntr=0.3,0.1

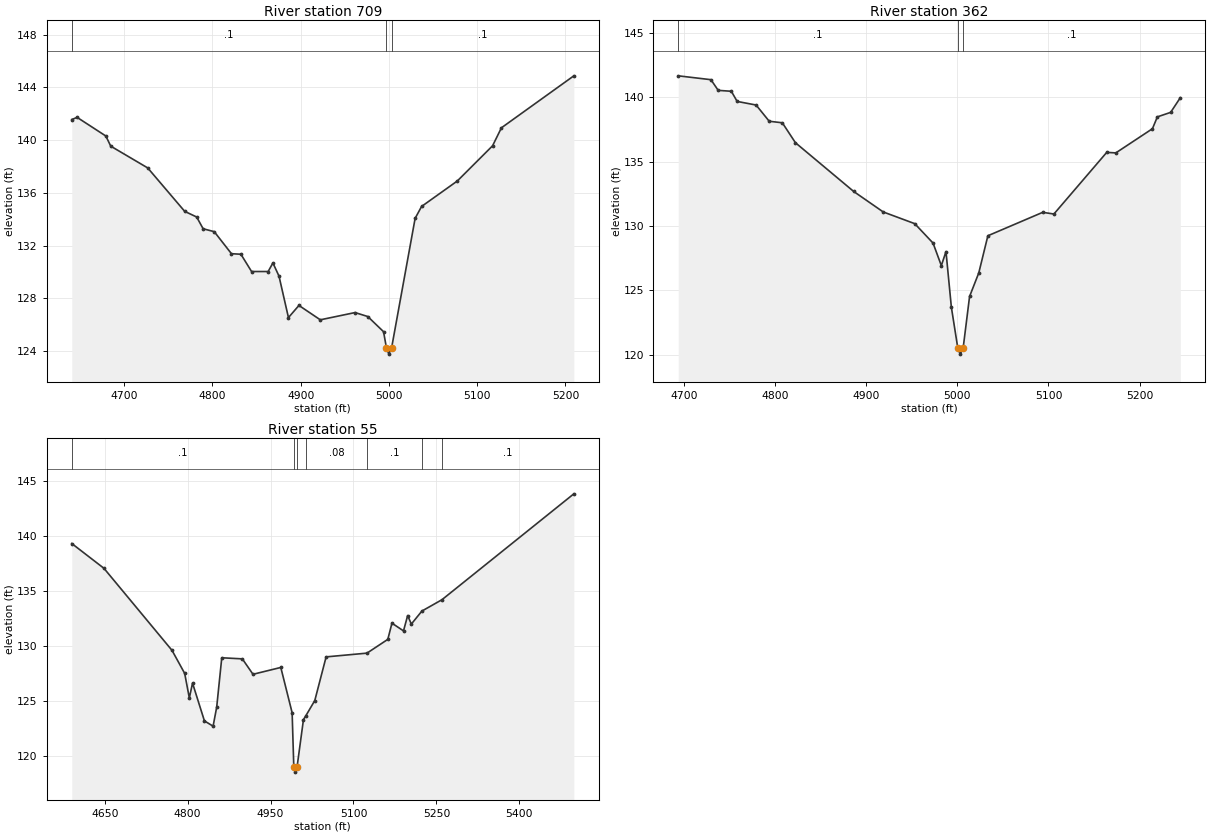
Type RM Length L Ch R = 1,709,347,347,347
BEGIN DESCRIPTION:
Mapping XS f582d143
END DESCRIPTION:
XS GIS Cut Line= 4
      2312155.52     13191430.49      2312306.55     13191477.37
      2312533.11     13191386.22      2312699.78     13191391.43
#Sta/Elev= 30
  4640.5  141.56  4646.6  141.72  4679.1  140.31  4684.7  139.54  4726.6  137.89
  4768.5  134.60  4782.1  134.17  4789.4  133.28  4802.0  133.06  4821.5  131.39
  4832.2  131.35  4844.3  130.04  4863.1  130.04  4868.5  130.69  4875.4  129.69
  4886.1  126.55  4898.0  127.47  4922.2  126.38  4961.6  126.93  4976.0  126.63
  4993.9  125.48  4997.1  124.28  4999.9  123.78  5003.1  124.28  5029.7  134.07
  5037.0  134.97  5077.5  136.90  5117.5  139.57  5127.5  140.93  5209.6  144.87
#Mann=3,-1,0
  4640.5     0.1       0  4997.1    0.07       0  5003.1     0.1       0
Bank Sta=4997.1,5003.1
Exp/Cntr=0.3,0.1

Type RM Length L Ch R = 1,362,307,307,307
BEGIN DESCRIPTION:
Mapping XS a1dde576
END DESCRIPTION:
XS GIS Cut Line= 3
      2312132.96     13191470.45      2312275.30     13191647.50
      2312598.23     13191619.72
#Sta/Elev= 30
  4693.5  141.67  4729.4  141.37  4737.4  140.54  4751.8  140.47  4758.2  139.68
  4779.0  139.40  4793.4  138.14  4807.8  138.02  4822.2  136.47  4886.2  132.68
  4918.6  131.09  4953.2  130.18  4973.3  128.67  4982.4  126.92  4987.5  128.01
  4993.4  123.69  5000.4  120.54  5003.1  120.04  5006.4  120.54  5013.4  124.52
  5023.5  126.35  5033.5  129.24  5093.7  131.06  5106.0  130.93  5164.0  135.72
  5174.0  135.68  5214.2  137.56  5219.6  138.48  5234.2  138.83  5244.8  139.97
#Mann=3,-1,0
  4693.5     0.1       0  5000.4    0.07       0  5006.4     0.1       0
Bank Sta=5000.4,5006.4
Exp/Cntr=0.3,0.1

Type RM Length L Ch R = 1,55,0,0,0
BEGIN DESCRIPTION:
UNT030 IN PECR 1.0
END DESCRIPTION:
XS GIS Cut Line= 4
      2312073.90     13191640.56      2312240.57     13191925.28
      2312398.95     13191960.91      2312708.04     13191682.26
#Sta/Elev= 30
  4590.3  139.31  4648.5  137.06  4771.7  129.61  4794.6  127.52  4803.0  125.29
  4808.8  126.64  4830.3  123.21  4846.0  122.73  4852.5  124.45  4861.7  128.94
  4898.9  128.84  4918.2  127.44  4968.5  128.06  4989.0  123.95  4992.0  119.06
  4994.7  118.56  4998.0  119.06  5009.5  123.33  5013.5  123.65  5030.0  125.06
  5050.5  129.02  5124.4  129.36  5162.1  130.61  5169.6  132.08  5190.5  131.38
  5198.0  132.77  5204.7  132.00  5223.8  133.18  5260.1  134.21  5498.7  143.82
#Mann=7,-1,0
  4590.3     0.1       0  4992.0    0.07       0  4998.0     0.1       0
  5013.5    0.08       0  5124.4     0.1       0  5223.8    0.08       0
  5260.1     0.1       0
Bank Sta=4992,4998
Exp/Cntr=0.3,0.1

Chan Stop Cuts=-1