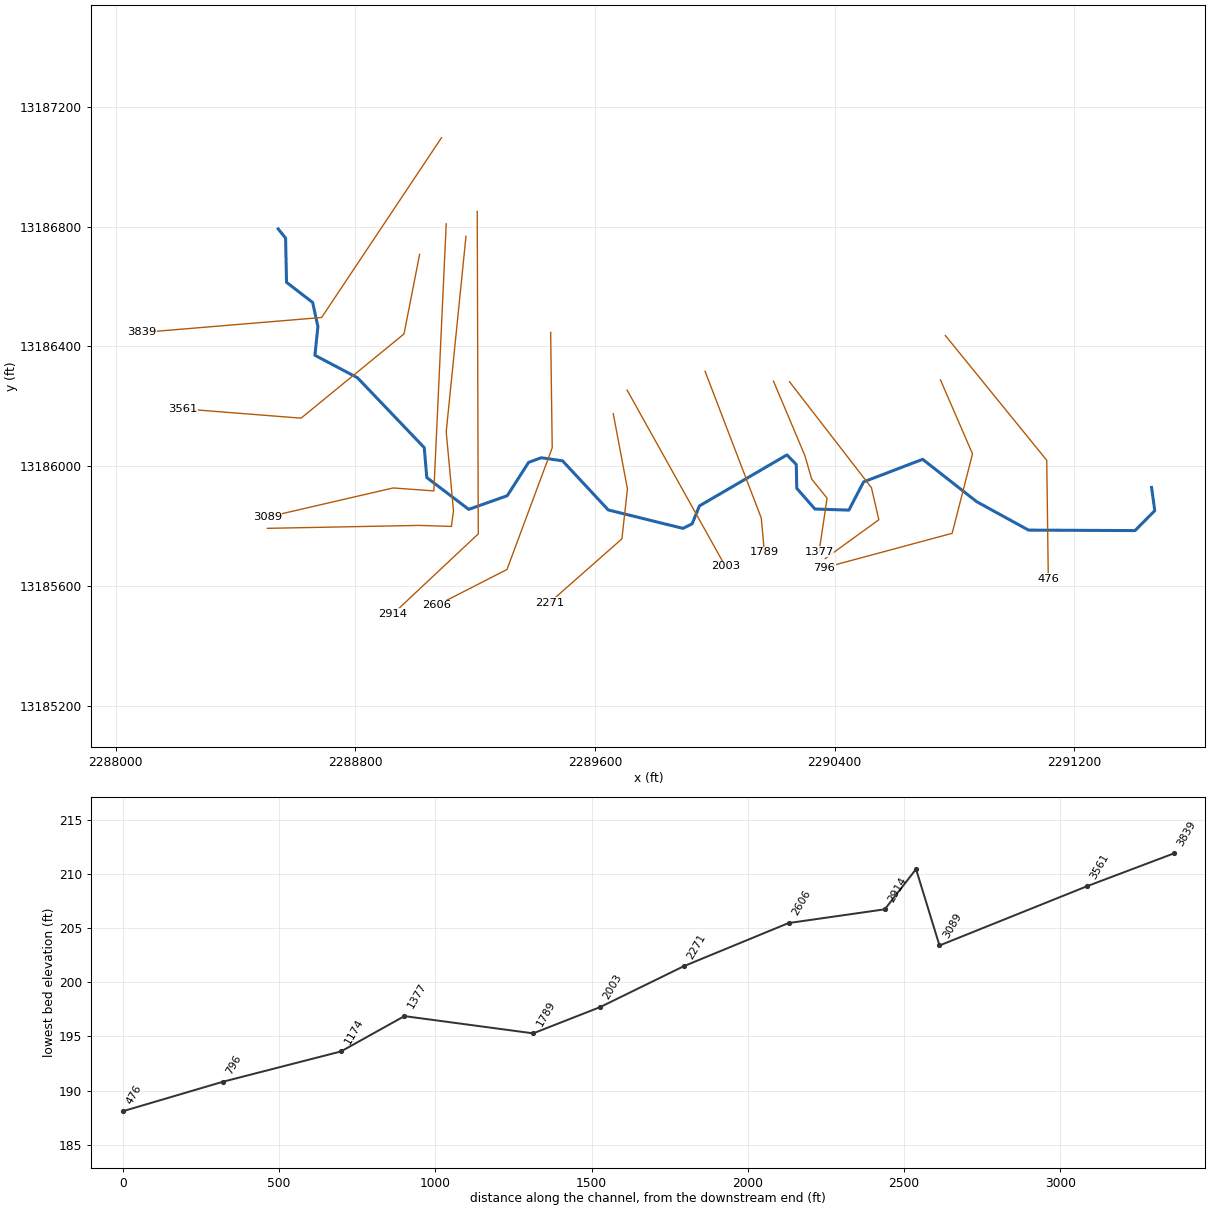
--- UNT072 IN PECR.prj (project) ---

Proj Title=UNT072 IN PECR Base Level Engineering
Current Plan=p01
Default Exp/Contr=0.3,0.1
English Units
Geom File=g01
Flow File=f01
Plan File=p01
Y Axis Title=Elevation
X Axis Title(PF)=Main Channel Distance
X Axis Title(XS)=Station
BEGIN DESCRIPTION:
UNT072 IN PECR
END DESCRIPTION:
DSS Export Rating Curves= 0
DSS Export Rating Curve Sorted= 0
DSS Export Volume Flow Curves= 0
DXF OffsetX= 0
DXF OffsetY= 0
DXF ScaleX= 1
DXF ScaleY= 10

--- UNT072 IN PECR.p01 (plan) ---

Plan Title=Multiple Run
Short Identifier=Multiple
Geom File=g01
Flow File=f01
Subcritical Flow
K Sum by GR= 0
Std Step Tol= 0.01
Critical Tol= 0.01
Num of Std Step Trials= 20
Max Error Tol= 0.3
Flow Tol Ratio= 0.001
Split Flow NTrial= 30
Split Flow Tol= 0.02
Split Flow Ratio= 0.02
Log Output Level= 0
Friction Slope Method= 1
Unsteady Friction Slope Method= 2
Unsteady Bridges Friction Slope Method= 1
Parabolic Critical Depth
Global Vel Dist=  1 , 1 , 1
Global Log Level= 0
CheckData=True
Encroach Param= -1, 0, 0, 0
BEGIN DESCRIPTION:
Multiple Run
END DESCRIPTION:

--- UNT072 IN PECR.f01 (steady flow) ---

Flow Title=Multiple
Program Version=4.10
Number of Profiles= 7
Profile Names=10-year,25-year,50-year,1pct_min,100-year,1pct_plu,500-year
River Rch & RM=UNT072 IN PECR,Reach-1         ,3839
     160     214     258     229     310     419     452
Boundary for River Rch & Prof#=UNT072 IN PECR,Reach-1         , 1
Up Type= 0
Dn Type= 3
Dn Slope=0.0086
Boundary for River Rch & Prof#=UNT072 IN PECR,Reach-1         , 2
Up Type= 0
Dn Type= 3
Dn Slope=0.0086
Boundary for River Rch & Prof#=UNT072 IN PECR,Reach-1         , 3
Up Type= 0
Dn Type= 3
Dn Slope=0.0086
Boundary for River Rch & Prof#=UNT072 IN PECR,Reach-1         , 4
Up Type= 0
Dn Type= 3
Dn Slope=0.0086
Boundary for River Rch & Prof#=UNT072 IN PECR,Reach-1         , 5
Up Type= 0
Dn Type= 3
Dn Slope=0.0086
Boundary for River Rch & Prof#=UNT072 IN PECR,Reach-1         , 6
Up Type= 0
Dn Type= 3
Dn Slope=0.0086
Boundary for River Rch & Prof#=UNT072 IN PECR,Reach-1         , 7
Up Type= 0
Dn Type= 3
Dn Slope=0.0086
DSS Import GetInterval= 0
DSS Import GetPeak= 0
DSS Import FillOption= 0

--- UNT072 IN PECR.g01 (geometry) ---

Geom Title=Existing Conditions
Program Version=4.10

River Reach=UNT072 IN PECR  ,Reach-1
Reach XY= 30
      2288542.73     13186792.61      2288567.35     13186761.78
      2288570.48     13186614.32       2288657.6     13186547.14
      2288675.21      13186466.9      2288665.35     13186370.63
      2288807.26     13186295.74      2289030.26     13186062.34
      2289038.82     13185962.43      2289178.77     13185856.23
      2289307.43     13185901.83      2289378.86     13186013.36
      2289421.22     13186028.63      2289492.05     13186018.22
      2289644.55     13185854.36      2289894.21     13185792.69
      2289924.81     13185808.14        2289949.     13185867.79
      2290241.18     13186038.11      2290272.38     13186006.16
        2290274.     13185926.65      2290334.41     13185857.38
      2290447.95     13185853.73      2290497.08     13185947.99
      2290694.27     13186023.33      2290874.99     13185881.65
      2291047.79     13185786.98      2291403.33      13185785.4
      2291469.24     13185851.95      2291458.47     13185929.45

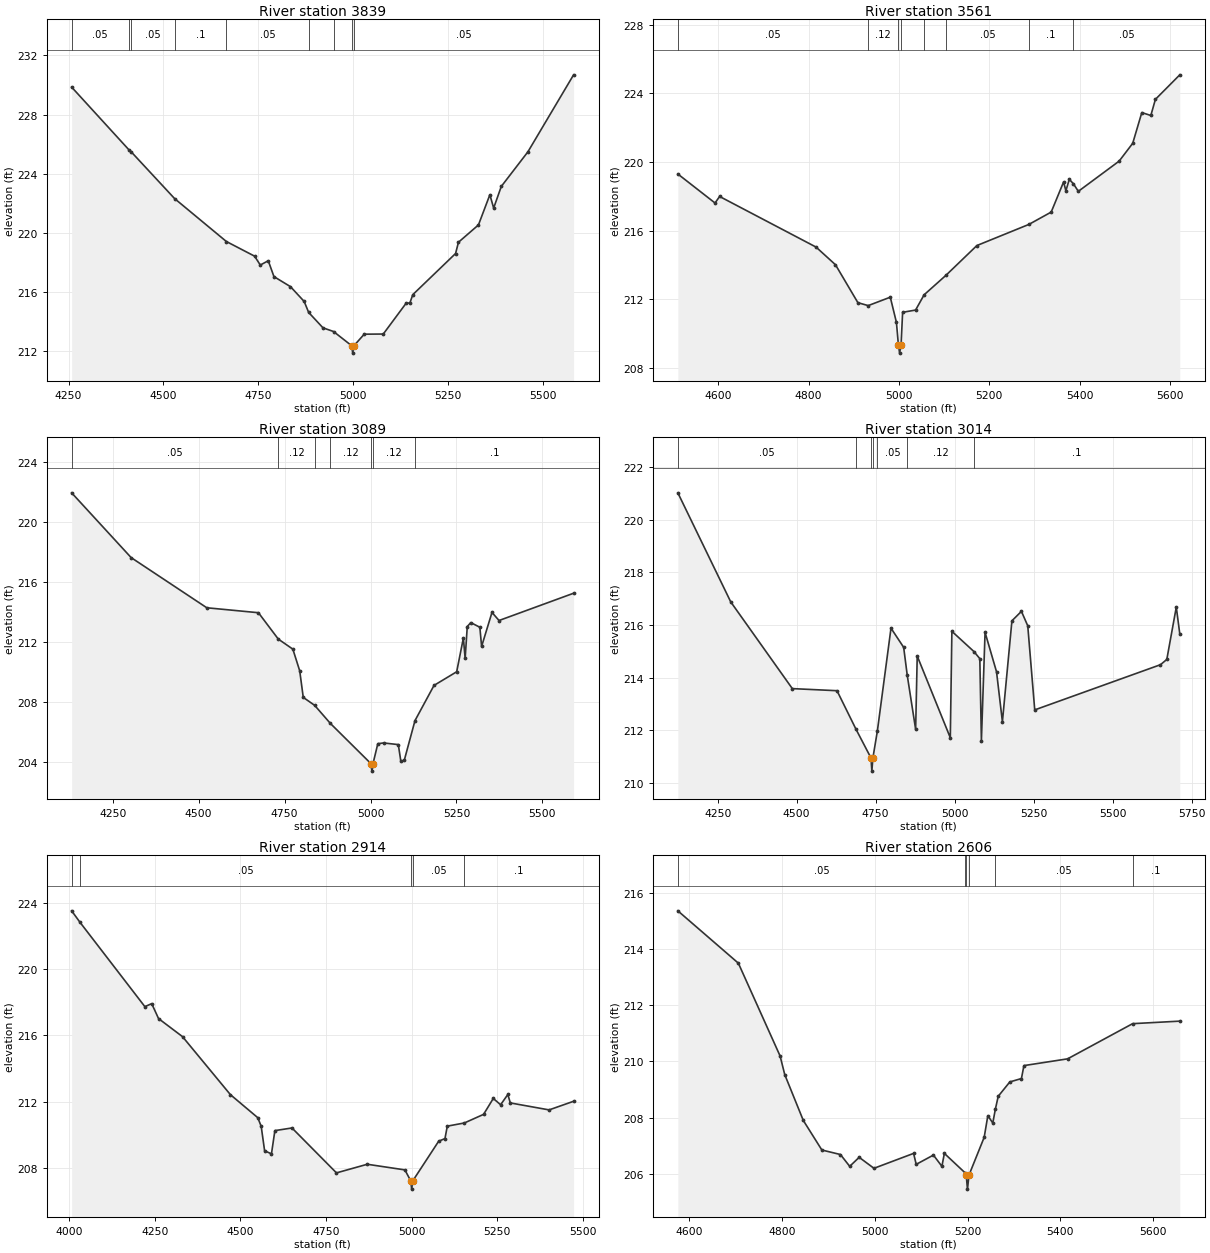
Type RM Length L Ch R = 1 ,3839    ,278,278,278
BEGIN DESCRIPTION:
UNT072 IN PECR 1.0
END DESCRIPTION:
XS GIS Cut Line= 3
      2289087.74     13187096.88      2288687.72     13186496.85
      2288087.74     13186446.86
#Sta/Elev= 30
  4258.1  229.86  4408.9  225.63  4414.7   225.5  4529.5  222.33    4666  219.43
  4740.4  218.44  4755.4  217.84  4776.4  218.13  4791.4  217.06    4835  216.38
  4871.1  215.38  4882.9  214.64  4920.6   213.6  4948.5  213.35  4996.3  212.39
  4999.1  211.89  5002.3  212.39  5029.4  213.17  5079.6  213.18  5139.8  215.26
  5149.8  215.28  5157.4  215.84  5270.2  218.62  5277.8  219.38  5330.5  220.55
  5360.6  222.59  5370.6  221.69  5390.7  223.15  5460.9  225.49  5581.3  230.69
#Mann= 9 ,-1 , 0
  4258.1     .05       0  4408.9      .1       0  4414.7     .05       0
  4529.5      .1       0    4666     .05       0  4882.9     .12       0
  4948.5     .05       0  4996.3     .03       0  5002.3     .05       0
Bank Sta=4996.3,5002.3
XS Rating Curve= 0 ,0
Exp/Cntr=0.3,0.1

Type RM Length L Ch R = 1 ,3561    ,472,472,472
BEGIN DESCRIPTION:
Mapping XS 2d789e39
END DESCRIPTION:
XS GIS Cut Line= 4
      2289014.82     13186707.61      2288962.73     13186441.97
      2288618.98     13186160.72      2288223.86     13186191.91
#Sta/Elev= 30
  4510.7   219.3    4593  217.61  4603.2  217.99  4816.7  215.04  4859.7  214.01
  4909.3   211.8  4932.1  211.63    4981  212.12  4994.6  210.65  4998.9  209.36
  5001.6  208.86  5004.9  209.36  5008.3  211.24    5037  211.37  5055.9  212.26
    5104  213.39  5172.7  215.13  5287.7  216.36  5337.2  217.08  5364.7  218.84
  5369.7  218.32  5377.3  218.99  5386.4  218.73  5397.3  218.29  5487.6  220.05
  5517.7  221.09  5537.8  222.88  5557.8  222.71  5567.9  223.65  5621.9  225.08
#Mann= 8 ,-1 , 0
  4510.7     .05       0  4932.1     .12       0  4998.9     .07       0
  5004.9     .12       0  5055.9      .1       0    5104     .05       0
  5287.7      .1       0  5386.4     .05       0
Bank Sta=4998.9,5004.9
XS Rating Curve= 0 ,0
Exp/Cntr=0.3,0.1

Type RM Length L Ch R = 1 ,3089    ,75,75,75
BEGIN DESCRIPTION:
Mapping XS cdb01b52
END DESCRIPTION:
XS GIS Cut Line= 4
      2289103.62     13186809.65      2289062.39     13185917.85
      2288926.54     13185927.72      2288506.41      13185830.5
#Sta/Elev= 30
  4130.6  221.96  4303.6  217.64  4523.8  214.29    4674  213.96  4731.8   212.2
  4774.1  211.53  4794.1  210.08  4804.4  208.31  4837.5  207.78  4883.4  206.57
  5001.3  203.89  5004.1  203.39  5007.3  203.89  5021.3  205.22  5038.1  205.27
  5080.9  205.16  5088.2  204.06  5098.2  204.11  5129.4  206.76  5184.8  209.11
  5250.7  210.02  5270.2  212.27  5275.3  210.91  5281.5  213.04  5291.8   213.3
  5318.1  212.99  5323.2  211.71  5353.4  213.98  5373.9  213.44  5590.8  215.26
#Mann= 7 ,-1 , 0
  4130.6     .05       0  4731.8     .12       0  4837.5     .05       0
  4883.4     .12       0  5001.3     .07       0  5007.3     .12       0
  5129.4      .1       0
Bank Sta=5001.3,5007.3
XS Rating Curve= 0 ,0
Exp/Cntr=0.3,0.1

Type RM Length L Ch R = 1 ,3014    ,100,100,100
BEGIN DESCRIPTION:
Mapping XS a3791fad
END DESCRIPTION:
XS GIS Cut Line= 6
       2289169.6       13186768.      2289103.62     13186115.22
      2289127.93     13185851.33      2289120.98     13185799.25
      2289013.35     13185802.72      2288506.64     13185792.91
#Sta/Elev= 30
    4124  221.03  4291.4  216.88  4486.3  213.58  4627.7   213.5    4688  212.03
  4735.3  210.94    4738  210.44  4741.3  210.94  4755.5  211.97  4798.6  215.88
  4838.7  215.15  4850.1  214.08  4876.6  212.03  4881.6  214.82  4986.3  211.71
  4991.3  215.76  5061.1  214.99  5079.7  214.72  5084.7   211.6  5096.3  215.72
  5132.6  214.22  5151.2  212.32  5181.3  216.16  5211.4  216.52  5231.4  215.97
  5253.5  212.77  5651.5  214.49  5671.5  214.69  5701.5  216.68  5712.6  215.66
#Mann= 7 ,-1 , 0
    4124     .05       0    4688     .12       0  4735.3     .07       0
  4741.3     .12       0  4755.5     .05       0  4850.1     .12       0
  5061.1      .1       0
Bank Sta=4735.3,4741.3
XS Rating Curve= 0 ,0
Exp/Cntr=0.3,0.1

Type RM Length L Ch R = 1 ,2914    ,308,308,308
BEGIN DESCRIPTION:
Mapping XS 7ab3e7d3
END DESCRIPTION:
XS GIS Cut Line= 3
      2289207.18     13186850.88      2289210.65     13185774.45
      2288925.94     13185507.09
#Sta/Elev= 30
  4006.5  223.52  4031.2  222.82  4220.5  217.74  4240.5  217.92  4260.5  217.02
  4330.5  215.93  4470.5  212.43  4550.5  211.04  4560.5  210.52  4570.5  209.04
  4590.5  208.86  4600.5  210.26  4650.5  210.42  4780.5  207.71  4870.5  208.23
  4980.5  207.89  4997.5  207.23  5000.3  206.73  5003.5  207.23  5079.2  209.62
  5097.6  209.78  5104.4  210.53  5154.1  210.72  5210.4  211.24  5238.8   212.2
  5260.2  211.82  5281.3  212.44  5288.6  211.93  5401.9  211.51  5473.5  212.03
#Mann= 5 ,-1 , 0
  4006.5      .1       0  4031.2     .05       0  4997.5     .04       0
  5003.5     .05       0  5154.1      .1       0
Bank Sta=4997.5,5003.5
XS Rating Curve= 0 ,0
Exp/Cntr=0.3,0.1

Type RM Length L Ch R = 1 ,2606    ,335,335,335
BEGIN DESCRIPTION:
Mapping XS 85de894f
END DESCRIPTION:
XS GIS Cut Line= 4
      2289452.31     13186447.21      2289457.52     13186061.76
      2289306.48     13185655.51       2289072.4     13185535.86
#Sta/Elev= 30
  4575.6  215.35    4706  213.49    4796  210.19    4806  209.53    4846   207.9
    4886  206.85    4926  206.69    4946  206.27  4966.4  206.59  4998.3   206.2
  5083.7  206.73  5089.3  206.34  5126.4  206.67  5144.7  206.27    5150  206.73
  5194.6  206.04  5197.1  205.96  5199.8  205.46  5203.1  205.96  5235.8   207.3
  5243.7  208.07  5254.4  207.81  5259.9   208.3  5266.1  208.76  5291.1  209.27
  5316.1  209.39  5321.5  209.85  5415.6  210.09  5555.7  211.34  5657.4  211.43
#Mann= 6 ,-1 , 0
  4575.6     .05       0  5194.6      .1       0  5197.1     .03       0
  5203.1      .1       0  5259.9     .05       0  5555.7      .1       0
Bank Sta=5197.1,5203.1
XS Rating Curve= 0 ,0
Exp/Cntr=0.3,0.1

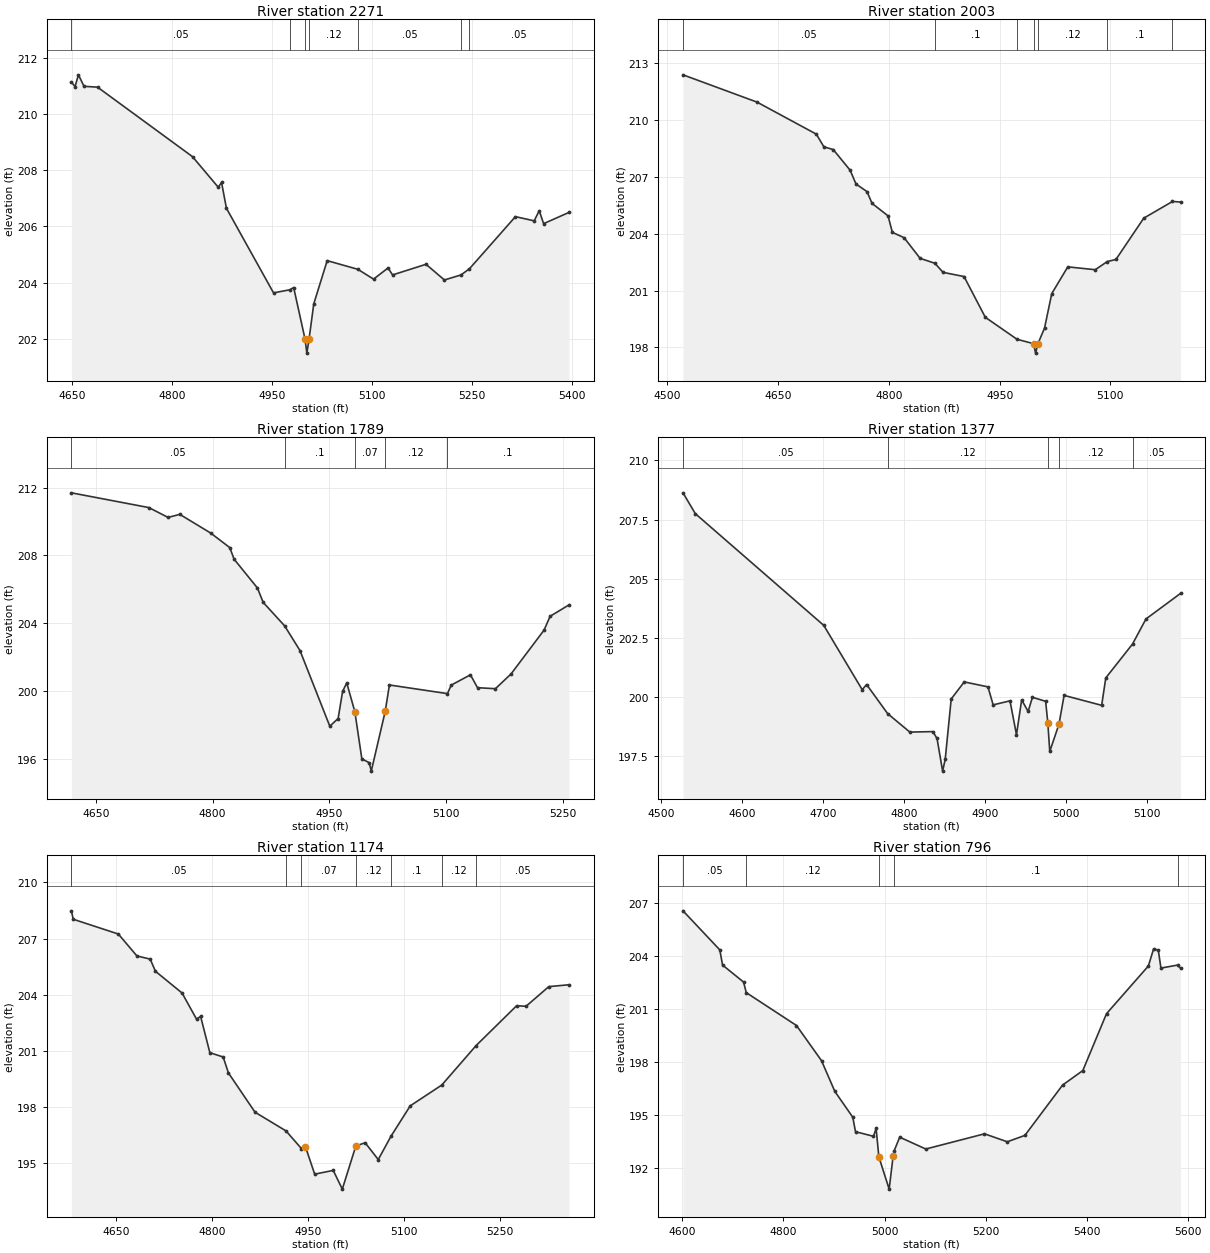
Type RM Length L Ch R = 1 ,2271    ,268,268,268
BEGIN DESCRIPTION:
Mapping XS 07217ea1
END DESCRIPTION:
XS GIS Cut Line= 4
      2289661.37     13186175.42      2289708.69     13185924.42
      2289690.18     13185757.79      2289447.47     13185543.88
#Sta/Elev= 30
  4649.4  211.15  4654.9  210.99  4659.9  211.41  4668.3     211  4688.6  210.97
  4831.1  208.49  4869.7   207.4  4874.7  207.57    4882  206.65  4952.7  203.63
  4977.1  203.74  4982.9  203.82    5000  201.98  5002.7  201.48    5006  201.98
  5013.1  203.24  5033.2  204.78  5079.3  204.47  5102.8  204.12  5124.6  204.52
  5131.3  204.27  5181.5  204.65  5209.1  204.09    5234  204.27  5246.7  204.49
  5315.7  206.35  5343.8   206.2  5351.4  206.56    5358   206.1    5396   206.5
#Mann= 7 ,-1 , 0
  4649.4     .05       0  4977.1     .12       0    5000     .07       0
    5006     .12       0  5079.3     .05       0    5234      .1       0
  5246.7     .05       0
Bank Sta=5000,5006
XS Rating Curve= 0 ,0
Exp/Cntr=0.3,0.1

Type RM Length L Ch R = 1 ,2003    ,214,214,214
BEGIN DESCRIPTION:
Mapping XS 99f9c0fe
END DESCRIPTION:
XS GIS Cut Line= 2
      2289707.52     13186254.47      2290035.63     13185665.95
#Sta/Elev= 30
  4521.2  212.38  4621.5  210.94  4701.8  209.25    4712  208.58  4724.6  208.44
  4747.5  207.35  4755.5  206.62  4770.4  206.22  4777.2   205.6  4798.9  204.94
  4804.7  204.07  4820.6  203.79  4842.3   202.7  4862.3  202.44  4873.4  201.96
  4901.8  201.74  4930.6  199.59  4973.6  198.43  4995.9   198.2  4998.7   197.7
  5001.9   198.2  5010.8  199.02  5020.6  200.84  5042.3  202.25  5079.5   202.1
  5095.8  202.53  5107.5  202.64  5145.2  204.82  5184.1   205.7    5195  205.67
#Mann= 7 ,-1 , 0
  4521.2     .05       0  4862.3      .1       0  4973.6     .12       0
  4995.9     .07       0  5001.9     .12       0  5095.8      .1       0
  5184.1     .05       0
Bank Sta=4995.9,5001.9
XS Rating Curve= 0 ,0
Exp/Cntr=0.3,0.1

Type RM Length L Ch R = 1 ,1789    ,412,412,412
BEGIN DESCRIPTION:
Mapping XS ac5f82ac
END DESCRIPTION:
XS GIS Cut Line= 3
      2289967.96     13186316.92      2290155.44     13185827.38
      2290165.86     13185712.77
#Sta/Elev= 30
  4618.7  211.69  4718.2  210.82  4742.9  210.24    4758  210.42  4797.6  209.32
  4822.2  208.46  4827.7  207.78  4857.7  206.08  4865.1  205.23  4892.6  203.85
  4912.4  202.39  4950.7  197.93  4961.4  198.38  4967.2  199.99  4972.5  200.48
  4982.9  198.78  4991.9     196  5001.3  195.78    5004  195.28  5021.9   198.8
  5027.3  200.36  5101.9  199.85  5106.7  200.35  5131.4  200.96  5140.5   200.2
  5163.5  200.14  5183.6  201.01  5226.1   203.6  5233.8  204.41    5258  205.08
#Mann= 5 ,-1 , 0
  4618.7     .05       0  4892.6      .1       0  4982.9     .07       0
  5021.9     .12       0  5101.9      .1       0
Bank Sta=4982.9,5021.9
XS Rating Curve= 0 ,0
Exp/Cntr=0.3,0.1

Type RM Length L Ch R = 1 ,1377    ,203,203,203
BEGIN DESCRIPTION:
Mapping XS fc7b3d74
END DESCRIPTION:
XS GIS Cut Line= 5
      2290196.22     13186284.46      2290301.15      13186035.5
      2290323.78     13185957.33      2290375.21     13185893.56
      2290348.47     13185714.62
#Sta/Elev= 30
  4527.3  208.63  4542.5  207.75  4701.1  203.03  4748.6  200.31    4754  200.53
    4780   199.3  4807.4  198.52  4835.8  198.54    4841  198.25  4847.9  196.87
  4851.1  197.37  4858.5  199.92  4874.6  200.64  4903.9  200.43  4910.3  199.67
  4931.1  199.84  4939.1  198.41  4945.5  199.88  4953.5  199.39  4958.8  199.99
  4975.1  199.82 4977.82  198.91  4980.2   197.7 4991.56  198.85  4997.9  200.07
  5044.3  199.65  5049.4  200.81  5082.4  202.24    5099   203.3  5141.7  204.38
#Mann= 5 ,-1 , 0
  4527.3     .05       0    4780     .12       0 4977.82     .07       0
 4991.56     .12       0  5082.4     .05       0
Bank Sta=4977.82,4991.56
XS Rating Curve= 0 ,0
Exp/Cntr=0.3,0.1

Type RM Length L Ch R = 1 ,1174    ,378,378,378
BEGIN DESCRIPTION:
Mapping XS 6ddbb29b
END DESCRIPTION:
XS GIS Cut Line= 4
      2290249.71     13186282.38      2290523.32     13185928.53
      2290548.01     13185821.56      2290369.07     13185691.99
#Sta/Elev= 30
  4580.5  208.48  4583.3  208.03  4653.9  207.24  4682.9  206.07  4703.7   205.9
  4711.9  205.25  4753.5  204.09  4776.2  202.69  4782.5  202.84    4797   200.9
  4817.8  200.67    4826  199.82  4867.6  197.72  4916.1  196.72  4940.1  195.78
  4946.4  195.88  4960.9  194.41  4989.9  194.61  5004.1  193.61  5025.2  195.91
  5039.8  196.09  5060.3  195.19  5080.3  196.44  5110.3  198.06  5159.6  199.17
  5213.3  201.28  5276.7  203.41  5291.4  203.38    5327  204.43  5358.5  204.53
#Mann= 7 ,-1 , 0
  4580.5     .05       0  4916.1     .12       0  4940.1     .07       0
  5025.2     .12       0  5080.3      .1       0  5159.6     .12       0
  5213.3     .05       0
Bank Sta=4946.4,5025.2
XS Rating Curve= 0 ,0
Exp/Cntr=0.3,0.1

Type RM Length L Ch R = 1 ,796     ,320,320,320
BEGIN DESCRIPTION:
Mapping XS 7e34de9b
END DESCRIPTION:
XS GIS Cut Line= 4
      2290753.71     13186288.56      2290860.69     13186041.68
      2290792.81      13185776.3      2290366.28     13185661.47
#Sta/Elev= 30
  4601.2  206.56    4674  204.35  4679.5  203.49    4721  202.53  4726.4  201.93
  4825.8  200.07  4875.3  198.08  4901.7  196.34  4937.2  194.88  4942.6  194.06
  4978.2   193.8  4983.4  194.25  4988.8  192.64  5009.2  190.81 5017.05  192.68
    5019  192.97  5030.1  193.75  5081.7  193.08  5197.9  193.94    5243  193.49
  5277.8  193.85  5352.5   196.7  5392.5  197.52  5439.4  200.74  5522.3  203.44
  5532.6  204.41  5541.9  204.33  5547.1  203.32  5580.1  203.49  5585.9  203.31
#Mann= 5 ,-1 , 0
  4601.2     .05       0  4726.4     .12       0  4988.8     .05       0
    5019      .1       0  5580.1     .05       0
Bank Sta=4988.8,5017.05
XS Rating Curve= 0 ,0
Exp/Cntr=0.3,0.1

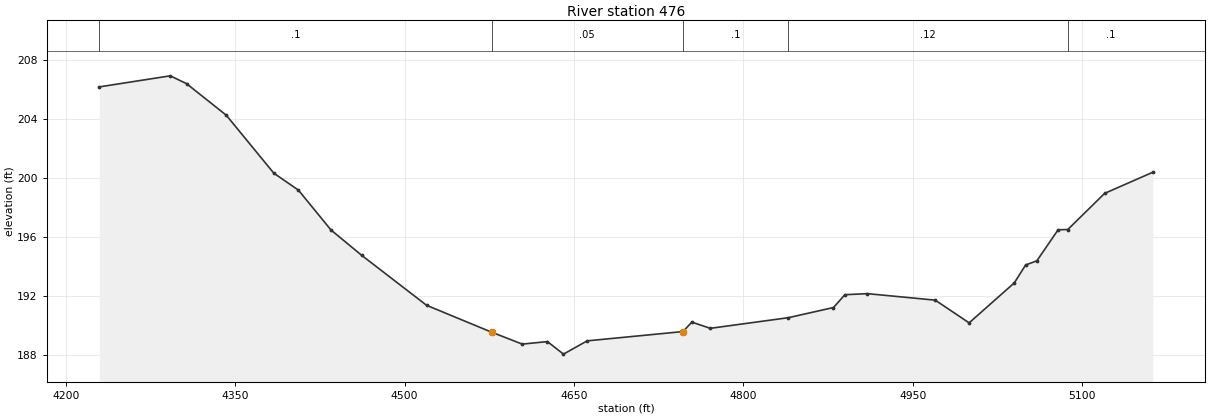
Type RM Length L Ch R = 1 ,476     ,0,0,0
BEGIN DESCRIPTION:
UNT072 IN PECR 2.0
END DESCRIPTION:
XS GIS Cut Line= 3
        2290770.     13186436.79      2291108.56     13186020.09
      2291113.77     13185624.23
#Sta/Elev= 30
  4229.7  206.21  4292.5  206.96  4306.9  206.43  4342.1  204.29  4384.2  200.36
    4406  199.21  4434.8  196.51    4462  194.79  4519.5   191.4    4577  189.58
  4604.2  188.77  4626.5  188.94  4640.7  188.09  4661.7  188.99  4746.5  189.62
  4754.4  190.26  4770.7  189.84  4839.8  190.56  4879.8  191.25  4889.9  192.12
  4909.9  192.19  4969.9  191.75  4999.9  190.21  5039.9  192.92  5049.9  194.13
  5059.9  194.42  5078.7  196.52  5087.3  196.54  5119.9  198.99  5162.5  200.42
#Mann= 5 ,-1 , 0
  4229.7      .1       0    4577     .05       0  4746.5      .1       0
  4839.8     .12       0  5087.3      .1       0
Bank Sta=4577,4746.5
XS Rating Curve= 0 ,0
Exp/Cntr=0.3,0.1

Chan Stop Cuts=-1
Use User Specified Reach Order=0
Composite Channel Slope=5