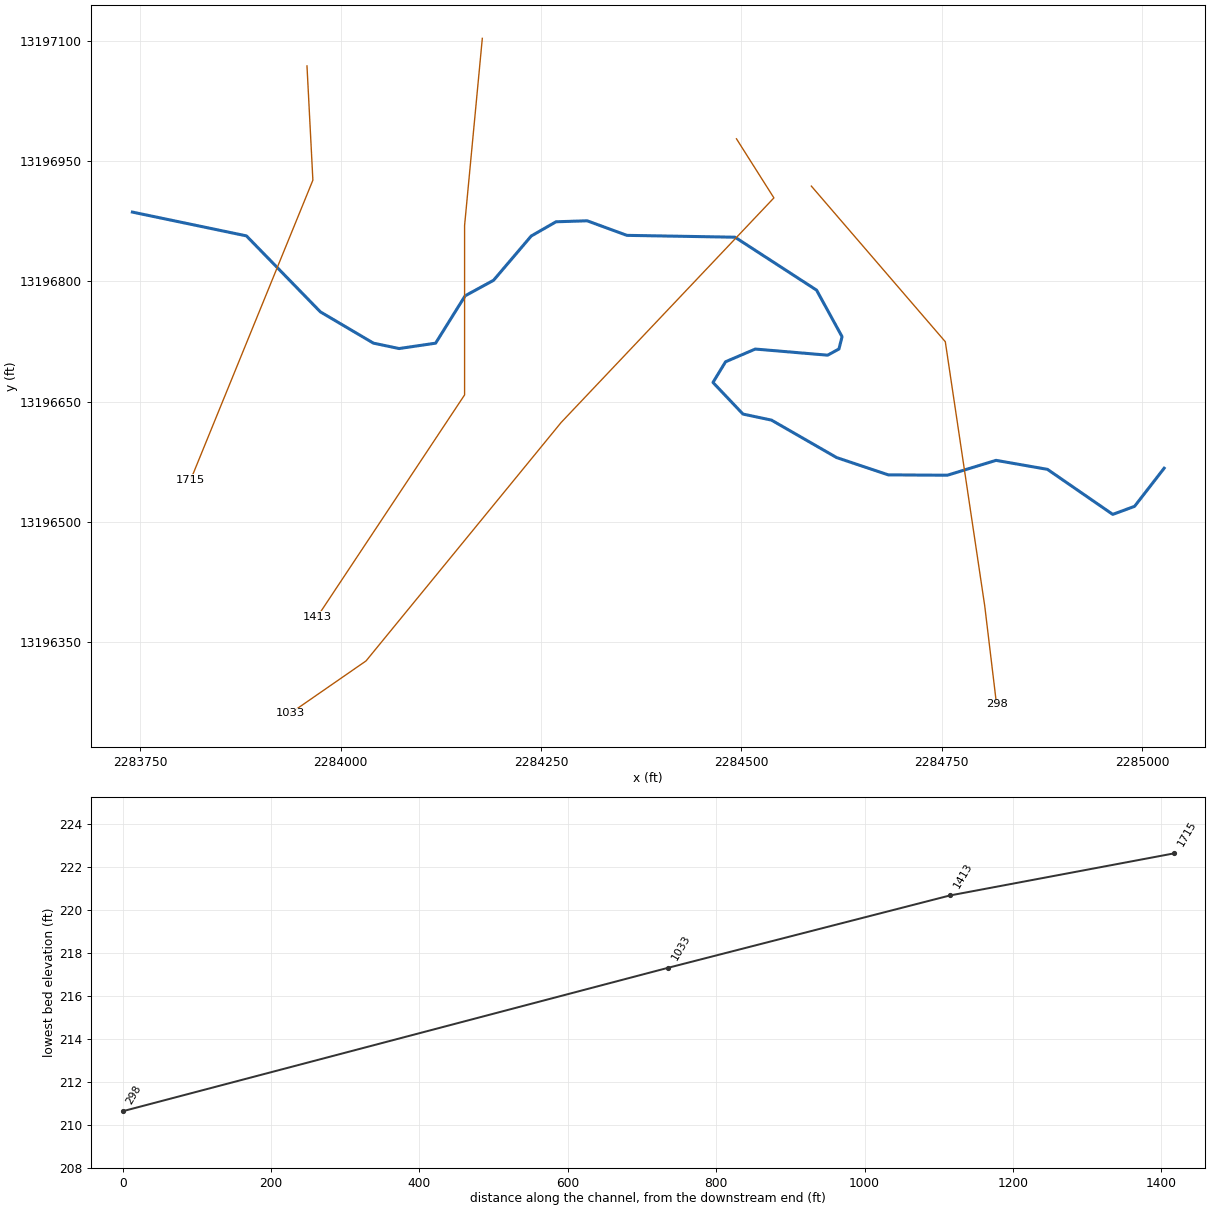
--- UNT073 IN PECR.prj (project) ---

Proj Title=UNT073 IN PECR Base Level Engineering
Current Plan=p01
Default Exp/Contr=0.3,0.1
English Units
Geom File=g01
Flow File=f01
Plan File=p01
Y Axis Title=Elevation
X Axis Title(PF)=Main Channel Distance
X Axis Title(XS)=Station
BEGIN DESCRIPTION:
UNT073 IN PECR
END DESCRIPTION:
DSS Export Rating Curves= 0
DSS Export Rating Curve Sorted= 0
DSS Export Volume Flow Curves= 0
DXF OffsetX= 0
DXF OffsetY= 0
DXF ScaleX= 1
DXF ScaleY= 10

--- UNT073 IN PECR.p01 (plan) ---

Plan Title=Multiple Run
Short Identifier=Multiple
Geom File=g01
Flow File=f01
Subcritical Flow
K Sum by GR= 0
Std Step Tol= 0.01
Critical Tol= 0.01
Num of Std Step Trials= 20
Max Error Tol= 0.3
Flow Tol Ratio= 0.001
Split Flow NTrial= 30
Split Flow Tol= 0.02
Split Flow Ratio= 0.02
Log Output Level= 0
Friction Slope Method= 1
Unsteady Friction Slope Method= 2
Unsteady Bridges Friction Slope Method= 1
Parabolic Critical Depth
Global Vel Dist=  1 , 1 , 1
Global Log Level= 0
CheckData=True
Encroach Param= -1, 0, 0, 0
BEGIN DESCRIPTION:
Multiple Run
END DESCRIPTION:

--- UNT073 IN PECR.f01 (steady flow) ---

Flow Title=Multiple
Program Version=4.10
Number of Profiles= 7
Profile Names=10-year,25-year,50-year,1pct_min,100-year,1pct_plu,500-year
River Rch & RM=UNT073 IN PECR,Reach-1         ,1715
     256     354     436     395     534     722     814
Boundary for River Rch & Prof#=UNT073 IN PECR,Reach-1         , 1
Up Type= 0
Dn Type= 3
Dn Slope=0.0091
Boundary for River Rch & Prof#=UNT073 IN PECR,Reach-1         , 2
Up Type= 0
Dn Type= 3
Dn Slope=0.0091
Boundary for River Rch & Prof#=UNT073 IN PECR,Reach-1         , 3
Up Type= 0
Dn Type= 3
Dn Slope=0.0091
Boundary for River Rch & Prof#=UNT073 IN PECR,Reach-1         , 4
Up Type= 0
Dn Type= 3
Dn Slope=0.0091
Boundary for River Rch & Prof#=UNT073 IN PECR,Reach-1         , 5
Up Type= 0
Dn Type= 3
Dn Slope=0.0091
Boundary for River Rch & Prof#=UNT073 IN PECR,Reach-1         , 6
Up Type= 0
Dn Type= 3
Dn Slope=0.0091
Boundary for River Rch & Prof#=UNT073 IN PECR,Reach-1         , 7
Up Type= 0
Dn Type= 3
Dn Slope=0.0091
DSS Import GetInterval= 0
DSS Import GetPeak= 0
DSS Import FillOption= 0

--- UNT073 IN PECR.g01 (geometry) ---

Geom Title=Existing Conditions
Program Version=4.10

River Reach=UNT073 IN PECR  ,Reach-1
Reach XY= 30
      2283740.31     13196886.41      2283882.57     13196856.74
      2283974.85     13196761.92      2284041.02      13196722.9
      2284073.05     13196716.15      2284118.64     13196722.85
      2284155.45     13196781.92      2284190.93     13196801.32
      2284237.95     13196856.58       2284268.9     13196874.33
      2284307.74     13196875.56      2284357.28     13196857.39
      2284492.22     13196855.08      2284593.99     13196789.03
      2284625.81     13196730.93       2284621.9     13196715.58
      2284607.81     13196707.87      2284517.57     13196715.52
      2284480.44     13196699.66      2284464.73     13196673.86
      2284502.13      13196634.4      2284537.72     13196626.85
      2284619.06     13196580.09      2284683.49     13196558.52
      2284757.17     13196558.08       2284817.9     13196576.65
      2284882.08     13196565.41      2284963.57     13196509.21
      2284990.79     13196519.25      2285027.72     13196566.86

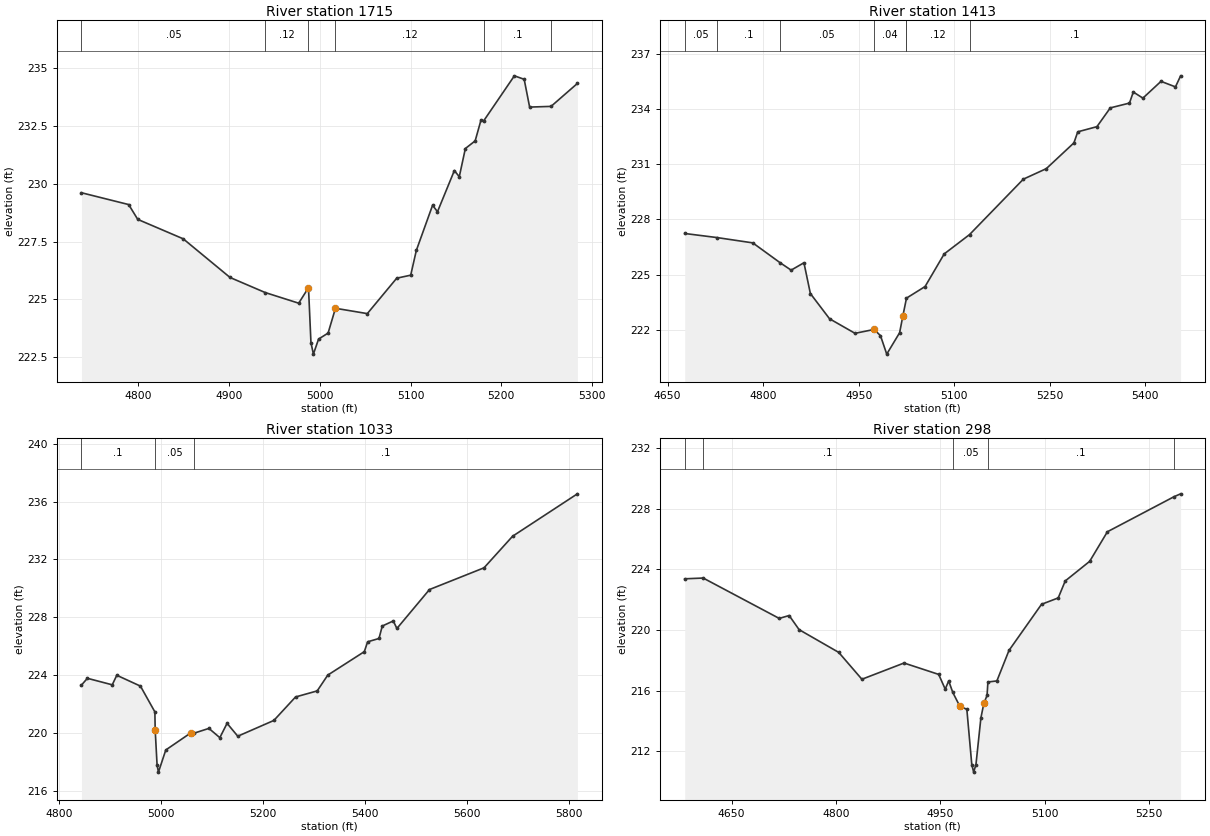
Type RM Length L Ch R = 1 ,1715    ,302,302,302
BEGIN DESCRIPTION:
UNT073 IN PECR 2.0
END DESCRIPTION:
XS GIS Cut Line= 3
      2283958.13     13197068.82       2283965.5     13196926.25
      2283813.09      13196552.6
#Sta/Elev= 30
  4737.5  229.61  4789.5   229.1  4799.5  228.46  4849.6  227.62  4901.2  225.95
  4939.9   225.3  4976.8  224.84  4987.6  225.51  4990.3  223.14    4993  222.64
  4998.7  223.29  5009.2  223.55  5017.3  224.62  5052.4  224.39  5084.8  225.92
  5100.2  226.05  5106.4  227.12  5124.3  229.07  5129.7  228.79  5148.3  230.57
  5153.7   230.3  5160.4  231.52  5171.2  231.85  5177.7  232.76  5180.5  232.71
  5214.4  234.66  5225.2  234.51  5231.2  233.31  5254.8  233.34  5283.8  234.33
#Mann= 6 ,-1 , 0
  4737.5     .05       0  4939.9     .12       0  4987.6     .07       0
  5017.3     .12       0  5180.5      .1       0  5254.8     .05       0
Bank Sta=4987.6,5017.3
XS Rating Curve= 0 ,0
Exp/Cntr=0.3,0.1

Type RM Length L Ch R = 1 ,1413    ,380,380,380
BEGIN DESCRIPTION:
Mapping XS 59248f0c
END DESCRIPTION:
XS GIS Cut Line= 4
      2284176.91     13197103.23      2284154.79     13196869.71
      2284154.79     13196658.29      2283970.85     13196381.16
#Sta/Elev= 30
  4676.9  227.23  4727.3  227.01  4783.8  226.72  4826.8  225.64    4844  225.24
  4864.1  225.64  4874.2  223.97  4904.3   222.6  4944.3  221.81  4974.3  222.02
  4984.3  221.68  4994.1  220.68  5014.3  221.84 5019.29  222.73  5025.1  223.72
  5054.3  224.35  5084.3  226.12  5124.1  227.17  5208.6  230.18  5244.6  230.75
    5288  232.15    5294  232.75  5324.1  233.03  5345.1  234.05  5375.2  234.31
  5381.2  234.91  5396.3  234.58  5424.7  235.49  5447.4  235.19  5455.5  235.79
#Mann= 7 ,-1 , 0
  4676.9     .05       0  4727.3      .1       0  4826.8     .05       0
  4974.3     .04       0  5025.1     .05       0  5025.1     .12       0
  5124.1      .1       0
Bank Sta=4974.3,5019.29
XS Rating Curve= 0 ,0
Exp/Cntr=0.3,0.1

Type RM Length L Ch R = 1 ,1033    ,735,735,735
BEGIN DESCRIPTION:
Mapping XS 87a41f39
END DESCRIPTION:
XS GIS Cut Line= 5
      2284494.06     13196977.84      2284540.75     13196904.13
      2284275.25     13196623.88      2284031.87     13196326.42
      2283937.27     13196260.92
#Sta/Elev= 30
  4844.6  223.32  4856.2  223.79    4905  223.34  4913.9     224  4960.3  223.25
  4988.6  221.47  4989.2  220.23  4992.9  217.81  4995.6  217.31    5010  218.84
  5059.4  220.03  5066.3  220.01  5094.6  220.33    5116  219.69  5130.2  220.68
  5151.2  219.79    5222  220.88  5264.5   222.5    5307  222.92  5327.7  224.01
  5399.4  225.63  5405.9  226.31  5428.2  226.54  5434.6   227.4  5456.2  227.75
  5463.3  227.23  5527.2  229.92  5634.2  231.42  5690.2   233.6  5817.3  236.53
#Mann= 3 ,-1 , 0
  4844.6      .1       0  4988.6     .05       0  5066.3      .1       0
Bank Sta=4989.2,5059.4
XS Rating Curve= 0 ,0
Exp/Cntr=0.3,0.1

Type RM Length L Ch R = 1 ,298     ,0,0,0
BEGIN DESCRIPTION:
UNT073 IN PECR 1.0
END DESCRIPTION:
XS GIS Cut Line= 4
      2284587.47     13196918.86      2284754.62     13196724.67
      2284803.79     13196395.25      2284818.54     13196272.33
#Sta/Elev= 30
  4582.5  223.37  4609.1  223.42  4718.4  220.76  4732.7  220.95    4747  220.02
    4804  218.52  4837.3  216.75  4897.9  217.82  4947.7  217.07  4957.1   216.1
  4962.1  216.64    4968  215.88  4978.1  214.97  4988.2  214.77  4995.3  211.13
    4998  210.63  5001.3  211.13  5008.4   214.2 5012.73  215.18 5017.27  215.68
  5018.5  216.57  5031.4  216.64  5048.8  218.65  5095.6  221.69  5119.6  222.11
  5129.7  223.23  5164.8  224.52  5190.3  226.47  5286.1  228.78  5295.6  228.97
#Mann= 5 ,-1 , 0
  4582.5     .05       0  4609.1      .1       0    4968     .05       0
  5018.5      .1       0  5286.1     .05       0
Bank Sta=4978.1,5012.73
XS Rating Curve= 0 ,0
Exp/Cntr=0.3,0.1

Chan Stop Cuts=-1
Use User Specified Reach Order=0
Composite Channel Slope=5