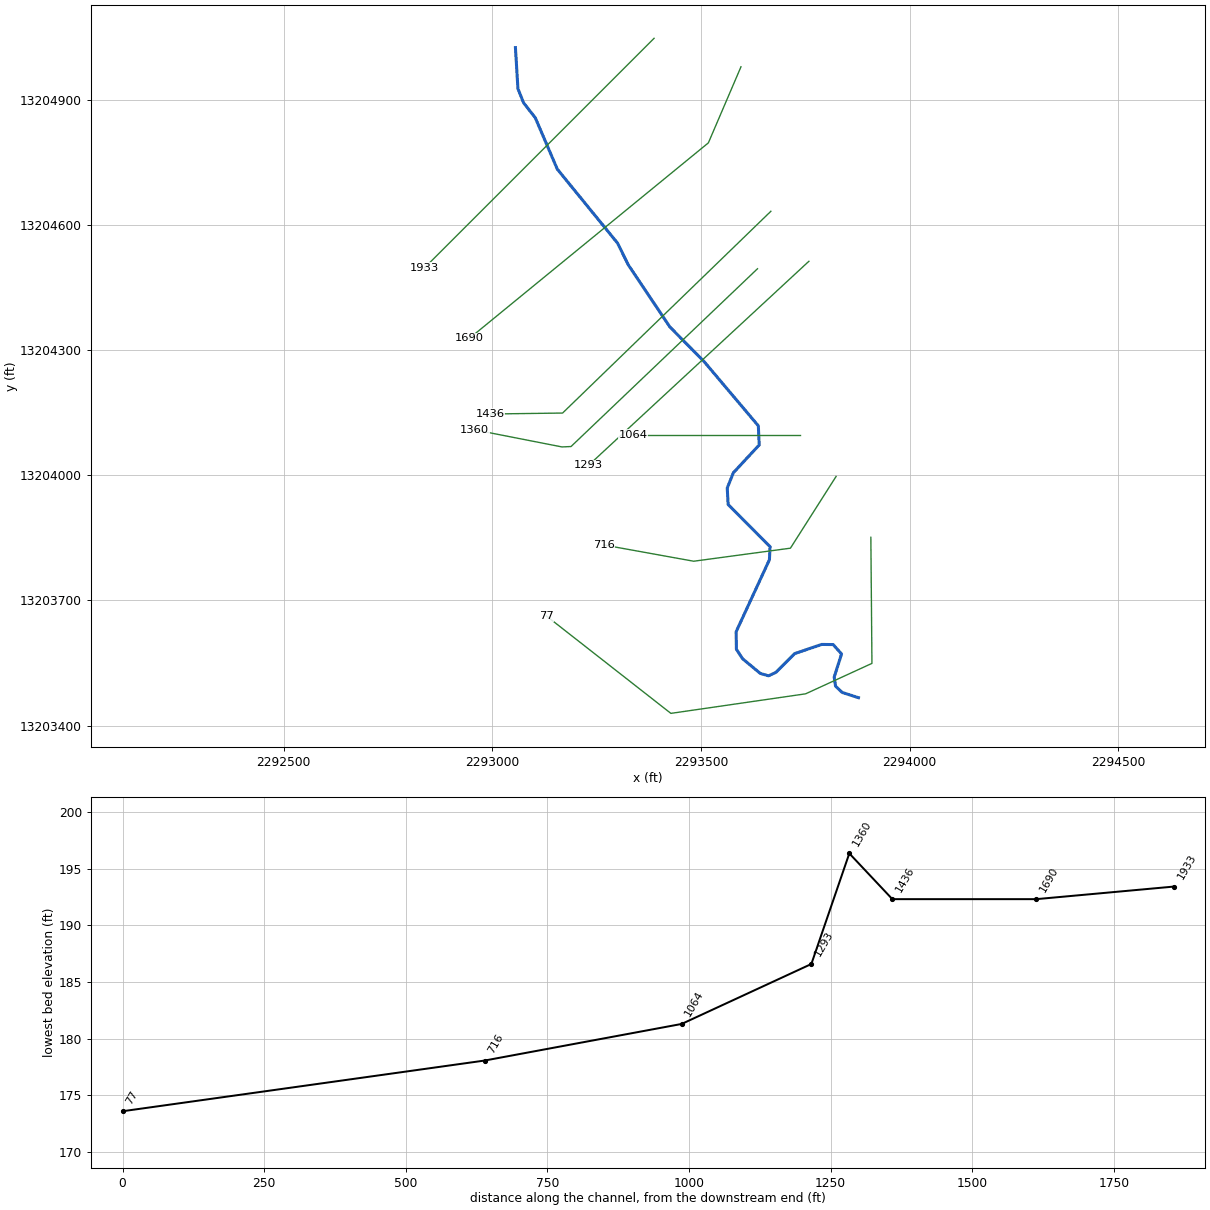
--- UNT074 IN PECR.prj (project) ---

Proj Title=UNT074 IN PECR Base Level Engineering
Current Plan=p01
Default Exp/Contr=0.3,0.1
English Units
Geom File=g01
Flow File=f01
Plan File=p01
Y Axis Title=Elevation
X Axis Title(PF)=Main Channel Distance
X Axis Title(XS)=Station
BEGIN DESCRIPTION:
UNT074 IN PECR
END DESCRIPTION:
DSS Export Rating Curves= 0
DSS Export Rating Curve Sorted= 0
DSS Export Volume Flow Curves= 0
DXF OffsetX= 0
DXF OffsetY= 0
DXF ScaleX= 1
DXF ScaleY= 10

--- UNT074 IN PECR.p01 (plan) ---

Plan Title=Multiple Run
Short Identifier=Multiple
Geom File=g01
Flow File=f01
Subcritical Flow
K Sum by GR= 0
Std Step Tol= 0.01
Critical Tol= 0.01
Num of Std Step Trials= 20
Max Error Tol= 0.3
Flow Tol Ratio= 0.001
Split Flow NTrial= 30
Split Flow Tol= 0.02
Split Flow Ratio= 0.02
Log Output Level= 0
Friction Slope Method= 1
Unsteady Friction Slope Method= 2
Unsteady Bridges Friction Slope Method= 1
Parabolic Critical Depth
Global Vel Dist=  1 , 1 , 1
Global Log Level= 0
CheckData=True
Encroach Param= -1, 0, 0, 0
BEGIN DESCRIPTION:
Multiple Run
END DESCRIPTION:

--- UNT074 IN PECR.f01 (steady flow) ---

Flow Title=Multiple
Program Version=4.10
Number of Profiles= 7
Profile Names=10-year,25-year,50-year,1pct_min,100-year,1pct_plu,500-year
River Rch & RM=UNT074 IN PECR,Reach-1         ,1933
     334     457     557     497     673     910     985
Boundary for River Rch & Prof#=UNT074 IN PECR,Reach-1         , 1
Up Type= 0
Dn Type= 3
Dn Slope=0.0069
Boundary for River Rch & Prof#=UNT074 IN PECR,Reach-1         , 2
Up Type= 0
Dn Type= 3
Dn Slope=0.0069
Boundary for River Rch & Prof#=UNT074 IN PECR,Reach-1         , 3
Up Type= 0
Dn Type= 3
Dn Slope=0.0069
Boundary for River Rch & Prof#=UNT074 IN PECR,Reach-1         , 4
Up Type= 0
Dn Type= 3
Dn Slope=0.0069
Boundary for River Rch & Prof#=UNT074 IN PECR,Reach-1         , 5
Up Type= 0
Dn Type= 3
Dn Slope=0.0069
Boundary for River Rch & Prof#=UNT074 IN PECR,Reach-1         , 6
Up Type= 0
Dn Type= 3
Dn Slope=0.0069
Boundary for River Rch & Prof#=UNT074 IN PECR,Reach-1         , 7
Up Type= 0
Dn Type= 3
Dn Slope=0.0069
DSS Import GetInterval= 0
DSS Import GetPeak= 0
DSS Import FillOption= 0

--- UNT074 IN PECR.g01 (geometry) ---

Geom Title=Existing Conditions
Program Version=4.10

River Reach=UNT074 IN PECR  ,Reach-1
Reach XY= 30
      2293055.58     13205024.55      2293061.58     13204926.15
      2293075.13      13204892.3      2293103.25     13204856.36
      2293155.86     13204733.45      2293300.13     13204556.36
      2293326.17     13204503.76      2293425.65     13204355.32
      2293507.94     13204271.99      2293637.63     13204118.34
      2293639.71     13204072.51      2293577.73     13204005.84
      2293563.15     13203969.38      2293565.23      13203929.8
      2293665.75     13203828.76      2293664.19     13203797.51
       2293584.5     13203625.11      2293585.02     13203582.93
      2293600.13     13203560.01       2293642.3     13203525.09
      2293662.05     13203519.33      2293679.98     13203527.71
      2293724.67     13203572.54      2293789.48     13203594.52
      2293816.94     13203594.21      2293837.01     13203571.67
      2293819.38      13203516.3      2293822.67     13203494.57
      2293838.37     13203479.55      2293877.51     13203466.88

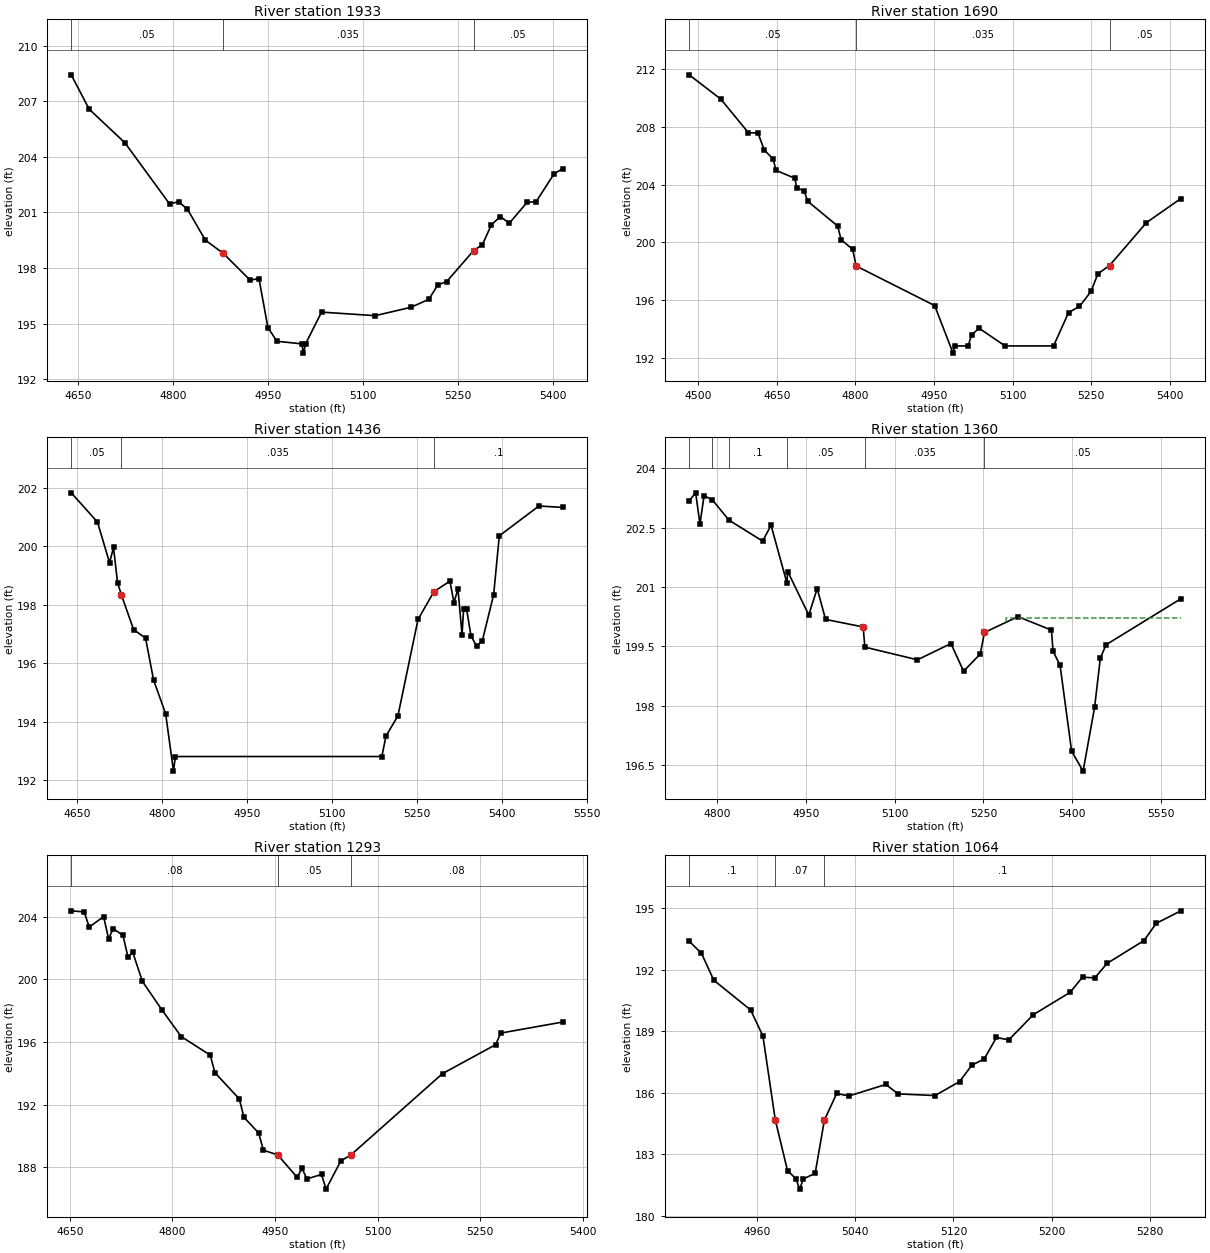
Type RM Length L Ch R = 1 ,1933    ,243,243,243
BEGIN DESCRIPTION:
UNT074 IN PECR 4.0
END DESCRIPTION:
XS GIS Cut Line= 3
      2293387.72     13205046.85      2293137.72     13204796.85
      2292837.73     13204496.86
#Sta/Elev= 30
  4638.6  208.42  4666.9  206.57  4723.4  204.76  4794.2  201.46  4808.3  201.58
  4822.4  201.18  4850.7  199.51    4879   198.8  4921.4  197.36  4935.6  197.43
  4949.7   194.8  4963.9  194.06  5003.3  193.92    5006  193.42  5009.3  193.92
  5034.6  195.63  5119.4  195.44    5176  195.89  5204.3  196.32  5218.4  197.09
  5232.6  197.28    5275  198.94  5289.1  199.27  5303.3  200.34  5317.4  200.78
  5331.6  200.42  5359.8  201.55    5374  201.58  5402.3  203.08  5416.4  203.37
#Mann= 3 , 0 , 0
  4638.6     .05       0    4879    .035       0    5275     .05       0
Bank Sta=4879,5275
XS Rating Curve= 0 ,0
Exp/Cntr=0.3,0.1

Type RM Length L Ch R = 1 ,1690    ,254,254,254
BEGIN DESCRIPTION:
Mapping XS f0206f38
END DESCRIPTION:
XS GIS Cut Line= 3
      2293596.05     13204978.71      2293517.92     13204796.41
      2292944.99     13204327.65
#Sta/Elev= 30
  4482.6  211.63  4543.1  209.94  4595.7  207.61  4613.9  207.59  4626.1   206.4
  4642.9  205.79  4648.3     205  4684.3  204.45  4687.9  203.79  4702.2  203.57
  4708.7  202.86  4766.1  201.13  4772.6  200.19  4794.8  199.51  4801.3  198.36
  4951.3  195.61  4986.3  192.31  4989.5  192.81  5015.2  192.81  5021.7  193.57
    5036  194.04  5085.6  192.81  5178.2  192.81  5206.9  195.13  5227.7  195.55
  5249.7  196.59  5262.9  197.82  5285.1  198.39  5355.5  201.37  5421.2  203.04
#Mann= 3 , 0 , 0
  4482.6     .05       0  4801.3    .035       0  5285.1     .05       0
Bank Sta=4801.3,5285.1
XS Rating Curve= 0 ,0
Exp/Cntr=0.3,0.1

Type RM Length L Ch R = 1 ,1436    ,76,76,76
BEGIN DESCRIPTION:
Mapping XS 9db61ae3
END DESCRIPTION:
XS GIS Cut Line= 3
      2293667.64     13204632.44      2293168.58     13204148.96
      2292995.44     13204146.71
#Sta/Elev= 30
  4640.3  201.83  4686.6  200.83  4707.9  199.44  4714.9  199.96  4722.1  198.75
    4729  198.33  4750.4  197.15  4771.5  196.86  4785.6  195.43    4807  194.27
  4820.8  192.31  4824.1  192.81  5188.7  192.81  5195.9  193.51    5217   194.2
  5252.5   197.5  5280.6  198.45  5308.9  198.81    5316  198.07    5323  198.55
  5330.2  196.98  5333.1  197.87  5338.1  197.87    5346  196.94    5356  196.58
    5366  196.77    5386  198.34    5396  200.36    5466  201.38  5508.3  201.33
#Mann= 3 , 0 , 0
  4640.3     .05       0    4729    .035       0  5280.6      .1       0
Bank Sta=4729,5280.6
XS Rating Curve= 0 ,0
Exp/Cntr=0.3,0.1

Type RM Length L Ch R = 1 ,1360    ,67,67,67
BEGIN DESCRIPTION:
UNT074 IN PECR 3.0
END DESCRIPTION:
XS GIS Cut Line= 4
      2293635.61     13204494.75      2293188.84     13204068.77
     2293167.035    13204067.794     2292957.638    13204108.846
#Sta/Elev= 30
  4752.6  203.18  4763.6  203.38  4770.8  202.59  4777.8  203.31  4791.9   203.2
  4819.8  202.69  4876.8  202.16    4891  202.56  4917.7  201.11  4919.3  201.39
  4954.8  200.29    4969  200.96  4983.2  200.18  5046.7  199.99  5049.6  199.48
  5138.5  199.16  5195.1  199.57  5216.5  198.87  5244.8  199.31  5251.7  199.85
  5308.4  200.25    5365  199.91  5367.7  199.38 5379.62199.01695399.059196.8522
5418.498196.34585437.937197.95645447.657199.20395457.376199.54095583.731200.7023
#Mann= 6 ,-1 , 0
  4752.6      .1       0  4791.9     .05       0  4819.8      .1       0
  4917.7     .05       0  5049.6    .035       0  5251.7     .05       0
#XS Ineff= 2 , 0
       0                 5287.85       0  200.22
Permanent Ineff=
       F       T
Bank Sta=5046.7,5251.7
XS Rating Curve= 0 ,0
Exp/Cntr=0.3,0.1

Type RM Length L Ch R = 1 ,1293    ,229,229,229
BEGIN DESCRIPTION:
Mapping XS 98df30f0
END DESCRIPTION:
XS GIS Cut Line= 2
      2293758.81     13204512.68      2293231.43     13204024.27
#Sta/Elev= 30
  4652.2  204.39  4671.1  204.32  4678.5  203.35  4699.5  204.02  4706.8   202.6
  4713.6  203.25  4727.8  202.82  4735.2  201.42    4742  201.75  4756.2  199.88
  4784.5  198.07  4812.9  196.35  4855.4  195.16  4862.2  194.04  4897.9  192.36
  4904.7  191.18  4926.2  190.18  4933.1  189.08    4954  188.78  4982.4  187.35
  4989.8  187.91  4996.6  187.24  5018.1  187.53  5024.7  186.59  5046.4   188.4
  5060.6  188.76    5195  193.98  5272.7  195.83    5280  196.57    5371  197.28
#Mann= 3 , 0 , 0
  4652.2     .08       0    4954     .05       0  5060.6     .08       0
Bank Sta=4954,5060.6
XS Rating Curve= 0 ,0
Exp/Cntr=0.3,0.1

Type RM Length L Ch R = 1 ,1064    ,348,348,348
BEGIN DESCRIPTION:
UNT074 IN PECR 2.0
END DESCRIPTION:
XS GIS Cut Line= 3
      2293737.76     13204096.85      2293637.72     13204096.85
      2293337.76     13204096.85
#Sta/Elev= 30
    4905  193.38    4915  192.79    4925  191.48    4955  190.03    4965  188.76
    4975  184.69    4985   182.2    4992   181.8  4994.8   181.3    4998   181.8
  5007.5  182.07    5015  184.66    5025  185.96    5035  185.84    5065   186.4
    5075  185.94    5105  185.86    5125  186.54    5135  187.34    5145  187.64
    5155  188.69    5165  188.57    5185   189.8    5215  190.89    5225  191.63
    5235  191.59    5245   192.3    5275  193.41    5285  194.25    5305  194.86
#Mann= 3 , 0 , 0
    4905      .1       0    4975     .07       0    5015      .1       0
Bank Sta=4975,5015
XS Rating Curve= 0 ,0
Exp/Cntr=0.3,0.1

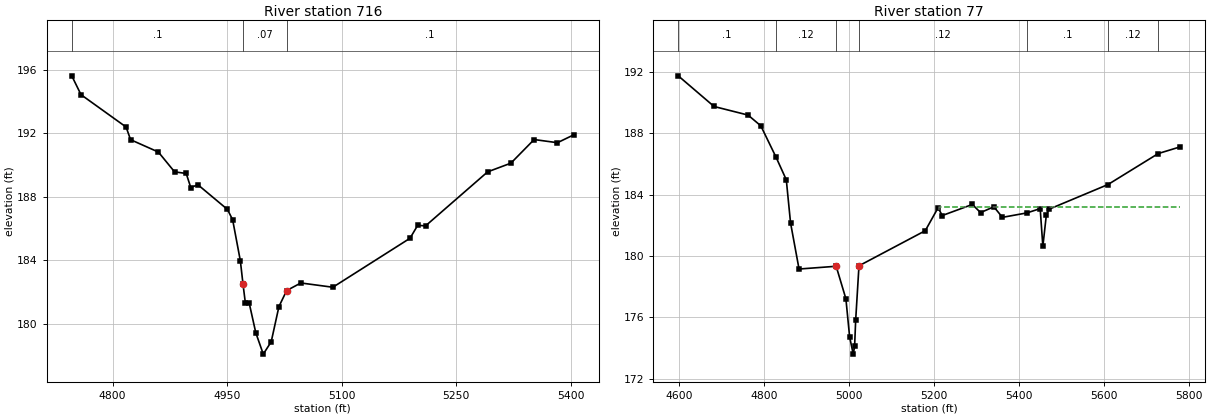
Type RM Length L Ch R = 1 ,716     ,639,639,639
BEGIN DESCRIPTION:
Mapping XS a5a54c3f
END DESCRIPTION:
XS GIS Cut Line= 4
      2293823.93     13203997.08      2293714.53     13203825.17
      2293482.76     13203793.92      2293266.59     13203832.99
#Sta/Elev= 30
  4746.5  195.63  4758.6  194.44  4817.6   192.4  4823.5   191.6  4859.9  190.82
  4881.1  189.57  4896.3  189.47  4902.3  188.58  4911.6  188.76  4950.3   187.2
  4957.1  186.55  4967.2  183.96 4970.72  182.47  4973.7  181.32  4978.7  181.31
  4987.4  179.42  4997.2  178.07  5007.6  178.85  5017.7  181.07  5027.8  182.08
  5046.4  182.56  5088.3  182.29  5189.3  185.38  5199.4   186.2  5209.6  186.16
  5290.9  189.57  5321.4  190.12  5351.8  191.61  5382.3  191.41  5403.8  191.91
#Mann= 3 , 0 , 0
  4746.5      .1       0 4970.72     .07       0  5027.8      .1       0
Bank Sta=4970.72,5027.8
XS Rating Curve= 0 ,0
Exp/Cntr=0.3,0.1

Type RM Length L Ch R = 1 ,77      ,0,0,0
BEGIN DESCRIPTION:
UNT074 IN PECR 1.0
END DESCRIPTION:
XS GIS Cut Line= 5
      2293907.24     13203851.25      2293909.85     13203549.13
      2293750.99     13203476.21      2293428.08     13203429.34
      2293129.79     13203662.78
#Sta/Elev= 30
    4598  191.75  4682.4  189.75  4762.4  189.19  4792.4  188.49  4828.5  186.43
  4852.4  184.97  4862.4  182.16  4882.4  179.15  4969.8  179.33  4992.7  177.21
  5001.5  174.72    5010   173.6  5013.2   174.1  5015.7   175.8  5023.5  179.36
  5179.6  181.65  5209.6  183.14  5219.7  182.64  5290.4  183.36  5309.8  182.83
    5341  183.21  5361.2  182.52  5418.8  182.81  5450.1  183.09  5456.4  180.63
  5464.5  182.65  5470.9  183.05  5609.7  184.66    5728  186.68    5780  187.12
#Mann= 7 ,-1 , 0
    4598      .1       0  4828.5     .12       0  4969.8     .07       0
  5023.5     .12       0  5418.8      .1       0  5609.7     .12       0
    5728      .1       0
#XS Ineff= 2 , 0
                         5212.15          183.18
Permanent Ineff=
       F       F
Bank Sta=4969.8,5023.5
XS Rating Curve= 0 ,0
Exp/Cntr=0.3,0.1

Chan Stop Cuts=-1
Use User Specified Reach Order=0
Composite Channel Slope=5