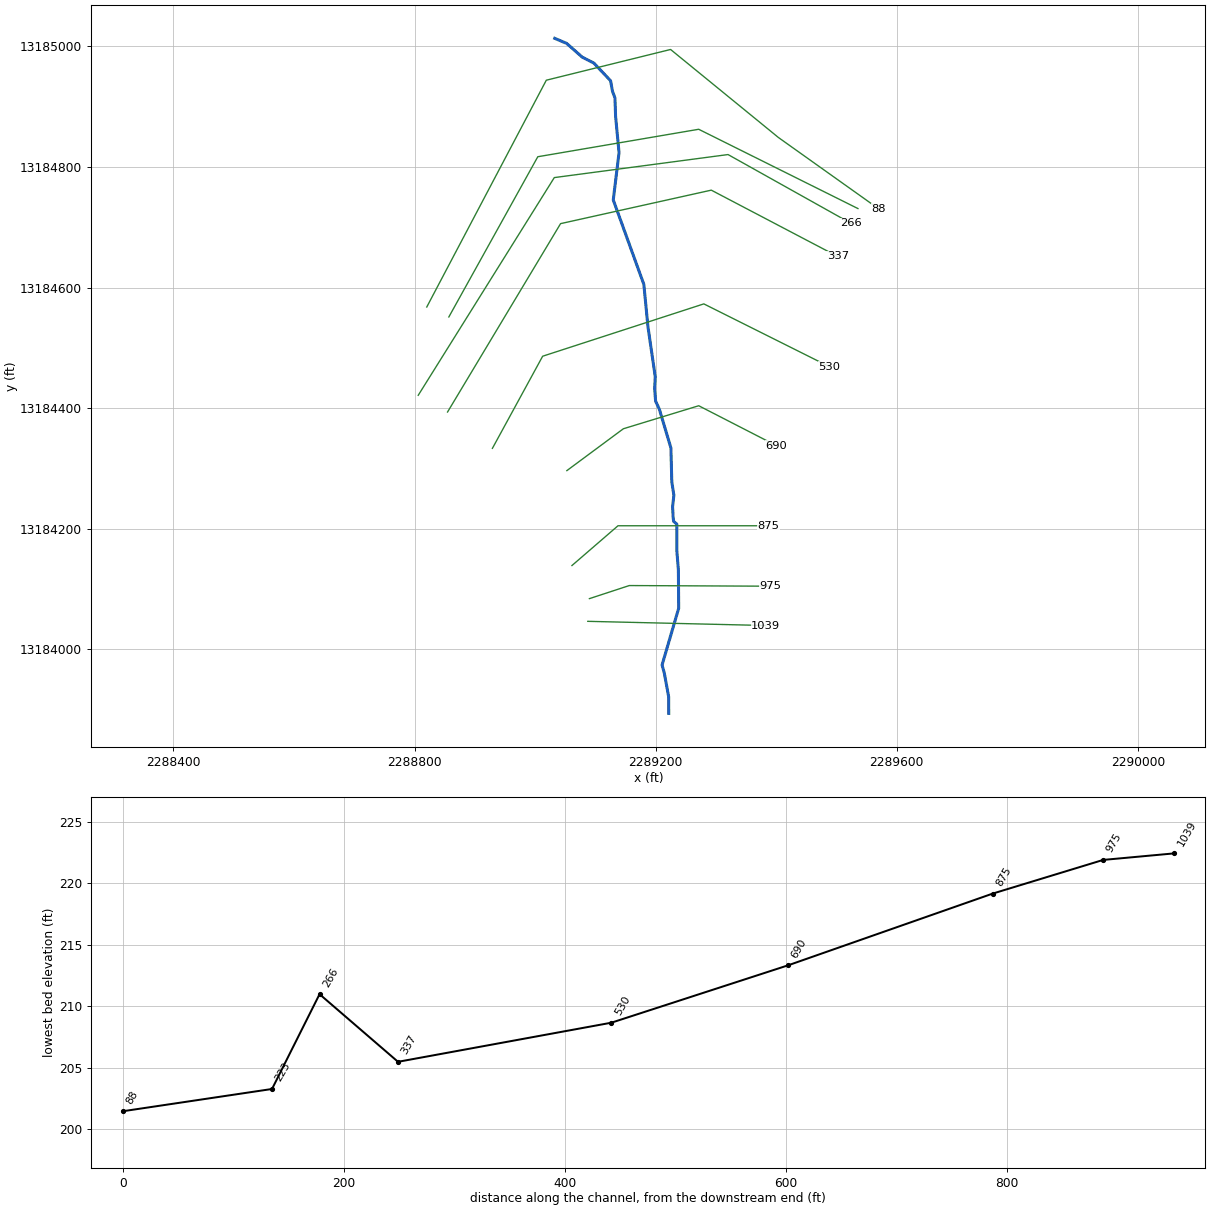
--- UNT143 IN PECR.prj (project) ---

Proj Title=UNT143 IN PECR Base Level Engineering
Current Plan=p01
Default Exp/Contr=0.3,0.1
English Units
Geom File=g01
Flow File=f01
Plan File=p01
Y Axis Title=Elevation
X Axis Title(PF)=Main Channel Distance
X Axis Title(XS)=Station
BEGIN DESCRIPTION:
UNT143 IN PECR
END DESCRIPTION:
DSS Export Rating Curves= 0
DSS Export Rating Curve Sorted= 0
DSS Export Volume Flow Curves= 0
DXF OffsetX= 0
DXF OffsetY= 0
DXF ScaleX= 1
DXF ScaleY= 10

--- UNT143 IN PECR.p01 (plan) ---

Plan Title=Multiple Run
Short Identifier=Multiple
Geom File=g01
Flow File=f01
Subcritical Flow
K Sum by GR= 0
Std Step Tol= 0.01
Critical Tol= 0.01
Num of Std Step Trials= 20
Max Error Tol= 0.3
Flow Tol Ratio= 0.001
Split Flow NTrial= 30
Split Flow Tol= 0.02
Split Flow Ratio= 0.02
Log Output Level= 0
Friction Slope Method= 1
Unsteady Friction Slope Method= 2
Unsteady Bridges Friction Slope Method= 1
Parabolic Critical Depth
Global Vel Dist=  1 , 1 , 1
Global Log Level= 0
CheckData=True
Encroach Param= -1, 0, 0, 0
BEGIN DESCRIPTION:
Multiple Run
END DESCRIPTION:

--- UNT143 IN PECR.f01 (steady flow) ---

Flow Title=Multiple
Program Version=4.10
Number of Profiles= 7
Profile Names=10-year,25-year,50-year,1pct_min,100-year,1pct_plu,500-year
River Rch & RM=UNT143 IN PECR,Reach-1         ,1039
      38      47      53      44      60      81      78
Boundary for River Rch & Prof#=UNT143 IN PECR,Reach-1         , 1
Up Type= 0
Dn Type= 3
Dn Slope=0.0133
Boundary for River Rch & Prof#=UNT143 IN PECR,Reach-1         , 2
Up Type= 0
Dn Type= 3
Dn Slope=0.0133
Boundary for River Rch & Prof#=UNT143 IN PECR,Reach-1         , 3
Up Type= 0
Dn Type= 3
Dn Slope=0.0133
Boundary for River Rch & Prof#=UNT143 IN PECR,Reach-1         , 4
Up Type= 0
Dn Type= 3
Dn Slope=0.0133
Boundary for River Rch & Prof#=UNT143 IN PECR,Reach-1         , 5
Up Type= 0
Dn Type= 3
Dn Slope=0.0133
Boundary for River Rch & Prof#=UNT143 IN PECR,Reach-1         , 6
Up Type= 0
Dn Type= 3
Dn Slope=0.0133
Boundary for River Rch & Prof#=UNT143 IN PECR,Reach-1         , 7
Up Type= 0
Dn Type= 3
Dn Slope=0.0133
DSS Import GetInterval= 0
DSS Import GetPeak= 0
DSS Import FillOption= 0

--- UNT143 IN PECR.g01 (geometry) ---

Geom Title=Existing Conditions
Program Version=4.10

River Reach=UNT143 IN PECR  ,Reach-1
Reach XY= 30
      2289221.69     13183893.63      2289221.53     13183921.23
      2289214.24     13183960.81      2289210.59     13183973.83
       2289238.2     13184068.11      2289237.68     13184131.13
      2289235.07     13184163.94      2289235.07      13184207.5
      2289229.79     13184212.25      2289228.93     13184219.08
      2289228.06     13184236.45      2289230.19     13184255.34
      2289226.74       13184278.      2289225.28     13184333.92
      2289206.14     13184398.07      2289199.93     13184411.34
      2289198.24     13184432.44      2289199.28     13184452.19
      2289187.16     13184535.29      2289180.36     13184605.31
      2289129.64     13184745.35      2289139.24     13184823.83
      2289133.51     13184883.73      2289132.47     13184914.46
       2289128.3     13184925.92      2289125.18     13184943.11
      2289097.57     13184972.27       2289078.3     13184982.17
      2289052.26     13185005.08      2289032.54     13185013.43

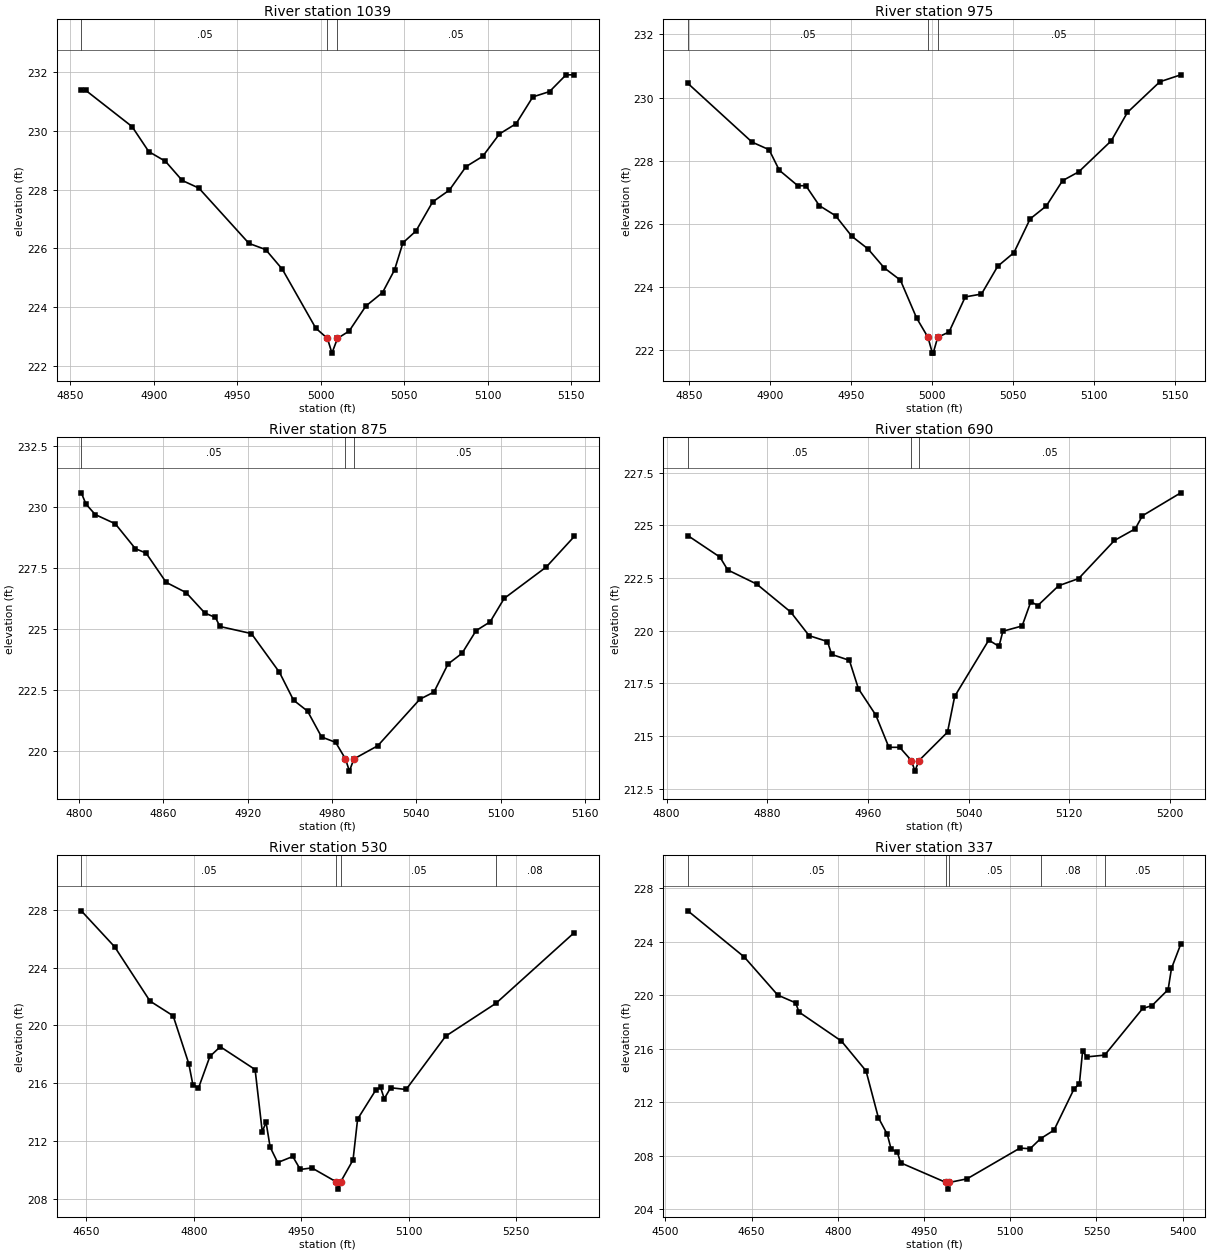
Type RM Length L Ch R = 1 ,1039    ,64,64,64
BEGIN DESCRIPTION:
UNT143 IN PECR 2.0
END DESCRIPTION:
XS GIS Cut Line= 2
      2289087.37     13184046.32      2289382.49     13184039.38
#Sta/Elev= 30
  4856.5  231.37  4859.2  231.37  4886.9  230.14  4896.9  229.29  4906.9  228.96
  4916.9  228.31  4926.9  228.05  4956.9  226.17  4966.9  225.96  4976.9  225.29
  4996.9  223.29  5003.9  222.94  5006.6  222.44  5009.9  222.94  5016.9  223.19
  5026.9  224.04  5036.9   224.5  5044.1  225.27  5049.1  226.19  5056.9  226.59
  5066.9  227.58  5076.9  227.98  5086.9  228.78  5096.9  229.13  5106.9  229.89
  5116.9  230.24  5126.9  231.15  5136.9  231.33  5146.8   231.9  5151.7   231.9
#Mann= 3 ,-1 , 0
  4856.5     .05       0  5003.9    .035       0  5009.9     .05       0
Bank Sta=5003.9,5009.9
XS Rating Curve= 0 ,0
Exp/Cntr=0.3,0.1

Type RM Length L Ch R = 1 ,975     ,100,100,100
BEGIN DESCRIPTION:
Mapping XS eb81beee
END DESCRIPTION:
XS GIS Cut Line= 3
      2289090.11     13184083.98      2289156.27     13184105.67
      2289390.64     13184104.59
#Sta/Elev= 30
  4849.4  230.45    4889  228.59  4899.5  228.35  4905.8   227.7  4917.2  227.21
  4922.2  227.21  4930.5  226.58  4940.5  226.26  4950.5  225.61  4960.5  225.21
  4970.5  224.61  4980.5  224.22  4990.5  223.02  4997.5  222.41  5000.2  221.91
  5000.7  221.91  5003.5  222.41  5010.5  222.58  5020.5  223.69  5030.5  223.78
  5040.5  224.66  5050.5  225.09  5060.5  226.16  5070.5  226.57  5080.5  227.37
  5090.5  227.65  5110.5  228.63  5120.5  229.53  5140.5   230.5  5153.4  230.72
#Mann= 3 ,-1 , 0
  4849.4     .05       0  4997.5    .035       0  5003.5     .05       0
Bank Sta=4997.5,5003.5
XS Rating Curve= 0 ,0
Exp/Cntr=0.3,0.1

Type RM Length L Ch R = 1 ,875     ,185,185,185
BEGIN DESCRIPTION:
Mapping XS eb81bee
END DESCRIPTION:
XS GIS Cut Line= 3
      2289061.12     13184138.87      2289137.53     13184204.86
      2289387.57     13184204.86
#Sta/Elev= 30
  4801.5  230.58  4804.8  230.12  4811.4  229.69  4825.7  229.31    4840  228.29
  4847.6  228.11  4861.9  226.91  4876.1  226.49  4889.5  225.65    4897  225.47
  4900.2   225.1  4922.6  224.81  4942.6  223.22  4952.6  222.08  4962.6  221.63
  4972.6  220.57  4982.6  220.35  4989.6  219.67  4992.4  219.17  4995.6  219.67
  5012.6  220.21  5042.6  222.12  5052.6  222.41  5062.6  223.56  5072.6     224
  5082.6  224.93  5092.6  225.29  5102.6  226.25  5132.6  227.54  5152.5  228.79
#Mann= 3 ,-1 , 0
  4801.5     .05       0  4989.6    .035       0  4995.6     .05       0
Bank Sta=4989.6,4995.6
XS Rating Curve= 0 ,0
Exp/Cntr=0.3,0.1

Type RM Length L Ch R = 1 ,690     ,160,160,160
BEGIN DESCRIPTION:
Mapping XS 6dced29e
END DESCRIPTION:
XS GIS Cut Line= 4
       2289052.7     13184296.34      2289146.42     13184365.77
      2289271.42     13184403.96      2289399.93     13184337.97
#Sta/Elev= 30
  4816.9  224.52  4842.4   223.5  4848.6  222.89  4871.6  222.22  4898.7  220.89
  4913.3  219.77  4927.9  219.49  4931.2  218.88  4945.3   218.6  4952.5  217.25
  4966.3     216  4976.7  214.47  4985.3  214.47  4994.6  213.84  4997.4  213.34
  5000.6  213.84  5023.3  215.19    5029  216.89  5056.1  219.56  5064.2  219.26
  5067.3  219.98  5082.6  220.23  5089.5  221.38  5095.1   221.2  5111.6  222.14
  5127.5  222.48    5156  224.29  5172.5  224.84  5178.2  225.46  5208.7  226.55
#Mann= 3 ,-1 , 0
  4816.9     .05       0  4994.6    .035       0  5000.6     .05       0
Bank Sta=4994.6,5000.6
XS Rating Curve= 0 ,0
Exp/Cntr=0.3,0.1

Type RM Length L Ch R = 1 ,530     ,193,193,193
BEGIN DESCRIPTION:
Mapping XS 9b4e494b
END DESCRIPTION:
XS GIS Cut Line= 4
      2288929.19     13184333.32      2289012.53     13184486.11
       2289279.9     13184572.92      2289488.25     13184468.74
#Sta/Elev= 30
  4643.1  227.94  4689.6  225.45    4739  221.69  4771.3  220.67  4793.1  217.36
  4798.8  215.91  4806.6  215.66  4822.6  217.86  4837.1  218.53  4885.7  216.95
  4895.7  212.65    4901   213.3  4906.7  211.58  4917.2  210.51  4938.3  210.93
  4948.8  210.03  4964.9  210.14  4999.1  209.17  5001.9  208.67  5005.1  209.17
  5022.4  210.69  5028.8  213.52  5053.9  215.51  5060.8  215.72    5066  214.93
  5074.9  215.69  5096.5  215.57  5151.7  219.26    5222  221.54  5331.2  226.43
#Mann= 4 ,-1 , 0
  4643.1     .05       0  4999.1    .035       0  5005.1     .05       0
    5222     .08       0
Bank Sta=4999.1,5005.1
XS Rating Curve= 0 ,0
Exp/Cntr=0.3,0.1

Type RM Length L Ch R = 1 ,337     ,71,71,71
BEGIN DESCRIPTION:
Mapping XS a0ad1832
END DESCRIPTION:
XS GIS Cut Line= 4
      2288854.74     13184393.53      2289042.25     13184706.04
      2289292.25      13184761.6      2289502.08     13184651.53
#Sta/Elev= 30
  4539.2   226.3  4637.3  222.85  4695.6     220  4726.7  219.42  4732.6  218.73
  4806.4  216.56  4849.2  214.33  4870.6  210.84  4886.1  209.59  4892.9  208.47
  4903.7  208.26  4909.3  207.46  4988.2  205.99    4991  205.49  4994.2  205.99
  5024.9  206.26    5117  208.56  5134.6  208.51  5152.7  209.26  5176.2   209.9
  5211.1  212.99  5220.3  213.36  5225.9  215.79  5233.7  215.38  5264.3  215.51
  5330.5     219  5346.6  219.21  5374.7  220.41  5380.5  221.99  5396.7  223.81
#Mann= 5 ,-1 , 0
  4539.2     .05       0  4988.2    .035       0  4994.2     .05       0
  5152.7     .08       0  5264.3     .05       0
Bank Sta=4988.2,4994.2
XS Rating Curve= 0 ,0
Exp/Cntr=0.3,0.1

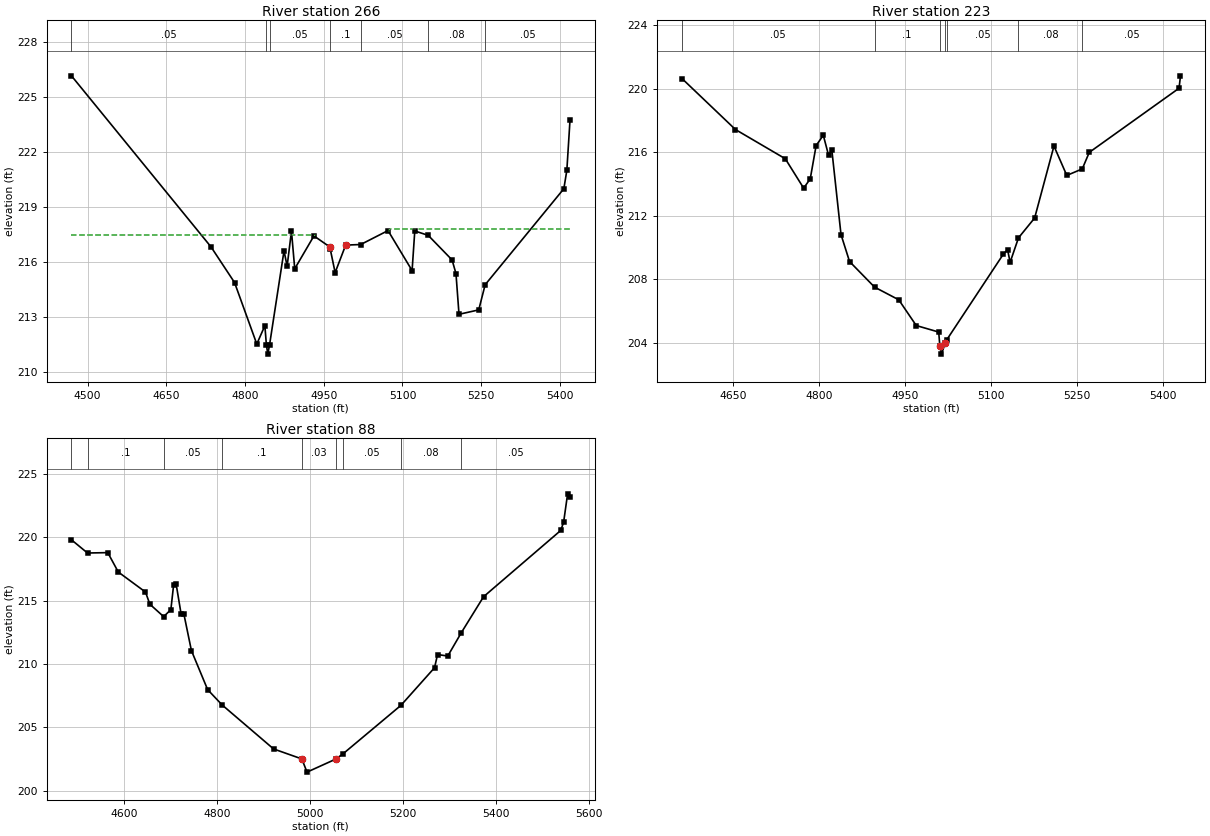
Type RM Length L Ch R = 1 ,266     ,43,43,43
BEGIN DESCRIPTION:
Mapping XS 457cbdc3
END DESCRIPTION:
XS GIS Cut Line= 4
      2288806.13      13184421.3      2289031.84     13184782.43
      2289320.03     13184820.63      2289523.84     13184706.63
#Sta/Elev= 30
  4469.2  226.15  4735.2  216.83    4780  214.89  4822.4  211.54  4837.8  212.54
  4840.7  211.49  4843.4  210.99  4846.7  211.49  4874.3  216.62  4880.2  215.78
  4888.5  217.69  4894.7  215.64  4931.3  217.43  4961.5  216.83  4962.5   216.7
  4971.7  215.43  4991.8  216.93  5020.4  216.96  5072.5  217.72  5118.4  215.54
  5123.5   217.7  5149.1  217.46  5194.6  216.12    5202  215.38  5207.8  213.16
  5245.4   213.4  5257.6  214.77  5407.6     220  5413.3     221  5419.3  223.72
#Mann= 7 ,-1 , 0
  4469.2     .05       0  4840.7     .07       0  4846.7     .05       0
  4962.5      .1       0  5020.4     .05       0  5149.1     .08       0
  5257.6     .05       0
#XS Ineff= 2 , 0
       0  4932.5  217.48 5073.64       0  217.82
Permanent Ineff=
       T       T
Bank Sta=4961.5,4991.8
XS Rating Curve= 0 ,0
Exp/Cntr=0.3,0.1

Type RM Length L Ch R = 1 ,223     ,135,135,135
BEGIN DESCRIPTION:
Mapping XS 457cb
END DESCRIPTION:
XS GIS Cut Line= 4
       2288856.9     13184551.21      2289004.45     13184817.01
      2289271.38     13184862.58      2289535.54     13184731.04
#Sta/Elev= 30
  4560.8  220.63  4654.1  217.42  4741.1  215.58  4773.1  213.73  4784.6  214.31
  4794.9  216.41  4807.4  217.06  4816.6   215.8  4822.3  216.13  4838.3  210.81
  4853.2  209.11  4896.8   207.5  4939.1   206.7  4969.6  205.08  5008.8  204.67
  5010.8  203.78  5013.6  203.28  5020.3  203.99  5022.8  204.18  5121.7  209.58
    5129  209.85  5133.4  209.06    5148   210.6  5176.2  211.85  5209.9  216.38
  5232.3  214.53  5259.3  214.94  5271.5  215.98  5428.2  220.02  5430.7   220.8
#Mann= 7 ,-1 , 0
  4560.8     .05       0  4896.8      .1       0  5010.8     .03       0
  5020.3      .1       0  5022.8     .05       0    5148     .08       0
  5259.3     .05       0
Bank Sta=5010.8,5020.3
XS Rating Curve= 0 ,0
Exp/Cntr=0.3,0.1

Type RM Length L Ch R = 1 ,88      ,0,0,0
BEGIN DESCRIPTION:
UNT143 IN PECR 1.0
END DESCRIPTION:
XS GIS Cut Line= 5
      2288820.27     13184567.73      2289018.56     13184943.96
      2289224.72     13184994.96      2289403.59     13184848.95
      2289569.59     13184730.83
#Sta/Elev= 30
  4486.3   219.8  4520.8  218.76  4564.4  218.79    4587  217.26  4645.5  215.68
  4654.9  214.72  4684.6  213.74  4700.1  214.29  4705.9   216.2  4711.5   216.3
  4722.3  213.91  4727.9  213.98  4744.3  211.06  4779.2  207.98  4810.4  206.77
    4921   203.3  4981.9  202.51  4992.9  201.47  5054.9   202.5  5070.6  202.92
    5195  206.74  5267.3  209.71  5273.7  210.75  5295.7  210.63  5324.8  212.47
  5372.7  215.31  5538.7  220.54  5544.9  221.19  5553.5  223.43  5558.6  223.18
#Mann= 9 ,-1 , 0
  4486.3     .05       0  4520.8      .1       0  4684.6     .05       0
  4810.4      .1       0  4981.9     .03       0  5054.9      .1       0
  5070.6     .05       0    5195     .08       0  5324.8     .05       0
Bank Sta=4981.9,5054.9
XS Rating Curve= 0 ,0
Exp/Cntr=0.3,0.1

Chan Stop Cuts=-1
Use User Specified Reach Order=0
Composite Channel Slope=5