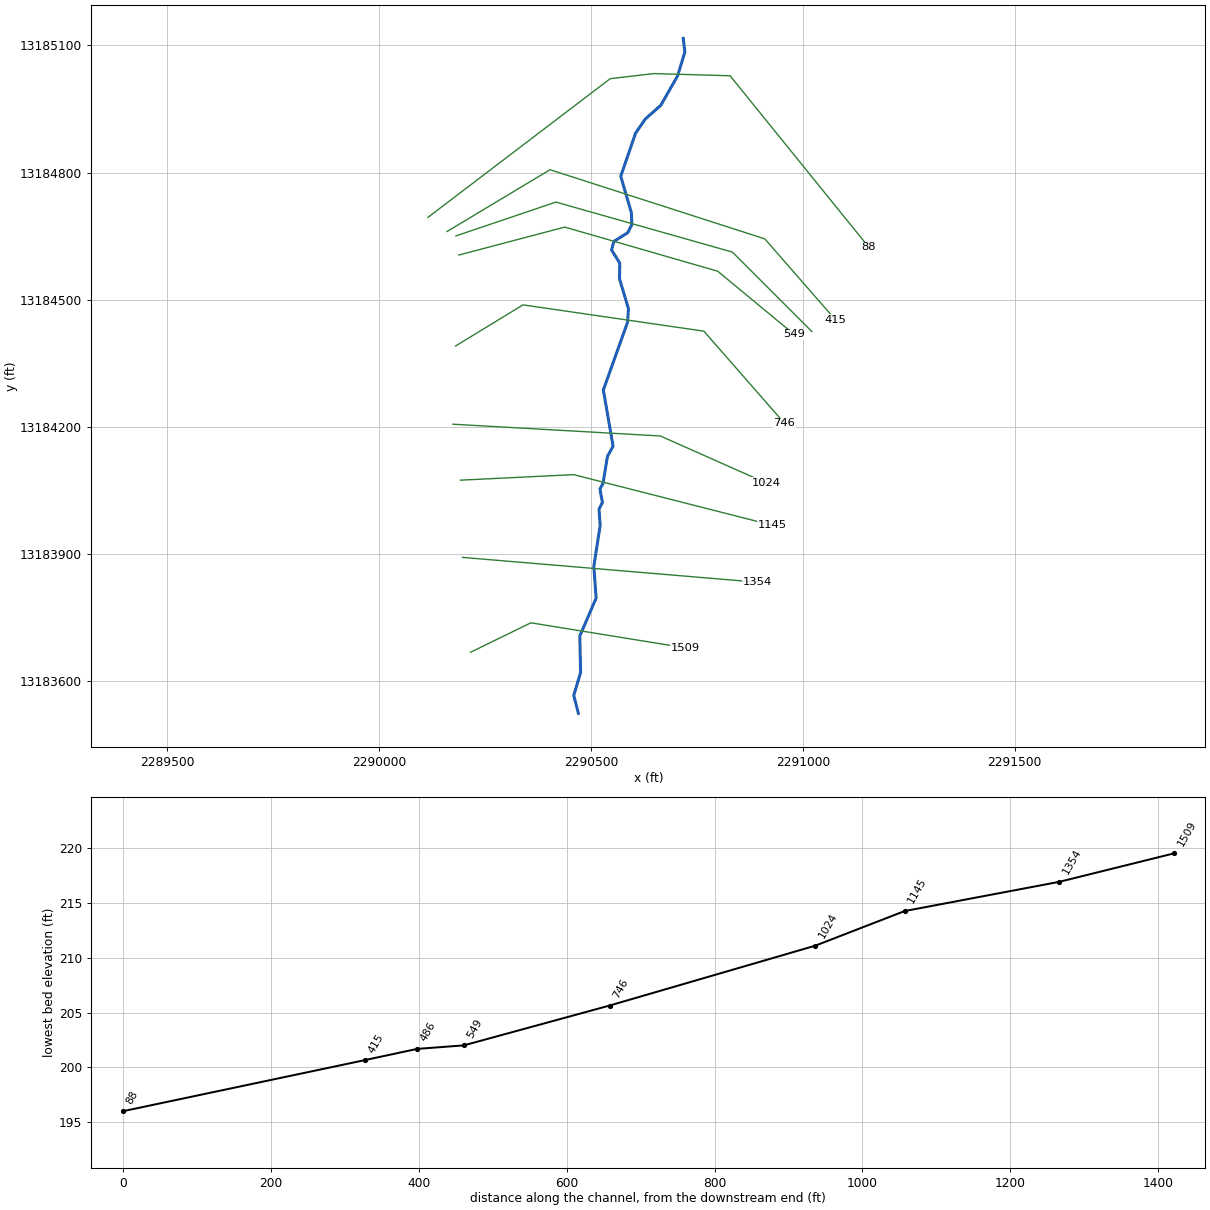
--- UNT223 IN PECR.prj (project) ---

Proj Title=UNT223 IN PECR Base Level Engineering
Current Plan=p01
Default Exp/Contr=0.3,0.1
English Units
Geom File=g01
Flow File=f01
Plan File=p01
Y Axis Title=Elevation
X Axis Title(PF)=Main Channel Distance
X Axis Title(XS)=Station
BEGIN DESCRIPTION:
UNT223 IN PECR
END DESCRIPTION:
DSS Export Rating Curves= 0
DSS Export Rating Curve Sorted= 0
DSS Export Volume Flow Curves= 0
DXF OffsetX= 0
DXF OffsetY= 0
DXF ScaleX= 1
DXF ScaleY= 10

--- UNT223 IN PECR.p01 (plan) ---

Plan Title=Multiple Run
Short Identifier=Multiple
Geom File=g01
Flow File=f01
Subcritical Flow
K Sum by GR= 0
Std Step Tol= 0.01
Critical Tol= 0.01
Num of Std Step Trials= 20
Max Error Tol= 0.3
Flow Tol Ratio= 0.001
Split Flow NTrial= 30
Split Flow Tol= 0.02
Split Flow Ratio= 0.02
Log Output Level= 0
Friction Slope Method= 1
Unsteady Friction Slope Method= 2
Unsteady Bridges Friction Slope Method= 1
Parabolic Critical Depth
Global Vel Dist=  1 , 1 , 1
Global Log Level= 0
CheckData=True
Encroach Param= -1, 0, 0, 0
BEGIN DESCRIPTION:
Multiple Run
END DESCRIPTION:

--- UNT223 IN PECR.f01 (steady flow) ---

Flow Title=Multiple
Program Version=4.10
Number of Profiles= 7
Profile Names=10-year,25-year,50-year,1pct_min,100-year,1pct_plu,500-year
River Rch & RM=UNT223 IN PECR,Reach-1         ,1509
      50      62      71      60      82     110     109
Boundary for River Rch & Prof#=UNT223 IN PECR,Reach-1         , 1
Up Type= 0
Dn Type= 3
Dn Slope=0.0143
Boundary for River Rch & Prof#=UNT223 IN PECR,Reach-1         , 2
Up Type= 0
Dn Type= 3
Dn Slope=0.0143
Boundary for River Rch & Prof#=UNT223 IN PECR,Reach-1         , 3
Up Type= 0
Dn Type= 3
Dn Slope=0.0143
Boundary for River Rch & Prof#=UNT223 IN PECR,Reach-1         , 4
Up Type= 0
Dn Type= 3
Dn Slope=0.0143
Boundary for River Rch & Prof#=UNT223 IN PECR,Reach-1         , 5
Up Type= 0
Dn Type= 3
Dn Slope=0.0143
Boundary for River Rch & Prof#=UNT223 IN PECR,Reach-1         , 6
Up Type= 0
Dn Type= 3
Dn Slope=0.0143
Boundary for River Rch & Prof#=UNT223 IN PECR,Reach-1         , 7
Up Type= 0
Dn Type= 3
Dn Slope=0.0143
DSS Import GetInterval= 0
DSS Import GetPeak= 0
DSS Import FillOption= 0

--- UNT223 IN PECR.g01 (geometry) ---

Geom Title=Existing Conditions
Program Version=4.10

River Reach=UNT223 IN PECR  ,Reach-1
Reach XY= 30
      2290470.31     13183523.52      2290459.37     13183565.83
      2290475.54     13183620.03      2290473.64     13183706.09
      2290512.15     13183795.48      2290506.75     13183870.79
      2290521.74     13183967.21      2290518.99     13184005.43
      2290526.98     13184021.17      2290521.24      13184052.9
      2290528.48     13184066.63      2290538.97     13184130.33
      2290552.21     13184154.06      2290529.23     13184286.96
      2290586.44     13184446.83      2290588.44     13184479.05
      2290567.45       13184549.      2290568.07     13184586.16
      2290548.66     13184617.36      2290554.03     13184637.58
      2290586.77     13184658.07      2290596.64     13184677.22
      2290595.33     13184705.38       2290570.3     13184791.31
      2290605.36     13184893.17      2290628.35      13184926.5
      2290664.76     13184958.69      2290704.53     13185028.22
      2290721.65     13185084.84      2290717.72     13185116.86

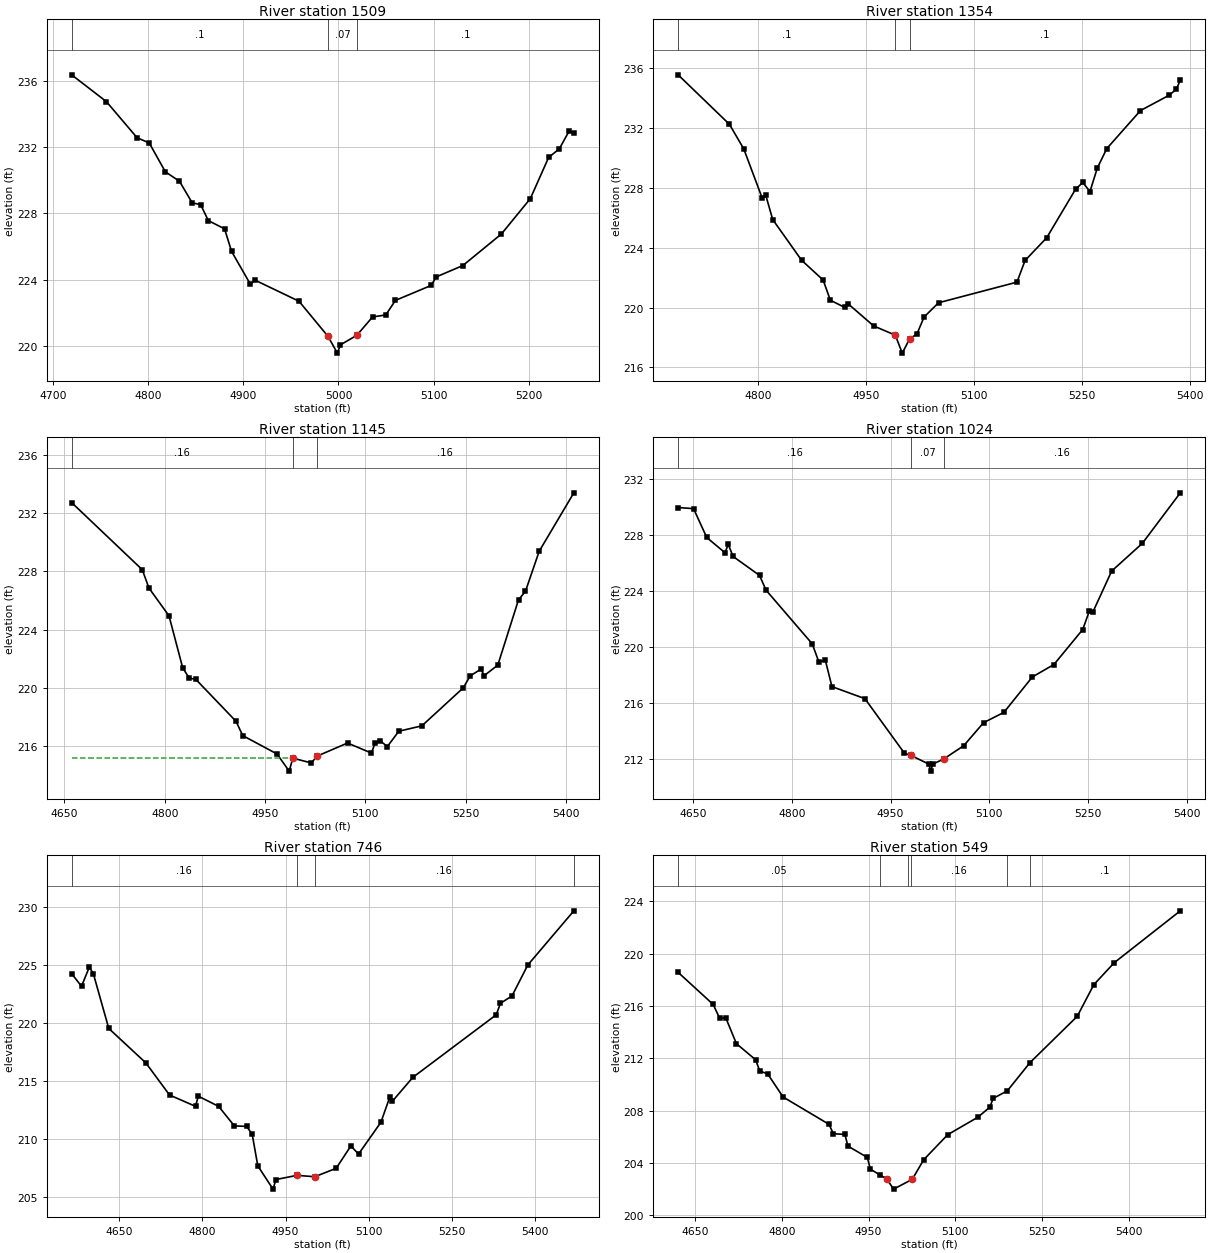
Type RM Length L Ch R = 1 ,1509    ,155,155,155
BEGIN DESCRIPTION:
UNT223 IN PECR 2.0
END DESCRIPTION:
XS GIS Cut Line= 3
      2290215.88     13183667.86      2290358.22     13183737.29
       2290722.8     13183678.27
#Sta/Elev= 30
  4719.6  236.39  4756.1  234.77  4788.4  232.58  4801.1  232.27  4818.1  230.52
  4832.9  229.95  4846.2  228.65  4855.2  228.53  4863.2  227.57  4880.3  227.07
  4887.6  225.71  4907.4  223.72  4912.5  223.96  4958.5  222.69  4988.9  220.57
  4998.8  219.55    5002  220.05  5019.3  220.63  5035.8  221.74  5049.7  221.86
  5059.8  222.74  5097.5  223.65  5102.6  224.16  5130.7  224.85  5171.2  226.76
  5201.6   228.9  5220.8  231.39    5232  231.91  5242.2  232.97  5247.3  232.86
#Mann= 3 ,-1 , 0
  4719.6      .1       0  4988.9     .07       0  5019.3      .1       0
Bank Sta=4988.9,5019.3
XS Rating Curve= 0 ,0
Exp/Cntr=0.3,0.1

Type RM Length L Ch R = 1 ,1354    ,209,209,209
BEGIN DESCRIPTION:
Mapping XS 08347e64
END DESCRIPTION:
XS GIS Cut Line= 2
      2290196.62      13183891.7      2290892.96     13183833.13
#Sta/Elev= 30
  4688.4  235.57  4759.8  232.26  4779.8  230.61  4805.4  227.32  4810.4  227.51
    4820  225.89  4860.1  223.17  4890.2  221.84  4900.2  220.49  4920.2  220.01
  4925.2  220.24  4960.5  218.77  4990.6  218.15  5000.3  216.95  5010.6  217.91
  5020.7  218.23  5030.7  219.37  5050.8  220.32  5159.9   221.7  5171.2  223.15
  5201.3  224.67  5241.4  227.91  5251.5  228.37  5261.5  227.76  5271.6  229.32
  5284.8  230.63  5331.8  233.18  5371.9  234.21  5381.9  234.62  5387.2  235.23
#Mann= 3 , 0 , 0
  4688.4      .1       0  4990.6     .07       0  5010.6      .1       0
Bank Sta=4990.6,5010.6
XS Rating Curve= 0 ,0
Exp/Cntr=0.3,0.1

Type RM Length L Ch R = 1 ,1145    ,121,121,121
BEGIN DESCRIPTION:
Mapping XS 08347e6
END DESCRIPTION:
XS GIS Cut Line= 3
      2290192.26     13184073.99      2290459.18     13184087.01
      2290927.88     13183967.67
#Sta/Elev= 30
  4660.8  232.72  4766.4  228.11  4776.4  226.85  4806.4  224.94  4826.8  221.38
  4836.5  220.67  4846.5  220.58  4906.6   217.7  4916.6  216.72  4967.8  215.46
  4986.1  214.28  4991.5  215.17  5019.4  214.84  5027.3   215.3  5073.3  216.21
  5109.1  215.52  5114.2  216.18  5122.6  216.34  5132.9  215.97    5150  217.02
  5184.5  217.39  5246.4     220  5256.7  220.82  5272.7  221.28  5277.8  220.84
    5298  221.56    5329  226.05  5339.3  226.62  5359.9  229.38  5411.7  233.39
#Mann= 3 , 0 , 0
  4660.8     .16       0  4991.5     .07       0  5027.3     .16       0
#XS Ineff= 2 , 0
       0 4991.46  215.18               0
Permanent Ineff=
       T       F
Bank Sta=4991.5,5027.3
XS Rating Curve= 0 ,0
Exp/Cntr=0.3,0.1

Type RM Length L Ch R = 1 ,1024    ,278,278,278
BEGIN DESCRIPTION:
Mapping XS a0c95206
END DESCRIPTION:
XS GIS Cut Line= 3
      2290174.25     13184206.04      2290663.78     13184178.27
      2290913.23      13184067.4
#Sta/Elev= 30
  4627.1  229.95  4650.6  229.87  4670.6  227.81  4698.3  226.72  4703.3  227.31
  4710.7  226.45  4750.8   225.1  4760.8  224.04  4830.9  220.21  4840.9  218.93
  4850.9  219.03  4860.9  217.15    4911  216.29  4971.1  212.39  4981.1  212.23
  5008.2  211.61  5010.9  211.11  5014.2  211.61  5031.2  211.99  5061.3  212.93
  5091.3  214.57  5122.3  215.31  5165.5  217.84  5198.3  218.73  5242.1  221.23
  5251.9  222.52  5257.4  222.47  5286.1  225.41  5332.7  227.39  5390.4     231
#Mann= 3 , 0 , 0
  4627.1     .16       0  4981.1     .07       0  5031.2     .16       0
Bank Sta=4981.1,5031.2
XS Rating Curve= 0 ,0
Exp/Cntr=0.3,0.1

Type RM Length L Ch R = 1 ,746     ,197,197,197
BEGIN DESCRIPTION:
Mapping XS 9b59b992
END DESCRIPTION:
XS GIS Cut Line= 4
      2290180.49     13184390.75      2290339.58     13184487.75
      2290766.48     13184425.66      2290956.64     13184208.33
#Sta/Elev= 30
  4563.9  224.25  4581.7  223.16  4595.8  224.82    4603  224.26  4630.9  219.52
  4697.9  216.54  4740.6  213.77  4787.5  212.79  4792.5  213.67  4829.2  212.79
  4857.6   211.1  4879.7  211.06  4889.8  210.38  4899.9  207.65  4927.4  205.64
  4932.7  206.47  4970.7  206.83  5002.8  206.71  5041.4  207.44  5067.9  209.37
  5081.8  208.67  5122.2  211.42    5138  213.57    5143  213.24  5179.7  215.29
  5330.3   220.7  5337.9  221.69  5358.8  222.33  5387.3     225  5470.4  229.68
#Mann= 4 ,-1 , 0
  4563.9     .16       0  4970.7     .07       0  5002.8     .16       0
  5470.4     .05       0
#XS Ineff= 2 , 0
       0  4970.3  206.82               0
Permanent Ineff=
       T       F
Bank Sta=4970.7,5002.8
XS Rating Curve= 0 ,0
Exp/Cntr=0.3,0.1

Type RM Length L Ch R = 1 ,549     ,63,63,63
BEGIN DESCRIPTION:
Mapping XS 11f29636
END DESCRIPTION:
XS GIS Cut Line= 4
      2290188.06     13184605.34      2290438.09     13184671.32
       2290799.2     13184567.15      2290979.74     13184417.86
#Sta/Elev= 30
  4620.5  218.56  4681.1  216.11  4692.5  215.04  4702.9  215.09  4721.4  213.11
  4754.6  211.88  4761.7  211.02  4775.3  210.81    4802  209.04  4881.5  206.95
  4889.1  206.23    4909  206.18  4914.2  205.29  4947.8  204.42    4953  203.53
  4970.1  203.07  4981.5  202.77  4993.2     202  5025.6  202.75  5045.2  204.24
  5086.9  206.16  5138.9  207.49  5159.7  208.26  5165.4  208.93    5190  209.51
  5229.1  211.66  5310.9   215.2  5339.5  217.61  5374.7  219.29  5489.2  223.26
#Mann= 6 ,-1 , 0
  4620.5     .05       0  4970.1     .16       0  5017.3     .07       0
  5023.3     .16       0    5190     .05       0  5229.1      .1       0
Bank Sta=4981.5,5025.6
XS Rating Curve= 0 ,0
Exp/Cntr=0.3,0.1

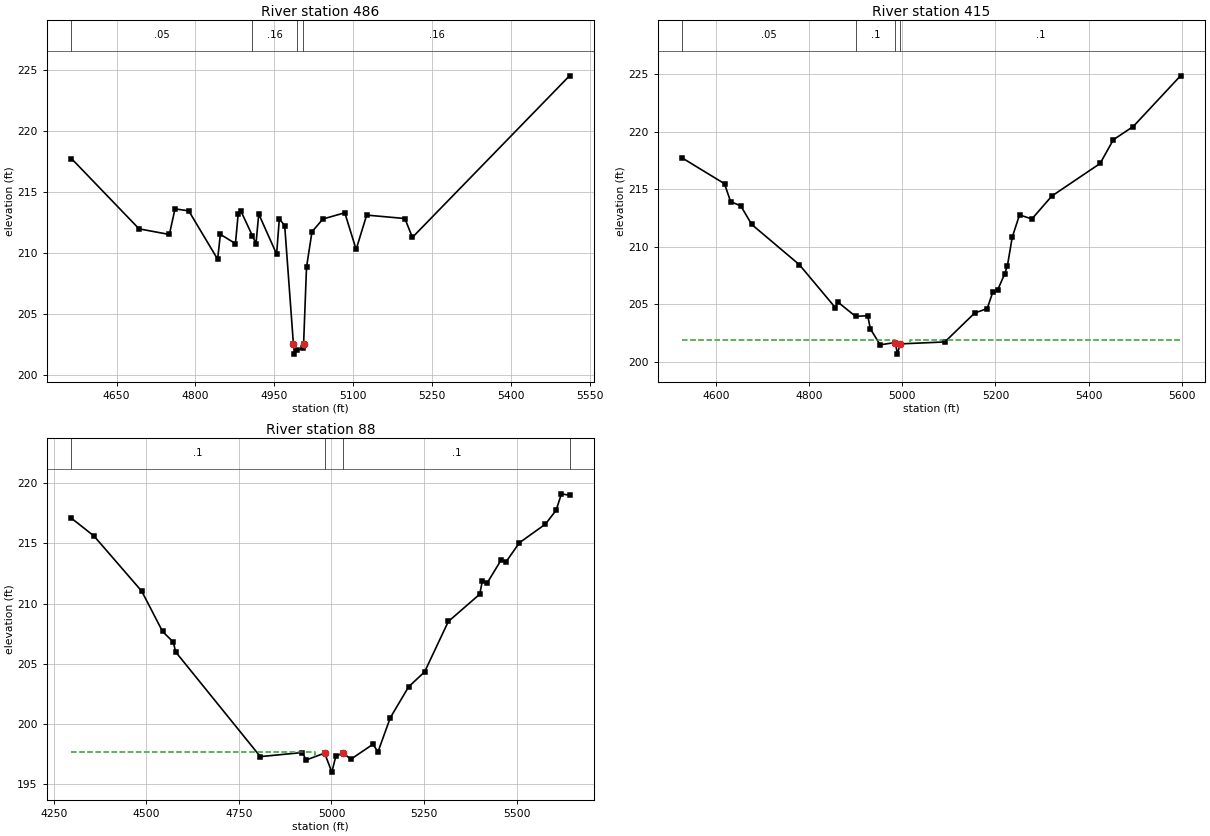
Type RM Length L Ch R = 1 ,486     ,71,71,71
BEGIN DESCRIPTION:
Mapping XS e6a58d2e
END DESCRIPTION:
XS GIS Cut Line= 4
      2290181.13     13184650.48      2290417.25     13184730.35
      2290833.92     13184612.29      2291021.42     13184424.79
#Sta/Elev= 30
    4564  217.73  4692.7  211.96  4750.3   211.5    4761   213.6  4787.1  213.44
  4842.1  209.47  4847.3  211.51    4876  210.75  4881.2   213.2  4886.5  213.41
  4908.4  211.38  4915.1  210.74  4920.3  213.18  4954.3  209.89  4959.5  212.79
  4969.7  212.22 4986.26  202.51  4988.2  201.68  4993.4  202.01  5005.3  202.17
 5005.65  202.52  5011.2  208.81  5021.6  211.72  5042.4  212.77    5084  213.28
  5105.6  210.27  5125.6  213.09  5198.3  212.81  5212.6  211.26  5511.5  224.52
#Mann= 4 ,-1 , 0
    4564     .05       0  4908.4     .16       0  4993.4     .07       0
  5005.3     .16       0
Bank Sta=4986.26,5005.65
XS Rating Curve= 0 ,0
Exp/Cntr=0.3,0.1

Type RM Length L Ch R = 1 ,415     ,327,327,327
BEGIN DESCRIPTION:
Mapping XS b24d2810
END DESCRIPTION:
XS GIS Cut Line= 4
      2290160.31     13184660.91      2290403.36     13184806.74
      2290910.31     13184643.54      2291076.99     13184452.56
#Sta/Elev= 30
  4527.8  217.71  4618.1  215.48  4631.2  213.92  4653.1  213.55  4676.4  211.94
  4778.9  208.43  4856.2  204.69  4861.5  205.18  4899.4  203.94  4925.6  203.99
  4931.4  202.84  4952.4  201.46 4984.67  201.66  4989.5  200.65    4995  201.54
  5091.2  201.71  5155.4  204.23  5182.2  204.61    5194  206.03  5204.5  206.22
  5219.5  207.61  5225.5  208.32    5236  210.83  5251.6  212.77  5278.1  212.41
    5321  214.41  5424.6  217.24  5453.1  219.31  5495.8  220.46  5597.3  224.87
#Mann= 4 ,-1 , 0
  4527.8     .05       0  4899.4      .1       0 4984.67     .03       0
    4995      .1       0
#XS Ineff= 2 , 0
       0 4983.74  201.92 5015.42       0  201.87
Permanent Ineff=
       T       T
Bank Sta=4984.67,4995
XS Rating Curve= 0 ,0
Exp/Cntr=0.3,0.1

Type RM Length L Ch R = 1 ,88      ,0,0,0
BEGIN DESCRIPTION:
UNT223 IN PECR 1.0
END DESCRIPTION:
XS GIS Cut Line= 5
      2290115.21     13184694.26      2290545.47     13185021.67
      2290648.32     13185033.67      2290828.31     13185028.53
      2291155.71     13184623.99
#Sta/Elev= 30
    4298   217.1  4358.9  215.62  4487.8  211.03    4544  207.68    4573   206.8
  4579.3  205.98    4808  197.27  4921.5  197.61  4931.6  196.99  4981.6  197.56
    5001  195.98  5011.6  197.28  5031.6   197.6  5051.7  197.04  5111.7  198.29
  5125.8  197.68  5158.8   200.5  5208.4  203.08  5251.5  204.32  5315.5  208.51
  5400.3  210.78  5407.5  211.89  5421.1  211.75  5457.8  213.61  5471.8  213.49
  5507.4  215.06  5577.7  216.61  5606.5  217.76  5620.9  219.13  5642.7  219.01
#Mann= 4 ,-1 , 0
    4298      .1       0  4981.6     .05       0  5031.6      .1       0
  5642.7      .1       0
#XS Ineff= 2 , 0
       0 4954.44  197.67 5034.44       0   197.5
Permanent Ineff=
       T       T
Bank Sta=4981.6,5031.6
XS Rating Curve= 0 ,0
Exp/Cntr=0.3,0.1

Chan Stop Cuts=-1
Use User Specified Reach Order=0
Composite Channel Slope=5