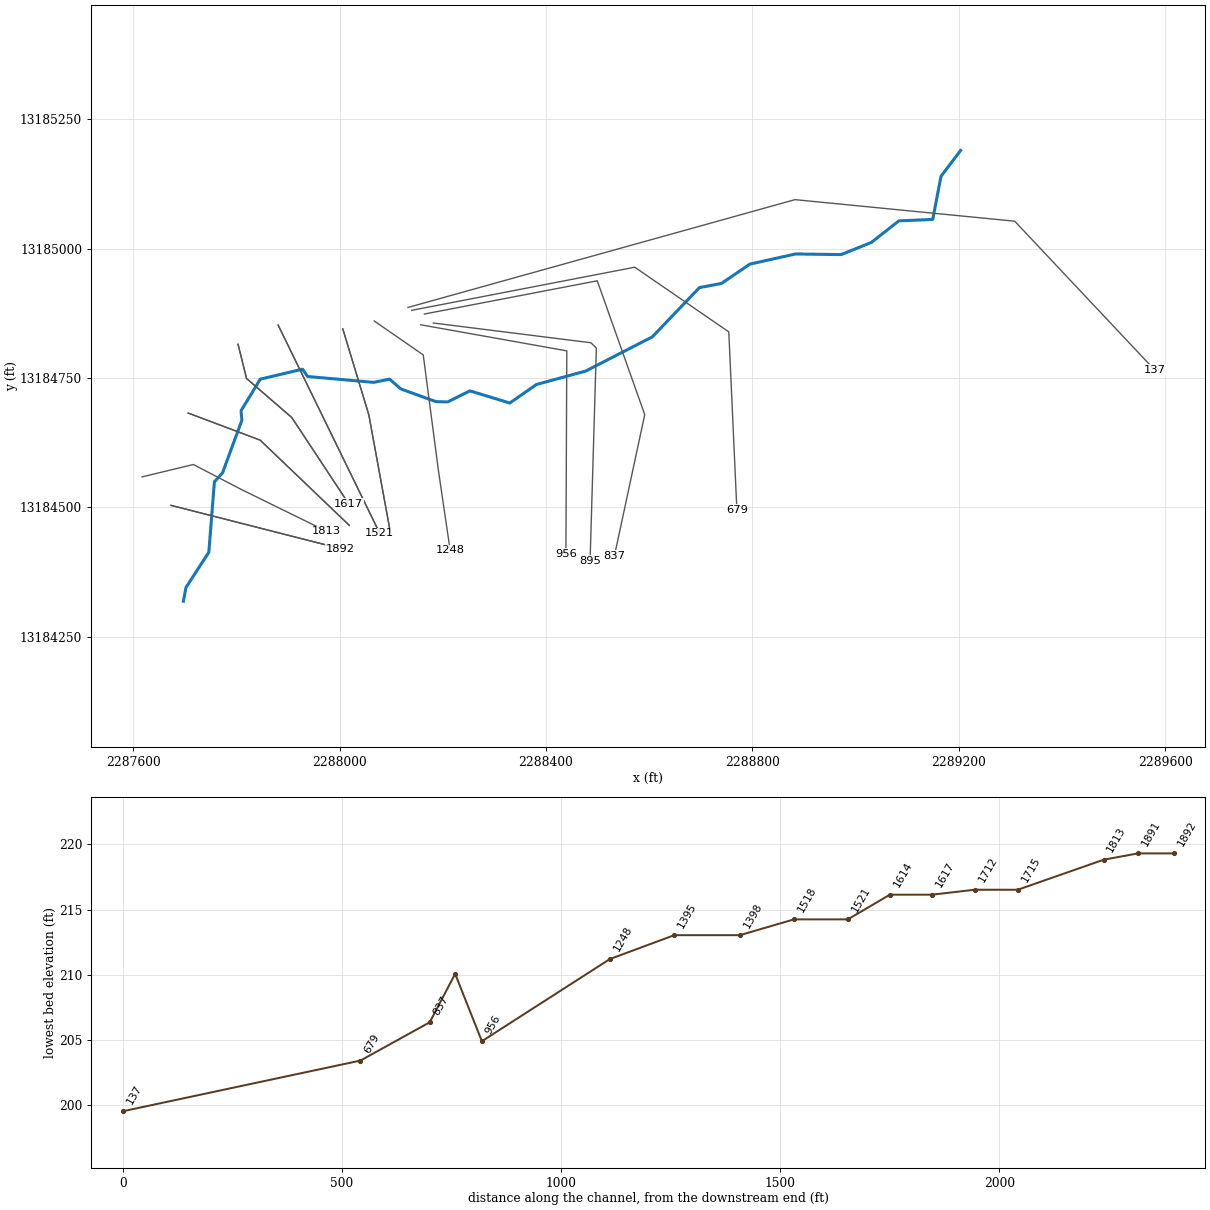
--- UNT283 IN PECR.prj (project) ---

Proj Title=UNT283 IN PECR Base Level Engineering
Current Plan=p01
Default Exp/Contr=0.3,0.1
English Units
Geom File=g01
Flow File=f01
Plan File=p01
Y Axis Title=Elevation
X Axis Title(PF)=Main Channel Distance
X Axis Title(XS)=Station
BEGIN DESCRIPTION:
UNT283 IN PECR
END DESCRIPTION:
DSS Export Rating Curves= 0
DSS Export Rating Curve Sorted= 0
DSS Export Volume Flow Curves= 0
DXF OffsetX= 0
DXF OffsetY= 0
DXF ScaleX= 1
DXF ScaleY= 10

--- UNT283 IN PECR.p01 (plan) ---

Plan Title=Multiple Run
Short Identifier=Multiple
Geom File=g01
Flow File=f01
Subcritical Flow
K Sum by GR= 0
Std Step Tol= 0.01
Critical Tol= 0.01
Num of Std Step Trials= 20
Max Error Tol= 0.3
Flow Tol Ratio= 0.001
Split Flow NTrial= 30
Split Flow Tol= 0.02
Split Flow Ratio= 0.02
Log Output Level= 0
Friction Slope Method= 1
Unsteady Friction Slope Method= 2
Unsteady Bridges Friction Slope Method= 1
Parabolic Critical Depth
Global Vel Dist=  1 , 1 , 1
Global Log Level= 0
CheckData=True
Encroach Param= -1, 0, 0, 0
BEGIN DESCRIPTION:
Multiple Run
END DESCRIPTION:

--- UNT283 IN PECR.f01 (steady flow) ---

Flow Title=Multiple
Program Version=4.10
Number of Profiles= 7
Profile Names=10-year,25-year,50-year,1pct_min,100-year,1pct_plu,500-year
River Rch & RM=UNT283 IN PECR,Reach-1         ,1892
      23      27      30      25      33      45      41
River Rch & RM=UNT283 IN PECR,Reach-1         ,137
      54      68      79      67      91     123     123
Boundary for River Rch & Prof#=UNT283 IN PECR,Reach-1         , 1
Up Type= 0
Dn Type= 3
Dn Slope=0.0072
Boundary for River Rch & Prof#=UNT283 IN PECR,Reach-1         , 2
Up Type= 0
Dn Type= 3
Dn Slope=0.0072
Boundary for River Rch & Prof#=UNT283 IN PECR,Reach-1         , 3
Up Type= 0
Dn Type= 3
Dn Slope=0.0072
Boundary for River Rch & Prof#=UNT283 IN PECR,Reach-1         , 4
Up Type= 0
Dn Type= 3
Dn Slope=0.0072
Boundary for River Rch & Prof#=UNT283 IN PECR,Reach-1         , 5
Up Type= 0
Dn Type= 3
Dn Slope=0.0072
Boundary for River Rch & Prof#=UNT283 IN PECR,Reach-1         , 6
Up Type= 0
Dn Type= 3
Dn Slope=0.0072
Boundary for River Rch & Prof#=UNT283 IN PECR,Reach-1         , 7
Up Type= 0
Dn Type= 3
Dn Slope=0.0072
DSS Import GetInterval= 0
DSS Import GetPeak= 0
DSS Import FillOption= 0

--- UNT283 IN PECR.g01 (geometry) ---

Geom Title=Existing Conditions
Program Version=4.10

River Reach=UNT283 IN PECR  ,Reach-1
Reach XY= 30
       2287697.1     13184318.73       2287702.2     13184345.38
      2287746.43     13184413.43      2287757.21     13184549.52
      2287773.08      13184567.1      2287810.51      13184668.6
      2287808.81     13184686.74      2287846.23     13184747.98
      2287927.89     13184767.26      2287938.09     13184753.09
      2288065.68     13184741.75      2288096.86     13184747.98
      2288118.61     13184729.01      2288186.81     13184704.48
      2288209.34     13184703.92      2288252.49     13184725.35
       2288329.7     13184701.84      2288381.44      13184737.6
      2288476.92     13184763.64      2288606.12     13184829.76
      2288697.25     13184924.83      2288740.11     13184933.01
      2288795.04     13184970.29      2288883.65     13184989.92
      2288971.81     13184988.71      2289030.32     13185012.07
      2289083.88     13185053.91      2289149.49      13185056.7
       2289165.6     13185140.15      2289203.52     13185189.95

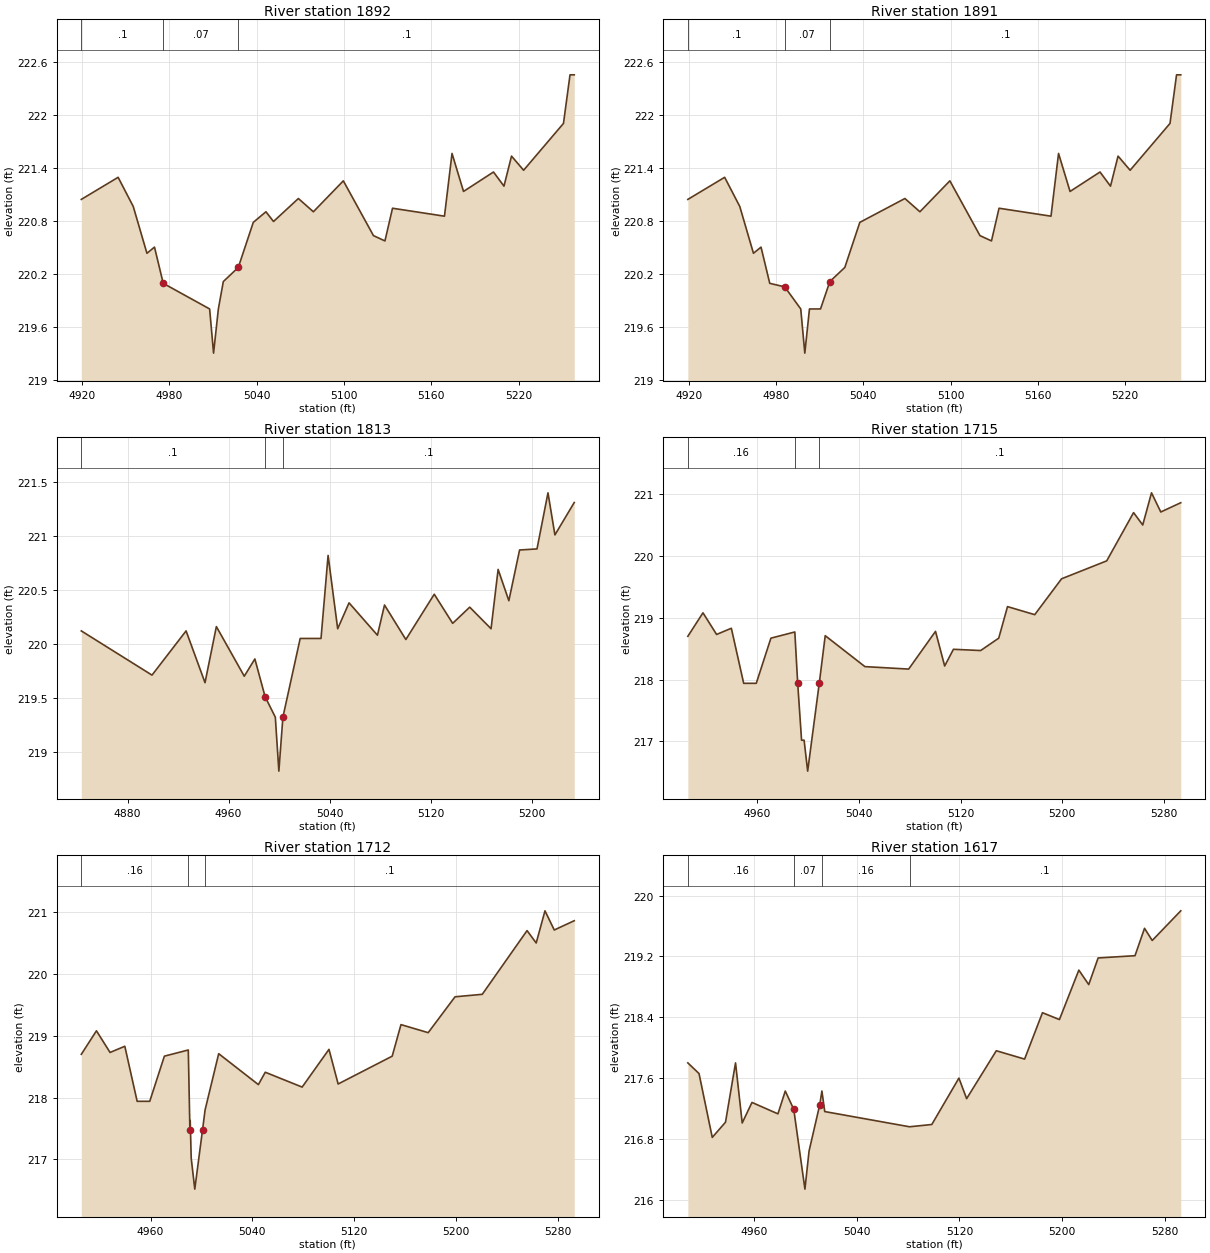
Type RM Length L Ch R = 1 ,1892    ,82,82,82
BEGIN DESCRIPTION:
UNT283 IN PECR 2.0
END DESCRIPTION:
XS GIS Cut Line= 2
      2287673.16     13184504.04      2288001.48     13184420.45
#Sta/Elev= 30
  4919.4  221.04  4944.7  221.29  4955.1  220.96  4964.5  220.43  4969.7   220.5
  4975.7  220.09  5007.6   219.8  5010.3   219.3  5013.6   219.8    5017  220.11
  5027.3  220.27  5037.6  220.78  5046.3   220.9  5051.5  220.79  5068.6  221.05
  5078.9   220.9  5099.5  221.25  5120.2  220.63  5128.1  220.57  5133.3  220.94
    5169  220.85  5174.2  221.56  5182.1  221.13  5202.7  221.35  5209.9  221.19
  5215.1  221.53  5223.4  221.37  5250.8   221.9  5255.3  222.45  5258.2  222.45
#Mann= 3 , 0 , 0
  4919.4      .1       0  4975.7     .07       0  5027.3      .1       0
Bank Sta=4975.7,5027.3
XS Rating Curve= 0 ,0
Exp/Cntr=0.3,0.1

Type RM Length L Ch R = 1 ,1891    ,78,78,78
BEGIN DESCRIPTION:
UNT283 IN PECR 2.0
END DESCRIPTION:
XS GIS Cut Line= 2
      2287673.16     13184504.04      2288001.48     13184420.45
#Sta/Elev= 30
  4919.4  221.04  4944.7  221.29  4955.1  220.96  4964.5  220.43  4969.7   220.5
  4975.7  220.09    4986  220.05    4997   219.8  4999.8   219.3    5003   219.8
  5010.6   219.8    5017  220.11  5027.3  220.27  5037.6  220.78  5068.6  221.05
  5078.9   220.9  5099.5  221.25  5120.2  220.63  5128.1  220.57  5133.3  220.94
    5169  220.85  5174.2  221.56  5182.1  221.13  5202.7  221.35  5209.9  221.19
  5215.1  221.53  5223.4  221.37  5250.8   221.9  5255.3  222.45  5258.2  222.45
#Mann= 3 , 0 , 0
  4919.4      .1       0    4986     .07       0    5017      .1       0
Bank Sta=4986,5017
XS Rating Curve= 0 ,0
Exp/Cntr=0.3,0.1

Type RM Length L Ch R = 1 ,1813    ,196,196,196
BEGIN DESCRIPTION:
Mapping XS 88d242
END DESCRIPTION:
XS GIS Cut Line= 4
        2287617.     13184559.09      2287716.41     13184582.96
      2287809.14     13184534.89      2287974.24     13184454.06
#Sta/Elev= 30
  4843.3  220.12  4899.3  219.71  4926.3  220.12  4941.3  219.64  4950.3  220.16
  4972.4   219.7  4980.8  219.86  4988.9  219.51    4997  219.32  4999.8  218.82
    5003  219.32  5016.7  220.05  5033.2  220.05  5038.8  220.82  5046.4  220.14
  5055.4  220.38  5077.9  220.08  5083.5  220.36  5100.4  220.04  5122.9  220.46
  5137.5  220.19    5151  220.34  5167.9  220.14  5173.5  220.69    5182   220.4
  5190.5  220.87  5204.3  220.88    5213   221.4  5218.5  221.01  5233.8  221.31
#Mann= 3 , 0 , 0
  4843.3      .1       0  4988.9     .07       0    5003      .1       0
Bank Sta=4988.9,5003
XS Rating Curve= 0 ,0
Exp/Cntr=0.3,0.1

Type RM Length L Ch R = 1 ,1715    ,98,98,98
BEGIN DESCRIPTION:
Mapping XS 88d242d5
END DESCRIPTION:
XS GIS Cut Line= 3
       2287706.6     13184682.35      2287845.91      13184630.1
      2288018.68     13184465.37
#Sta/Elev= 30
  4905.6   218.7  4917.5  219.08  4928.2  218.73  4939.8  218.83  4949.5  217.94
  4959.4  217.94  4970.9  218.67  4989.7  218.77 4991.93  217.95    4995  217.02
    4997  217.02  4999.8  216.52 5008.91  217.94  5013.6  218.71  5044.8  218.21
  5079.2  218.17  5100.3  218.78  5107.5  218.22  5114.4  218.49  5135.8  218.47
    5150  218.67  5156.9  219.18  5178.3  219.05  5199.4  219.63  5234.9  219.92
    5256   220.7  5263.2   220.5  5270.1  221.02  5277.4  220.71  5293.1  220.86
#Mann= 3 ,-1 , 0
  4905.6     .16       0  4989.7     .07       0 5008.91      .1       0
Bank Sta=4991.93,5008.91
XS Rating Curve= 0 ,0
Exp/Cntr=0.3,0.1

Type RM Length L Ch R = 1 ,1712    ,98,98,98
BEGIN DESCRIPTION:
Mapping XS 88d242d5
END DESCRIPTION:
XS GIS Cut Line= 3
       2287706.6     13184682.35      2287845.91      13184630.1
      2288018.68     13184465.37
#Sta/Elev= 30
  4905.6   218.7  4917.5  219.08  4928.2  218.73  4939.8  218.83  4949.5  217.94
  4959.4  217.94  4970.9  218.67  4989.7  218.77 4990.96  217.48  4991.2  217.63
    4992  217.02  4994.8  216.52 5000.91  217.48  5002.9   217.8  5013.6  218.71
  5044.8  218.21  5050.2  218.41  5079.2  218.17  5100.3  218.78  5107.5  218.22
    5150  218.67  5156.9  219.18  5178.3  219.05  5199.4  219.63  5220.8  219.67
    5256   220.7  5263.2   220.5  5270.1  221.02  5277.4  220.71  5293.1  220.86
#Mann= 3 ,-1 , 0
  4905.6     .16       0  4989.7     .07       0  5002.9      .1       0
Bank Sta=4990.96,5000.91
XS Rating Curve= 0 ,0
Exp/Cntr=0.3,0.1

Type RM Length L Ch R = 1 ,1617    ,96,96,96
BEGIN DESCRIPTION:
Mapping XS 88d2
END DESCRIPTION:
XS GIS Cut Line= 4
      2287803.07     13184815.25      2287819.55      13184749.3
      2287907.23     13184673.78      2288017.46     13184507.13
#Sta/Elev= 30
  4908.7   217.8  4917.4  217.66  4927.7  216.82    4938  217.02  4945.8   217.8
    4951  217.01  4958.6  217.28  4978.8  217.13  4984.5  217.43  4991.1  217.19
  4999.8  216.14    5003  216.64 5011.34  217.25    5013  217.43 5015.22  217.16
  5081.2  216.96  5098.5  216.99  5119.6   217.6  5125.6  217.33  5148.7  217.96
  5170.7  217.85  5184.6  218.46  5197.8  218.37  5212.9  219.02  5220.6  218.83
  5227.9  219.18  5256.6  219.21    5264  219.57    5270  219.41  5292.2   219.8
#Mann= 4 ,-1 , 0
  4908.7     .16       0  4991.1     .07       0    5013     .16       0
  5081.2      .1       0
Bank Sta=4991.1,5011.34
XS Rating Curve= 0 ,0
Exp/Cntr=0.3,0.1

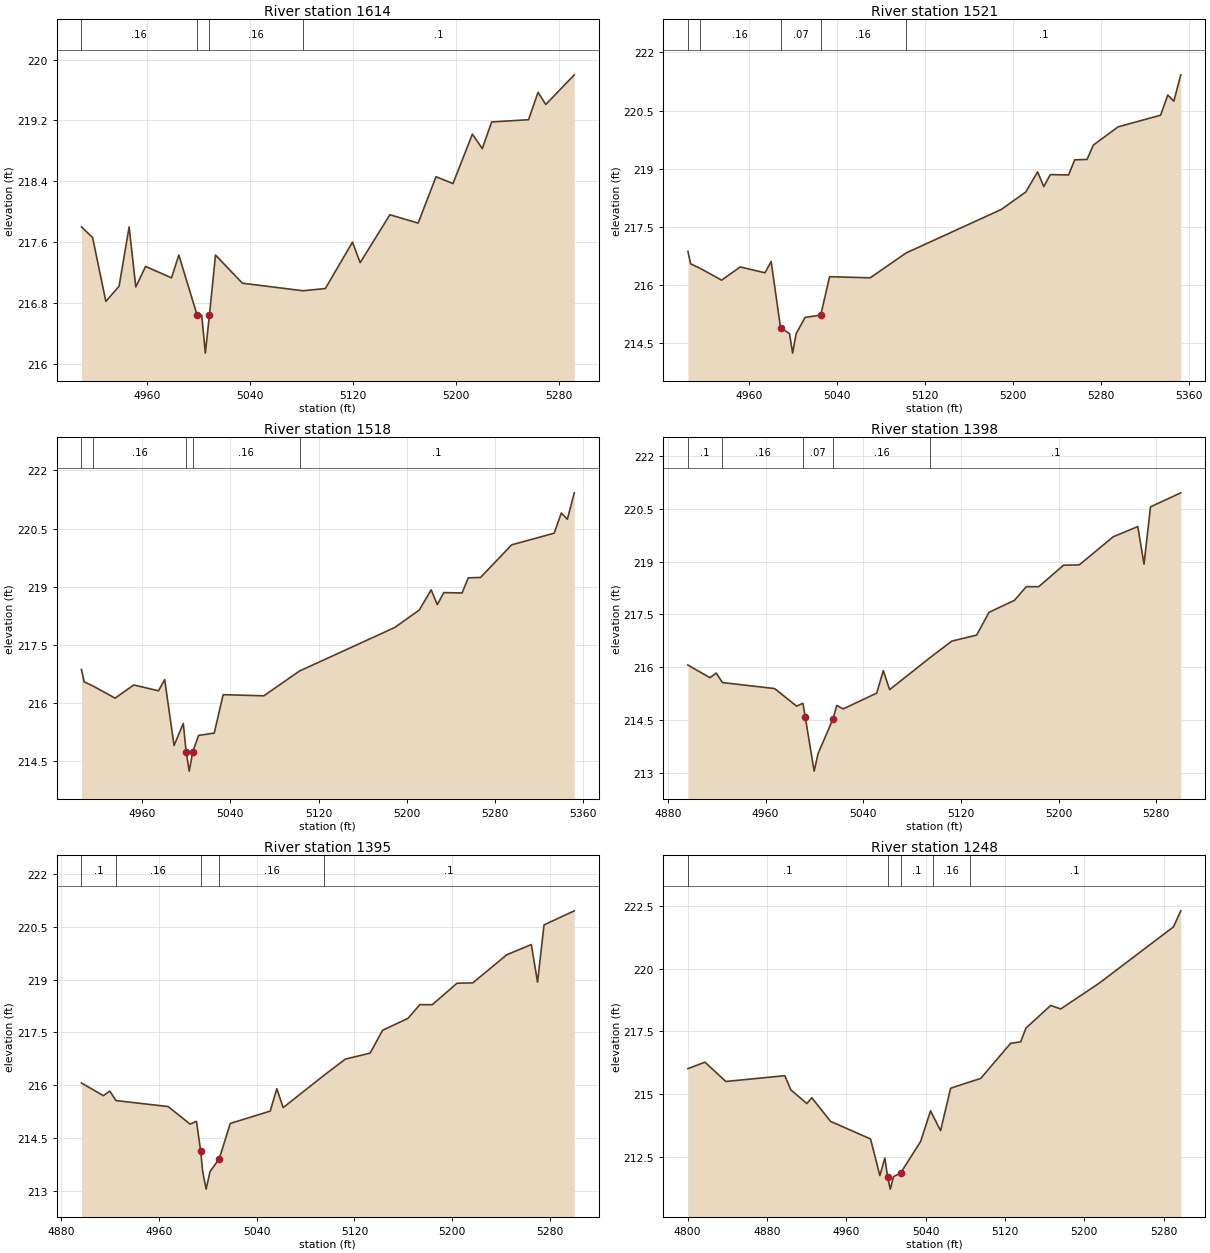
Type RM Length L Ch R = 1 ,1614    ,96,96,96
BEGIN DESCRIPTION:
Mapping XS 88d2
END DESCRIPTION:
XS GIS Cut Line= 4
      2287803.07     13184815.25      2287819.55      13184749.3
      2287907.23     13184673.78      2288017.46     13184507.13
#Sta/Elev= 30
  4908.7   217.8  4917.4  217.66  4927.7  216.82    4938  217.02  4945.8   217.8
    4951  217.01  4958.6  217.28  4978.8  217.13  4984.5  217.43  4998.7  216.64
  5002.3  216.64  5005.1  216.14  5008.3  216.64    5013  217.43  5033.9  217.06
  5081.2  216.96  5098.5  216.99  5119.6   217.6  5125.6  217.33  5148.7  217.96
  5170.7  217.85  5184.6  218.46  5197.8  218.37  5212.9  219.02  5220.6  218.83
  5227.9  219.18  5256.6  219.21    5264  219.57    5270  219.41  5292.2   219.8
#Mann= 4 ,-1 , 0
  4908.7     .16       0  4998.7     .07       0  5008.3     .16       0
  5081.2      .1       0
Bank Sta=4998.7,5008.3
XS Rating Curve= 0 ,0
Exp/Cntr=0.3,0.1

Type RM Length L Ch R = 1 ,1521    ,123,123,123
BEGIN DESCRIPTION:
Mapping XS aeba3f98
END DESCRIPTION:
XS GIS Cut Line= 2
       2287880.8     13184852.43      2288077.51     13184450.37
#Sta/Elev= 30
  4904.7  216.87  4907.2  216.55  4915.5  216.44  4935.3  216.13  4952.2  216.47
  4974.7  216.32  4980.3  216.61  4988.8  214.91    4997  214.75  4999.8  214.25
    5003  214.75  5011.1  215.17  5025.3  215.23  5033.4  216.22  5070.3  216.19
  5102.8  216.83  5189.2  217.95  5211.5   218.4  5222.3  218.92  5227.9  218.54
  5233.8  218.85  5250.4  218.84    5256  219.23  5267.2  219.24  5272.9  219.61
  5295.4  220.08    5334  220.38  5340.5   220.9    5346  220.74  5352.3  221.42
#Mann= 5 ,-1 , 0
  4904.7      .1       0  4915.5     .16       0  4988.8     .07       0
  5025.3     .16       0  5102.8      .1       0
Bank Sta=4988.8,5025.3
XS Rating Curve= 0 ,0
Exp/Cntr=0.3,0.1

Type RM Length L Ch R = 1 ,1518    ,123,123,123
BEGIN DESCRIPTION:
Mapping XS aeba3f98
END DESCRIPTION:
XS GIS Cut Line= 2
       2287880.8     13184852.43      2288077.51     13184450.37
#Sta/Elev= 30
  4904.7  216.87  4907.2  216.55  4915.5  216.44  4935.3  216.13  4952.2  216.47
  4974.7  216.32  4980.3  216.61  4988.8  214.91  4997.2  215.48  4999.8  214.75
  5002.6  214.25  5005.8  214.75  5011.1  215.17  5025.3  215.23  5033.4  216.22
  5070.3  216.19  5102.8  216.83  5189.2  217.95  5211.5   218.4  5222.3  218.92
  5227.9  218.54  5233.8  218.85  5250.4  218.84    5256  219.23  5267.2  219.24
  5295.4  220.08    5334  220.38  5340.5   220.9    5346  220.74  5352.3  221.42
#Mann= 5 ,-1 , 0
  4904.7      .1       0  4915.5     .16       0  4999.8     .07       0
  5005.8     .16       0  5102.8      .1       0
Bank Sta=4999.8,5005.8
XS Rating Curve= 0 ,0
Exp/Cntr=0.3,0.1

Type RM Length L Ch R = 1 ,1398    ,150,150,150
BEGIN DESCRIPTION:
Mapping XS 88
END DESCRIPTION:
XS GIS Cut Line= 3
      2288006.19     13184844.78      2288056.53     13184678.99
      2288098.19     13184452.46
#Sta/Elev= 30
  4896.4  216.06  4914.4   215.7  4919.6  215.83  4924.7  215.56  4967.4  215.39
  4985.4  214.89  4990.6  214.97 4992.54  214.57  4999.8  213.04    5003  213.54
 5015.28  214.53  5018.3  214.91  5023.5  214.81    5051  215.26  5056.4   215.9
  5061.6  215.36  5094.7  216.27  5112.5  216.74  5132.8  216.91    5143  217.56
  5163.8   217.9  5173.5  218.29  5183.7  218.29    5204   218.9  5216.9  218.91
  5244.7  219.71  5264.8     220  5269.9  218.93  5275.2  220.56    5300  220.96
#Mann= 5 ,-1 , 0
  4896.4      .1       0  4924.7     .16       0  4990.6     .07       0
 5015.28     .16       0  5094.7      .1       0
Bank Sta=4992.54,5015.28
XS Rating Curve= 0 ,0
Exp/Cntr=0.3,0.1

Type RM Length L Ch R = 1 ,1395    ,147,147,147
BEGIN DESCRIPTION:
Mapping XS 88
END DESCRIPTION:
XS GIS Cut Line= 3
      2288006.19     13184844.78      2288056.53     13184678.99
      2288098.19     13184452.46
#Sta/Elev= 30
  4896.4  216.06  4914.4   215.7  4919.6  215.83  4924.7  215.56  4967.4  215.39
  4985.4  214.89  4990.6  214.97 4994.06  214.12  4995.7  213.54  4998.5  213.04
  5001.7  213.54  5009.2   213.9  5018.3  214.91    5051  215.26  5056.4   215.9
  5061.6  215.36  5094.7  216.27  5112.5  216.74  5132.8  216.91    5143  217.56
  5163.8   217.9  5173.5  218.29  5183.7  218.29    5204   218.9  5216.9  218.91
  5244.7  219.71  5264.8     220  5269.9  218.93  5275.2  220.56    5300  220.96
#Mann= 5 ,-1 , 0
  4896.4      .1       0  4924.7     .16       0 4994.06     .07       0
  5009.2     .16       0  5094.7      .1       0
Bank Sta=4994.06,5009.2
XS Rating Curve= 0 ,0
Exp/Cntr=0.3,0.1

Type RM Length L Ch R = 1 ,1248    ,292,292,292
BEGIN DESCRIPTION:
Mapping XS 0a9aaa26
END DESCRIPTION:
XS GIS Cut Line= 4
      2288066.88     13184860.47      2288161.98     13184794.84
      2288191.45     13184571.18      2288214.21     13184417.19
#Sta/Elev= 30
  4800.4  216.01  4817.6  216.27  4838.6   215.5  4898.1  215.73  4904.1  215.17
  4920.3  214.62  4925.3  214.85  4944.2  213.91  4984.5  213.21  4993.9  211.75
  4998.9  212.45  5001.7  211.71  5004.4  211.21  5007.7  211.71  5014.8  211.85
    5035  213.11    5045  214.33  5047.5  214.13  5055.1  213.54  5065.2  215.23
  5084.4  215.48  5095.5  215.62  5125.7  217.02  5135.8  217.08  5141.2  217.63
  5166.1  218.53  5176.2  218.39  5215.1  219.42  5289.8  221.66  5297.2   222.3
#Mann= 5 ,-1 , 0
  4800.4      .1       0  5001.7     .07       0  5014.8      .1       0
  5047.5     .16       0  5084.4      .1       0
Bank Sta=5001.7,5014.8
XS Rating Curve= 0 ,0
Exp/Cntr=0.3,0.1

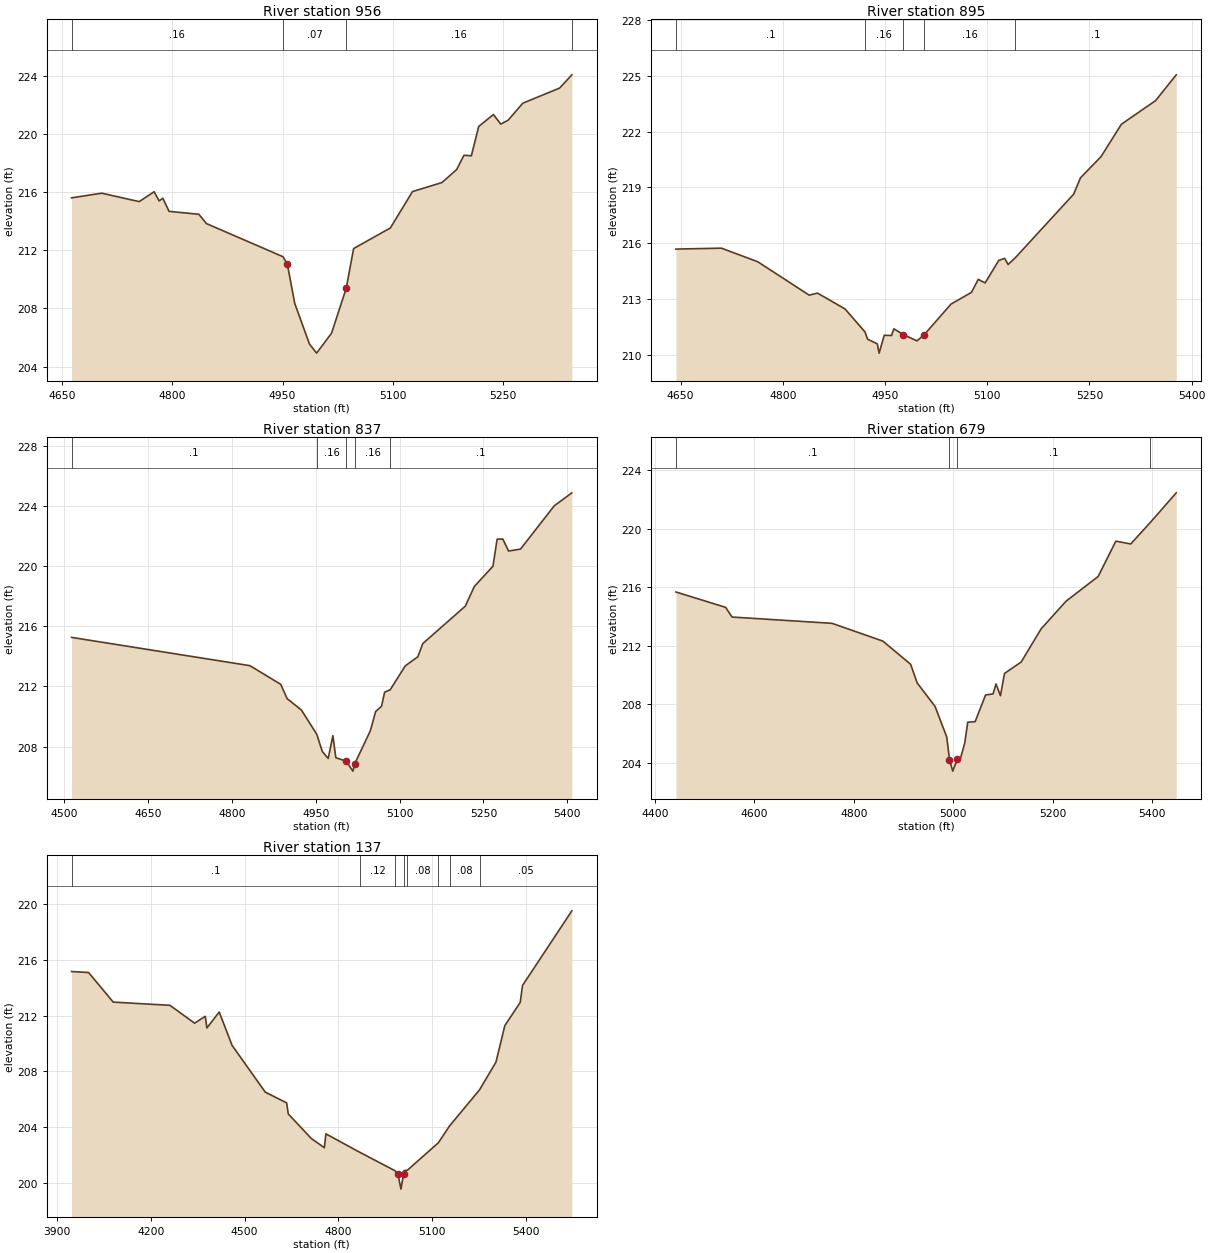
Type RM Length L Ch R = 1 ,956     ,61,61,61
BEGIN DESCRIPTION:
Mapping XS ee8be837
END DESCRIPTION:
XS GIS Cut Line= 3
      2288157.25     13184853.01      2288440.26     13184802.66
      2288438.53     13184410.21
#Sta/Elev= 30
  4663.3   215.6  4704.4  215.92  4755.2  215.34  4775.5  216.02  4782.3  215.39
  4787.4  215.57  4795.8  214.67  4836.3  214.47  4846.6  213.83  4950.7  211.55
  4956.6  211.02  4966.6  208.34  4986.6  205.55  4996.3  204.92  5016.6  206.29
  5036.6  209.38  5046.6  212.11  5096.6  213.53  5126.6  216.03  5166.6  216.65
  5186.6  217.54  5196.6  218.53  5206.6  218.49  5216.6  220.51  5236.6  221.33
  5246.6  220.67  5256.6  220.94  5276.6  222.11  5326.6  223.15  5343.2  224.06
#Mann= 4 ,-1 , 0
  4663.3     .16       0  4950.7     .07       0  5036.6     .16       0
  5343.2      .1       0
Bank Sta=4956.6,5036.6
XS Rating Curve= 0 ,0
Exp/Cntr=0.3,0.1

Type RM Length L Ch R = 1 ,895     ,58,58,58
BEGIN DESCRIPTION:
Mapping XS f392d9ed
END DESCRIPTION:
XS GIS Cut Line= 4
      2288181.56     13184856.48      2288487.13     13184818.28
      2288497.55     13184807.87      2288485.39     13184396.43
#Sta/Elev= 30
  4643.1  215.68  4709.8  215.73  4763.1     215  4838.7   213.2  4850.9  213.31
  4891.2  212.46  4920.6  211.22  4924.4  210.83  4938.6  210.58  4941.3  210.08
  4948.8  211.04  4959.5  211.03    4963  211.39  4976.8  211.08  4996.8  210.74
  5006.8  211.04  5046.8  212.72  5076.8  213.35  5086.8  214.05  5096.9  213.86
  5116.9  215.07  5125.6  215.18  5130.6  214.85  5141.1  215.21  5226.9  218.64
  5236.9  219.52  5266.9  220.65  5296.9   222.4    5347  223.67  5377.4  225.06
#Mann= 5 ,-1 , 0
  4643.1      .1       0  4920.6     .16       0  4976.8     .07       0
  5006.8     .16       0  5141.1      .1       0
#XS Ineff= 2 , 0
       0 4959.43  211.03               0
Permanent Ineff=
       T       F
Bank Sta=4976.8,5006.8
XS Rating Curve= 0 ,0
Exp/Cntr=0.3,0.1

Type RM Length L Ch R = 1 ,837     ,158,158,158
BEGIN DESCRIPTION:
Mapping XS 652cb150
END DESCRIPTION:
XS GIS Cut Line= 4
      2288164.23     13184873.84      2288499.28     13184938.07
       2288591.3     13184679.39       2288532.5     13184406.16
#Sta/Elev= 30
    4513  215.26  4832.2  213.38  4887.3  212.14  4898.7  211.19  4924.3  210.43
  4951.8  208.82  4961.6  207.68  4972.2  207.21  4980.6  208.73  4985.9  207.26
    5004  207.04  5016.5  206.37  5019.8  206.87  5047.6  209.05  5057.1  210.33
  5067.7  210.69  5073.2  211.62  5083.2  211.78  5110.2  213.37  5132.6  213.97
  5141.5  214.85  5217.6  217.34  5233.6  218.64    5267  219.99  5274.5  221.79
  5284.7   221.8    5295     221  5316.3  221.13  5376.8  224.01  5408.2  224.87
#Mann= 5 ,-1 , 0
    4513      .1       0  4951.8     .16       0    5004     .05       0
  5019.8     .16       0  5083.2      .1       0
Bank Sta=5004,5019.8
XS Rating Curve= 0 ,0
Exp/Cntr=0.3,0.1

Type RM Length L Ch R = 1 ,679     ,542,542,542
BEGIN DESCRIPTION:
Mapping XS 7bef97d2
END DESCRIPTION:
XS GIS Cut Line= 4
      2288139.67       13184881.      2288571.95     13184964.33
      2288754.24     13184839.33      2288769.87     13184495.56
#Sta/Elev= 30
  4442.7  215.67  4542.6  214.62  4555.4  213.96  4756.4  213.53  4858.3  212.32
  4914.2  210.74  4927.5  209.46  4963.4  207.86  4986.9  205.77 4991.82  204.39
 4992.37  204.23    4999  203.44  5008.1  204.26  5014.2  204.28    5023  205.34
  5029.1  206.78    5044  206.82  5064.9  208.64  5079.9  208.71  5085.9  209.39
  5094.8  208.59    5103  210.11  5136.5  210.89  5176.5  213.15  5226.6  215.04
  5291.2  216.73  5326.7  219.14  5356.7  218.95  5396.3  220.43  5448.1  222.44
#Mann= 4 ,-1 , 0
  4442.7      .1       0 4991.82     .03       0  5008.1      .1       0
  5396.3     .05       0
Bank Sta=4992.37,5008.1
XS Rating Curve= 0 ,0
Exp/Cntr=0.3,0.1

Type RM Length L Ch R = 1 ,137     ,0,0,0
BEGIN DESCRIPTION:
UNT283 IN PECR 1.0
END DESCRIPTION:
XS GIS Cut Line= 4
      2288132.51     13184886.59      2288882.53     13185094.93
      2289308.42     13185053.27      2289579.88     13184765.56
#Sta/Elev= 30
  3946.1  215.15  4000.7  215.08  4079.5  212.96  4261.2  212.73    4340  211.45
  4374.3  211.94  4379.5  211.11  4418.9  212.25  4460.1  209.86  4566.3  206.51
  4634.8  205.74    4640  204.95  4713.7  203.19  4755.5  202.53  4760.5  203.52
  4869.8  202.19  4980.9  200.89    4991  200.65  5000.8  199.56  5009.4  200.67
  5011.1  200.89  5021.6  200.92  5120.5  202.88  5156.5  204.09  5252.3  206.67
    5305  208.66  5333.3  211.27  5382.7  212.94    5390  214.15    5548   219.5
#Mann= 8 ,-1 , 0
  3946.1      .1       0  4869.8     .12       0  4980.9     .03       0
  5011.1     .12       0  5021.6     .08       0  5120.5     .05       0
  5156.5     .08       0  5252.3     .05       0
Bank Sta=4991,5009.4
XS Rating Curve= 0 ,0
Exp/Cntr=0.3,0.1

Chan Stop Cuts=-1
Use User Specified Reach Order=0
Composite Channel Slope=5