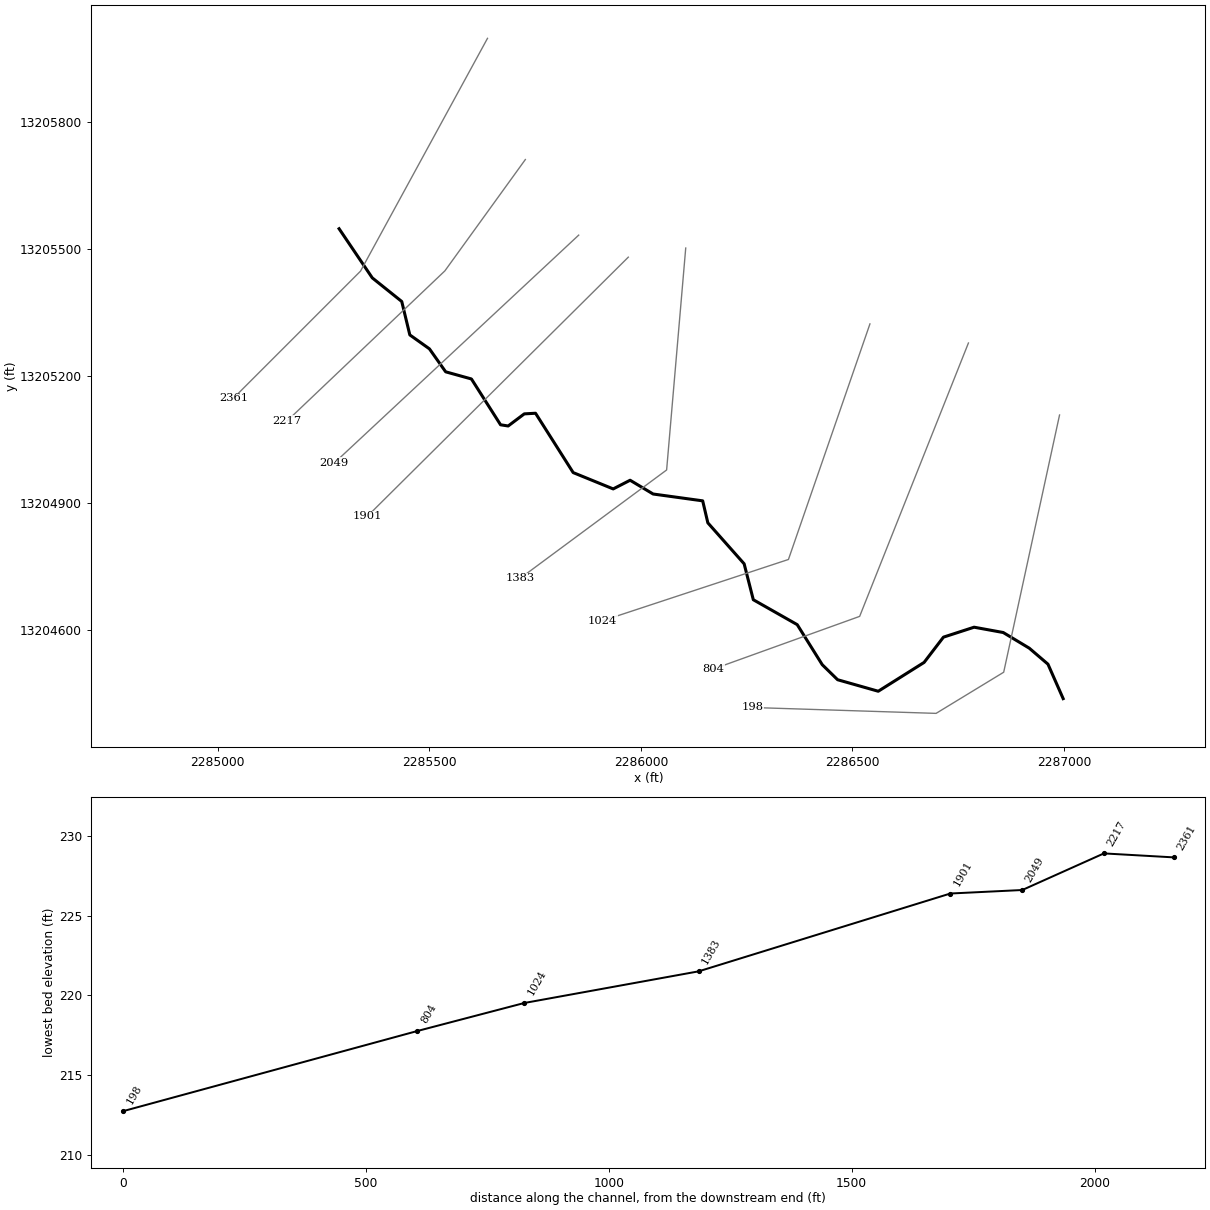
--- UNT290 IN PECR.prj (project) ---

Proj Title=UNT290 IN PECR Base Level Engineering
Current Plan=p01
Default Exp/Contr=0.3,0.1
English Units
Geom File=g01
Flow File=f01
Plan File=p01
Y Axis Title=Elevation
X Axis Title(PF)=Main Channel Distance
X Axis Title(XS)=Station
BEGIN DESCRIPTION:
UNT290 IN PECR
END DESCRIPTION:
DSS Export Rating Curves= 0
DSS Export Rating Curve Sorted= 0
DSS Export Volume Flow Curves= 0
DXF OffsetX= 0
DXF OffsetY= 0
DXF ScaleX= 1
DXF ScaleY= 10

--- UNT290 IN PECR.p01 (plan) ---

Plan Title=Multiple Run
Short Identifier=Multiple
Geom File=g01
Flow File=f01
Subcritical Flow
K Sum by GR= 0
Std Step Tol= 0.01
Critical Tol= 0.01
Num of Std Step Trials= 20
Max Error Tol= 0.3
Flow Tol Ratio= 0.001
Split Flow NTrial= 30
Split Flow Tol= 0.02
Split Flow Ratio= 0.02
Log Output Level= 0
Friction Slope Method= 1
Unsteady Friction Slope Method= 2
Unsteady Bridges Friction Slope Method= 1
Parabolic Critical Depth
Global Vel Dist=  1 , 1 , 1
Global Log Level= 0
CheckData=True
Encroach Param= -1, 0, 0, 0
BEGIN DESCRIPTION:
Multiple Run
END DESCRIPTION:

--- UNT290 IN PECR.f01 (steady flow) ---

Flow Title=Multiple
Program Version=4.10
Number of Profiles= 7
Profile Names=10-year,25-year,50-year,1pct_min,100-year,1pct_plu,500-year
River Rch & RM=UNT290 IN PECR,Reach-1         ,2361
      78     100     117     101     137     185     189
Boundary for River Rch & Prof#=UNT290 IN PECR,Reach-1         , 1
Up Type= 0
Dn Type= 3
Dn Slope=0.005
Boundary for River Rch & Prof#=UNT290 IN PECR,Reach-1         , 2
Up Type= 0
Dn Type= 3
Dn Slope=0.005
Boundary for River Rch & Prof#=UNT290 IN PECR,Reach-1         , 3
Up Type= 0
Dn Type= 3
Dn Slope=0.005
Boundary for River Rch & Prof#=UNT290 IN PECR,Reach-1         , 4
Up Type= 0
Dn Type= 3
Dn Slope=0.005
Boundary for River Rch & Prof#=UNT290 IN PECR,Reach-1         , 5
Up Type= 0
Dn Type= 3
Dn Slope=0.005
Boundary for River Rch & Prof#=UNT290 IN PECR,Reach-1         , 6
Up Type= 0
Dn Type= 3
Dn Slope=0.005
Boundary for River Rch & Prof#=UNT290 IN PECR,Reach-1         , 7
Up Type= 0
Dn Type= 3
Dn Slope=0.005
DSS Import GetInterval= 0
DSS Import GetPeak= 0
DSS Import FillOption= 0

--- UNT290 IN PECR.g01 (geometry) ---

Geom Title=Existing Conditions

River Reach=UNT290 IN PECR,Reach-1
Reach XY= 30
      2285287.09     13205547.02      2285365.51     13205430.89
      2285435.11     13205375.12      2285454.19     13205296.16
      2285500.52     13205263.25      2285538.87     13205208.97
      2285599.74     13205192.09      2285668.57     13205083.83
      2285686.51     13205081.00      2285724.60     13205109.61
      2285751.19     13205111.11      2285840.11     13204970.91
      2285934.65     13204932.32      2285974.62     13204952.83
      2286029.00     13204920.29      2286146.08     13204904.15
      2286158.27     13204852.18      2286244.02     13204755.39
      2286265.68     13204670.53      2286369.44     13204611.65
      2286428.57     13204517.02      2286464.83     13204481.54
      2286560.86     13204454.31      2286669.17     13204522.43
      2286714.90     13204582.12      2286787.29     13204605.62
      2286856.11     13204593.07      2286917.59     13204556.11
      2286961.79     13204518.29      2286997.72     13204436.86

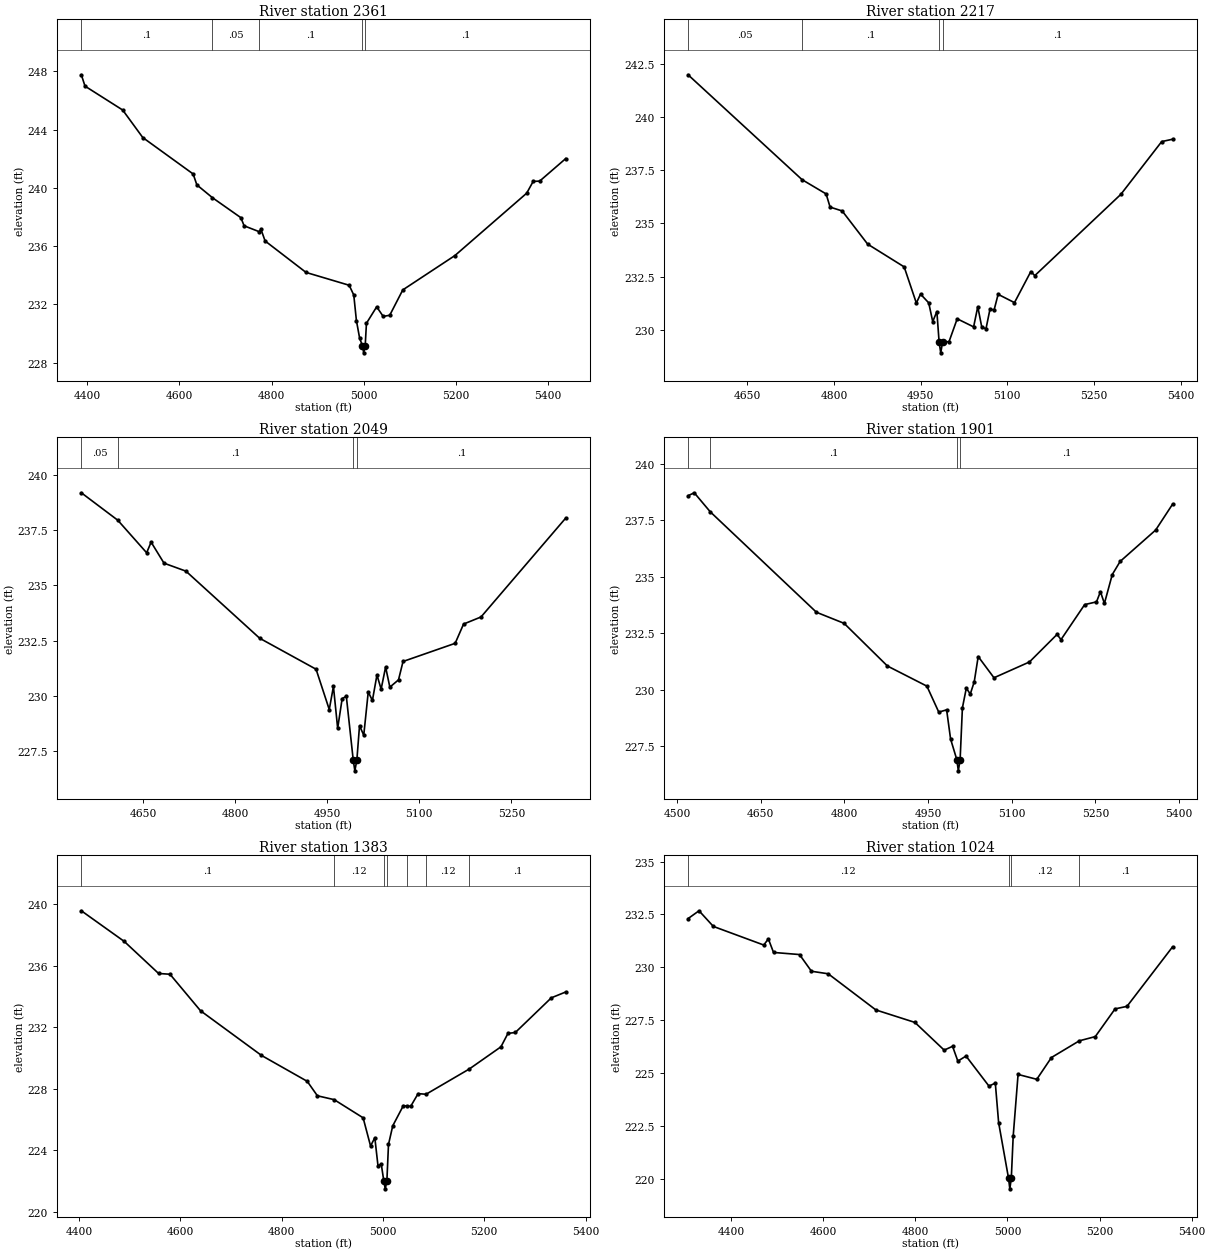
Type RM Length L Ch R = 1,2361,144,144,144
BEGIN DESCRIPTION:
UNT290 IN PECR 3.0
END DESCRIPTION:
XS GIS Cut Line= 3
      2285637.70     13205996.82      2285337.72     13205446.85
      2285037.73     13205146.87
#Sta/Elev= 30
  4387.4  247.76  4395.4  246.98  4477.1  245.34  4520.7  243.45  4629.9  240.95
  4638.0  240.20  4671.8  239.32  4733.4  237.95  4740.5  237.39  4773.0  236.99
  4777.0  237.15  4786.0  236.35  4874.8  234.19  4968.3  233.31  4978.3  232.64
  4984.0  230.89  4991.1  229.66  4997.1  229.17  4999.8  228.67  5003.1  229.17
  5005.8  230.70  5028.0  231.83  5042.1  231.17  5056.3  231.25  5084.6  232.99
  5197.7  235.35  5353.3  239.63  5367.4  240.44  5381.5  240.46  5438.1  242.01
#Mann=5,-1,0
  4387.4     0.1       0  4671.8    0.05       0  4773.0     0.1       0
  4997.1    0.07       0  5003.1     0.1       0
Bank Sta=4997.1,5003.1
Exp/Cntr=0.3,0.1

Type RM Length L Ch R = 1,2217,168,168,168
BEGIN DESCRIPTION:
Mapping XS 14ca7680
END DESCRIPTION:
XS GIS Cut Line= 3
      2285727.12     13205710.47      2285537.02     13205447.45
      2285164.65     13205093.31
#Sta/Elev= 30
  4547.5  241.99  4744.8  237.06  4786.4  236.39  4793.3  235.77  4814.2  235.59
  4858.3  234.03  4921.5  232.96  4942.6  231.26  4949.8  231.68  4964.0  231.27
  4970.9  230.39  4978.1  230.86  4982.0  229.42  4984.8  228.92  4988.0  229.42
  4999.2  229.45  5013.3  230.52  5041.7  230.14  5048.9  231.09  5055.8  230.13
  5063.1  230.05  5070.0  230.97  5077.2  230.94  5084.1  231.67  5112.4  231.28
  5140.7  232.74  5147.6  232.55  5296.5  236.37  5367.2  238.85  5385.9  238.96
#Mann=4,-1,0
  4547.5    0.05       0  4744.8     0.1       0  4982.0    0.07       0
  4988.0     0.1       0
Bank Sta=4982,4988
Exp/Cntr=0.3,0.1

Type RM Length L Ch R = 1,2049,148,148,148
BEGIN DESCRIPTION:
Mapping XS ac547978
END DESCRIPTION:
XS GIS Cut Line= 2
      2285853.16     13205531.91      2285275.92     13204993.73
#Sta/Elev= 30
  4549.3  239.18  4608.7  237.94  4655.7  236.47  4663.0  236.95  4684.0  236.00
  4719.7  235.64  4839.8  232.61  4931.7  231.21  4953.2  229.39  4960.0  230.43
  4966.9  228.54  4974.2  229.88  4981.0  229.99  4992.2  227.12  4994.9  226.62
  4998.2  227.12  5002.5  228.66  5009.4  228.23  5016.7  230.18  5023.5  229.80
  5030.9  230.95  5037.7  230.31  5045.0  231.31  5051.9  230.40  5066.0  230.73
  5073.4  231.56  5158.3  232.38  5172.0  233.25  5200.4  233.57  5338.5  238.04
#Mann=4,-1,0
  4549.3    0.05       0  4608.7     0.1       0  4992.2    0.07       0
  4998.2     0.1       0
Bank Sta=4992.2,4998.2
Exp/Cntr=0.3,0.1

Type RM Length L Ch R = 1,1901,518,518,518
BEGIN DESCRIPTION:
UNT290 IN PECR 2.0
END DESCRIPTION:
XS GIS Cut Line= 2
      2285970.36     13205479.85      2285354.01     13204867.83
#Sta/Elev= 30
  4519.8  238.58  4530.9  238.71  4559.5  237.87  4750.0  233.42  4799.6  232.93
  4877.3  231.04  4948.0  230.15  4969.3  229.00  4983.4  229.10  4990.5  227.81
  5001.6  226.90  5004.4  226.40  5007.6  226.90  5011.7  229.19  5018.7  230.06
  5025.8  229.80  5032.9  230.34  5040.0  231.46  5068.3  230.52  5131.9  231.22
  5181.4  232.44  5188.5  232.21  5230.9  233.76  5252.1  233.88  5259.2  234.33
  5266.3  233.81  5280.4  235.09  5294.5  235.67  5358.2  237.06  5388.4  238.20
#Mann=4,-1,0
  4519.8    0.05       0  4559.5     0.1       0  5001.6    0.07       0
  5007.6     0.1       0
Bank Sta=5001.6,5007.6
Exp/Cntr=0.3,0.1

Type RM Length L Ch R = 1,1383,359,359,359
BEGIN DESCRIPTION:
Mapping XS 0ee3c587
END DESCRIPTION:
XS GIS Cut Line= 3
      2286106.02     13205501.36      2286060.89     13204977.08
      2285714.84     13204721.01
#Sta/Elev= 30
  4404.3  239.56  4489.1  237.57  4556.9  235.49  4579.4  235.44  4639.7  233.07
  4760.1  230.17  4850.4  228.49  4870.5  227.55  4903.6  227.30  4960.8  226.12
  4975.5  224.29  4983.9  224.83  4990.1  223.02  4996.7  223.10  5001.7  222.01
  5004.5  221.51  5007.7  222.01  5010.9  224.39  5019.3  225.60  5040.2  226.91
  5047.9  226.88  5054.8  226.87  5069.4  227.69  5085.1  227.65  5170.5  229.29
  5233.0  230.73  5246.8  231.60  5261.4  231.66  5332.5  233.91  5361.0  234.29
#Mann=7,-1,0
  4404.3     0.1       0  4903.6    0.12       0  5001.7    0.07       0
  5007.7    0.12       0  5047.9     0.1       0  5085.1    0.12       0
  5170.5     0.1       0
Bank Sta=5001.7,5007.7
Exp/Cntr=0.3,0.1

Type RM Length L Ch R = 1,1024,220,220,220
BEGIN DESCRIPTION:
Mapping XS 29b62fa8
END DESCRIPTION:
XS GIS Cut Line= 3
      2286541.23     13205322.16      2286348.68     13204765.64
      2285909.33     13204620.80
#Sta/Elev= 30
  4306.8  232.30  4330.6  232.67  4361.7  231.93  4471.1  231.05  4481.1  231.34
  4492.3  230.70  4548.7  230.60  4574.6  229.81  4611.0  229.69  4714.5  227.98
  4799.2  227.39  4862.7  226.08  4880.9  226.26  4892.4  225.56  4910.1  225.80
  4959.9  224.38  4973.7  224.52  4980.9  222.65  5002.4  220.02  5005.2  219.52
  5008.4  220.02  5012.5  222.01  5023.1  224.93  5063.7  224.70  5095.5  225.73
  5156.0  226.52  5190.7  226.72  5233.6  228.03  5259.5  228.15  5358.3  230.96
#Mann=4,-1,0
  4306.8    0.12       0  5002.4    0.07       0  5008.4    0.12       0
  5156.0     0.1       0
Bank Sta=5002.4,5008.4
Exp/Cntr=0.3,0.1

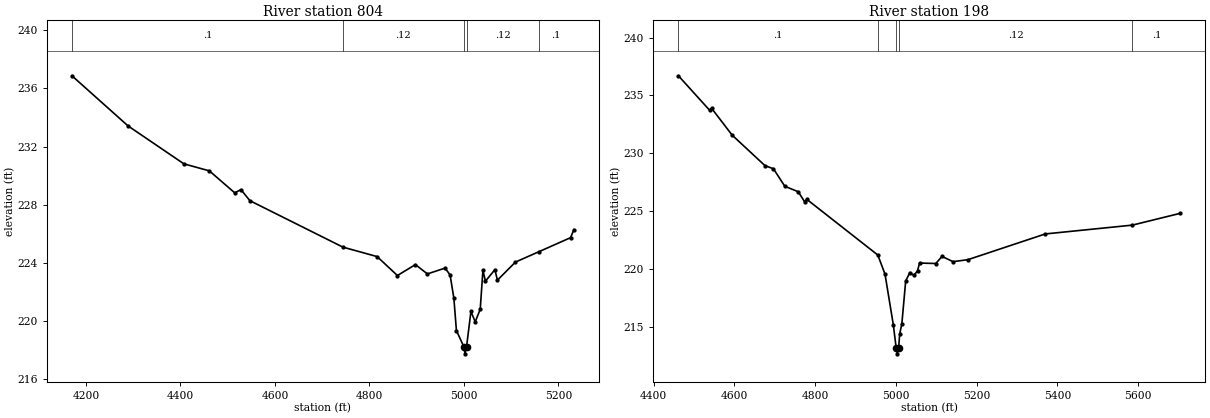
Type RM Length L Ch R = 1,804,606,606,606
BEGIN DESCRIPTION:
Mapping XS a877c790
END DESCRIPTION:
XS GIS Cut Line= 3
      2286773.88     13205277.05      2286516.93     13204631.21
      2286171.23     13204506.75
#Sta/Elev= 30
  4170.4  236.86  4289.0  233.42  4407.4  230.81  4461.2  230.33  4515.0  228.82
  4528.2  229.04  4547.1  228.28  4744.0  225.09  4816.4  224.44  4859.4  223.14
  4897.5  223.89  4922.9  223.25  4960.3  223.65  4970.9  223.18  4978.9  221.58
  4984.3  219.36  4999.8  218.26  5002.6  217.76  5005.8  218.26  5015.0  220.67
  5024.1  219.96  5034.7  220.82  5040.4  223.50  5045.7  222.75  5065.7  223.54
  5071.1  222.82  5109.1  224.06  5158.5  224.77  5226.0  225.74  5232.9  226.29
#Mann=5,-1,0
  4170.4     0.1       0  4744.0    0.12       0  4999.8    0.07       0
  5005.8    0.12       0  5158.5     0.1       0
Bank Sta=4999.8,5005.8
Exp/Cntr=0.3,0.1

Type RM Length L Ch R = 1,198,0,0,0
BEGIN DESCRIPTION:
UNT290 IN PECR 1.0
END DESCRIPTION:
XS GIS Cut Line= 4
      2286989.16     13205106.93      2286857.21     13204499.26
      2286697.49     13204402.04      2286263.43     13204415.93
#Sta/Elev= 30
  4461.5  236.70  4538.7  233.73  4543.8  233.89  4594.6  231.58  4675.9  228.95
  4696.9  228.68  4725.0  227.17  4758.3  226.70  4774.1  225.83  4779.3  226.05
  4955.4  221.24  4973.2  219.59  4993.7  215.24  5000.9  213.22  5003.7  212.72
  5006.9  213.22  5009.6  214.45  5014.8  215.28  5024.4  219.00  5034.6  219.73
  5044.9  219.49  5053.7  219.88  5058.8  220.55  5098.9  220.51  5114.4  221.12
  5141.6  220.67  5178.4  220.84  5370.1  223.06  5585.7  223.82  5704.6  224.84
#Mann=5,-1,0
  4461.5     0.1       0  4955.4    0.12       0  5000.9    0.07       0
  5006.9    0.12       0  5585.7     0.1       0
Bank Sta=5000.9,5006.9
Exp/Cntr=0.3,0.1

Chan Stop Cuts=-1