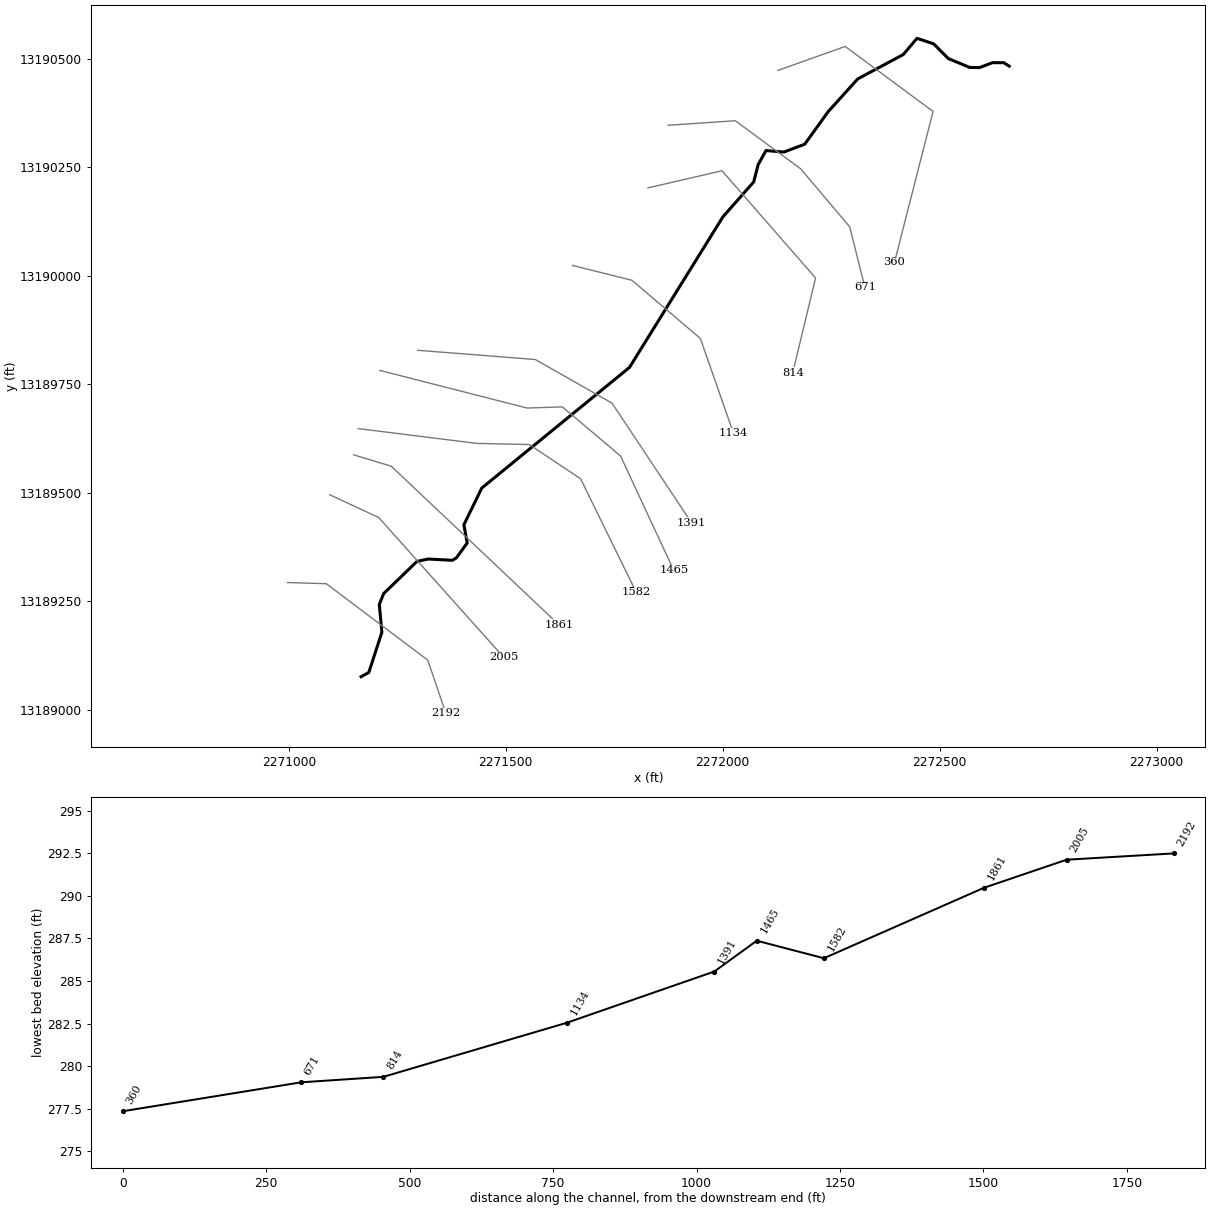
--- UNT300 IN PECR.prj (project) ---

Proj Title=UNT300 IN PECR Base Level Engineering
Current Plan=p01
Default Exp/Contr=0.3,0.1
English Units
Geom File=g01
Flow File=f01
Plan File=p01
Y Axis Title=Elevation
X Axis Title(PF)=Main Channel Distance
X Axis Title(XS)=Station
BEGIN DESCRIPTION:
UNT300 IN PECR
END DESCRIPTION:
DSS Export Rating Curves= 0
DSS Export Rating Curve Sorted= 0
DSS Export Volume Flow Curves= 0
DXF OffsetX= 0
DXF OffsetY= 0
DXF ScaleX= 1
DXF ScaleY= 10

--- UNT300 IN PECR.p01 (plan) ---

Plan Title=Multiple Run
Short Identifier=Multiple
Geom File=g01
Flow File=f01
Subcritical Flow
K Sum by GR= 0
Std Step Tol= 0.01
Critical Tol= 0.01
Num of Std Step Trials= 20
Max Error Tol= 0.3
Flow Tol Ratio= 0.001
Split Flow NTrial= 30
Split Flow Tol= 0.02
Split Flow Ratio= 0.02
Log Output Level= 0
Friction Slope Method= 1
Unsteady Friction Slope Method= 2
Unsteady Bridges Friction Slope Method= 1
Parabolic Critical Depth
Global Vel Dist=  1 , 1 , 1
Global Log Level= 0
CheckData=True
Encroach Param= -1, 0, 0, 0
BEGIN DESCRIPTION:
Multiple Run
END DESCRIPTION:

--- UNT300 IN PECR.f01 (steady flow) ---

Flow Title=Multiple
Program Version=4.10
Number of Profiles= 7
Profile Names=10-year,25-year,50-year,1pct_min,100-year,1pct_plu,500-year
River Rch & RM=UNT300 IN PECR,Reach-1         ,2192
      62      78      90      77     104     141     141
Boundary for River Rch & Prof#=UNT300 IN PECR,Reach-1         , 1
Up Type= 0
Dn Type= 3
Dn Slope=0.0044
Boundary for River Rch & Prof#=UNT300 IN PECR,Reach-1         , 2
Up Type= 0
Dn Type= 3
Dn Slope=0.0044
Boundary for River Rch & Prof#=UNT300 IN PECR,Reach-1         , 3
Up Type= 0
Dn Type= 3
Dn Slope=0.0044
Boundary for River Rch & Prof#=UNT300 IN PECR,Reach-1         , 4
Up Type= 0
Dn Type= 3
Dn Slope=0.0044
Boundary for River Rch & Prof#=UNT300 IN PECR,Reach-1         , 5
Up Type= 0
Dn Type= 3
Dn Slope=0.0044
Boundary for River Rch & Prof#=UNT300 IN PECR,Reach-1         , 6
Up Type= 0
Dn Type= 3
Dn Slope=0.0044
Boundary for River Rch & Prof#=UNT300 IN PECR,Reach-1         , 7
Up Type= 0
Dn Type= 3
Dn Slope=0.0044
DSS Import GetInterval= 0
DSS Import GetPeak= 0
DSS Import FillOption= 0

--- UNT300 IN PECR.g01 (geometry) ---

Geom Title=Existing Conditions
Program Version=4.10

River Reach=UNT300 IN PECR  ,Reach-1
Reach XY= 30
      2271166.57     13189075.56       2271184.3     13189085.39
      2271214.41     13189178.16      2271208.47     13189241.73
      2271218.42     13189267.03      2271295.21     13189341.28
      2271321.24     13189346.85      2271377.11     13189343.86
      2271385.92     13189349.26      2271411.08     13189383.74
       2271403.4     13189425.74      2271444.63     13189510.39
      2271785.09     13189788.43      2272000.52     13190135.63
      2272071.32     13190215.83      2272081.58     13190255.72
      2272099.75     13190288.22      2272140.82     13190284.79
      2272188.96     13190302.81      2272243.31     13190378.28
      2272311.16     13190453.33      2272416.17     13190509.54
      2272447.72     13190546.85      2272486.02     13190534.24
      2272519.79     13190500.32      2272569.05     13190479.85
      2272591.82     13190479.44      2272621.82     13190490.77
      2272647.69     13190490.74       2272660.3     13190482.73

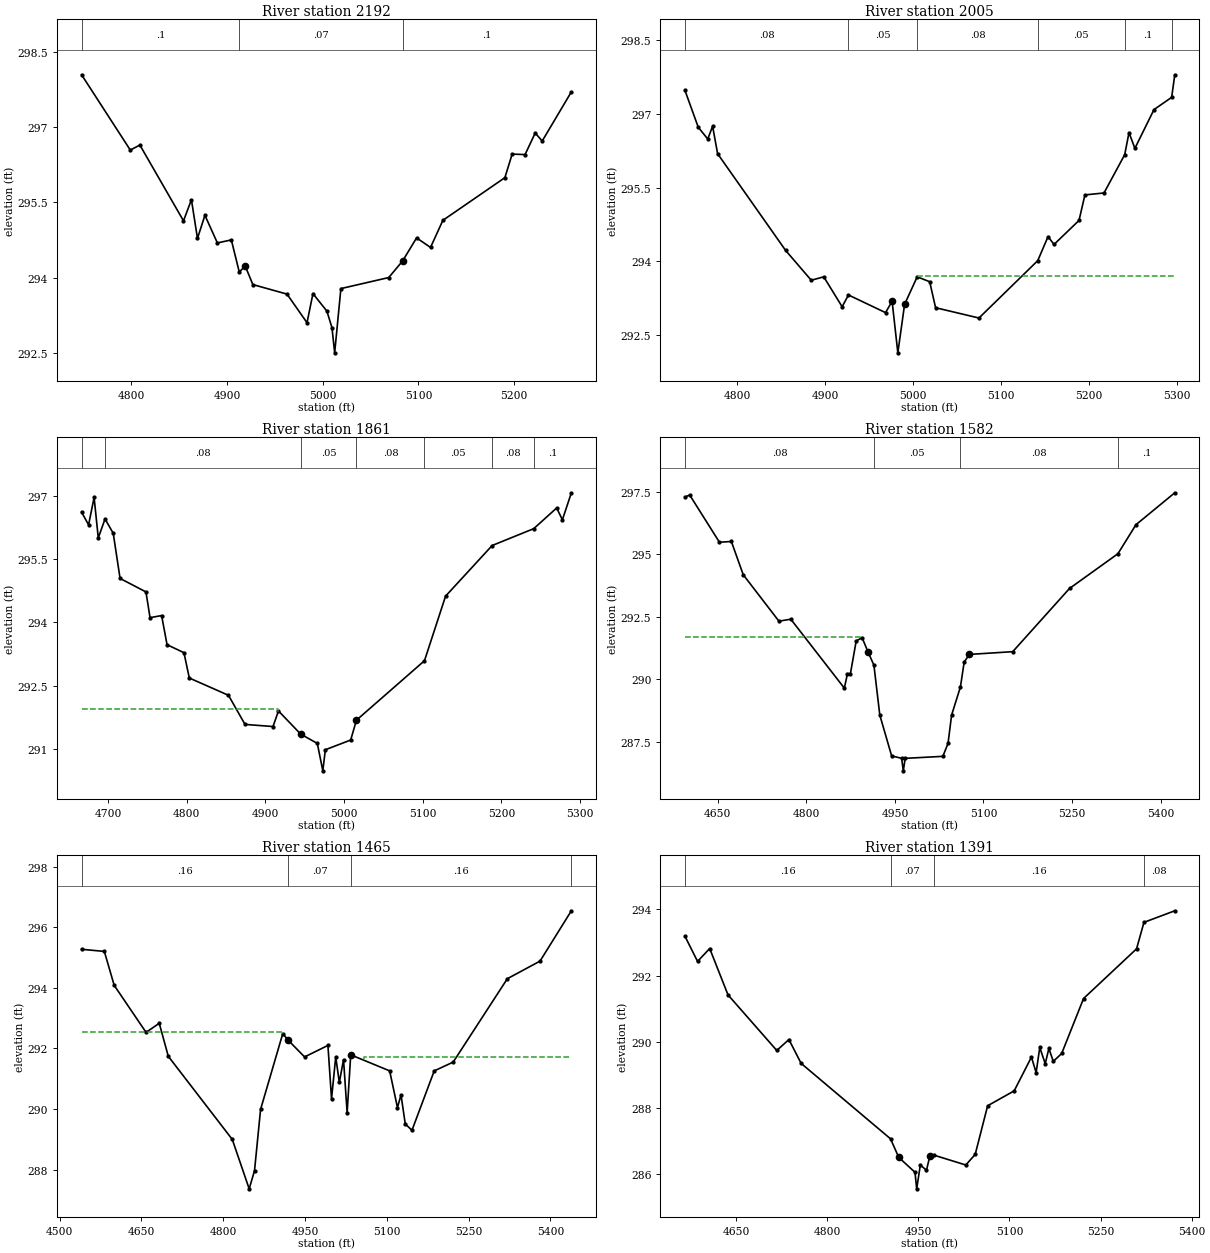
Type RM Length L Ch R = 1 ,2192    ,187,187,187
BEGIN DESCRIPTION:
UNT300 IN PECR 2.0
END DESCRIPTION:
XS GIS Cut Line= 4
      2270996.81     13189292.58      2271086.15     13189289.95
      2271320.12     13189113.82      2271361.91     13188991.07
#Sta/Elev= 30
    4748  298.04  4798.9  296.54  4808.9  296.64  4854.5  295.13  4862.8  295.55
  4869.1  294.78  4876.9  295.24  4889.9  294.69  4904.5  294.75  4912.8  294.11
    4919  294.23    4927  293.86  4962.7  293.67  4983.6   293.1  4989.8  293.68
  5004.4  293.33  5009.7     293  5012.5   292.5    5019  293.78    5069     294
  5083.5  294.33  5098.1  294.79  5112.7   294.6  5125.6  295.14  5190.4  295.99
    5198  296.46  5211.5  296.45  5222.1  296.88  5229.4  296.72  5259.9   297.7
#Mann= 3 ,-1 , 0
    4748      .1       0  4912.8     .07       0  5083.5      .1       0
Bank Sta=4919,5083.5
XS Rating Curve= 0 ,0
Exp/Cntr=0.3,0.1

Type RM Length L Ch R = 1 ,2005    ,144,144,144
BEGIN DESCRIPTION:
Mapping XS 9fc10716
END DESCRIPTION:
XS GIS Cut Line= 3
      2271094.05       13189495.      2271207.08     13189442.43
      2271495.02     13189120.46
#Sta/Elev= 30
  4740.7  297.48  4755.8  296.73  4766.6  296.49  4772.1  296.75  4777.8  296.19
    4855  294.22  4884.2  293.61  4898.4  293.68  4919.3  293.07  4926.5  293.31
  4968.6  292.95  4976.1  293.18  4982.6  292.13  4990.3  293.12  5004.6  293.68
  5018.8  293.58  5025.5  293.05  5074.8  292.84  5141.6  294.01  5153.3   294.5
  5160.1  294.34  5188.5  294.83  5195.2  295.35  5216.9  295.39  5240.4  296.17
  5245.3  296.62    5252   296.3  5273.7  297.09  5293.8  297.34  5297.3   297.8
#Mann= 6 ,-1 , 0
  4740.7     .08       0  4926.5     .05       0  5004.6     .08       0
  5141.6     .05       0  5240.4      .1       0  5293.8     .05       0
#XS Ineff= 2 , 0
                         5004.97          293.69
Permanent Ineff=
       F       F
Bank Sta=4976.1,4990.3
XS Rating Curve= 0 ,0
Exp/Cntr=0.3,0.1

Type RM Length L Ch R = 1 ,1861    ,279,279,279
BEGIN DESCRIPTION:
Mapping XS e13b4b8a
END DESCRIPTION:
XS GIS Cut Line= 3
      2271149.24     13189587.02        2271236.     13189560.73
      2271622.44     13189195.32
#Sta/Elev= 30
  4666.4  296.61  4675.3  296.31  4682.3  296.96  4687.6     296  4696.2  296.45
  4706.6  296.11  4715.3  295.04  4748.2  294.72  4753.4  294.11  4768.1  294.16
    4775  293.47  4796.5  293.28  4803.3  292.68  4853.1  292.27  4874.1  291.58
  4909.7  291.53  4916.6   291.9  4944.9  291.35    4966  291.13    4973  290.48
  4976.2  290.98  5008.4  291.21  5015.7  291.68  5102.2  293.09    5129  294.62
  5188.2  295.82  5241.1  296.22  5270.2  296.71  5277.5  296.43  5288.9  297.07
#Mann= 7 ,-1 , 0
  4666.4     .08       0  4696.2     .08       0  4944.9     .05       0
  5015.7     .08       0  5102.2     .05       0  5188.2     .08       0
  5241.1      .1       0
#XS Ineff= 2 , 0
       0 4916.16  291.95               0
Permanent Ineff=
       T       F
Bank Sta=4944.9,5015.7
XS Rating Curve= 0 ,0
Exp/Cntr=0.3,0.1

Type RM Length L Ch R = 1 ,1582    ,117,117,117
BEGIN DESCRIPTION:
Mapping XS 4ae7a6ca
END DESCRIPTION:
XS GIS Cut Line= 5
      2271159.76     13189647.48      2271433.16     13189613.31
      2271554.09     13189610.68      2271672.39     13189531.81
       2271800.5     13189270.38
#Sta/Elev= 30
  4594.3   297.3  4602.3  297.38  4652.7  295.49  4672.9  295.52    4693  294.19
  4753.5  292.33  4773.6  292.41  4864.3  289.65  4869.6  290.23  4874.6  290.23
  4884.4  291.54  4894.4  291.67  4904.4   291.1  4914.4  290.57  4924.4  288.57
  4944.4  286.94  4961.4  286.84  4964.2  286.34  4967.4  286.84  5031.2  286.92
    5040  287.44    5046  288.57    5061   289.7  5067.3  290.69    5076     291
  5149.6  291.11  5245.8  293.64  5327.8  295.03  5358.3  296.19  5424.1  297.47
#Mann= 4 ,-1 , 0
  4594.3     .08       0  4914.4     .05       0    5061     .08       0
  5327.8      .1       0
#XS Ineff= 2 , 0
       0 4893.92  291.69               0
Permanent Ineff=
       T       F
Bank Sta=4904.4,5076
XS Rating Curve= 0 ,0
Exp/Cntr=0.3,0.1

Type RM Length L Ch R = 1 ,1465    ,74,74,74
BEGIN DESCRIPTION:
Mapping XS 617cee0c
END DESCRIPTION:
XS GIS Cut Line= 5
      2271209.75     13189781.55      2271548.84      13189694.8
      2271630.33     13189697.43      2271764.41     13189584.39
      2271887.26     13189320.39
#Sta/Elev= 30
  4540.4  295.27  4582.1   295.2  4600.2  294.08  4658.6  292.53  4682.8  292.83
  4699.4  291.74  4816.7     289  4847.7  287.37  4857.5  287.97  4868.6  289.99
  4909.3  292.49  4919.3  292.27  4949.3  291.72  4992.1   292.1  4998.7  290.34
  5006.4  291.72    5013  290.88  5020.7  291.63  5027.3  289.88  5033.9  291.79
  5105.3  291.26  5119.6  290.05  5126.1  290.47  5133.9  289.51  5146.2   289.3
    5187  291.26  5221.8  291.55  5321.1   294.3    5381  294.88  5438.5  296.54
#Mann= 4 ,-1 , 0
  4540.4     .16       0  4919.3     .07       0  5033.9     .16       0
  5438.5     .08       0
#XS Ineff= 2 , 0
       0 4908.84  292.55 5058.01       0  291.72
Permanent Ineff=
       T       T
Bank Sta=4919.3,5033.9
XS Rating Curve= 0 ,0
Exp/Cntr=0.3,0.1

Type RM Length L Ch R = 1 ,1391    ,257,257,257
BEGIN DESCRIPTION:
Mapping XS abb67c2b
END DESCRIPTION:
XS GIS Cut Line= 4
      2271297.12      13189827.9      2271568.18     13189806.58
      2271744.81     13189706.09      2271928.11     13189430.37
#Sta/Elev= 30
  4565.9  293.19  4586.6  292.43  4606.6  292.82  4636.7  291.42    4717  289.74
    4737  290.07  4757.1  289.35  4904.3  287.07  4917.8  286.51  4944.5  286.06
  4947.3  285.56  4953.3  286.28  4963.4  286.12  4969.1  286.56  4975.3  286.58
  5028.2  286.28  5043.6   286.6  5064.1  288.07  5107.8  288.52  5136.2  289.54
  5143.9  289.07  5149.9  289.83  5158.9  289.34  5164.9   289.8  5172.2  289.41
    5186  289.65    5222  291.31  5309.2  292.81  5321.4  293.61  5372.1  293.96
#Mann= 4 ,-1 , 0
  4565.9     .16       0  4904.3     .07       0  4975.3     .16       0
  5321.4     .08       0
Bank Sta=4917.8,4969.1
XS Rating Curve= 0 ,0
Exp/Cntr=0.3,0.1

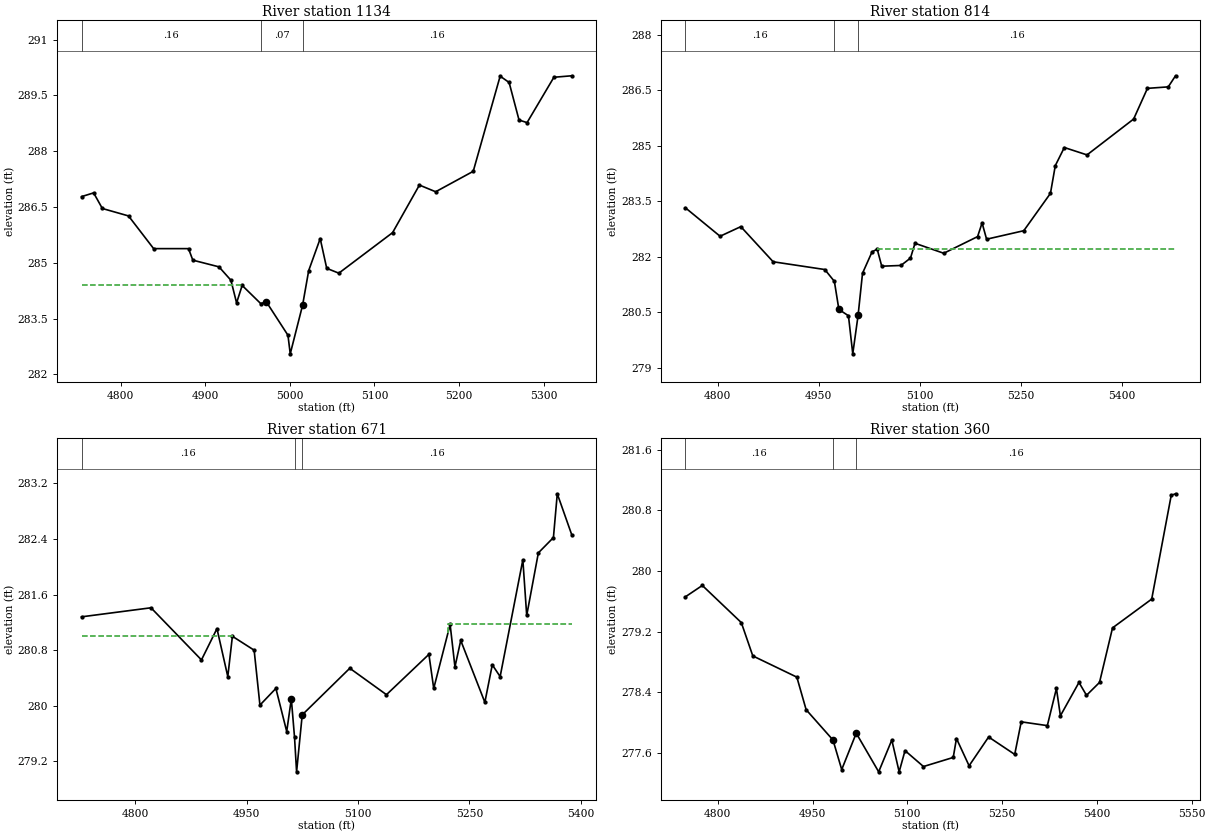
Type RM Length L Ch R = 1 ,1134    ,320,320,320
BEGIN DESCRIPTION:
Mapping XS 69dffa07
END DESCRIPTION:
XS GIS Cut Line= 4
      2271653.95     13190023.42      2271790.69     13189989.24
      2271948.43     13189855.16      2272024.67     13189636.97
#Sta/Elev= 30
    4754  286.78  4768.2  286.88  4778.5  286.46  4809.4  286.26  4839.1  285.38
  4880.3  285.38  4885.4  285.07  4916.3  284.89  4930.4  284.53  4937.1  283.92
  4943.7  284.39  4965.7   283.9  4972.2  283.95  4997.8  283.05  5000.5  282.55
  5015.1  283.86  5022.3  284.79  5035.9  285.65  5043.6  284.85  5057.9  284.72
  5121.4  285.81  5153.1  287.09  5172.3  286.91  5216.7  287.46  5248.5  290.02
  5259.1  289.85  5270.8  288.84  5280.3  288.77    5312  289.99  5333.1  290.03
#Mann= 3 ,-1 , 0
    4754     .16       0  4965.7     .07       0  5015.1     .16       0
#XS Ineff= 2 , 0
       0 4943.65  284.41               0
Permanent Ineff=
       T       F
Bank Sta=4972.2,5015.1
XS Rating Curve= 0 ,0
Exp/Cntr=0.3,0.1

Type RM Length L Ch R = 1 ,814     ,143,143,143
BEGIN DESCRIPTION:
Mapping XS 08649c06
END DESCRIPTION:
XS GIS Cut Line= 4
      2271827.49     13190202.18      2271998.38     13190241.61
      2272213.95      13189994.5      2272161.38     13189776.34
#Sta/Elev= 30
    4752  283.32  4803.5  282.55  4834.3  282.81  4882.3  281.86    4959  281.65
  4973.2  281.33  4979.9  280.57  4994.1   280.4  5000.5  279.37  5008.4  280.41
    5015  281.55  5029.2  282.13  5036.8   282.2  5043.5  281.74    5072  281.76
  5086.2  281.96  5092.9  282.36  5135.6  282.09  5185.8  282.54  5192.5  282.91
  5199.2  282.47  5254.4   282.7    5294  283.71  5301.2  284.46  5314.6  284.95
  5348.3  284.75  5417.5  285.72    5438  286.55  5468.9  286.59  5479.7  286.89
#Mann= 3 ,-1 , 0
    4752     .16       0  4973.2     .07       0  5008.4     .16       0
#XS Ineff= 2 , 0
                         5036.25           282.2
Permanent Ineff=
       F       F
Bank Sta=4979.9,5008.4
XS Rating Curve= 0 ,0
Exp/Cntr=0.3,0.1

Type RM Length L Ch R = 1 ,671     ,311,311,311
XS GIS Cut Line= 5
      2271874.41     13190346.53       2272028.9     13190356.94
      2272179.94     13190245.83      2272292.79     13190112.15
      2272327.52     13189973.21
#Sta/Elev= 30
  4727.4  281.28  4820.9  281.41  4888.9  280.66  4909.8  281.11  4924.4  280.42
  4930.6     281  4959.9   280.8  4967.7  280.01  4989.2  280.25  5003.8  279.63
    5010   280.1  5014.3  279.55  5017.1  279.05  5024.7  279.87  5088.8  280.54
  5138.2  280.16  5195.4  280.74  5201.9  280.25    5224  281.17  5230.5  280.56
  5238.3  280.94  5270.8  280.05  5280.8  280.59  5291.4  280.42    5322   282.1
  5327.2   281.3  5342.9   282.2  5363.2  282.42  5368.4  283.05  5387.9  282.46
#Mann= 3 ,-1 , 0
  4727.4     .16       0  5014.3     .07       0  5024.7     .16       0
#XS Ineff= 2 , 0
         4930.78  281.01 5221.17          281.17
Permanent Ineff=
       F       F
Bank Sta=5010,5024.7
XS Rating Curve= 0 ,0
Exp/Cntr=0.3,0.1

Type RM Length L Ch R = 1 ,360     ,0,0,0
BEGIN DESCRIPTION:
UNT300 IN PECR 1.0
END DESCRIPTION:
XS GIS Cut Line= 4
      2272127.18     13190472.95       2272282.3     13190528.16
      2272484.72     13190378.31      2272395.76     13190030.31
#Sta/Elev= 30
  4748.8  279.66  4775.6  279.81  4837.3  279.32  4855.5  278.88  4925.2   278.6
  4939.9  278.17  4982.4  277.77  4996.2  277.38  5019.2  277.86  5054.7  277.35
  5075.5  277.77  5087.1  277.35  5096.4  277.63  5125.6  277.42  5172.7  277.54
  5177.8  277.79  5197.8  277.43  5228.7  277.81    5270  277.58  5280.3  278.01
  5321.6  277.96    5336  278.45  5342.3  278.09  5371.7  278.53  5383.6  278.36
  5404.2  278.53  5424.8  279.25  5486.8  279.63  5517.7     281  5524.5  281.02
#Mann= 3 , 0 , 0
  4748.8     .16       0  4982.4     .07       0  5019.2     .16       0
Bank Sta=4982.4,5019.2
XS Rating Curve= 0 ,0
Exp/Cntr=0.3,0.1

Chan Stop Cuts=-1
Use User Specified Reach Order=0
Composite Channel Slope=5