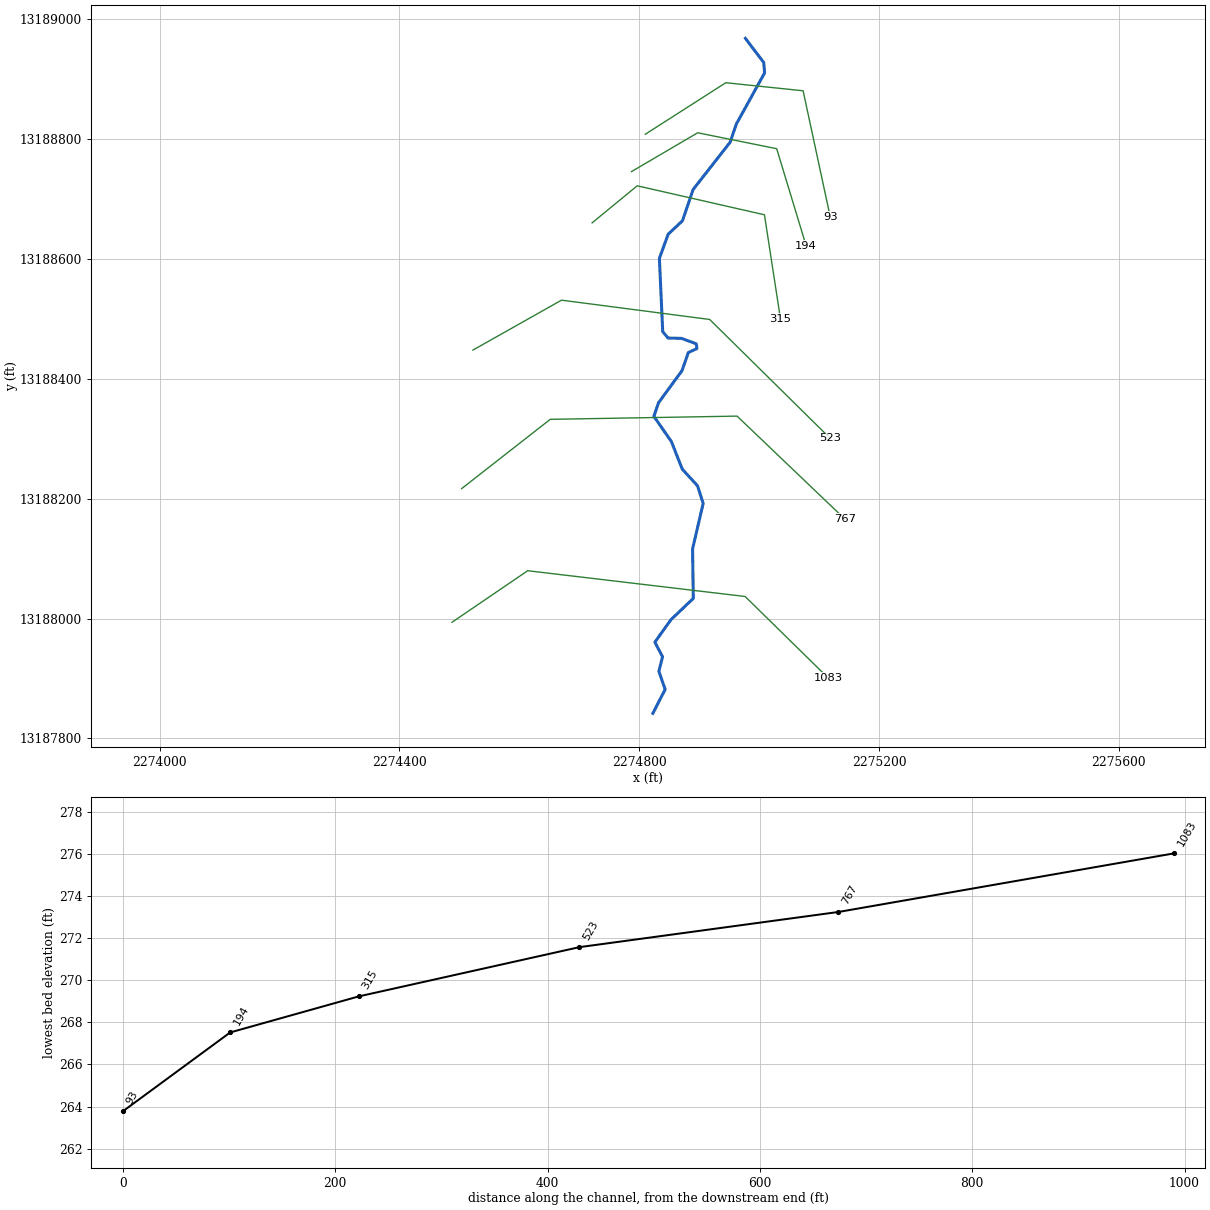
--- UNT301 IN PECR.prj (project) ---

Proj Title=UNT301 IN PECR Base Level Engineering
Current Plan=p01
Default Exp/Contr=0.3,0.1
English Units
Geom File=g01
Flow File=f01
Plan File=p01
Y Axis Title=Elevation
X Axis Title(PF)=Main Channel Distance
X Axis Title(XS)=Station
BEGIN DESCRIPTION:
UNT301 IN PECR
END DESCRIPTION:
DSS Export Rating Curves= 0
DSS Export Rating Curve Sorted= 0
DSS Export Volume Flow Curves= 0
DXF OffsetX= 0
DXF OffsetY= 0
DXF ScaleX= 1
DXF ScaleY= 10

--- UNT301 IN PECR.p01 (plan) ---

Plan Title=Multiple Run
Short Identifier=Multiple
Geom File=g01
Flow File=f01
Subcritical Flow
K Sum by GR= 0
Std Step Tol= 0.01
Critical Tol= 0.01
Num of Std Step Trials= 20
Max Error Tol= 0.3
Flow Tol Ratio= 0.001
Split Flow NTrial= 30
Split Flow Tol= 0.02
Split Flow Ratio= 0.02
Log Output Level= 0
Friction Slope Method= 1
Unsteady Friction Slope Method= 2
Unsteady Bridges Friction Slope Method= 1
Parabolic Critical Depth
Global Vel Dist=  1 , 1 , 1
Global Log Level= 0
CheckData=True
Encroach Param= -1, 0, 0, 0
BEGIN DESCRIPTION:
Multiple Run
END DESCRIPTION:

--- UNT301 IN PECR.f01 (steady flow) ---

Flow Title=Multiple
Program Version=4.10
Number of Profiles= 7
Profile Names=10-year,25-year,50-year,1pct_min,100-year,1pct_plu,500-year
River Rch & RM=UNT301 IN PECR,Reach-1         ,1083
      38      46      52      43      58      79      75
Boundary for River Rch & Prof#=UNT301 IN PECR,Reach-1         , 1
Up Type= 0
Dn Type= 3
Dn Slope=0.027
Boundary for River Rch & Prof#=UNT301 IN PECR,Reach-1         , 2
Up Type= 0
Dn Type= 3
Dn Slope=0.027
Boundary for River Rch & Prof#=UNT301 IN PECR,Reach-1         , 3
Up Type= 0
Dn Type= 3
Dn Slope=0.027
Boundary for River Rch & Prof#=UNT301 IN PECR,Reach-1         , 4
Up Type= 0
Dn Type= 3
Dn Slope=0.027
Boundary for River Rch & Prof#=UNT301 IN PECR,Reach-1         , 5
Up Type= 0
Dn Type= 3
Dn Slope=0.027
Boundary for River Rch & Prof#=UNT301 IN PECR,Reach-1         , 6
Up Type= 0
Dn Type= 3
Dn Slope=0.027
Boundary for River Rch & Prof#=UNT301 IN PECR,Reach-1         , 7
Up Type= 0
Dn Type= 3
Dn Slope=0.027
DSS Import GetInterval= 0
DSS Import GetPeak= 0
DSS Import FillOption= 0

--- UNT301 IN PECR.g01 (geometry) ---

Geom Title=Existing Conditions
Program Version=4.10

River Reach=UNT301 IN PECR  ,Reach-1
Reach XY= 30
      2274822.72     13187841.85       2274843.3     13187881.88
      2274832.81     13187912.07      2274838.92     13187936.14
      2274826.16     13187960.73      2274853.04     13187998.22
      2274890.19     13188033.55      2274889.03     13188116.22
      2274906.65     13188192.04      2274897.41     13188221.22
      2274871.86     13188249.16      2274853.62     13188295.32
      2274824.47     13188337.22      2274832.03     13188359.64
      2274871.48     13188413.62      2274881.92     13188443.74
      2274896.26     13188450.13      2274895.22      13188458.2
      2274870.48     13188467.32      2274848.08     13188467.84
      2274839.23     13188478.51      2274833.67     13188600.78
      2274848.37      13188641.1      2274872.05     13188663.28
      2274890.02     13188715.69      2274951.83     13188794.66
      2274961.91     13188824.53       2275009.1     13188910.01
      2275007.75     13188927.22      2274977.16     13188967.71

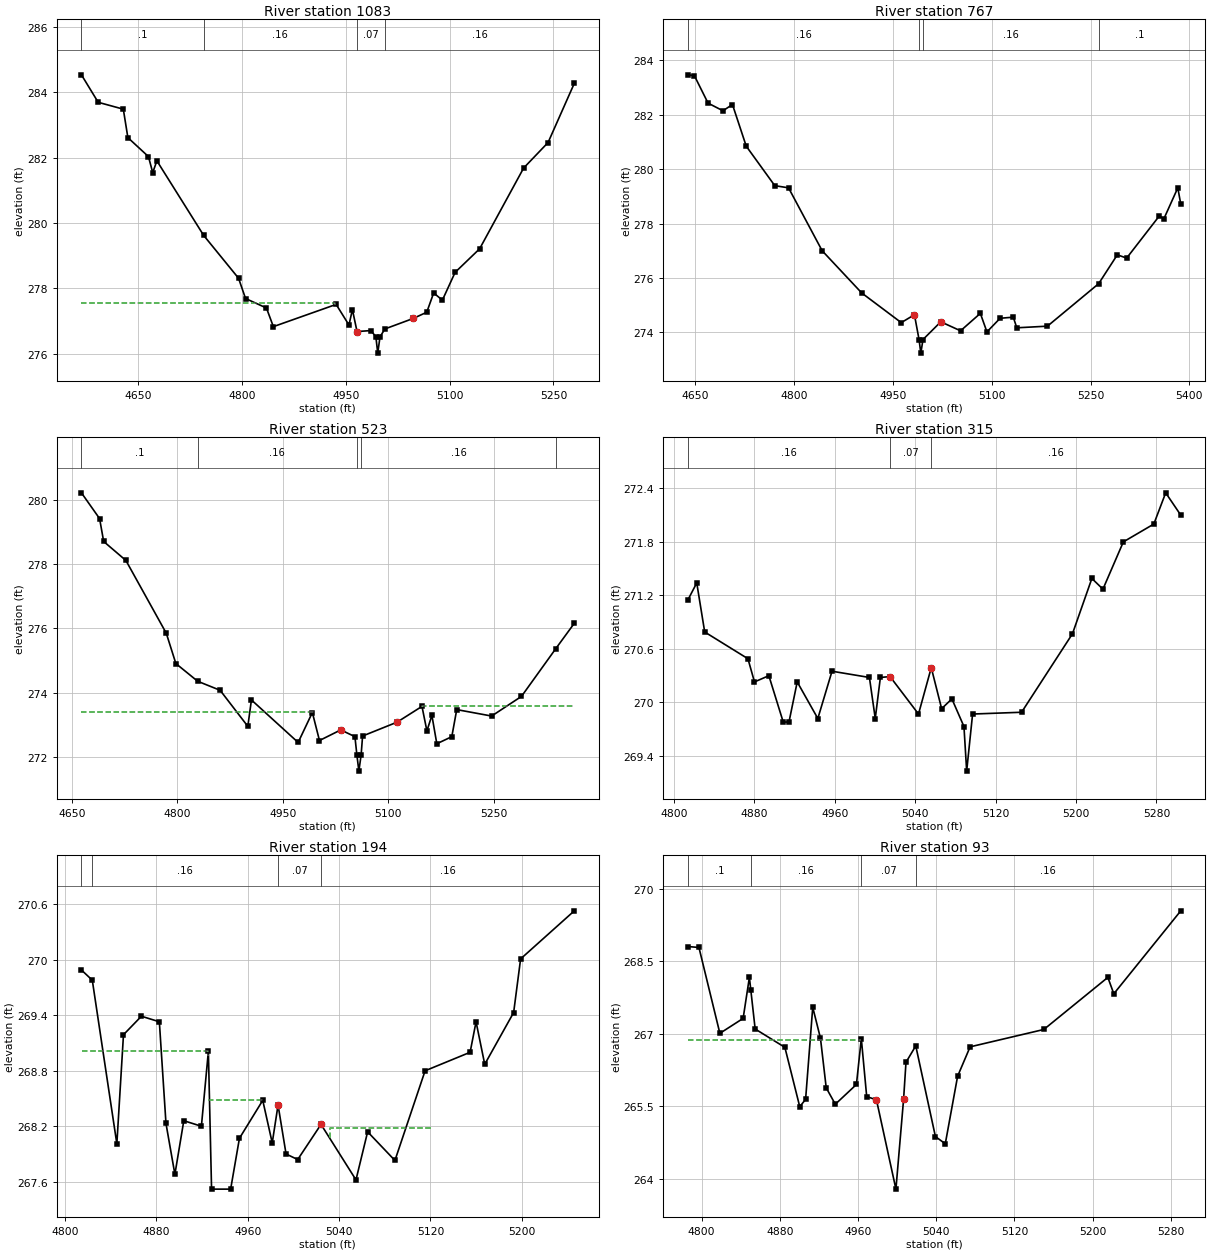
Type RM Length L Ch R = 1 ,1083    ,316,316,316
BEGIN DESCRIPTION:
UNT301 IN PECR 2.0
END DESCRIPTION:
XS GIS Cut Line= 4
      2274487.75     13187993.78      2274614.03     13188079.77
      2274976.66     13188036.79      2275115.28     13187900.84
#Sta/Elev= 30
    4568  284.53  4592.2  283.69  4628.5  283.48  4635.1  282.61  4664.8  282.03
    4671  281.54    4677   281.9  4744.6  279.62    4795  278.31  4805.1  277.69
  4835.3   277.4  4845.3  276.83    4936  277.51  4954.5  276.88  4959.5  277.35
  4966.2  276.68  4986.3  276.71  4993.4  276.52  4996.1  276.02  4999.4  276.52
  5006.5  276.76  5047.3  277.08  5066.9  277.27  5076.9  277.86  5089.5  277.64
  5107.9  278.49  5143.3  279.21  5206.9  281.68  5242.2  282.46  5280.1  284.27
#Mann= 4 ,-1 , 0
    4568      .1       0  4744.6     .16       0  4966.2     .07       0
  5006.5     .16       0
#XS Ineff= 2 , 0
       0 4934.25  277.54               0
Permanent Ineff=
       T       F
Bank Sta=4966.2,5047.3
XS Rating Curve= 0 ,0
Exp/Cntr=0.3,0.1

Type RM Length L Ch R = 1 ,767     ,244,244,244
BEGIN DESCRIPTION:
Mapping XS e9776cce
END DESCRIPTION:
XS GIS Cut Line= 4
      2274503.86     13188216.73      2274651.64     13188332.26
      2274963.23     13188337.64      2275142.98     13188165.93
#Sta/Elev= 30
  4639.1  283.46  4648.9  283.43  4669.7  282.42  4692.3  282.14  4706.7  282.37
  4727.6  280.84  4770.9  279.39  4791.8  279.31  4842.8     277  4902.8  275.45
  4962.8  274.36  4982.8  274.65  4989.8  273.74  4992.5  273.24  4995.8  273.74
  5022.8  274.39  5052.8  274.06  5082.8   274.7  5092.8  274.02  5112.8  274.52
  5132.8  274.56  5138.1  274.17  5184.6  274.23  5262.3  275.79  5290.6  276.85
  5304.8  276.73  5354.1  278.27  5361.4  278.18  5382.4  279.31  5386.9  278.71
#Mann= 4 ,-1 , 0
  4639.1     .16       0  4989.8     .07       0  4995.8     .16       0
  5262.3      .1       0
#XS Ineff= 2 , 0
       0                 5082.87       0  274.65
Permanent Ineff=
       F       T
Bank Sta=4982.8,5022.8
XS Rating Curve= 0 ,0
Exp/Cntr=0.3,0.1

Type RM Length L Ch R = 1 ,523     ,208,208,208
BEGIN DESCRIPTION:
Mapping XS 275571d2
END DESCRIPTION:
XS GIS Cut Line= 4
      2274522.69     13188447.76      2274670.44     13188531.04
      2274917.57     13188498.81      2275118.07     13188300.97
#Sta/Elev= 30
  4663.8  280.21  4689.6  279.41  4695.4   278.7    4727  278.11  4784.4  275.85
    4798  274.91    4829  274.36  4860.9  274.08  4900.3  272.96  4905.4  273.78
  4971.8  272.46    4992  273.39  5002.1  272.52  5032.4  272.85  5052.5  272.64
  5055.3  272.07  5058.1  271.57  5061.3  272.07  5063.4  272.66  5112.4  273.09
  5147.8  273.58  5154.8  272.82  5161.9   273.3  5168.9  272.42  5190.2  272.64
  5197.2  273.48  5246.8  273.28  5289.2  273.89  5337.9  275.37  5364.3  276.16
#Mann= 5 ,-1 , 0
  4663.8      .1       0    4829     .16       0  5055.3     .07       0
  5061.3     .16       0  5337.9      .1       0
#XS Ineff= 2 , 0
       0 4992.27  273.42 5148.07       0   273.6
Permanent Ineff=
       T       T
Bank Sta=5032.4,5112.4
XS Rating Curve= 0 ,0
Exp/Cntr=0.3,0.1

Type RM Length L Ch R = 1 ,315     ,121,121,121
BEGIN DESCRIPTION:
Mapping XS 44e89cb6
END DESCRIPTION:
XS GIS Cut Line= 4
      2274721.44     13188659.95      2274796.69     13188721.76
       2275008.9     13188673.41      2275035.52     13188500.37
#Sta/Elev= 30
  4814.1  271.15  4822.9  271.34  4830.8  270.79  4873.8  270.49  4880.3  270.23
  4894.6   270.3  4908.9  269.78  4914.6  269.78  4922.8  270.23  4943.3  269.82
  4957.4  270.35  4994.6  270.28  5000.4  269.82  5005.5  270.28  5015.1  270.29
  5043.4  269.87  5056.1  270.39  5066.4  269.93  5076.6  270.04  5088.6  269.73
  5091.3  269.23  5097.2  269.87  5145.9  269.89  5196.5  270.77  5215.8  271.39
  5226.8  271.27  5247.1   271.8  5277.4     272  5289.2  272.35  5304.2   272.1
#Mann= 3 , 0 , 0
  4814.1     .16       0  5015.1     .07       0  5056.1     .16       0
#XS Ineff= 2 , 0
       0 4975.69  270.28 5057.73       0  270.27
Permanent Ineff=
       T       T
Bank Sta=5015.1,5056.1
XS Rating Curve= 0 ,0
Exp/Cntr=0.3,0.1

Type RM Length L Ch R = 1 ,194     ,101,101,101
XS GIS Cut Line= 4
      2274787.18     13188745.47      2274897.56      13188810.2
      2275029.31     13188783.62      2275078.41     13188621.87
#Sta/Elev= 30
  4814.5  269.89    4824  269.78  4845.5  268.01  4851.3  269.19    4867  269.39
  4882.7  269.33  4888.5  268.23  4896.3  267.68  4904.1  268.26  4919.5   268.2
  4925.6  269.01  4928.4  267.52  4945.1  267.52  4952.8  268.07  4973.2  268.48
  4981.5  268.02  4986.6  268.43  4993.6   267.9  5003.8  267.84  5024.2  268.22
  5054.8  267.62    5065  268.14  5088.9  267.83  5115.3   268.8  5154.7     269
  5159.9  269.33  5167.5  268.87  5192.8  269.43  5198.9  270.01  5245.9  270.53
#Mann= 4 ,-1 , 0
  4814.5      .1       0    4824     .16       0  4986.6     .07       0
  5024.2     .16       0
#XS Ineff= 3 ,-1
  4815.2 4925.26  269.01 4925.26 4972.96  268.48 5031.66 5122.33  268.18
Permanent Ineff=
       T       T       T
Bank Sta=4986.6,5024.2
XS Rating Curve= 0 ,0
Exp/Cntr=0.3,0.1

Type RM Length L Ch R = 1 ,93      ,0,0,0
BEGIN DESCRIPTION:
UNT301 IN PECR 1.0
END DESCRIPTION:
XS GIS Cut Line= 4
      2274810.14     13188807.72      2274944.43     13188893.67
      2275073.37     13188880.24      2275118.62     13188669.93
#Sta/Elev= 30
    4786  268.81  4797.3  268.79  4818.7  267.01  4842.5  267.32  4848.9  268.17
  4850.4   267.9  4854.8   267.1  4885.2  266.72  4900.4  265.49  4906.4  265.64
  4913.7  267.55  4921.6  266.91  4927.5  265.88  4936.8  265.54  4958.4  265.95
  4963.4   266.9  4968.9   265.7  4978.9  265.63  4998.8  263.78 5006.63  265.64
  5009.1  266.41  5019.1  266.75  5039.2  264.87  5049.3  264.72  5061.9  266.12
  5074.7  266.73  5150.1  267.09  5215.6  268.17  5221.7  267.83  5290.2  269.55
#Mann= 4 ,-1 , 0
    4786      .1       0  4850.4     .16       0  4963.4     .07       0
  5019.1     .16       0
#XS Ineff= 2 , 0
       0 4963.54  266.88 5019.06       0  266.73
Permanent Ineff=
       T       T
Bank Sta=4978.9,5006.63
XS Rating Curve= 0 ,0
Exp/Cntr=0.3,0.1

Chan Stop Cuts=-1
Use User Specified Reach Order=0
Composite Channel Slope=5