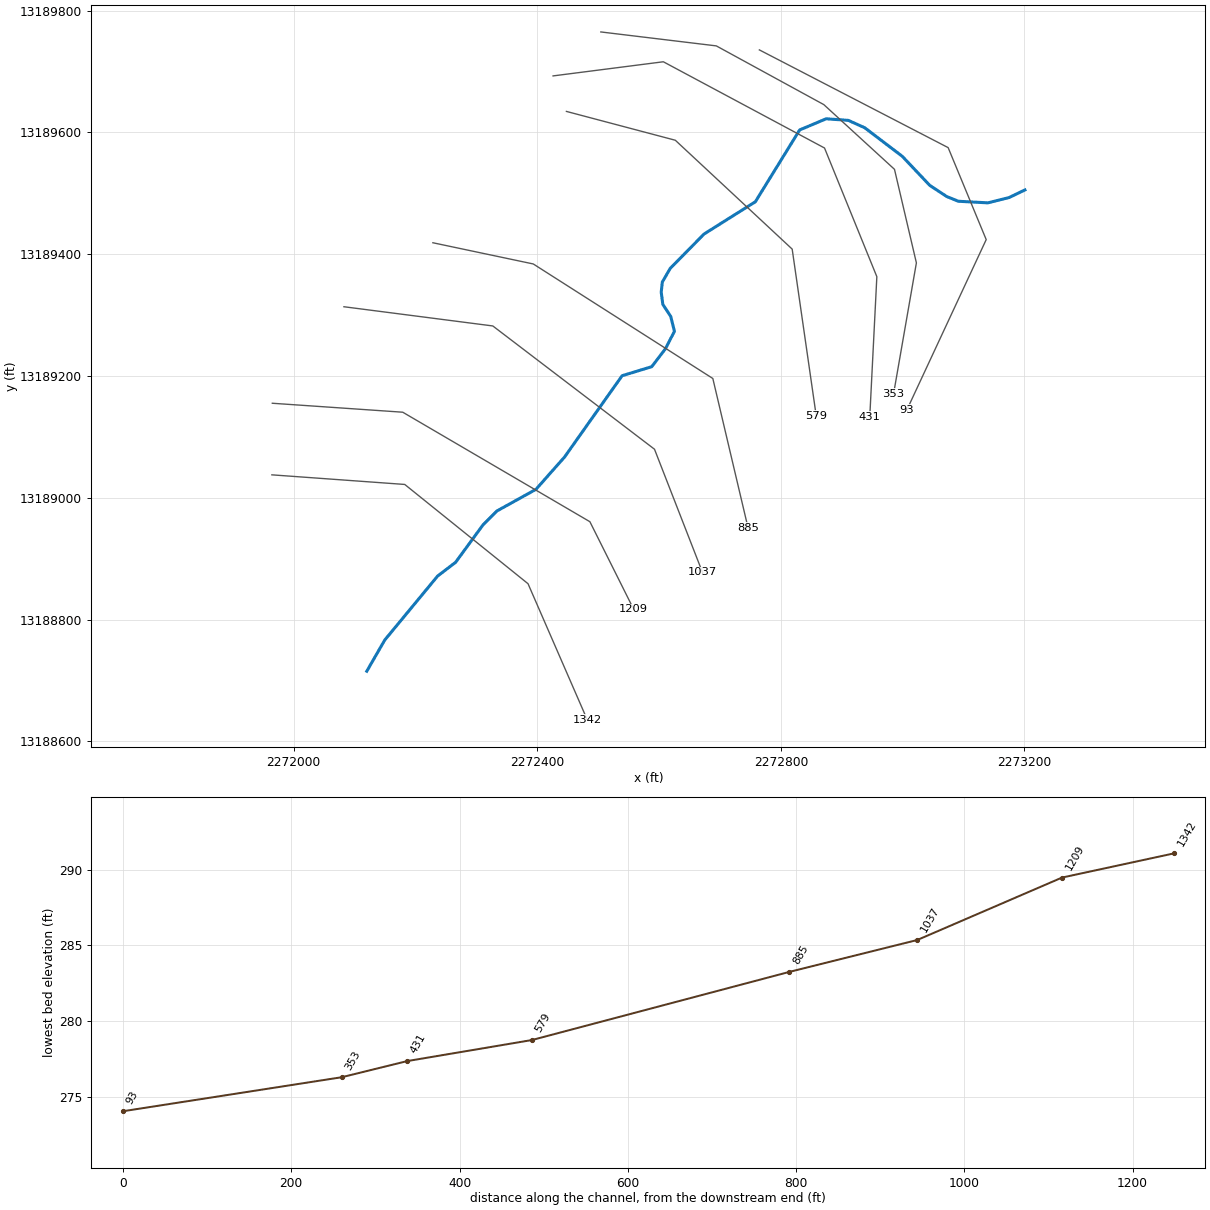
--- UNT302 IN PECR.prj (project) ---

Proj Title=UNT302 IN PECR Base Level Engineering
Current Plan=p01
Default Exp/Contr=0.3,0.1
English Units
Geom File=g01
Flow File=f01
Plan File=p01
Y Axis Title=Elevation
X Axis Title(PF)=Main Channel Distance
X Axis Title(XS)=Station
BEGIN DESCRIPTION:
UNT302 IN PECR
END DESCRIPTION:
DSS Export Rating Curves= 0
DSS Export Rating Curve Sorted= 0
DSS Export Volume Flow Curves= 0
DXF OffsetX= 0
DXF OffsetY= 0
DXF ScaleX= 1
DXF ScaleY= 10

--- UNT302 IN PECR.p01 (plan) ---

Plan Title=Multiple Run
Short Identifier=Multiple
Geom File=g01
Flow File=f01
Subcritical Flow
K Sum by GR= 0
Std Step Tol= 0.01
Critical Tol= 0.01
Num of Std Step Trials= 20
Max Error Tol= 0.3
Flow Tol Ratio= 0.001
Split Flow NTrial= 30
Split Flow Tol= 0.02
Split Flow Ratio= 0.02
Log Output Level= 0
Friction Slope Method= 1
Unsteady Friction Slope Method= 2
Unsteady Bridges Friction Slope Method= 1
Parabolic Critical Depth
Global Vel Dist=  1 , 1 , 1
Global Log Level= 0
CheckData=True
Encroach Param= -1, 0, 0, 0
BEGIN DESCRIPTION:
Multiple Run
END DESCRIPTION:

--- UNT302 IN PECR.f01 (steady flow) ---

Flow Title=Multiple
Program Version=4.10
Number of Profiles= 7
Profile Names=10-year,25-year,50-year,1pct_min,100-year,1pct_plu,500-year
River Rch & RM=UNT302 IN PECR,Reach-1         ,1342
      20      23      25      20      27      37      33
Boundary for River Rch & Prof#=UNT302 IN PECR,Reach-1         , 1
Up Type= 0
Dn Type= 3
Dn Slope=0.0123
Boundary for River Rch & Prof#=UNT302 IN PECR,Reach-1         , 2
Up Type= 0
Dn Type= 3
Dn Slope=0.0123
Boundary for River Rch & Prof#=UNT302 IN PECR,Reach-1         , 3
Up Type= 0
Dn Type= 3
Dn Slope=0.0123
Boundary for River Rch & Prof#=UNT302 IN PECR,Reach-1         , 4
Up Type= 0
Dn Type= 3
Dn Slope=0.0123
Boundary for River Rch & Prof#=UNT302 IN PECR,Reach-1         , 5
Up Type= 0
Dn Type= 3
Dn Slope=0.0123
Boundary for River Rch & Prof#=UNT302 IN PECR,Reach-1         , 6
Up Type= 0
Dn Type= 3
Dn Slope=0.0123
Boundary for River Rch & Prof#=UNT302 IN PECR,Reach-1         , 7
Up Type= 0
Dn Type= 3
Dn Slope=0.0123
DSS Import GetInterval= 0
DSS Import GetPeak= 0
DSS Import FillOption= 0

--- UNT302 IN PECR.g01 (geometry) ---

Geom Title=Existing Conditions
Program Version=4.10

River Reach=UNT302 IN PECR  ,Reach-1
Reach XY= 30
      2272120.06     13188715.13      2272149.57     13188766.34
      2272236.38     13188871.38      2272265.89     13188893.95
      2272311.03     13188955.58       2272333.6     13188978.15
      2272397.83     13189013.74      2272444.71     13189066.69
      2272539.33     13189200.37      2272587.94     13189215.13
      2272610.51     13189244.64      2272625.26     13189273.29
      2272619.19     13189297.59      2272606.17     13189317.56
      2272603.56     13189337.52       2272605.3     13189354.02
      2272618.32     13189376.58      2272673.88     13189433.01
      2272758.08     13189485.96       2272830.9     13189603.95
       2272874.4     13189622.24      2272910.85     13189619.64
      2272937.76     13189607.49       2272999.4     13189560.61
      2273044.54     13189512.87      2273072.31     13189494.64
      2273091.41     13189486.83      2273140.02     13189484.22
      2273174.74      13189492.9      2273200.82     13189505.45

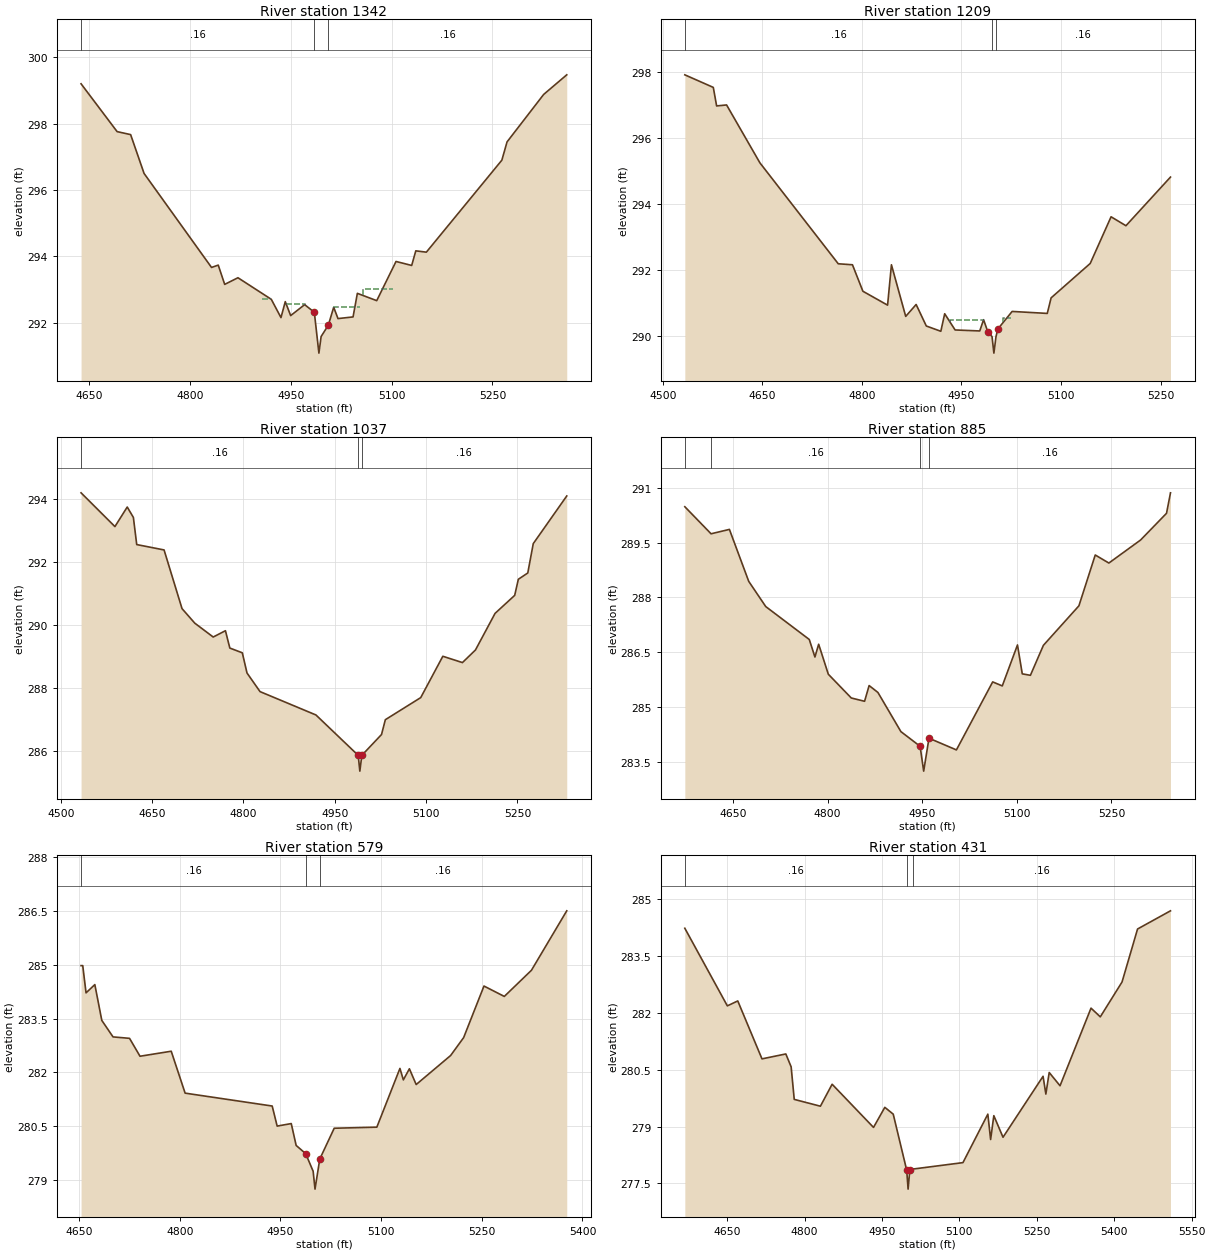
Type RM Length L Ch R = 1 ,1342    ,133,133,133
BEGIN DESCRIPTION:
UNT302 IN PECR 2.0
END DESCRIPTION:
XS GIS Cut Line= 4
      2271964.22     13189037.58       2272182.4     13189021.81
      2272384.82     13188858.81      2272482.08      13188635.4
#Sta/Elev= 30
  4638.2   299.2  4691.8  297.76  4711.9  297.67  4731.9   296.5  4832.2  293.67
  4842.2  293.74  4851.8  293.16  4871.5  293.36  4921.1  292.71  4935.5  292.16
  4941.9  292.64  4949.9  292.22  4970.7  292.55  4985.1  292.32  4991.9  291.09
  4995.2  291.59  5005.9  291.93  5013.9  292.47  5020.3  292.13  5042.7  292.18
  5049.1  292.89  5077.9  292.67  5106.6  293.85  5129.9  293.73    5136  294.17
  5151.7  294.13    5264   296.9  5271.7  297.45  5326.2  298.88  5360.5  299.47
#Mann= 3 , 0 , 0
  4638.2     .16       0  4985.1     .07       0  5005.9     .16       0
#XS Ineff= 6 ,-1
 4897.86 4906.61  292.76 4907.23 4921.12  292.71 4921.51    4942  292.63
    4943 4970.71  292.56 5014.04 5052.57  292.47 5057.14 5101.55  293.02
Permanent Ineff=
       F       F       F       F       T       T
Bank Sta=4985.1,5005.9
XS Rating Curve= 0 ,0
Exp/Cntr=0.3,0.1

Type RM Length L Ch R = 1 ,1209    ,172,172,172
BEGIN DESCRIPTION:
Mapping XS 5106cc08
END DESCRIPTION:
XS GIS Cut Line= 4
      2271964.93     13189155.14       2272179.1     13189140.43
      2272486.41     13188960.62      2272558.31     13188816.81
#Sta/Elev= 30
  4533.3   297.9  4576.2  297.52  4581.2  296.96  4596.2  296.99  4646.4  295.24
  4764.4  292.19  4785.8  292.16  4801.5  291.36  4838.7  290.94  4844.5  292.16
    4866   290.6  4881.7  290.96    4897  290.31  4918.9  290.15  4924.7  290.68
  4940.4  290.19  4977.5  290.16  4983.3   290.5  4989.7  290.13    4996  289.99
  4998.8  289.49    5002  289.99  5004.8  290.22  5026.3  290.75  5079.2  290.69
    5085  291.16  5143.9   292.2  5175.3  293.61  5197.7  293.34  5264.8  294.81
#Mann= 3 ,-1 , 0
  4533.3     .16       0    4996     .07       0    5002     .16       0
#XS Ineff= 4 ,-1
 4878.12 4924.49  290.63 4932.98 4983.27  290.49 5012.91  5025.2  290.56
 5026.29  5083.4  290.74
Permanent Ineff=
       T       T       T       F
Bank Sta=4989.7,5004.8
XS Rating Curve= 0 ,0
Exp/Cntr=0.3,0.1

Type RM Length L Ch R = 1 ,1037    ,152,152,152
BEGIN DESCRIPTION:
Mapping XS 62a15ce3
END DESCRIPTION:
XS GIS Cut Line= 4
      2272082.54     13189313.61      2272326.99     13189282.07
      2272592.51     13189079.64      2272671.37     13188877.22
#Sta/Elev= 30
  4533.4  294.18    4589  293.11  4609.2  293.73  4619.3   293.4  4624.8  292.54
  4669.7  292.37  4699.2  290.51  4720.1  290.05  4750.4  289.61  4770.5  289.81
  4777.7  289.26  4798.2  289.11  4805.9  288.47  4827.3  287.88  4919.1  287.14
  4988.5  285.86  4991.2  285.36  4994.5  285.86  5026.8  286.52  5033.1  286.99
  5091.2  287.69  5127.5     289  5159.7   288.8  5181.1   289.2  5213.3  290.36
  5245.5  290.93  5251.5  291.44    5267  291.64    5276  292.57    5331  294.08
#Mann= 3 ,-1 , 0
  4533.4     .16       0  4988.5     .07       0  4994.5     .16       0
Bank Sta=4988.5,4994.5
XS Rating Curve= 0 ,0
Exp/Cntr=0.3,0.1

Type RM Length L Ch R = 1 ,885     ,306,306,306
BEGIN DESCRIPTION:
Mapping XS a4d65604
END DESCRIPTION:
XS GIS Cut Line= 4
       2272228.6     13189418.69      2272393.43     13189383.87
      2272688.29      13189195.8      2272746.09     13188950.73
#Sta/Elev= 30
  4573.7  290.48  4615.3  289.74  4644.4  289.86    4675  288.44    4702  287.75
    4771  286.85    4780  286.37  4785.9  286.72  4801.2   285.9  4837.6  285.25
  4858.7  285.16  4865.9  285.59  4879.9   285.4  4916.3  284.33  4946.7  283.93
  4952.4  283.25  4960.8  284.15  5004.3  283.83  5061.8  285.69    5077  285.58
  5101.1   286.7  5108.7  285.91  5121.6  285.87  5142.2  286.69  5198.5  287.77
  5224.4  289.16    5246  288.94  5296.3  289.57  5337.4   290.3  5343.7  290.86
#Mann= 4 ,-1 , 0
  4573.7     .08       0  4615.3     .16       0  4946.7     .07       0
  4960.8     .16       0
Bank Sta=4946.7,4960.8
XS Rating Curve= 0 ,0
Exp/Cntr=0.3,0.1

Type RM Length L Ch R = 1 ,579     ,148,148,148
BEGIN DESCRIPTION:
Mapping XS 7bcc2a13
END DESCRIPTION:
XS GIS Cut Line= 4
      2272447.88     13189634.35      2272626.68     13189587.02
      2272818.59     13189408.25      2272858.03     13189134.82
#Sta/Elev= 30
  4653.1  284.98  4655.6  284.98  4660.5  284.22  4673.6  284.45    4684  283.45
  4700.7  282.99  4725.3  282.95  4740.9  282.45  4787.4  282.59  4808.1  281.42
  4937.8  281.06  4945.2   280.5  4966.2  280.57  4973.5  279.96  4987.7  279.73
  4998.8  279.24  5001.6  278.74  5008.7  279.58  5030.2  280.44  5093.7  280.47
  5128.1  282.11  5133.2  281.79  5142.2   282.1  5152.3  281.66  5203.6  282.47
    5223  282.97  5253.3  284.41  5283.6  284.12    5324  284.85  5376.6  286.51
#Mann= 3 , 0 , 0
  4653.1     .16       0  4987.7     .07       0  5008.7     .16       0
Bank Sta=4987.7,5008.7
XS Rating Curve= 0 ,0
Exp/Cntr=0.3,0.1

Type RM Length L Ch R = 1 ,431     ,78,78,78
BEGIN DESCRIPTION:
Mapping XS 280737aa
END DESCRIPTION:
XS GIS Cut Line= 5
      2272425.94     13189692.66      2272607.03     13189715.88
      2272871.71     13189574.25      2272957.62     13189362.97
      2272946.01      13189133.1
#Sta/Elev= 30
    4568  284.24  4650.4  282.19  4670.6  282.32  4717.5  280.79  4763.7  280.92
    4774  280.58    4780  279.72  4830.7  279.54  4853.4  280.12  4933.6  278.98
  4955.5  279.51  4971.8  279.33  4997.9  277.85  5000.6  277.35  5003.9  277.85
    5010  277.88  5106.9  278.05  5155.1  279.33  5160.5  278.66  5166.7  279.29
  5184.5  278.72  5262.1  280.33  5267.5  279.86    5274  280.43    5295  280.08
    5355  282.13    5373   281.9  5415.1  282.82  5445.2  284.22    5509   284.7
#Mann= 3 ,-1 , 0
    4568     .16       0  4997.9     .07       0    5010     .16       0
Bank Sta=4997.9,5003.9
XS Rating Curve= 0 ,0
Exp/Cntr=0.3,0.1

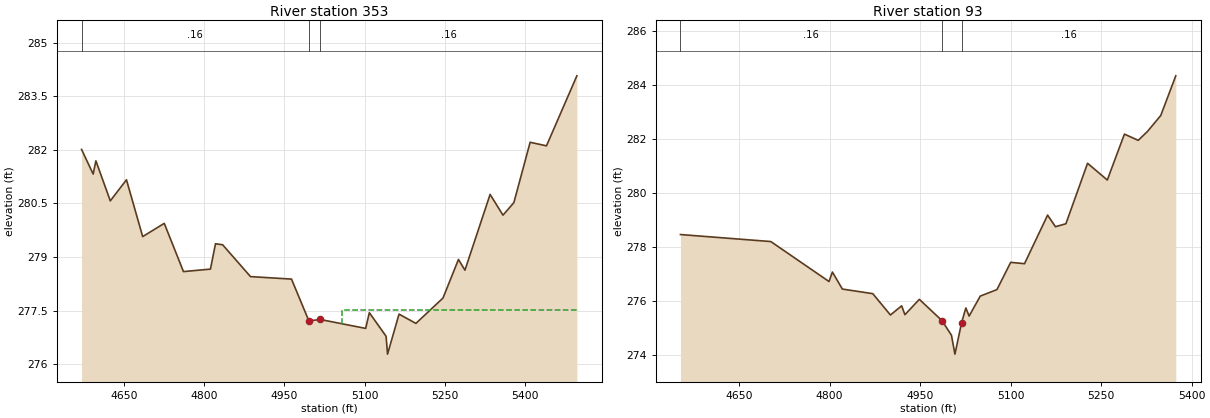
Type RM Length L Ch R = 1 ,353     ,260,260,260
BEGIN DESCRIPTION:
Mapping XS 02aa6e19
END DESCRIPTION:
XS GIS Cut Line= 6
      2272504.38     13189764.85        2272694.     13189741.96
      2272870.54     13189645.52      2272986.59     13189539.27
      2273022.55     13189385.62      2272985.13     13189170.86
#Sta/Elev= 30
  4570.9  282.01  4592.6  281.32  4597.7  281.69  4624.6  280.57  4654.8  281.16
  4685.1  279.57  4725.4  279.94  4761.3  278.59  4811.7  278.66  4821.1  279.37
  4834.5  279.34  4886.5  278.45  4963.1  278.38  4995.6  277.21  5016.6  277.25
  5101.7     277  5108.5  277.44  5139.8  276.78  5142.5  276.28    5164   277.4
  5195.5  277.14  5246.1  277.85    5275  278.93  5287.1  278.63  5334.1  280.75
  5358.2  280.17  5378.5  280.52  5408.9  282.21  5439.4  282.11  5496.2  284.07
#Mann= 3 , 0 , 0
  4570.9     .16       0  4995.6     .07       0  5016.6     .16       0
#XS Ineff= 2 , 0
       0                 5057.31       0  277.51
Permanent Ineff=
       F       T
Bank Sta=4995.6,5016.6
XS Rating Curve= 0 ,0
Exp/Cntr=0.3,0.1

Type RM Length L Ch R = 1 ,93      ,0,0,0
BEGIN DESCRIPTION:
UNT302 IN PECR 1.0
END DESCRIPTION:
XS GIS Cut Line= 4
      2272764.71     13189735.38       2273074.7      13189574.9
       2273137.2     13189423.86      2273006.98     13189144.33
#Sta/Elev= 30
  4552.8  278.46  4702.6   278.2    4799  276.72  4804.6  277.07  4821.2  276.44
  4871.5  276.27  4900.8  275.48  4919.4  275.82  4924.8  275.49  4948.7  276.06
  4986.3  275.27  5001.9  274.73  5007.7  274.03  5018.8   275.2  5025.8  275.74
  5031.2  275.44  5049.7  276.18  5077.3  276.42  5100.1  277.43    5123  277.38
  5161.3  279.18  5174.3  278.75  5191.6  278.86  5227.5   281.1  5260.2  280.48
  5288.6  282.18  5311.5  281.95  5326.8  282.28  5348.8  282.87  5373.7  284.34
#Mann= 3 , 0 , 0
  4552.8     .16       0  4986.3     .07       0  5018.8     .16       0
Bank Sta=4986.3,5018.8
XS Rating Curve= 0 ,0
Exp/Cntr=0.3,0.1

Chan Stop Cuts=-1
Use User Specified Reach Order=0
Composite Channel Slope=5