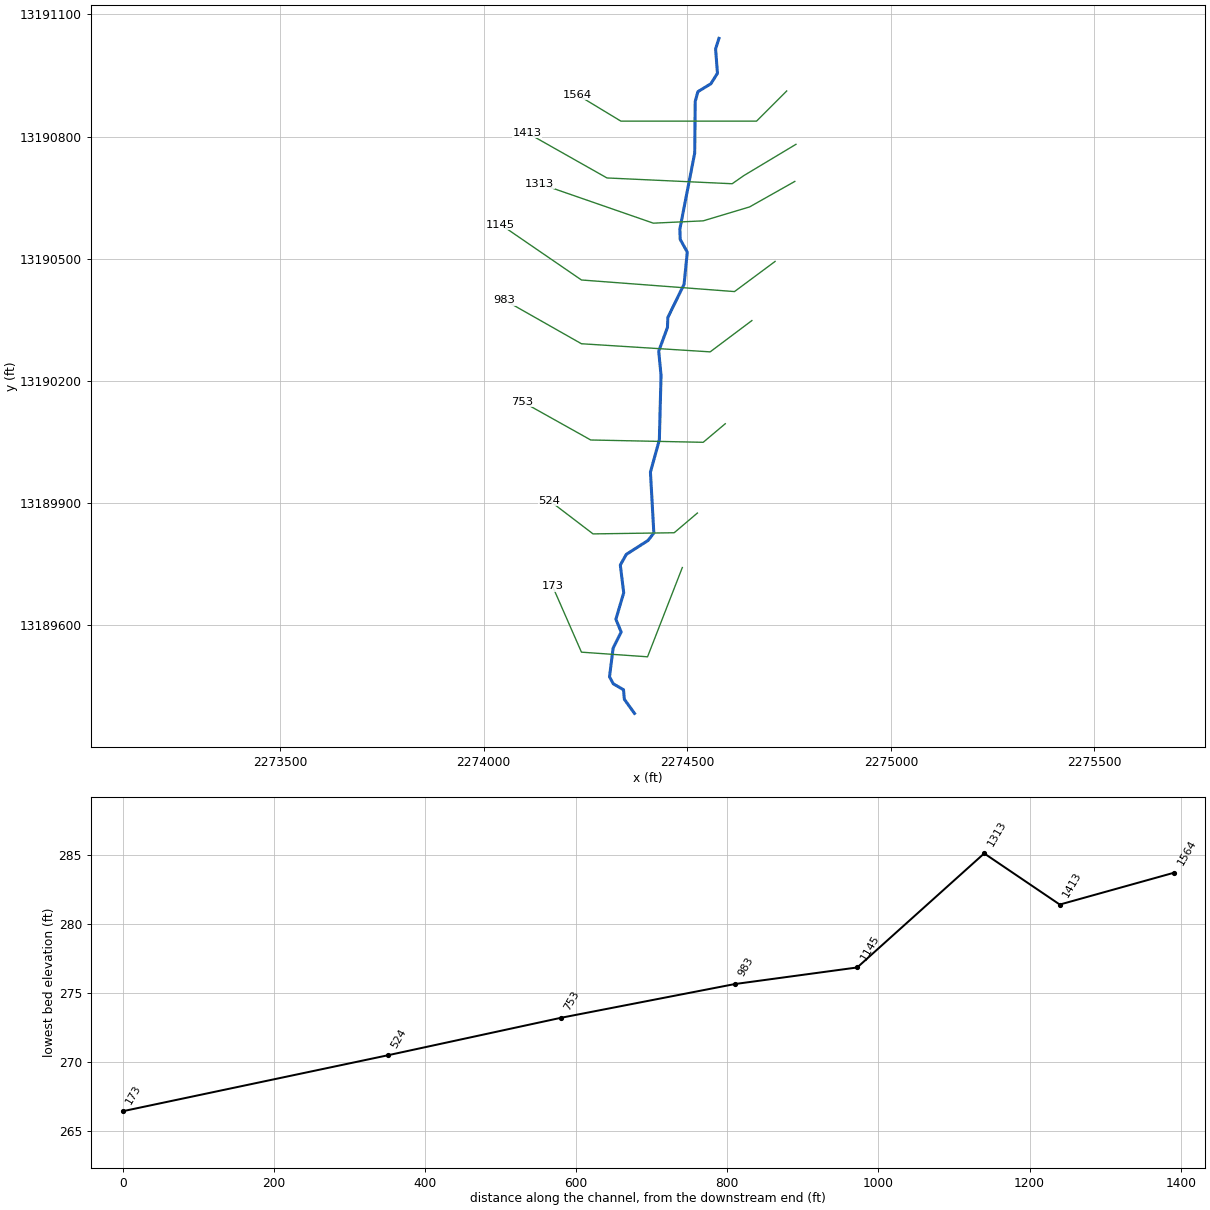
--- UNT303 IN PECR.prj (project) ---

Proj Title=UNT303 IN PECR Base Level Engineering
Current Plan=p01
Default Exp/Contr=0.3,0.1
English Units
Geom File=g01
Flow File=f01
Plan File=p01
Y Axis Title=Elevation
X Axis Title(PF)=Main Channel Distance
X Axis Title(XS)=Station
BEGIN DESCRIPTION:
UNT303 IN PECR
END DESCRIPTION:
DSS Export Rating Curves= 0
DSS Export Rating Curve Sorted= 0
DSS Export Volume Flow Curves= 0
DXF OffsetX= 0
DXF OffsetY= 0
DXF ScaleX= 1
DXF ScaleY= 10

--- UNT303 IN PECR.p01 (plan) ---

Plan Title=Multiple Run
Short Identifier=Multiple
Geom File=g01
Flow File=f01
Subcritical Flow
K Sum by GR= 0
Std Step Tol= 0.01
Critical Tol= 0.01
Num of Std Step Trials= 20
Max Error Tol= 0.3
Flow Tol Ratio= 0.001
Split Flow NTrial= 30
Split Flow Tol= 0.02
Split Flow Ratio= 0.02
Log Output Level= 0
Friction Slope Method= 1
Unsteady Friction Slope Method= 2
Unsteady Bridges Friction Slope Method= 1
Parabolic Critical Depth
Global Vel Dist=  1 , 1 , 1
Global Log Level= 0
CheckData=True
Encroach Param= -1, 0, 0, 0
BEGIN DESCRIPTION:
Multiple Run
END DESCRIPTION:

--- UNT303 IN PECR.f01 (steady flow) ---

Flow Title=Multiple
Number of Profiles=7
Profile Names=10-year,25-year,50-year,1pct_min,100-year,1pct_plu,500-year
River Rch & RM= UNT303 IN PECR,Reach-1,1564
      34      40      45      38      51      69      65
Boundary for River Rch & Prof#=UNT303 IN PECR,Reach-1,1
Up Type=0
Dn Type=3
Dn Slope=0.005
Boundary for River Rch & Prof#=UNT303 IN PECR,Reach-1,2
Up Type=0
Dn Type=3
Dn Slope=0.005
Boundary for River Rch & Prof#=UNT303 IN PECR,Reach-1,3
Up Type=0
Dn Type=3
Dn Slope=0.005
Boundary for River Rch & Prof#=UNT303 IN PECR,Reach-1,4
Up Type=0
Dn Type=3
Dn Slope=0.005
Boundary for River Rch & Prof#=UNT303 IN PECR,Reach-1,5
Up Type=0
Dn Type=3
Dn Slope=0.005
Boundary for River Rch & Prof#=UNT303 IN PECR,Reach-1,6
Up Type=0
Dn Type=3
Dn Slope=0.005
Boundary for River Rch & Prof#=UNT303 IN PECR,Reach-1,7
Up Type=0
Dn Type=3
Dn Slope=0.005

--- UNT303 IN PECR.g01 (geometry) ---

Geom Title=Existing Conditions
Program Version=4.10

River Reach=UNT303 IN PECR  ,Reach-1
Reach XY= 30
        2274578.     13191041.04      2274569.67     13191015.22
      2274574.25     13190955.25      2274558.01     13190929.43
      2274526.19      13190910.1      2274519.68     13190886.23
      2274518.37     13190759.28      2274481.92     13190572.65
      2274482.78     13190547.47      2274500.14     13190516.22
      2274492.33     13190437.23       2274452.4     13190355.63
      2274451.53     13190331.33      2274430.01     13190272.82
      2274435.73     13190213.45      2274431.57     13190055.11
      2274409.69     13189975.95      2274418.03     13189826.47
      2274403.96     13189808.24      2274350.32     13189773.86
      2274335.73     13189747.82      2274344.07     13189679.59
      2274324.85     13189614.68      2274337.82     13189583.24
      2274318.03     13189543.65      2274309.17     13189473.34
      2274318.55     13189456.15      2274343.55     13189441.57
      2274345.63     13189418.13      2274370.56     13189383.57

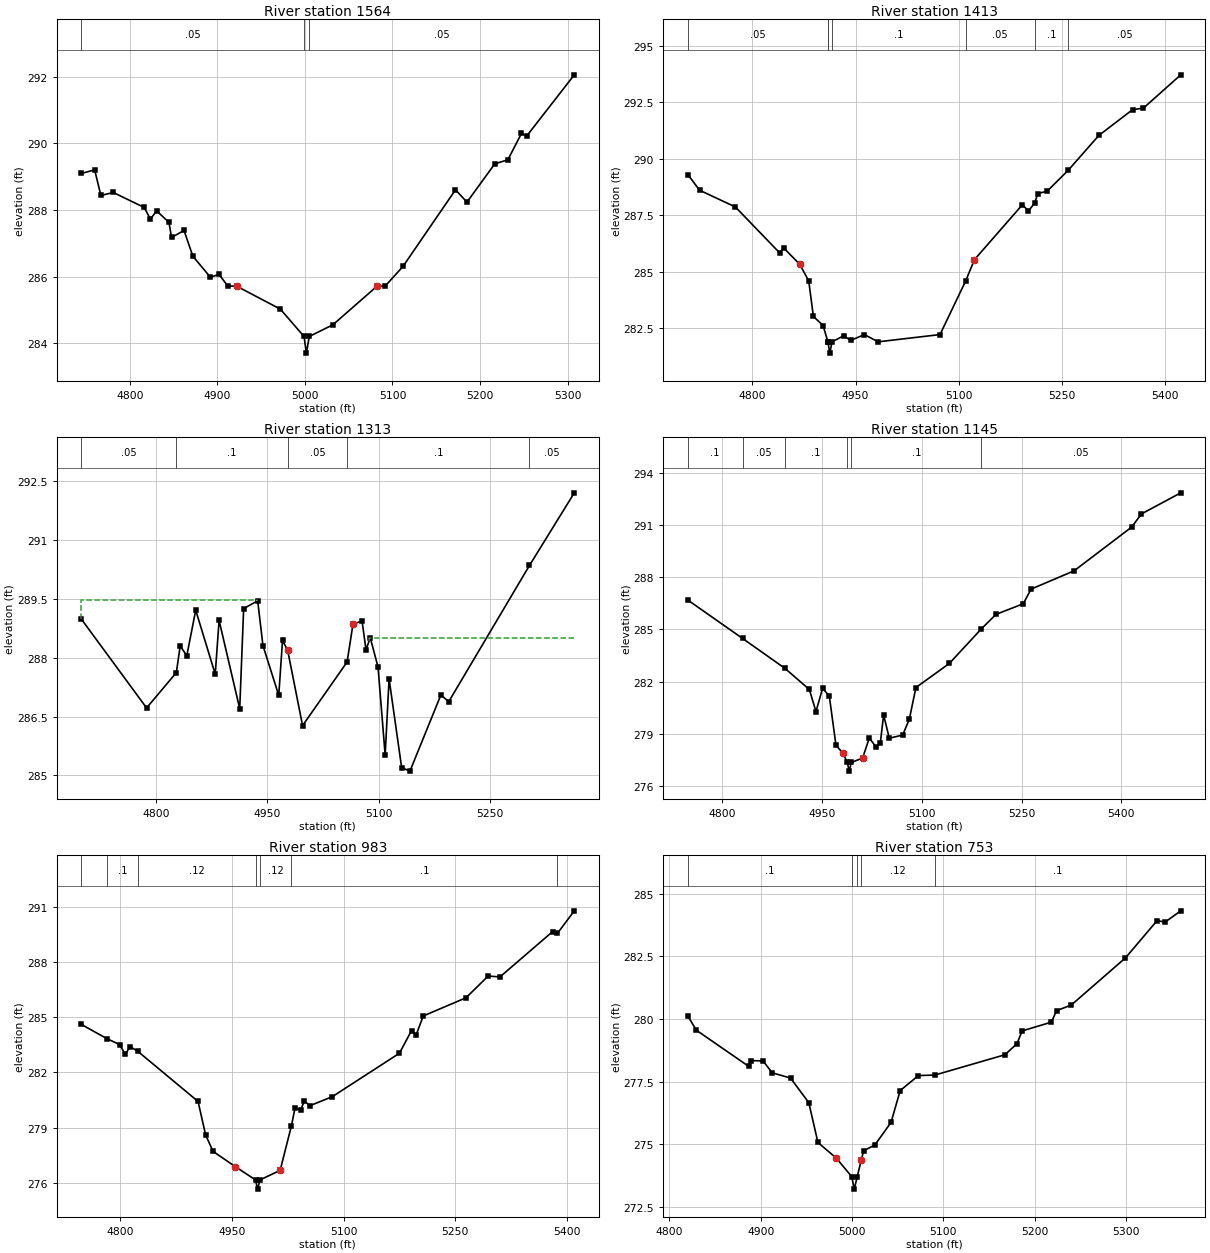
Type RM Length L Ch R = 1 ,1564    ,151,151,151
BEGIN DESCRIPTION:
UNT303 IN PECR 2.0
END DESCRIPTION:
XS GIS Cut Line= 4
      2274744.23     13190911.77       2274670.2     13190837.74
      2274337.12     13190837.74      2274230.08     13190902.53
#Sta/Elev= 30
  4744.8   289.1  4759.9  289.21    4767  288.44  4781.2  288.53  4816.5  288.08
  4823.6  287.73  4830.7  287.98  4844.8  287.63  4847.7  287.18    4862  287.39
    4872  286.62    4892  285.99    4902  286.07    4912  285.72    4922  285.72
    4972  285.03    4999  284.21  5001.7  283.71    5005  284.21    5032  284.56
    5082  285.71    5092  285.73    5112  286.31    5172  288.61  5185.1  288.24
  5216.9  289.39  5231.8  289.51  5247.3   290.3  5253.2  290.22  5307.7  292.06
#Mann= 3 ,-1 , 0
  4744.8     .05       0    4999    .035       0    5005     .05       0
Bank Sta=4922,5082
XS Rating Curve= 0 ,0
Exp/Cntr=0.3,0.1

Type RM Length L Ch R = 1 ,1413    ,100,100,100
BEGIN DESCRIPTION:
Mapping XS 4dee1c74
END DESCRIPTION:
XS GIS Cut Line= 5
      2274766.97     13190780.78      2274638.89     13190703.93
      2274610.42     13190684.01      2274302.96     13190698.24
      2274106.56     13190809.24
#Sta/Elev= 30
    4706   289.3    4723  288.61  4775.1  287.87  4839.6  285.84  4845.4  286.06
    4869  285.33  4881.9   284.6  4888.7  283.03  4902.8  282.63  4909.7  281.92
  4909.8  281.91  4912.6  281.41  4915.8  281.91  4932.9  282.18  4942.9  281.97
  4962.9  282.23  4982.9  281.91    5073  282.23  5110.5  284.61  5123.1  285.54
    5193  287.97  5201.7  287.69  5210.7  288.04  5215.4  288.46  5229.1  288.57
  5259.9   289.5  5304.2  291.03  5353.3  292.17  5369.2  292.24  5423.5  293.71
#Mann= 7 ,-1 , 0
    4706     .05       0  4909.7      .1       0  4909.8     .07       0
  4915.8      .1       0  5110.5     .05       0  5210.7      .1       0
  5259.9     .05       0
Bank Sta=4869,5123.1
XS Rating Curve= 0 ,0
Exp/Cntr=0.3,0.1

Type RM Length L Ch R = 1 ,1313    ,168,168,168
BEGIN DESCRIPTION:
Mapping XS 246d4865
END DESCRIPTION:
XS GIS Cut Line= 5
      2274764.16      13190689.7      2274653.12     13190627.07
      2274539.25      13190592.9      2274416.83     13190587.21
      2274137.87     13190683.99
#Sta/Elev= 30
  4699.5  288.98  4787.3  286.72  4827.4  287.62  4832.6   288.3  4841.5  288.05
  4853.5  289.21  4879.8  287.58    4885  288.95  4912.8   286.7  4918.1  289.25
    4937  289.45  4944.1  288.31  4965.4  287.04  4970.5  288.44  4977.4  288.19
  4997.5  286.27  5057.5  287.89  5065.5  288.86  5077.7  288.93    5083   288.2
  5088.7  288.51  5099.2  287.76  5108.8  285.52  5114.1  287.46    5131   285.2
  5142.2  285.11  5183.9  287.05  5194.5  286.88  5303.3  290.35  5363.7   292.2
#Mann= 5 ,-1 , 0
  4699.5     .05       0  4827.4      .1       0  4977.4     .05       0
  5057.5      .1       0  5303.3     .05       0
#XS Ineff= 2 , 0
       0 4935.91  289.47 5087.29       0  288.51
Permanent Ineff=
       T       T
Bank Sta=4977.4,5065.5
XS Rating Curve= 0 ,0
Exp/Cntr=0.3,0.1

Type RM Length L Ch R = 1 ,1145    ,162,162,162
BEGIN DESCRIPTION:
Mapping XS cc3eebf8
END DESCRIPTION:
XS GIS Cut Line= 4
      2274715.75     13190493.26      2274616.11     13190419.24
      2274240.33     13190447.71      2274041.88     13190583.79
#Sta/Elev= 30
    4748  286.68  4830.2  284.48  4893.7  282.77  4930.7  281.55  4940.7  280.28
  4950.7  281.62  4960.8  281.16  4970.8  278.34  4980.8  277.92  4987.9  277.36
  4990.6  276.86  4993.9  277.36  5010.9  277.61  5020.9  278.76    5031  278.25
  5037.5  278.47  5042.5  280.09    5051  278.75  5071.1  278.93  5081.1  279.83
  5091.1  281.66  5141.3  283.04  5189.6  285.03  5211.5  285.86  5252.6  286.47
  5264.3  287.31    5329  288.36  5415.6  290.87  5430.5  291.63  5489.6  292.84
#Mann= 6 ,-1 , 0
    4748      .1       0  4830.2     .05       0  4893.7      .1       0
  4987.9     .07       0  4993.9      .1       0  5189.6     .05       0
Bank Sta=4980.8,5010.9
XS Rating Curve= 0 ,0
Exp/Cntr=0.3,0.1

Type RM Length L Ch R = 1 ,983     ,230,230,230
BEGIN DESCRIPTION:
Mapping XS f5aaa6a2
END DESCRIPTION:
XS GIS Cut Line= 4
      2274658.79     13190348.05      2274556.33     13190271.21
      2274240.33     13190291.14      2274051.14     13190398.44
#Sta/Elev= 30
  4747.9   284.6  4782.1  283.83  4799.2  283.51  4806.9  282.97  4813.1   283.4
  4823.7  283.14  4904.6  280.42  4914.7  278.61  4924.7  277.71  4954.7  276.88
  4981.8  276.16  4984.5  275.66  4987.8  276.16  5014.9  276.68  5030.1  279.11
  5034.9  280.07  5042.5  279.98  5047.5  280.44  5054.9  280.19    5085  280.68
  5175.2  283.04  5191.4  284.27  5197.7  284.04  5207.1  285.06  5264.6  286.05
  5294.4  287.23  5310.2  287.18  5380.9  289.64  5387.3  289.54  5410.1  290.77
#Mann= 7 ,-1 , 0
  4747.9     .05       0  4782.1      .1       0  4823.7     .12       0
  4981.8     .07       0  4987.8     .12       0  5030.1      .1       0
  5387.3     .05       0
Bank Sta=4954.7,5014.9
XS Rating Curve= 0 ,0
Exp/Cntr=0.3,0.1

Type RM Length L Ch R = 1 ,753     ,229,229,229
BEGIN DESCRIPTION:
Mapping XS a04aba74
END DESCRIPTION:
XS GIS Cut Line= 4
      2274593.37     13190094.72      2274539.25     13190049.15
       2274263.1     13190054.84      2274095.15     13190148.78
#Sta/Elev= 30
  4820.4  280.12  4829.6  279.56  4886.8  278.12  4889.1  278.35  4902.7  278.33
  4912.7  277.86  4932.7  277.65  4952.7  276.67  4962.7  275.08  4982.7  274.46
  4999.7  273.72  5002.5  273.22  5005.7  273.72  5010.3   274.4  5012.7  274.75
    5025  274.98  5042.7  275.88  5052.7  277.15  5072.7  277.75  5090.7  277.77
  5167.4  278.58  5180.5  279.02  5186.2  279.53  5218.2  279.88  5223.9  280.34
  5239.9  280.56  5299.2  282.44  5333.9  283.93  5342.6  283.87  5359.8  284.32
#Mann= 5 ,-1 , 0
  4820.4      .1       0  4999.7     .07       0  5005.7      .1       0
  5010.3     .12       0  5090.7      .1       0
Bank Sta=4982.7,5010.3
XS Rating Curve= 0 ,0
Exp/Cntr=0.3,0.1

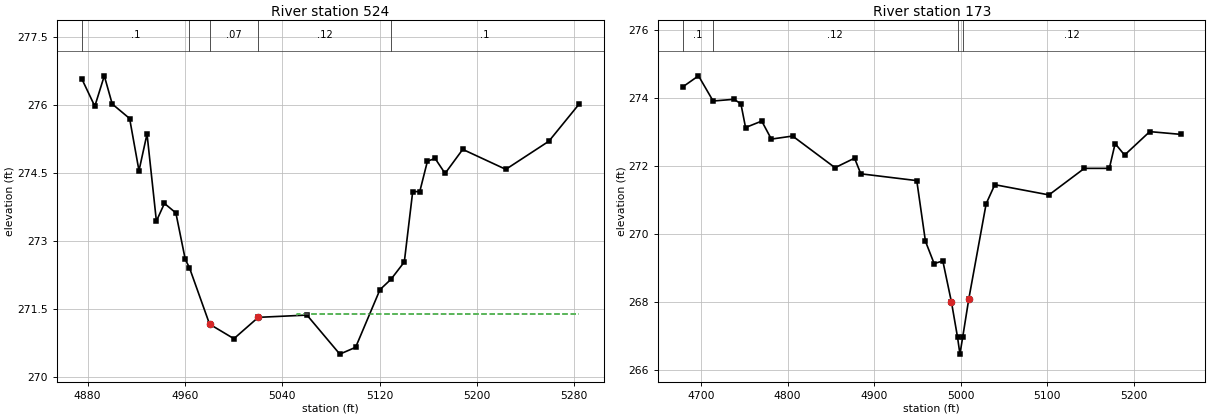
Type RM Length L Ch R = 1 ,524     ,351,351,351
BEGIN DESCRIPTION:
Mapping XS b36e5c9b
END DESCRIPTION:
XS GIS Cut Line= 4
      2274524.99     13189875.47      2274468.08     13189827.09
      2274268.79     13189824.25      2274161.63     13189906.03
#Sta/Elev= 30
  4875.2  276.58    4886  275.97  4893.8  276.64  4900.3  276.02  4914.6   275.7
  4922.3  274.55  4928.9  275.36  4936.6  273.44  4943.2  273.83  4952.6  273.62
  4960.3   272.6  4963.8  272.41  4980.3  271.17  5000.3  270.85  5020.3  271.32
  5060.3  271.37  5087.3  270.51  5100.3  270.66  5120.3  271.93  5129.4  272.16
  5140.3  272.54  5147.2  274.09    5153  274.09  5159.3  274.76  5165.6  274.82
  5173.8  274.49  5188.3  275.02  5223.7  274.58  5259.1   275.2    5284  276.02
#Mann= 5 ,-1 , 0
  4875.2      .1       0  4963.8     .12       0  4980.3     .07       0
  5020.3     .12       0  5129.4      .1       0
#XS Ineff= 2 , 0
       0                 5052.07       0   271.4
Permanent Ineff=
       F       T
Bank Sta=4980.3,5020.3
XS Rating Curve= 0 ,0
Exp/Cntr=0.3,0.1

Type RM Length L Ch R = 1 ,173     ,0,0,0
BEGIN DESCRIPTION:
UNT303 IN PECR 1.0
END DESCRIPTION:
XS GIS Cut Line= 4
        2274488.     13189741.67       2274402.6     13189522.48
      2274240.33     13189533.86      2274169.16     13189696.13
#Sta/Elev= 30
  4679.1  274.32    4697  274.64  4713.9   273.9  4737.9  273.95    4746  273.82
  4751.4  273.12  4770.1  273.31  4781.2  272.78  4805.8  272.87  4854.8  271.94
  4877.4  272.22  4884.6  271.76  4949.3  271.56  4959.3  269.78  4969.4  269.12
  4979.4   269.2  4989.4  267.99  4996.4  266.96  4999.2  266.46  5002.4  266.96
  5009.5  268.09  5029.5  270.88  5039.5  271.44  5102.1  271.14    5143  271.92
  5171.9  271.92  5178.6  272.65  5189.5  272.31  5218.6     273  5254.2  272.92
#Mann= 4 ,-1 , 0
  4679.1      .1       0  4713.9     .12       0  4996.4     .07       0
  5002.4     .12       0
Bank Sta=4989.4,5009.5
XS Rating Curve= 0 ,0
Exp/Cntr=0.3,0.1

Chan Stop Cuts=-1
Use User Specified Reach Order=0
Composite Channel Slope=5