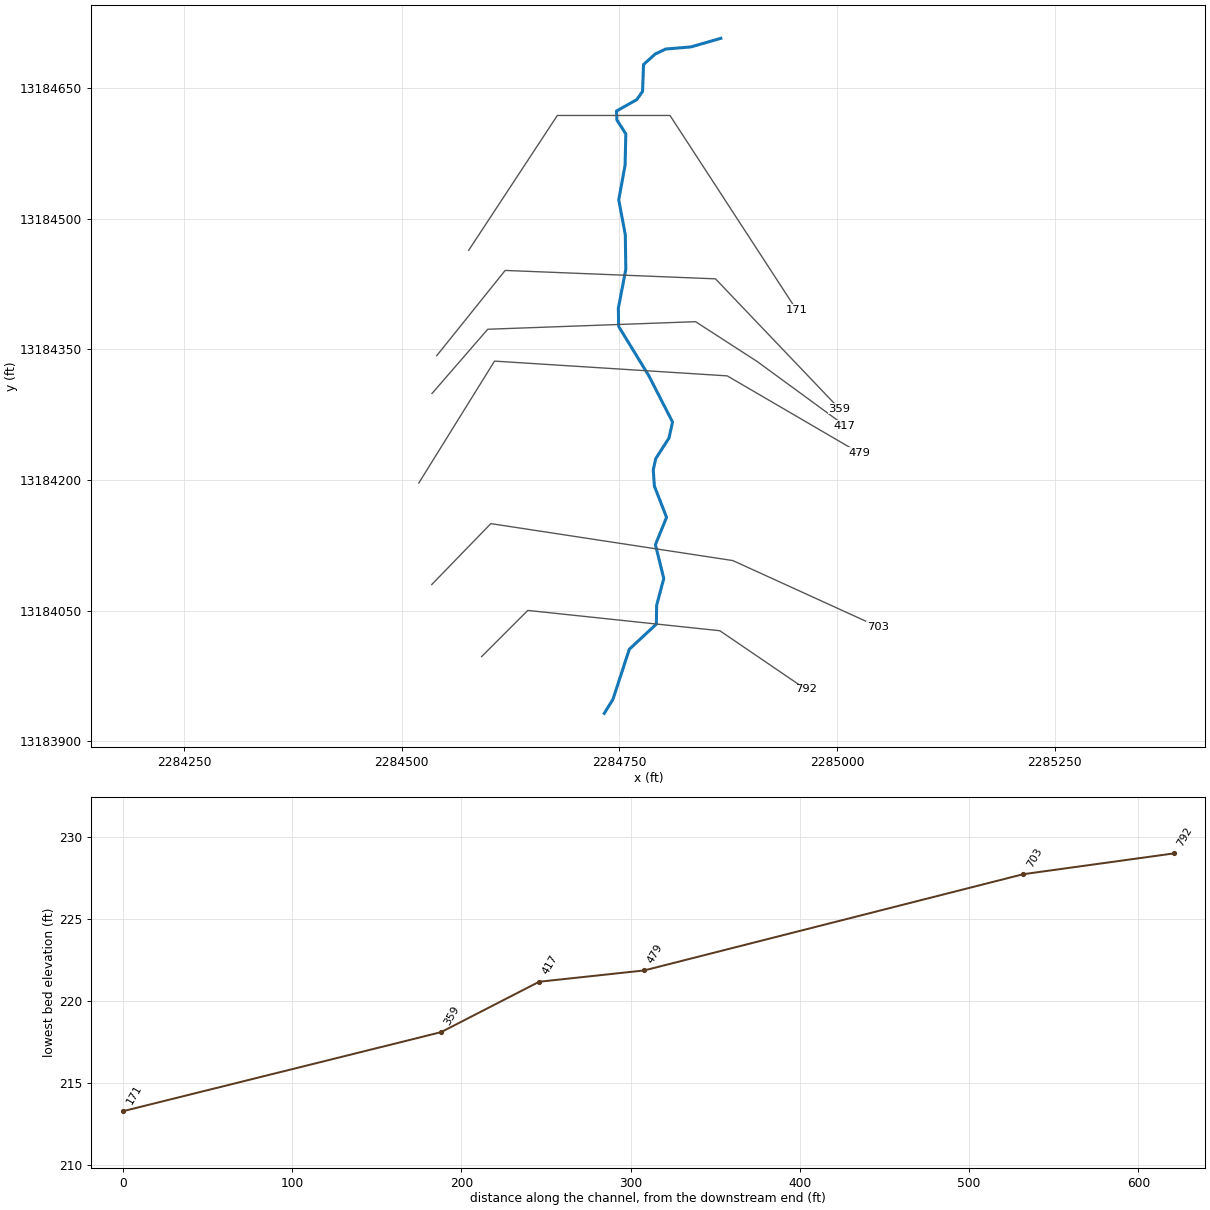
--- UNT304 IN PECR.prj (project) ---

Proj Title=UNT304 IN PECR Base Level Engineering
Current Plan=p01
Default Exp/Contr=0.3,0.1
English Units
Geom File=g01
Flow File=f01
Plan File=p01
Y Axis Title=Elevation
X Axis Title(PF)=Main Channel Distance
X Axis Title(XS)=Station
BEGIN DESCRIPTION:
UNT304 IN PECR
END DESCRIPTION:
DSS Export Rating Curves= 0
DSS Export Rating Curve Sorted= 0
DSS Export Volume Flow Curves= 0
DXF OffsetX= 0
DXF OffsetY= 0
DXF ScaleX= 1
DXF ScaleY= 10

--- UNT304 IN PECR.p01 (plan) ---

Plan Title=Multiple Run
Short Identifier=Multiple
Geom File=g01
Flow File=f01
Subcritical Flow
K Sum by GR= 0
Std Step Tol= 0.01
Critical Tol= 0.01
Num of Std Step Trials= 20
Max Error Tol= 0.3
Flow Tol Ratio= 0.001
Split Flow NTrial= 30
Split Flow Tol= 0.02
Split Flow Ratio= 0.02
Log Output Level= 0
Friction Slope Method= 1
Unsteady Friction Slope Method= 2
Unsteady Bridges Friction Slope Method= 1
Parabolic Critical Depth
Global Vel Dist=  1 , 1 , 1
Global Log Level= 0
CheckData=True
Encroach Param= -1, 0, 0, 0
BEGIN DESCRIPTION:
Multiple Run
END DESCRIPTION:

--- UNT304 IN PECR.f01 (steady flow) ---

Flow Title=Multiple
Program Version=4.10
Number of Profiles= 7
Profile Names=10-year,25-year,50-year,1pct_min,100-year,1pct_plu,500-year
River Rch & RM=UNT304 IN PECR,Reach-1         ,792
      49      61      69      59      80     108     105
Boundary for River Rch & Prof#=UNT304 IN PECR,Reach-1         , 1
Up Type= 0
Dn Type= 3
Dn Slope=0.0141
Boundary for River Rch & Prof#=UNT304 IN PECR,Reach-1         , 2
Up Type= 0
Dn Type= 3
Dn Slope=0.0141
Boundary for River Rch & Prof#=UNT304 IN PECR,Reach-1         , 3
Up Type= 0
Dn Type= 3
Dn Slope=0.0141
Boundary for River Rch & Prof#=UNT304 IN PECR,Reach-1         , 4
Up Type= 0
Dn Type= 3
Dn Slope=0.0141
Boundary for River Rch & Prof#=UNT304 IN PECR,Reach-1         , 5
Up Type= 0
Dn Type= 3
Dn Slope=0.0141
Boundary for River Rch & Prof#=UNT304 IN PECR,Reach-1         , 6
Up Type= 0
Dn Type= 3
Dn Slope=0.0141
Boundary for River Rch & Prof#=UNT304 IN PECR,Reach-1         , 7
Up Type= 0
Dn Type= 3
Dn Slope=0.0141
DSS Import GetInterval= 0
DSS Import GetPeak= 0
DSS Import FillOption= 0

--- UNT304 IN PECR.g01 (geometry) ---

Geom Title=Existing Conditions
Program Version=4.10

River Reach=UNT304 IN PECR  ,Reach-1
Reach XY= 30
      2284732.72     13183931.86      2284742.69     13183948.09
      2284761.46     13184005.49      2284792.51     13184034.39
      2284792.87     13184055.93      2284801.06     13184086.79
      2284791.43     13184125.63      2284804.26     13184157.05
      2284790.29     13184192.93      2284788.95     13184211.47
      2284791.84     13184224.55      2284806.99     13184247.99
      2284811.12     13184266.54      2284783.81     13184319.82
      2284749.21     13184376.33      2284748.87     13184397.24
      2284757.45     13184441.94      2284756.88     13184481.52
      2284749.32     13184521.85      2284756.62      13184561.5
      2284757.44     13184597.49      2284747.18     13184613.55
      2284746.75     13184623.75      2284769.97     13184636.77
       2284776.7     13184646.32       2284777.8     13184677.15
      2284791.17      13184689.2      2284803.24     13184694.94
      2284832.37     13184697.42      2284866.63     13184707.25

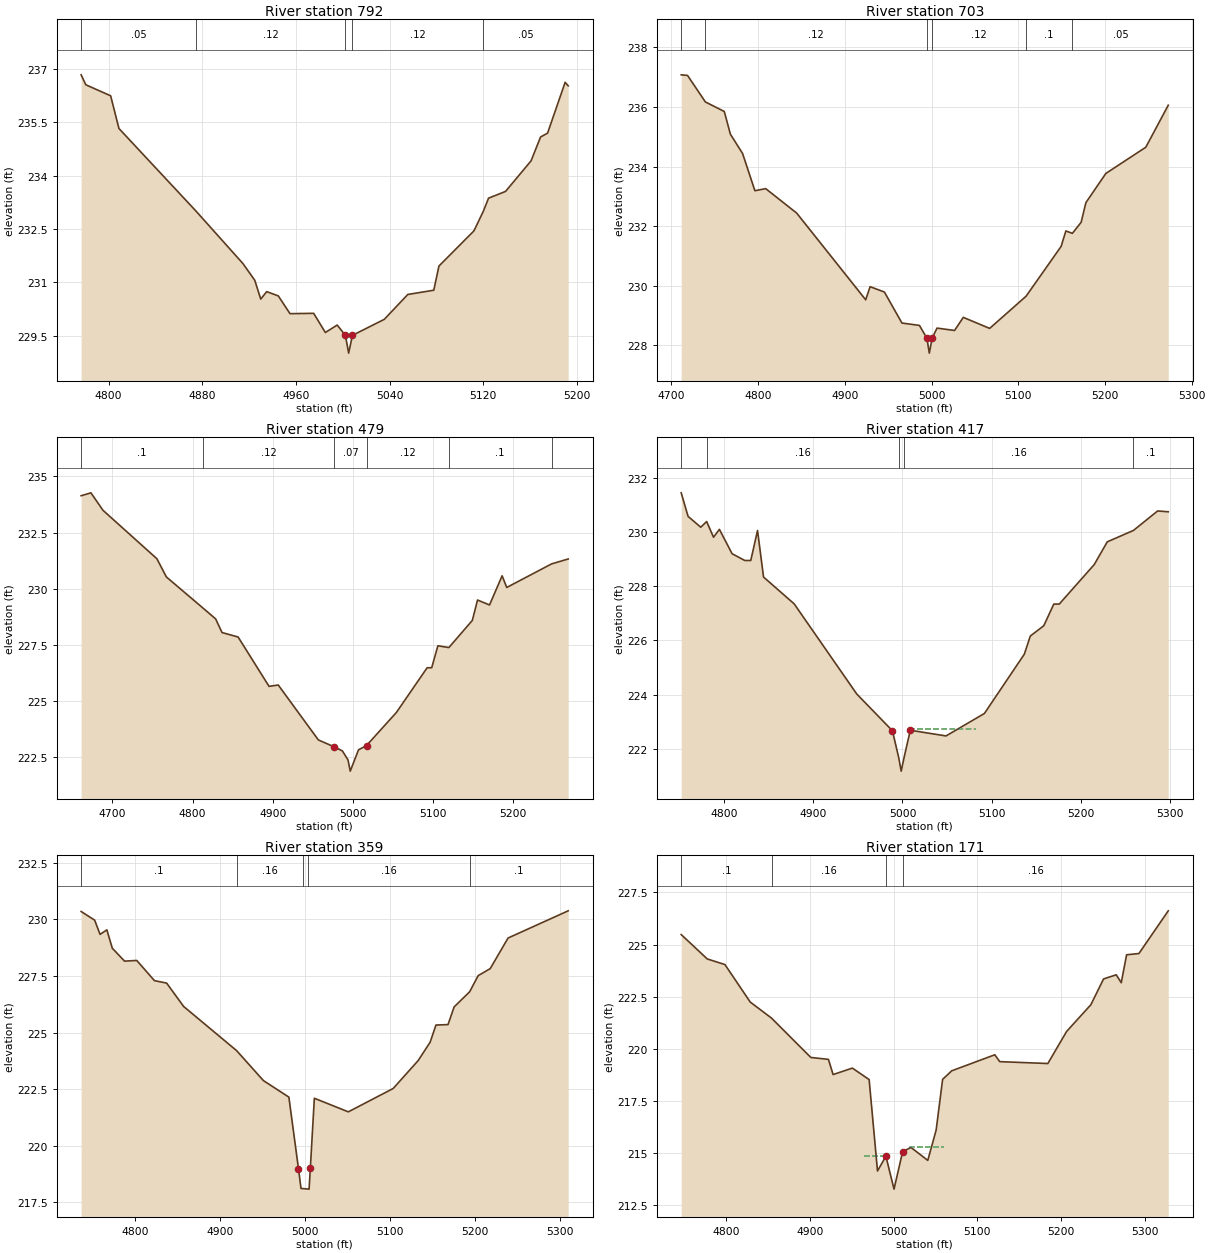
Type RM Length L Ch R = 1 ,792     ,89,89,89
BEGIN DESCRIPTION:
UNT304 IN PECR 2.0
END DESCRIPTION:
XS GIS Cut Line= 4
      2284591.82     13183997.09      2284644.84     13184050.12
      2284865.46     13184026.79      2284963.96     13183959.73
#Sta/Elev= 30
  4776.5  236.84  4780.5  236.56  4801.7  236.25  4808.8  235.33  4874.5  233.01
  4914.7  231.53  4924.8  231.06  4929.9  230.53    4935  230.74  4944.9  230.62
  4954.9  230.12  4975.1  230.13  4985.1  229.59  4995.2   229.8  5002.2  229.51
    5005  229.01  5008.2  229.51  5035.4  229.96  5055.5  230.66  5077.7  230.78
  5082.1  231.46    5112  232.45    5120     233  5124.5  233.37    5139  233.56
  5160.8  234.42  5168.9  235.09  5174.9   235.2  5189.9  236.63  5192.5  236.53
#Mann= 5 ,-1 , 0
  4776.5     .05       0  4874.5     .12       0  5002.2     .07       0
  5008.2     .12       0    5120     .05       0
Bank Sta=5002.2,5008.2
XS Rating Curve= 0 ,0
Exp/Cntr=0.3,0.1

Type RM Length L Ch R = 1 ,703     ,224,224,224
BEGIN DESCRIPTION:
Mapping XS d72b38ae
END DESCRIPTION:
XS GIS Cut Line= 4
      2284534.54     13184079.82      2284602.42     13184149.82
      2284880.31      13184107.4        2285047.     13184031.44
#Sta/Elev= 30
  4711.2  237.08  4718.5  237.06  4739.1  236.17  4760.9  235.85  4767.9  235.09
    4782  234.44  4796.2  233.19  4808.7  233.26  4844.4  232.44    4924  229.53
  4929.1  229.97  4945.6  229.79  4965.8  228.75    4986  228.67  4994.6  228.24
  4997.4  227.74  5000.6  228.24  5006.3  228.58  5026.5   228.5  5036.6  228.94
    5067  228.57    5109  229.65  5149.4  231.32  5154.9  231.84  5162.4  231.76
  5172.5  232.13    5178  232.79    5201  233.77  5247.1  234.65    5273  236.06
#Mann= 6 ,-1 , 0
  4711.2     .05       0  4739.1     .12       0  4994.6     .07       0
  5000.6     .12       0    5109      .1       0  5162.4     .05       0
Bank Sta=4994.6,5000.6
XS Rating Curve= 0 ,0
Exp/Cntr=0.3,0.1

Type RM Length L Ch R = 1 ,479     ,62,62,62
BEGIN DESCRIPTION:
Mapping XS a8b4113d
END DESCRIPTION:
XS GIS Cut Line= 4
      2284519.68     13184196.49      2284606.66      13184336.5
      2284873.95     13184319.53      2285025.49     13184231.13
#Sta/Elev= 30
  4660.9  234.14  4673.1  234.27  4688.2  233.49  4755.5  231.33  4767.3  230.52
  4813.4  229.12  4828.8  228.65  4836.8  228.04  4856.9  227.84  4895.5  225.64
    4907   225.7  4957.1  223.25  4977.1  222.94  4987.1  222.76  4994.1  222.36
  4996.9  221.86  5007.2  222.81  5017.2     223  5054.6  224.48  5092.9  226.47
  5098.6  226.47  5106.3  227.45    5120  227.37  5149.3  228.58  5155.8  229.49
  5170.8  229.27  5186.5  230.57  5192.3  230.05  5248.2   231.1    5269  231.32
#Mann= 6 ,-1 , 0
  4660.9      .1       0  4813.4     .12       0  4977.1     .07       0
  5017.2     .12       0    5120      .1       0  5248.2     .05       0
Bank Sta=4977.1,5017.2
XS Rating Curve= 0 ,0
Exp/Cntr=0.3,0.1

Type RM Length L Ch R = 1 ,417     ,58,58,58
XS GIS Cut Line= 5
      2284534.86     13184299.33      2284598.85     13184373.09
      2284837.57     13184381.77       2284908.1     13184336.19
      2285009.01     13184262.41
#Sta/Elev= 30
  4752.2  231.45  4759.9  230.58  4774.1  230.18  4780.7  230.39  4788.4  229.81
    4795   230.1  4809.2   229.2  4823.5  228.95  4830.1  228.95  4837.7  230.06
  4844.4  228.34  4878.7  227.35  4948.8  224.02  4988.8  222.66  4995.8  221.67
  4998.6  221.17  5001.8  221.67  5008.8  222.68  5048.8  222.47  5091.8   223.3
  5136.5  225.49  5143.2  226.16  5158.3  226.54  5169.5  227.34  5175.6  227.34
  5214.8   228.8  5229.4  229.64  5258.7  230.06  5285.8  230.78  5297.7  230.75
#Mann= 5 ,-1 , 0
  4752.2      .1       0  4780.7     .16       0  4995.8     .07       0
  5001.8     .16       0  5258.7      .1       0
#XS Ineff= 1 ,-1
 5008.81 5082.39  222.72
Permanent Ineff=
       T
Bank Sta=4988.8,5008.8
XS Rating Curve= 0 ,0
Exp/Cntr=0.3,0.1

Type RM Length L Ch R = 1 ,359     ,188,188,188
BEGIN DESCRIPTION:
Mapping XS 36d4cb08
END DESCRIPTION:
XS GIS Cut Line= 4
      2284540.22     13184342.68      2284618.87     13184440.65
      2284860.44     13184430.99      2285002.71     13184281.87
#Sta/Elev= 30
  4736.1  230.34    4752  229.96  4758.4  229.33  4766.4  229.53  4772.8  228.72
  4787.2  228.15  4801.6  228.18  4822.4  227.29  4836.8  227.18  4856.8  226.15
  4919.2   224.2  4950.7  222.88  4980.7  222.15 4992.03  218.99 4994.97  218.12
 5004.51  218.09 5005.97  219.01  5010.7   222.1  5050.7   221.5  5103.5  222.53
  5132.9  223.76    5147  224.57  5153.9  225.33  5168.1  225.35  5175.3  226.13
  5193.6   226.8  5203.6  227.51  5217.8  227.82  5238.8  229.17  5309.6  230.37
#Mann= 5 ,-1 , 0
  4736.1      .1       0  4919.2     .16       0  4997.7     .07       0
  5003.7     .16       0  5193.6      .1       0
Bank Sta=4992.03,5005.97
XS Rating Curve= 0 ,0
Exp/Cntr=0.3,0.1

Type RM Length L Ch R = 1 ,171     ,0,0,0
BEGIN DESCRIPTION:
UNT304 IN PECR 1.0
END DESCRIPTION:
XS GIS Cut Line= 4
      2284576.97      13184463.8      2284678.79     13184618.64
      2284808.19     13184618.64      2284953.62     13184395.22
#Sta/Elev= 30
  4746.5  225.48  4777.6  224.31  4798.7  224.04  4828.9  222.24  4854.3  221.47
  4901.2  219.58  4922.2  219.49  4927.8  218.76  4950.8  219.07  4970.8  218.52
  4980.8  214.13  4990.8  214.84  5000.5  213.26  5010.8  215.06  5020.8  215.26
  5040.8  214.64  5050.8   216.1  5058.5  218.53  5069.4  218.94  5120.8  219.71
  5126.7  219.38  5184.1  219.29  5206.5  220.83  5235.4  222.11  5250.6  223.35
  5265.7  223.55  5271.7  223.17  5278.1  224.51  5292.8  224.57  5327.8  226.62
#Mann= 4 ,-1 , 0
  4746.5      .1       0  4854.3     .16       0  4990.8     .07       0
  5010.8     .16       0
#XS Ineff= 2 ,-1
 4964.15 4989.83  214.84 5019.18 5060.27  215.26
Permanent Ineff=
       T       T
Bank Sta=4990.8,5010.8
XS Rating Curve= 0 ,0
Exp/Cntr=0.3,0.1

Chan Stop Cuts=-1
Use User Specified Reach Order=0
Composite Channel Slope=5