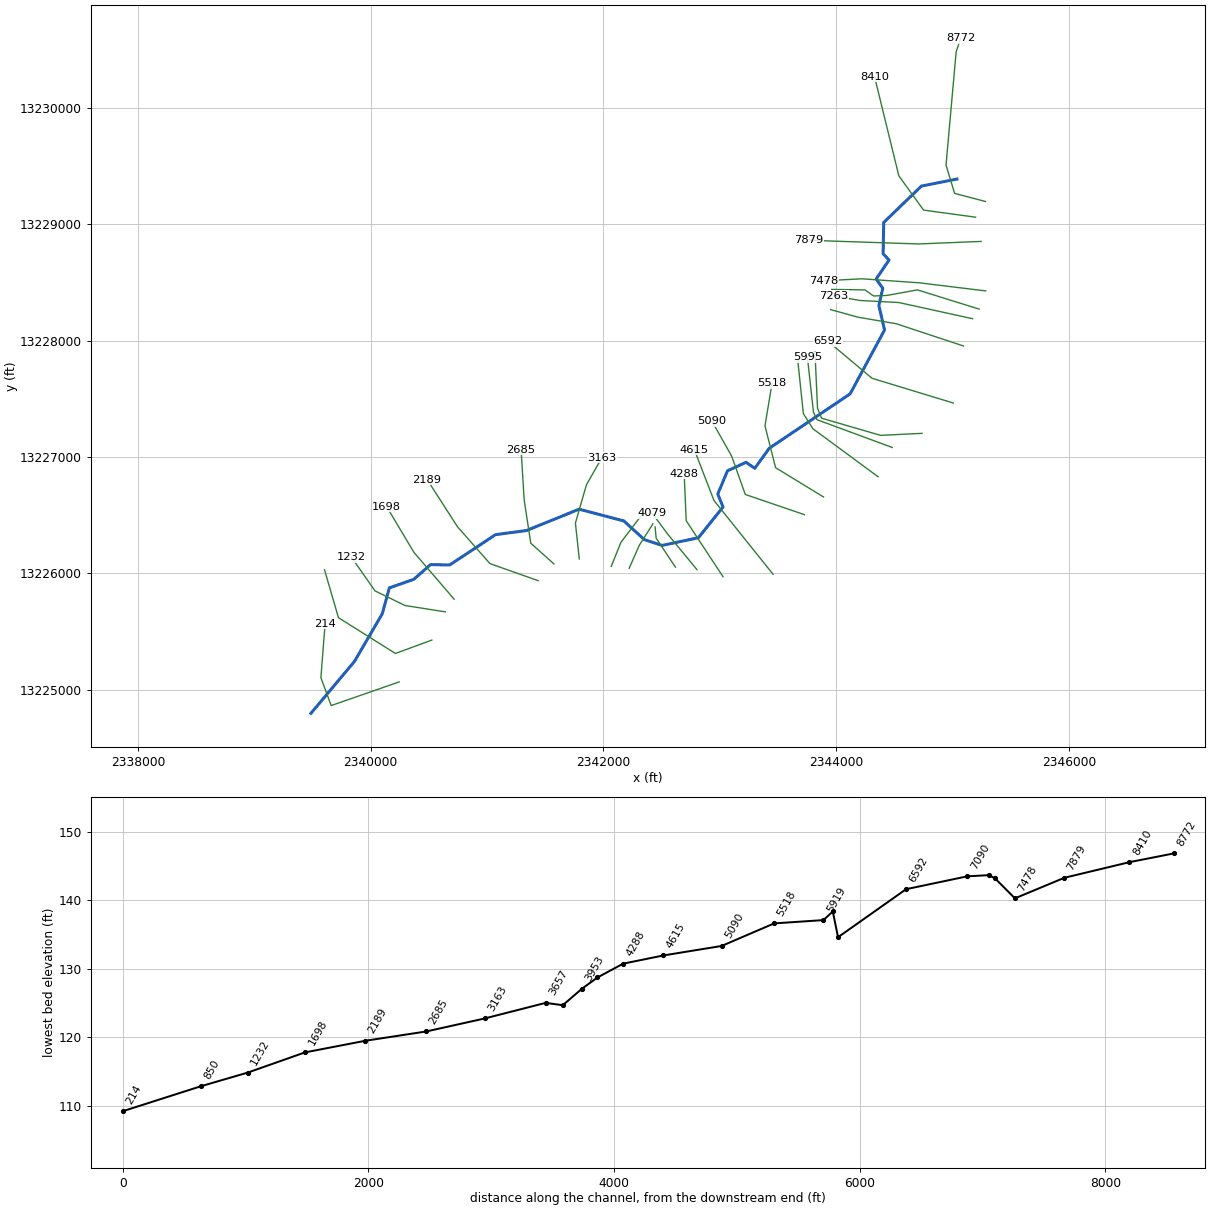
--- UNT306 IN PECR.prj (project) ---

Proj Title=UNT306 IN PECR Base Level Engineering
Current Plan=p01
Default Exp/Contr=0.3,0.1
English Units
Geom File=g01
Flow File=f01
Plan File=p01
Y Axis Title=Elevation
X Axis Title(PF)=Main Channel Distance
X Axis Title(XS)=Station
BEGIN DESCRIPTION:
UNT306 IN PECR
END DESCRIPTION:
DSS Export Rating Curves= 0
DSS Export Rating Curve Sorted= 0
DSS Export Volume Flow Curves= 0
DXF OffsetX= 0
DXF OffsetY= 0
DXF ScaleX= 1
DXF ScaleY= 10

--- UNT306 IN PECR.p01 (plan) ---

Plan Title=Multiple Run
Short Identifier=Multiple
Geom File=g01
Flow File=f01
Subcritical Flow
K Sum by GR= 0
Std Step Tol= 0.01
Critical Tol= 0.01
Num of Std Step Trials= 20
Max Error Tol= 0.3
Flow Tol Ratio= 0.001
Split Flow NTrial= 30
Split Flow Tol= 0.02
Split Flow Ratio= 0.02
Log Output Level= 0
Friction Slope Method= 1
Unsteady Friction Slope Method= 2
Unsteady Bridges Friction Slope Method= 1
Parabolic Critical Depth
Global Vel Dist=  1 , 1 , 1
Global Log Level= 0
CheckData=True
Encroach Param= -1, 0, 0, 0
BEGIN DESCRIPTION:
Multiple Run
END DESCRIPTION:

--- UNT306 IN PECR.f01 (steady flow) ---

Flow Title=Multiple
Program Version=4.10
Number of Profiles= 7
Profile Names=10-year,25-year,50-year,1pct_min,100-year,1pct_plu,500-year
River Rch & RM=UNT306 IN PECR,Reach-1         ,8772
     381     515     621     548     741    1002    1056
Boundary for River Rch & Prof#=UNT306 IN PECR,Reach-1         , 1
Up Type= 0
Dn Type= 3
Dn Slope=0.04
Boundary for River Rch & Prof#=UNT306 IN PECR,Reach-1         , 2
Up Type= 0
Dn Type= 3
Dn Slope=0.04
Boundary for River Rch & Prof#=UNT306 IN PECR,Reach-1         , 3
Up Type= 0
Dn Type= 3
Dn Slope=0.04
Boundary for River Rch & Prof#=UNT306 IN PECR,Reach-1         , 4
Up Type= 0
Dn Type= 3
Dn Slope=0.04
Boundary for River Rch & Prof#=UNT306 IN PECR,Reach-1         , 5
Up Type= 0
Dn Type= 3
Dn Slope=0.04
Boundary for River Rch & Prof#=UNT306 IN PECR,Reach-1         , 6
Up Type= 0
Dn Type= 3
Dn Slope=0.04
Boundary for River Rch & Prof#=UNT306 IN PECR,Reach-1         , 7
Up Type= 0
Dn Type= 3
Dn Slope=0.04
DSS Import GetInterval= 0
DSS Import GetPeak= 0
DSS Import FillOption= 0

--- UNT306 IN PECR.g01 (geometry) ---

Geom Title=Existing Conditions
Program Version=4.10

River Reach=UNT306 IN PECR  ,Reach-1
Reach XY= 30
      2345038.43     13229388.55      2344733.22     13229328.65
      2344408.74     13229015.63      2344403.53     13228746.36
      2344454.57     13228692.72      2344343.63      13228529.7
      2344400.93     13228450.01      2344367.07     13228302.09
      2344416.03     13228091.68       2344120.2     13227542.72
      2343424.36     13227074.49      2343300.93     13226902.61
      2343225.93      13226954.7      2343066.03     13226881.26
       2342982.7     13226681.26      2343028.01     13226570.32
      2342816.03     13226306.26      2342504.57     13226240.11
      2342351.45     13226290.11      2342175.41     13226450.53
      2341791.03     13226551.57      2341338.95     13226368.24
       2341072.8     13226332.82      2340678.53     13226071.88
      2340513.95     13226075.53      2340370.72     13225948.97
       2340160.3     13225875.53      2340099.36     13225652.61
      2339860.82     13225243.76      2339486.15     13224796.85

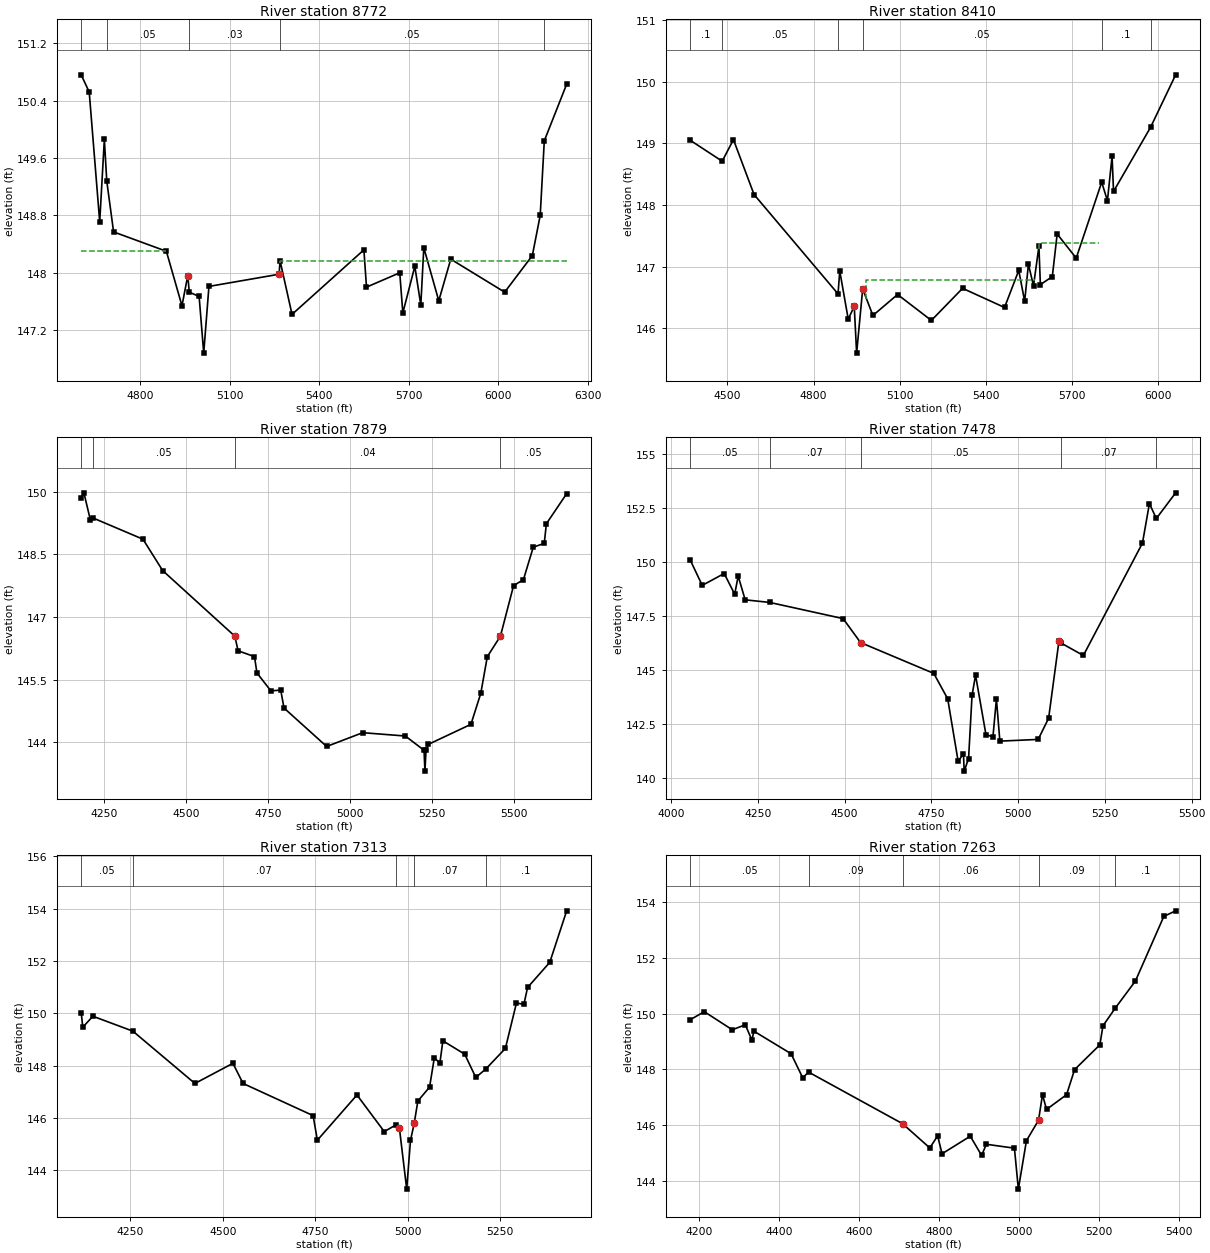
Type RM Length L Ch R = 1 ,8772    ,362,362,362
BEGIN DESCRIPTION:
UNT306 IN PECR 19.0
END DESCRIPTION:
XS GIS Cut Line= 5
      2345282.81     13229196.12      2345018.06     13229265.56
      2344944.27     13229508.61      2345031.08     13230480.84
      2345070.13     13230597.99
#Sta/Elev= 30
  4602.2  150.76  4629.1  150.52  4664.3  148.71  4679.8  149.86  4687.9  149.28
  4710.8  148.57  4887.7   148.3    4940  147.54  4959.4  147.96  4964.6  147.73
  4997.5  147.67  5012.9  146.88  5030.4  147.81 5265.63  147.98  5268.7  148.17
  5308.9  147.42  5549.8  148.32  5558.5   147.8    5670     148  5680.3  147.44
  5720.5  148.09  5740.6  147.55  5750.6  148.35  5800.8  147.61    5841  148.19
  6021.7  147.73  6114.4  148.24  6140.8   148.8  6154.5  149.84  6229.5  150.63
#Mann= 5 ,-1 , 0
  4602.2     .08       0  4687.9     .05       0  4964.6     .03       0
  5268.7     .05       0  6154.5     .08       0
#XS Ineff= 2 , 0
       0 4887.71   148.3 5268.25       0  148.17
Permanent Ineff=
       T       T
Bank Sta=4959.4,5265.63
XS Rating Curve= 0 ,0
Exp/Cntr=0.3,0.1

Type RM Length L Ch R = 1 ,8410    ,531,531,531
BEGIN DESCRIPTION:
Mapping XS fcb9ffd8
END DESCRIPTION:
XS GIS Cut Line= 4
      2345198.22     13229061.05      2344751.21     13229121.81
      2344538.54     13229416.95      2344330.21      13230267.6
#Sta/Elev= 30
    4370  149.05  4481.5  148.71  4520.7  149.06  4592.5  148.17  4884.9  146.56
    4891  146.93  4920.5  146.15  4941.4  146.36  4949.7   145.6  4970.8  146.64
  5006.4  146.21  5092.3  146.55    5210  146.13  5318.7  146.65  5464.8  146.34
  5514.3  146.94  5534.9  146.44    5548  147.04  5565.7  146.69  5584.5  147.33
  5589.6  146.71  5631.2  146.84  5648.1  147.53  5714.4  147.14  5803.2  148.37
  5823.1  148.07  5839.3  148.79  5844.4  148.22  5973.4  149.26  6060.7  150.11
#Mann= 6 ,-1 , 0
    4370      .1       0  4481.5     .05       0  4884.9     .03       0
  4970.8     .05       0  5803.2      .1       0  5973.4     .05       0
#XS Ineff= 2 ,-1
 4983.87 5571.25  146.79  5583.2 5792.21  147.39
Permanent Ineff=
       T       T
Bank Sta=4941.4,4970.8
XS Rating Curve= 0 ,0
Exp/Cntr=0.3,0.1

Type RM Length L Ch R = 1 ,7879    ,401,401,401
BEGIN DESCRIPTION:
UNT306 IN PECR 18.0
END DESCRIPTION:
XS GIS Cut Line= 4
      2345246.02     13228852.71      2344707.81     13228831.01
      2343922.22     13228857.05      2343765.93     13228865.73
#Sta/Elev= 30
  4179.8  149.85  4188.1  149.97  4208.1  149.31  4215.3  149.37  4368.3  148.86
  4428.3  148.11  4648.5  146.54  4658.5  146.19  4708.5  146.05    4716  145.66
  4758.6  145.23  4788.6  145.25  4798.6  144.82  4928.7   143.9  5038.7  144.23
  5168.8  144.15  5225.8  143.81  5228.6  143.31  5231.8  143.81  5238.8  143.95
  5368.9  144.43  5398.9  145.17  5418.9  146.05  5458.9  146.54    5499  147.75
    5529  147.89  5559.1  148.67  5592.6  148.76  5599.1  149.23    5661  149.95
#Mann= 4 ,-1 , 0
  4179.8     .08       0  4215.3     .05       0  4648.5     .04       0
  5458.9     .05       0
Bank Sta=4648.5,5458.9
XS Rating Curve= 0 ,0
Exp/Cntr=0.3,0.1

Type RM Length L Ch R = 1 ,7478    ,165,165,165
BEGIN DESCRIPTION:
Mapping XS 4c268d48
END DESCRIPTION:
XS GIS Cut Line= 4
      2345285.04     13228427.37      2344716.49     13228496.81
       2344221.7     13228531.53      2343892.23     13228514.19
#Sta/Elev= 30
  4055.2   150.1    4090  148.92  4153.2  149.47  4183.5  148.51  4193.5  149.35
  4213.7  148.25  4284.2  148.13  4495.8  147.38  4546.1  146.27  4757.1  144.84
  4797.2  143.66  4827.2  140.77  4842.6  141.11  4844.6  140.31  4857.3  140.89
  4867.3  143.82  4877.4  144.76  4907.4     142  4927.5   141.9  4937.5  143.65
  4947.5   141.7  5057.8  141.78  5087.9  142.76  5117.9  146.36  5123.5  146.25
    5188  145.67  5358.3  150.88  5378.3  152.71  5398.3  152.02  5453.9  153.21
#Mann= 5 ,-1 , 0
  4055.2     .05       0  4284.2     .07       0  4546.1     .05       0
  5123.5     .07       0  5398.3      .1       0
#XS Ineff= 1 ,-1
 4739.61 4876.94  144.69
Permanent Ineff=
       T
Bank Sta=4546.1,5117.9
XS Rating Curve= 0 ,0
Exp/Cntr=0.3,0.1

Type RM Length L Ch R = 1 ,7313    ,50,50,50
BEGIN DESCRIPTION:
Mapping XS c28015af
END DESCRIPTION:
XS GIS Cut Line= 6
      2345228.62     13228271.12      2344699.13     13228436.04
      2344434.37      13228388.3      2344321.52     13228383.96
      2344247.74     13228436.04      2343962.03     13228440.37
#Sta/Elev= 30
  4117.1  150.03  4121.4  149.47  4148.7  149.89  4256.8  149.32  4424.6  147.32
  4527.4  148.09  4554.7  147.32  4744.2  146.09  4755.6  145.15  4862.7  146.88
  4936.5  145.48  4967.4  145.73  4977.4  145.62  4997.2  143.28  5007.4  145.14
  5017.4  145.79  5027.4  146.65    5059  147.18    5072  148.31  5086.8  148.09
    5095  148.95    5154  148.44    5184  147.55  5210.9  147.87    5264  148.66
    5294   150.4    5314  150.34    5324  150.99    5384  151.95  5429.7  153.92
#Mann= 5 ,-1 , 0
  4117.1     .05       0  4256.8     .07       0  4967.4     .05       0
  5017.4     .07       0  5210.9      .1       0
#XS Ineff= 2 ,-1
  4117.1 4519.54  148.03 4660.66 4863.93  146.52
Permanent Ineff=
       T       T
Bank Sta=4977.4,5017.4
XS Rating Curve= 0 ,0
Exp/Cntr=0.3,0.1

Type RM Length L Ch R = 1 ,7263    ,173,173,173
BEGIN DESCRIPTION:
UNT306 IN PECR 17.0
END DESCRIPTION:
XS GIS Cut Line= 4
      2345172.25     13228188.64      2344538.54     13228327.54
      2344208.68      13228344.9      2343978.64     13228383.96
#Sta/Elev= 30
  4178.5  149.78  4213.8  150.07  4283.7  149.42  4316.2   149.6  4332.6  149.05
  4337.7  149.37  4430.5  148.56  4459.5   147.7  4474.3   147.9  4708.8  146.05
  4776.9  145.18  4796.5  145.61  4807.6  144.97  4878.1   145.6  4906.3  144.91
  4918.2  145.31  4988.3  145.17  4998.1   143.7  5018.3  145.44  5048.4  146.17
  5058.4  147.09  5068.4  146.56  5118.5  147.09  5138.5  147.99  5201.7  148.88
  5209.3  149.56  5239.7  150.19  5290.4  151.17  5361.4  153.49  5390.9  153.69
#Mann= 5 ,-1 , 0
  4178.5     .05       0  4474.3     .09       0  4708.8     .06       0
  5048.4     .09       0  5239.7      .1       0
Bank Sta=4708.8,5048.4
XS Rating Curve= 0 ,0
Exp/Cntr=0.3,0.1

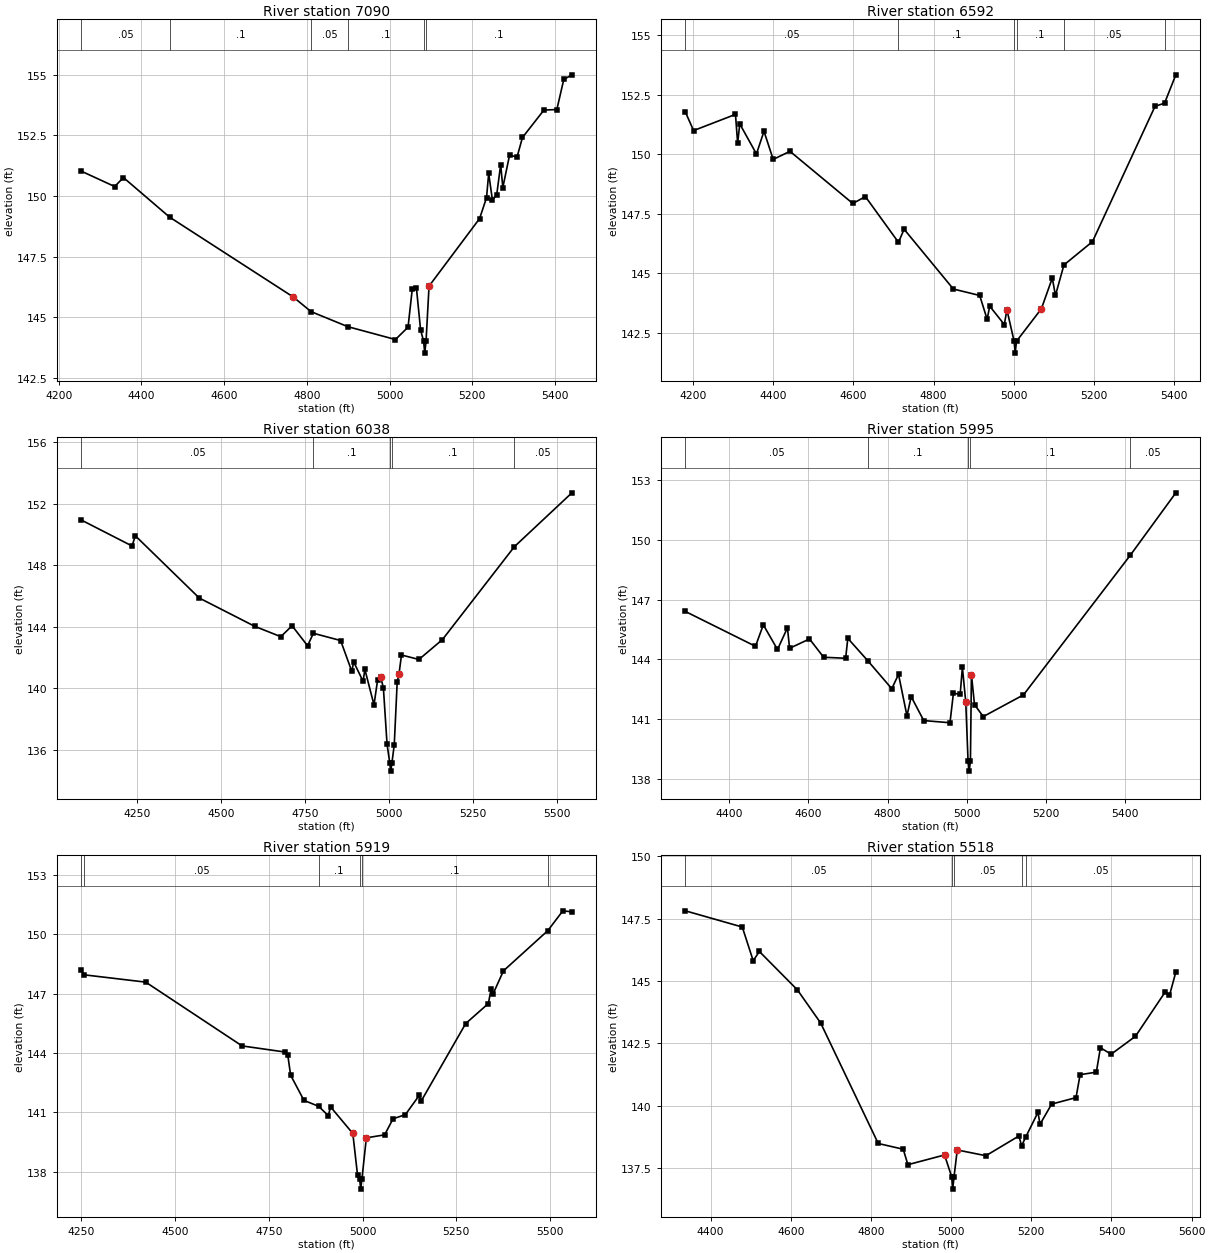
Type RM Length L Ch R = 1 ,7090    ,498,498,498
BEGIN DESCRIPTION:
UNT306 IN PECR 16.0
END DESCRIPTION:
XS GIS Cut Line= 4
      2345094.09     13227954.27      2344516.84     13228145.24
      2344186.97     13228201.67      2343952.62     13228266.77
#Sta/Elev= 30
  4254.8  151.02  4335.2  150.39  4356.3  150.76    4468  149.13  4767.1  145.84
  4809.9  145.24  4898.8  144.62  5014.1  144.09  5044.5   144.6  5054.7  146.16
  5064.8  146.21  5074.9  144.48  5082.1  144.03  5084.9  143.53  5088.1  144.03
  5095.3  146.29  5217.5  149.07  5234.3  149.93  5239.5  150.93  5248.6  149.83
    5259  150.06  5268.5  151.29  5273.7  150.35  5290.1  151.69    5308   151.6
  5321.2  152.41  5373.1  153.54  5404.3  153.56  5421.1   154.8  5440.7  154.99
#Mann= 6 ,-1 , 0
  4254.8     .05       0    4468      .1       0  4809.9     .05       0
  4898.8      .1       0  5082.1     .07       0  5088.1      .1       0
Bank Sta=4767.1,5095.3
XS Rating Curve= 0 ,0
Exp/Cntr=0.3,0.1

Type RM Length L Ch R = 1 ,6592    ,554,554,554
BEGIN DESCRIPTION:
UNT306 IN PECR 15.0
END DESCRIPTION:
XS GIS Cut Line= 3
      2345007.29     13227463.82       2344308.5     13227676.49
      2343930.87     13227993.36
#Sta/Elev= 30
  4180.9  151.77  4201.4  150.99  4305.9  151.67  4311.3  150.46  4316.6  151.27
  4358.2  150.01    4377  150.96    4400  149.78  4441.8  150.12  4598.6  147.93
  4629.9  148.22  4712.5   146.3  4726.5  146.85  4849.4  144.34  4915.1  144.07
  4933.6  143.07  4940.1  143.62  4976.5  142.85    4983  143.47  5000.9  142.15
  5003.6  141.65  5006.9  142.15  5068.9  143.51  5096.2   144.8    5104  144.07
  5125.2  145.35  5196.4  146.33  5352.5  152.01  5376.2  152.14  5404.3  153.33
#Mann= 6 ,-1 , 0
  4180.9     .05       0  4712.5      .1       0  5000.9     .07       0
  5006.9      .1       0  5125.2     .05       0  5376.2      .1       0
Bank Sta=4983,5068.9
XS Rating Curve= 0 ,0
Exp/Cntr=0.3,0.1

Type RM Length L Ch R = 1 ,6038    ,43,43,43
BEGIN DESCRIPTION:
UNT306 IN PECR 14.0
END DESCRIPTION:
XS GIS Cut Line= 5
      2344738.16      13227203.4      2344382.29     13227186.04
      2343874.47     13227333.61      2343839.75     13227420.42
      2343818.06     13227902.02
#Sta/Elev= 30
  4084.7  150.93  4235.3  149.25  4245.3  149.91  4435.6  145.87    4601  144.03
  4678.5  143.36    4712  144.07  4758.2  142.77  4775.5  143.58  4856.6  143.11
  4890.1   141.1  4895.3  141.73  4923.6  140.46  4928.8  141.24    4956  138.93
  4966.7  140.54  4976.6  140.71  4984.1     140  4994.9  136.38  5003.2  135.13
    5006  134.63  5009.2  135.13  5016.4  136.35  5025.1  140.42  5030.5  140.94
  5037.9  142.17  5089.8  141.88  5159.8  143.17    5374   149.2  5545.4   152.7
#Mann= 5 ,-1 , 0
  4084.7     .05       0  4775.5      .1       0  5003.2     .07       0
  5009.2      .1       0    5374     .05       0
Bank Sta=4976.6,5030.5
XS Rating Curve= 0 ,0
Exp/Cntr=0.3,0.1

Type RM Length L Ch R = 1 ,5995    ,76,76,76
BEGIN DESCRIPTION:
Mapping XS d8178f92
END DESCRIPTION:
XS GIS Cut Line= 4
      2344482.13     13227081.87      2343835.41     13227320.59
      2343805.03      13227385.7      2343752.94     13227858.82
#Sta/Elev= 30
  4289.9  146.41  4466.8  144.66  4486.5  145.74  4522.3   144.5  4547.4  145.59
  4552.8  144.56    4603  145.03  4638.7  144.11  4694.2  144.06  4699.7  145.06
  4750.7  143.92  4810.6  142.53  4827.6  143.25  4848.9  141.17  4859.6  142.13
  4891.2  140.93  4957.4  140.82  4966.1  142.31  4983.1  142.24  4988.7  143.61
  4997.2  141.86    5003  138.89  5005.8  138.39    5009  138.89  5011.5  143.24
  5019.3  141.73  5041.4  141.13  5142.8  142.22  5412.1  149.23  5527.1  152.37
#Mann= 5 ,-1 , 0
  4289.9     .05       0  4750.7      .1       0    5003     .07       0
    5009      .1       0  5412.1     .05       0
Bank Sta=4997.2,5011.5
XS Rating Curve= 0 ,0
Exp/Cntr=0.3,0.1

Type RM Length L Ch R = 1 ,5919    ,401,401,401
BEGIN DESCRIPTION:
UNT306 IN PECR 13.0
END DESCRIPTION:
XS GIS Cut Line= 4
      2344360.61     13226830.12      2343800.69     13227242.47
      2343718.22     13227372.67      2343670.48     13227828.39
#Sta/Elev= 30
  4250.4  148.17  4257.3  147.95  4421.8  147.58  4678.7  144.36  4793.6  144.05
  4800.4  143.92  4808.2  142.88  4843.7  141.61    4883  141.31  4908.5  140.84
  4914.7  141.28    4974  139.94  4986.5  137.85  4992.2  137.63    4995  137.13
  4998.2  137.63  5010.1  139.72  5058.8  139.87  5081.2  140.68  5114.1  140.89
    5151  141.86  5156.1  141.57    5275  145.49  5335.4   146.5  5342.5  147.21
  5347.6  146.97  5375.6  148.15  5493.9  150.18    5534  151.18  5558.1  151.13
#Mann= 6 ,-1 , 0
  4250.4      .1       0  4257.3     .05       0    4883      .1       0
  4992.2     .07       0  4998.2      .1       0  5493.9     .05       0
Bank Sta=4974,5010.1
XS Rating Curve= 0 ,0
Exp/Cntr=0.3,0.1

Type RM Length L Ch R = 1 ,5518    ,428,428,428
BEGIN DESCRIPTION:
Mapping XS eb6ce5ae
END DESCRIPTION:
XS GIS Cut Line= 4
       2343891.8     13226656.55      2343479.51     13226908.26
      2343388.36     13227268.51      2343449.02     13227632.44
#Sta/Elev= 30
  4336.9  147.81  4478.9  147.16  4506.1  145.81  4521.5  146.18  4616.4  144.64
  4674.5  143.31  4818.1  138.48  4880.4  138.25  4892.1  137.63  4983.5  138.02
  5001.2  137.15  5003.9  136.65  5007.2  137.15  5015.2  138.22  5086.7  137.99
  5168.9  138.78  5175.9  138.39  5186.4  138.75  5216.6  139.73  5221.7  139.25
  5250.7  140.06  5311.5  140.32  5321.7  141.24  5362.2  141.34  5372.4  142.32
  5399.1  142.06  5459.9  142.78  5534.6  144.57  5544.7  144.42  5560.5  145.35
#Mann= 5 ,-1 , 0
  4336.9     .05       0  5001.2     .03       0  5007.2     .05       0
  5175.9     .08       0  5186.4     .05       0
Bank Sta=4983.5,5015.2
XS Rating Curve= 0 ,0
Exp/Cntr=0.3,0.1

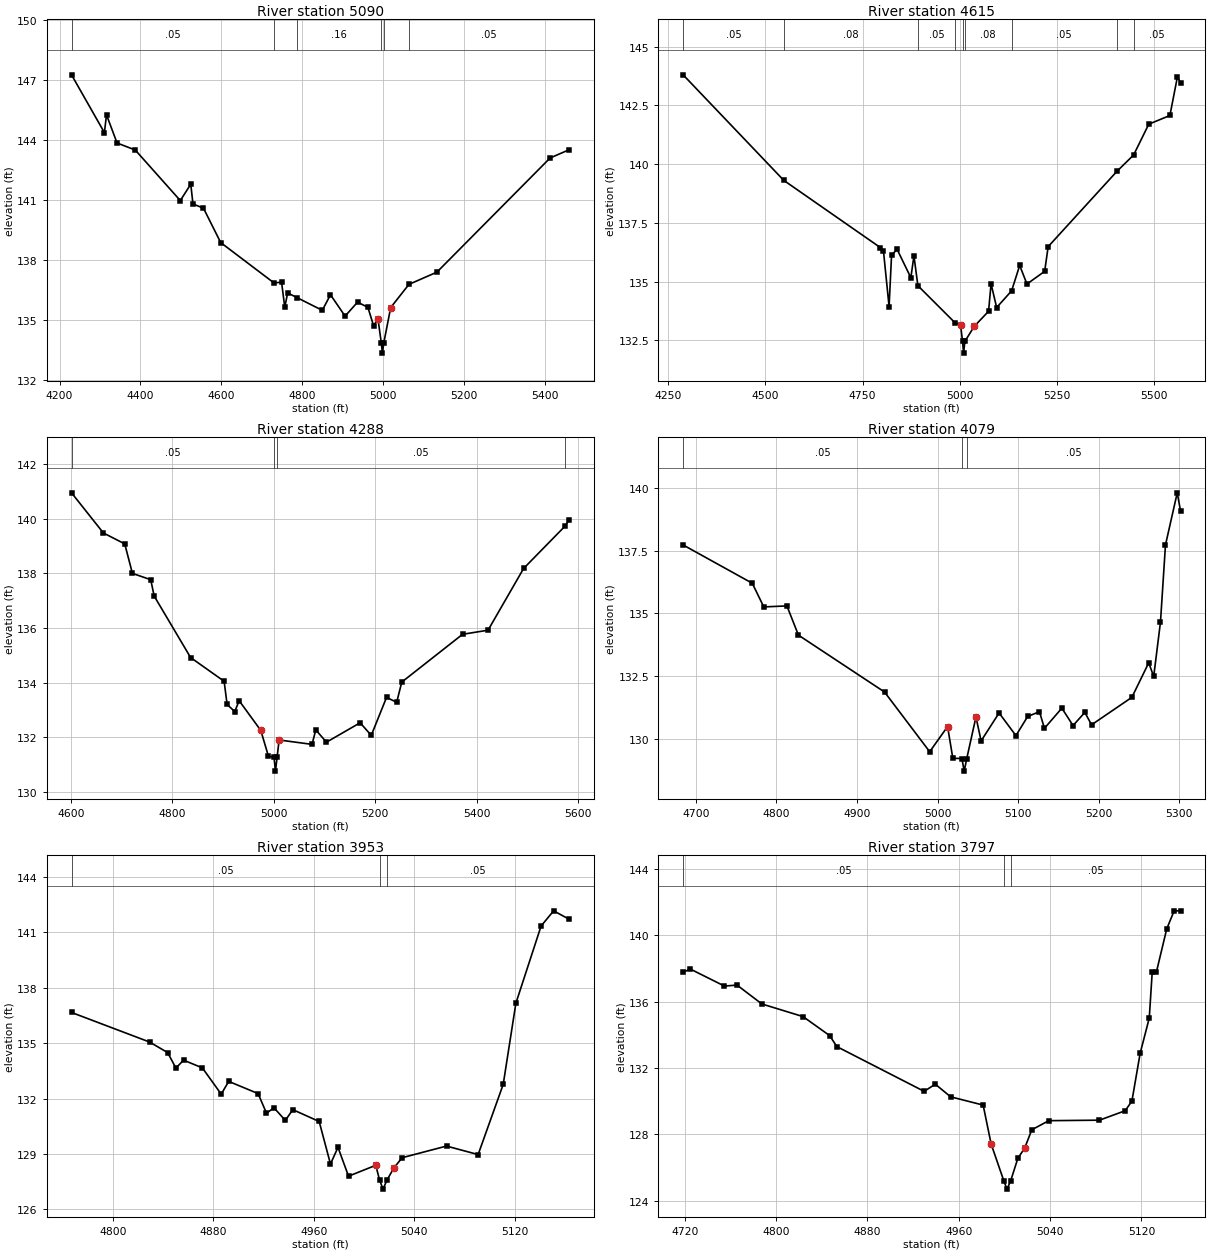
Type RM Length L Ch R = 1 ,5090    ,475,475,475
BEGIN DESCRIPTION:
UNT306 IN PECR 12.0
END DESCRIPTION:
XS GIS Cut Line= 4
      2343726.87     13226504.63      2343219.09     13226678.23
      2343101.91     13227008.09      2342932.68     13227307.49
#Sta/Elev= 30
  4229.7  147.27    4311  144.38  4316.2  145.27  4342.3  143.86  4387.3  143.51
  4498.8  140.98  4524.7   141.8  4530.1  140.81  4556.1   140.6  4598.7  138.88
  4730.7  136.86  4749.3   136.9  4757.2  135.65  4764.4  136.36  4787.2  136.13
  4850.1  135.49  4870.3  136.27  4906.5   135.2  4937.3   135.9  4962.9  135.64
  4977.1  134.71  4987.7  135.08  4996.1  133.85  4998.8  133.35  5002.1  133.85
  5019.3  135.63  5064.5  136.79  5133.6   137.4  5413.6  143.11  5460.3  143.52
#Mann= 6 ,-1 , 0
  4229.7     .05       0  4730.7     .08       0  4787.2     .16       0
  4996.1     .07       0  5002.1     .16       0  5064.5     .05       0
Bank Sta=4987.7,5019.3
XS Rating Curve= 0 ,0
Exp/Cntr=0.3,0.1

Type RM Length L Ch R = 1 ,4615    ,327,327,327
BEGIN DESCRIPTION:
UNT306 IN PECR 11.0
END DESCRIPTION:
XS GIS Cut Line= 3
      2343457.79     13225992.49        2342950.     13226626.15
      2342781.24     13227063.17
#Sta/Elev= 30
    4288   143.8  4547.1  139.31  4795.8  136.45  4803.8  136.29  4818.2  133.94
  4824.6  136.14    4839  136.37  4874.2  135.17  4882.2   136.1  4892.3  134.83
  4987.4  133.26  5002.3  133.15  5007.3  132.46    5010  131.96  5013.3  132.46
  5037.5   133.1  5074.3  133.74  5080.7  134.91  5095.1   133.9  5133.6  134.61
  5154.4  135.69  5173.1   134.9  5218.7  135.44  5227.7  136.49  5404.5  139.69
  5447.7  140.39  5486.7   141.7  5541.1  142.07  5560.4  143.71  5568.5  143.47
#Mann= 9 ,-1 , 0
    4288     .05       0  4547.1     .08       0  4892.3     .05       0
  4987.4     .08       0  5007.3     .07       0  5013.3     .08       0
  5133.6     .05       0  5404.5     .16       0  5447.7     .05       0
Bank Sta=5002.3,5037.5
XS Rating Curve= 0 ,0
Exp/Cntr=0.3,0.1

Type RM Length L Ch R = 1 ,4288    ,209,209,209
BEGIN DESCRIPTION:
UNT306 IN PECR 10.0
END DESCRIPTION:
XS GIS Cut Line= 3
      2343028.11     13225970.78      2342711.28     13226452.54
      2342693.92     13226856.16
#Sta/Elev= 30
  4601.3  140.95  4664.1  139.48  4706.2  139.08  4721.3     138  4757.4  137.77
  4764.2  137.17    4836  134.92  4902.1  134.05    4908   133.2  4923.1  132.94
  4931.7  133.34  4974.4  132.25  4989.4  131.31  5000.5  131.26  5003.3  130.76
  5006.5  131.26  5010.5   131.9  5075.4  131.74  5082.8  132.27  5103.9  131.82
  5170.2  132.53  5192.2  132.07  5222.3  133.46  5242.3  133.28  5252.3  134.02
  5372.2  135.77  5422.4  135.92  5492.5  138.18  5573.6  139.72  5581.9  139.95
#Mann= 4 ,-1 , 0
  4601.3     .05       0  5000.5    .035       0  5006.5     .05       0
  5573.6     .08       0
Bank Sta=4974.4,5010.5
XS Rating Curve= 0 ,0
Exp/Cntr=0.3,0.1

Type RM Length L Ch R = 1 ,4079    ,126,126,126
BEGIN DESCRIPTION:
Mapping XS c7cc406e
END DESCRIPTION:
XS GIS Cut Line= 3
      2342804.05      13226031.8      2342550.55     13226339.78
      2342420.27     13226515.07
#Sta/Elev= 30
  4684.3  137.72  4770.1   136.2  4784.4  135.26  4813.1   135.3  4827.4  134.14
  4934.3  131.88  4990.3  129.51  5012.5  130.51    5019  129.25  5030.3  129.24
  5033.1  128.74  5036.3  129.24  5047.7  130.89  5054.1  129.94  5076.4  131.05
  5097.3  130.15  5111.9  130.91  5126.5   131.1  5132.7  130.44  5154.3  131.24
  5168.2  130.55  5182.8  131.07  5191.2  130.58  5241.2  131.67  5262.1  133.04
  5268.3   132.5  5276.7  134.66  5282.9  137.72  5297.5  139.79  5301.6  139.07
#Mann= 3 ,-1 , 0
  4684.3     .05       0  5030.3    .035       0  5036.3     .05       0
Bank Sta=5012.5,5047.7
XS Rating Curve= 0 ,0
Exp/Cntr=0.3,0.1

Type RM Length L Ch R = 1 ,3953    ,156,156,156
BEGIN DESCRIPTION:
Mapping XS eea9309a
END DESCRIPTION:
XS GIS Cut Line= 3
      2342619.26     13226053.13      2342453.43     13226301.88
      2342443.96     13226398.96
#Sta/Elev= 30
  4766.9  136.66  4829.1  135.06  4843.5  134.49  4850.1  133.65  4856.2  134.08
  4871.2  133.66  4886.2  132.24  4892.2  132.93  4915.6  132.27  4922.3  131.21
  4928.3   131.5  4937.3  130.82  4943.3   131.4  4964.3  130.76  4973.3  128.46
  4979.3  129.36  4987.7   127.8  5009.4  128.39  5012.4   127.6  5015.2   127.1
  5018.4   127.6  5023.8  128.24  5030.4   128.8  5065.8  129.43    5091  128.97
    5111  132.77  5121.1  137.16  5141.2  141.34  5151.2  142.16  5163.4  141.71
#Mann= 3 ,-1 , 0
  4766.9     .05       0  5012.4    .035       0  5018.4     .05       0
Bank Sta=5009.4,5023.8
XS Rating Curve= 0 ,0
Exp/Cntr=0.3,0.1

Type RM Length L Ch R = 1 ,3797    ,140,140,140
BEGIN DESCRIPTION:
UNT306 IN PECR 9.0
END DESCRIPTION:
XS GIS Cut Line= 4
      2342221.29     13226043.69      2342308.92     13226242.65
      2342413.16     13226406.11      2342425.02     13226427.46
#Sta/Elev= 30
  4718.6  137.77  4724.8  137.97  4754.8  136.94  4765.8     137  4787.6  135.86
  4823.6   135.1    4847  133.95  4853.2  133.29  4929.7  130.59  4939.5  131.02
  4952.9  130.26  4981.4  129.76  4988.4  127.41  4999.5  125.19  5002.3  124.69
  5005.5  125.19  5011.8  126.55  5017.8  127.17    5024  128.27  5038.9  128.82
  5083.3  128.85  5105.8  129.42  5111.7     130  5118.9  132.88  5126.9  135.01
  5129.5   137.8  5133.2   137.8  5142.2  140.39  5148.7  141.48  5154.3  141.48
#Mann= 3 ,-1 , 0
  4718.6     .05       0  4999.5    .035       0  5005.5     .05       0
Bank Sta=4988.4,5017.8
XS Rating Curve= 0 ,0
Exp/Cntr=0.3,0.1

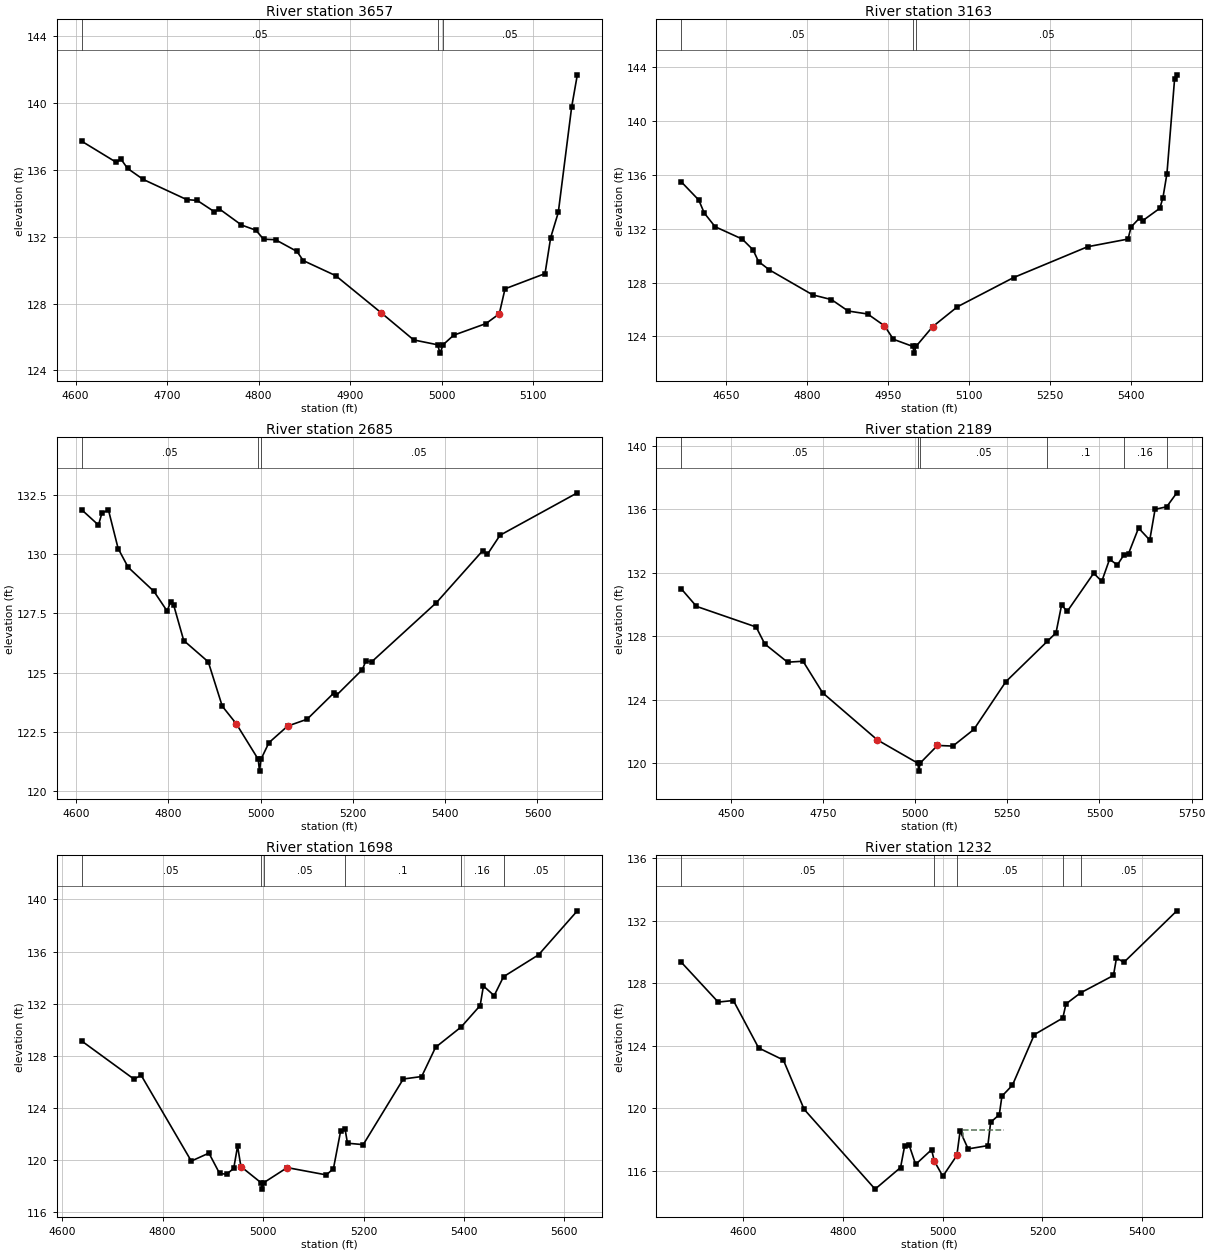
Type RM Length L Ch R = 1 ,3657    ,494,494,494
BEGIN DESCRIPTION:
UNT306 IN PECR 8.0
END DESCRIPTION:
XS GIS Cut Line= 3
      2342067.29     13226060.25      2342150.21     13226266.34
      2342343.44     13226520.85
#Sta/Elev= 30
  4606.5  137.72  4644.2  136.46  4649.6  136.64  4656.7  136.09  4673.8  135.43
  4721.4  134.22  4732.9  134.17  4751.7  133.49  4757.1  133.66  4781.2   132.7
  4796.9  132.39  4805.4  131.85  4818.4  131.82  4841.8  131.12  4848.7  130.57
  4884.1  129.67    4934  127.44  4969.4  125.82  4995.5  125.53  4998.2  125.03
  5001.5  125.53    5013   126.1  5048.4   126.8  5062.9  127.38  5069.2  128.88
  5112.9  129.79  5119.1  131.95  5127.4  133.45    5142  139.76  5148.2  141.69
#Mann= 3 ,-1 , 0
  4606.5     .05       0  4995.5     .04       0  5001.5     .05       0
Bank Sta=4934,5062.9
XS Rating Curve= 0 ,0
Exp/Cntr=0.3,0.1

Type RM Length L Ch R = 1 ,3163    ,478,478,478
BEGIN DESCRIPTION:
UNT306 IN PECR 7.0
END DESCRIPTION:
XS GIS Cut Line= 4
       2341792.5     13226124.21      2341759.33     13226432.17
      2341854.09     13226761.45      2341986.27     13226992.77
#Sta/Elev= 30
  4566.2  135.51    4599  134.14  4609.1  133.18  4629.2  132.16  4679.5  131.24
  4699.6  130.44  4709.7  129.57  4729.8  128.95  4810.2  127.09  4844.9  126.74
  4875.8  125.89    4912  125.67  4943.2  124.79  4959.7  123.79  4995.6  123.26
  4998.3  122.76  5001.6  123.26  5032.3  124.72  5078.5  126.21  5182.6  128.38
  5319.7  130.67  5394.5  131.24  5400.3  132.14  5416.1  132.81  5421.9  132.61
  5453.5  133.53  5459.3  134.32  5466.7  136.11  5480.9  143.16    5485  143.45
#Mann= 3 ,-1 , 0
  4566.2     .05       0  4995.6    .035       0  5001.6     .05       0
Bank Sta=4943.2,5032.3
XS Rating Curve= 0 ,0
Exp/Cntr=0.3,0.1

Type RM Length L Ch R = 1 ,2685    ,496,496,496
BEGIN DESCRIPTION:
UNT306 IN PECR 6.0
END DESCRIPTION:
XS GIS Cut Line= 4
      2341574.55     13226081.58      2341375.57     13226259.24
      2341318.71     13226633.53       2341292.7      13227061.5
#Sta/Elev= 30
  4612.2  131.88  4648.8  131.23  4656.3  131.74  4670.5  131.86  4691.4  130.24
  4713.1  129.45  4769.1  128.43  4797.6   127.6  4805.1     128  4811.8  127.85
  4833.5  126.36  4886.7  125.46    4917  123.59  4947.3  122.85  4994.9  121.35
  4997.7  120.85  5000.9  121.35  5018.1  122.05  5058.6  122.75  5100.9  123.04
  5159.5  124.16  5164.5  124.05  5220.4  125.13  5228.2   125.5  5240.7  125.46
  5381.1  127.96  5481.3  130.15  5491.3  129.99  5518.8   130.8  5686.3  132.59
#Mann= 3 ,-1 , 0
  4612.2     .05       0  4994.9    .035       0  5000.9     .05       0
Bank Sta=4947.3,5058.6
XS Rating Curve= 0 ,0
Exp/Cntr=0.3,0.1

Type RM Length L Ch R = 1 ,2189    ,491,491,491
BEGIN DESCRIPTION:
UNT306 IN PECR 5.0
END DESCRIPTION:
XS GIS Cut Line= 4
      2341439.56     13225937.05      2341024.97     13226083.94
      2340745.43     13226401.37      2340484.84     13226806.47
#Sta/Elev= 30
  4365.3     131    4407  129.88  4568.8  128.58  4592.3  127.51  4654.1  126.36
  4696.1  126.42  4749.2  124.43  4897.5  121.46  5007.4  119.99  5010.2  119.49
  5013.4  119.99  5060.7  121.11  5102.4  121.07  5159.4  122.12  5246.1  125.13
  5358.7  127.68  5382.1  128.21  5397.3  129.97  5412.5  129.56  5484.3  131.97
  5506.3  131.46  5527.4  132.85  5548.5  132.49  5566.7  133.14  5578.9  133.21
    5606  134.82  5636.4  134.06  5650.8     136  5682.3  136.16  5709.8  137.04
#Mann= 6 ,-1 , 0
  4365.3     .05       0  5007.4    .035       0  5013.4     .05       0
  5358.7      .1       0  5566.7     .16       0  5682.3     .05       0
Bank Sta=4897.5,5060.7
XS Rating Curve= 0 ,0
Exp/Cntr=0.3,0.1

Type RM Length L Ch R = 1 ,1698    ,466,466,466
BEGIN DESCRIPTION:
UNT306 IN PECR 4.0
END DESCRIPTION:
XS GIS Cut Line= 3
      2340717.01     13225778.34      2340371.14     13226181.06
      2340137.35     13226573.08
#Sta/Elev= 30
  4638.5  129.15  4742.9  126.22  4757.1  126.52    4857  119.94  4892.1  120.55
  4913.4  118.99  4927.2  118.93  4941.5  119.38  4949.2  121.09  4955.8  119.52
  4995.6  118.29  4998.3  117.79  5001.6  118.29    5048  119.44  5125.9  118.88
  5140.1  119.36  5154.4  122.24    5163  122.43  5168.1  121.31  5199.4   121.2
  5279.2  126.23  5315.8  126.42  5343.5  128.66  5394.5  130.22  5432.3  131.86
  5438.8  133.36  5460.2  132.62  5478.8  134.07  5548.7  135.75  5625.8  139.12
#Mann= 6 ,-1 , 0
  4638.5     .05       0  4995.6    .035       0  5001.6     .05       0
    5163      .1       0  5394.5     .16       0  5478.8     .05       0
Bank Sta=4955.8,5048
XS Rating Curve= 0 ,0
Exp/Cntr=0.3,0.1

Type RM Length L Ch R = 1 ,1232    ,382,382,382
BEGIN DESCRIPTION:
UNT306 IN PECR 3.0
END DESCRIPTION:
XS GIS Cut Line= 4
      2340641.15     13225669.38      2340295.34     13225723.86
      2340037.13     13225849.41      2339833.42     13226140.76
#Sta/Elev= 30
  4476.3  129.35  4550.6  126.79    4581  126.89  4631.6  123.86  4681.1  123.09
  4722.7  119.94  4864.8  114.84  4915.8  116.22  4923.8  117.57  4932.8  117.67
    4946  116.42  4977.9  117.36  4983.4  116.63  5000.4  115.66  5028.5  116.99
    5035  118.55  5051.1  117.41  5090.6  117.62  5096.2  119.11  5113.5   119.6
  5118.8  120.78  5139.8  121.48  5183.6  124.71  5240.7  125.77    5247  126.67
  5276.3  127.38  5342.1  128.49  5348.2  129.61    5363  129.33    5469  132.62
#Mann= 5 ,-1 , 0
  4476.3     .05       0  4983.4    .035       0  5028.5     .05       0
  5240.7     .16       0  5276.3     .05       0
#XS Ineff= 3 ,-1
 4791.57 4927.62  117.29 4934.59 4977.33  117.12 5040.99 5122.97  118.62
Permanent Ineff=
       T       T       T
Bank Sta=4983.4,5028.5
XS Rating Curve= 0 ,0
Exp/Cntr=0.3,0.1

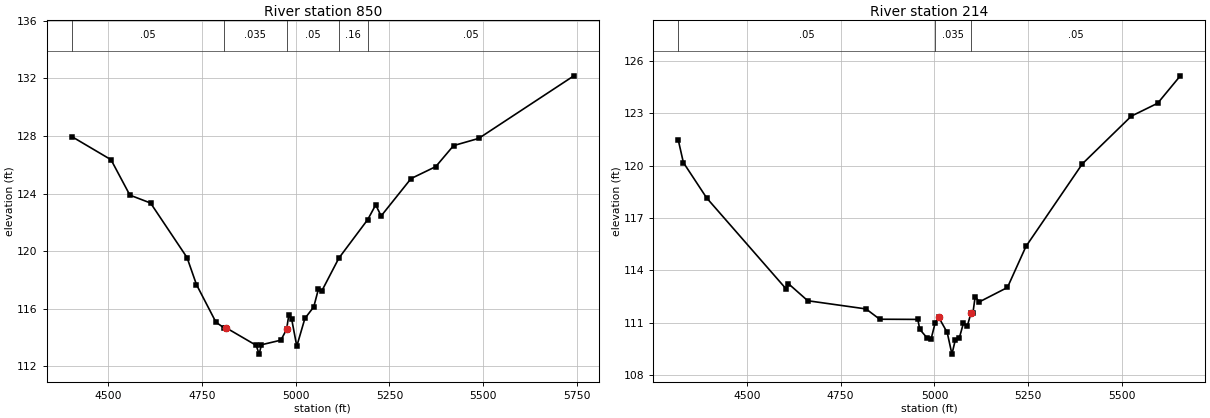
Type RM Length L Ch R = 1 ,850     ,636,636,636
BEGIN DESCRIPTION:
UNT306 IN PECR 2.0
END DESCRIPTION:
XS GIS Cut Line= 4
      2340525.06     13225426.39      2340212.55     13225311.81
      2339722.97      13225619.1      2339603.18     13226030.53
#Sta/Elev= 30
  4402.6  127.96  4507.3  126.35  4557.6  123.89  4612.8  123.34  4710.1  119.55
  4735.3  117.67  4787.2  115.06  4808.4  114.67  4814.3  114.67  4894.6  113.45
  4902.4  112.84  4908.6  113.49  4960.4  113.81  4975.7  114.56  4981.6  115.56
  4989.1  115.29  5002.9  113.39  5024.5  115.32  5048.1  116.12  5060.6  117.36
    5070  117.25  5115.1  119.51  5192.1  122.19  5213.4  123.21  5227.9  122.44
  5307.7  125.04  5373.6  125.87  5421.1  127.33  5488.1  127.83    5742  132.18
#Mann= 5 ,-1 , 0
  4402.6     .05       0  4808.4    .035       0  4975.7     .05       0
  5115.1     .16       0  5192.1     .05       0
Bank Sta=4814.3,4975.7
XS Rating Curve= 0 ,0
Exp/Cntr=0.3,0.1

Type RM Length L Ch R = 1 ,214     ,0,0,0
BEGIN DESCRIPTION:
UNT306 IN PECR 1.0
END DESCRIPTION:
XS GIS Cut Line= 4
      2340243.76       13225067.      2339660.47     13224863.89
      2339571.92     13225103.47      2339608.38     13225566.97
#Sta/Elev= 30
  4317.2  121.47  4330.9  120.17    4393  118.14  4605.4  112.91  4610.7  113.23
  4662.3  112.25  4817.7  111.78  4854.1  111.19  4955.6  111.18  4960.9  110.61
  4980.7  110.11  4991.3  110.08    5002  110.99  5011.1  111.31    5034  110.43
  5046.6  109.19  5055.3  109.98  5065.9  110.09  5077.3  110.97  5087.3  110.78
    5097  111.52  5102.3  111.52  5108.6  112.49  5119.2  112.18  5194.5  113.01
  5243.8  115.36  5394.3   120.1  5524.7  122.83  5594.9  123.57  5655.2  125.14
#Mann= 3 ,-1 , 0
  4317.2     .05       0    5002    .035       0    5097     .05       0
Bank Sta=5011.1,5097
XS Rating Curve= 0 ,0
Exp/Cntr=0.3,0.1

Chan Stop Cuts=-1
Use User Specified Reach Order=0
Composite Channel Slope=5