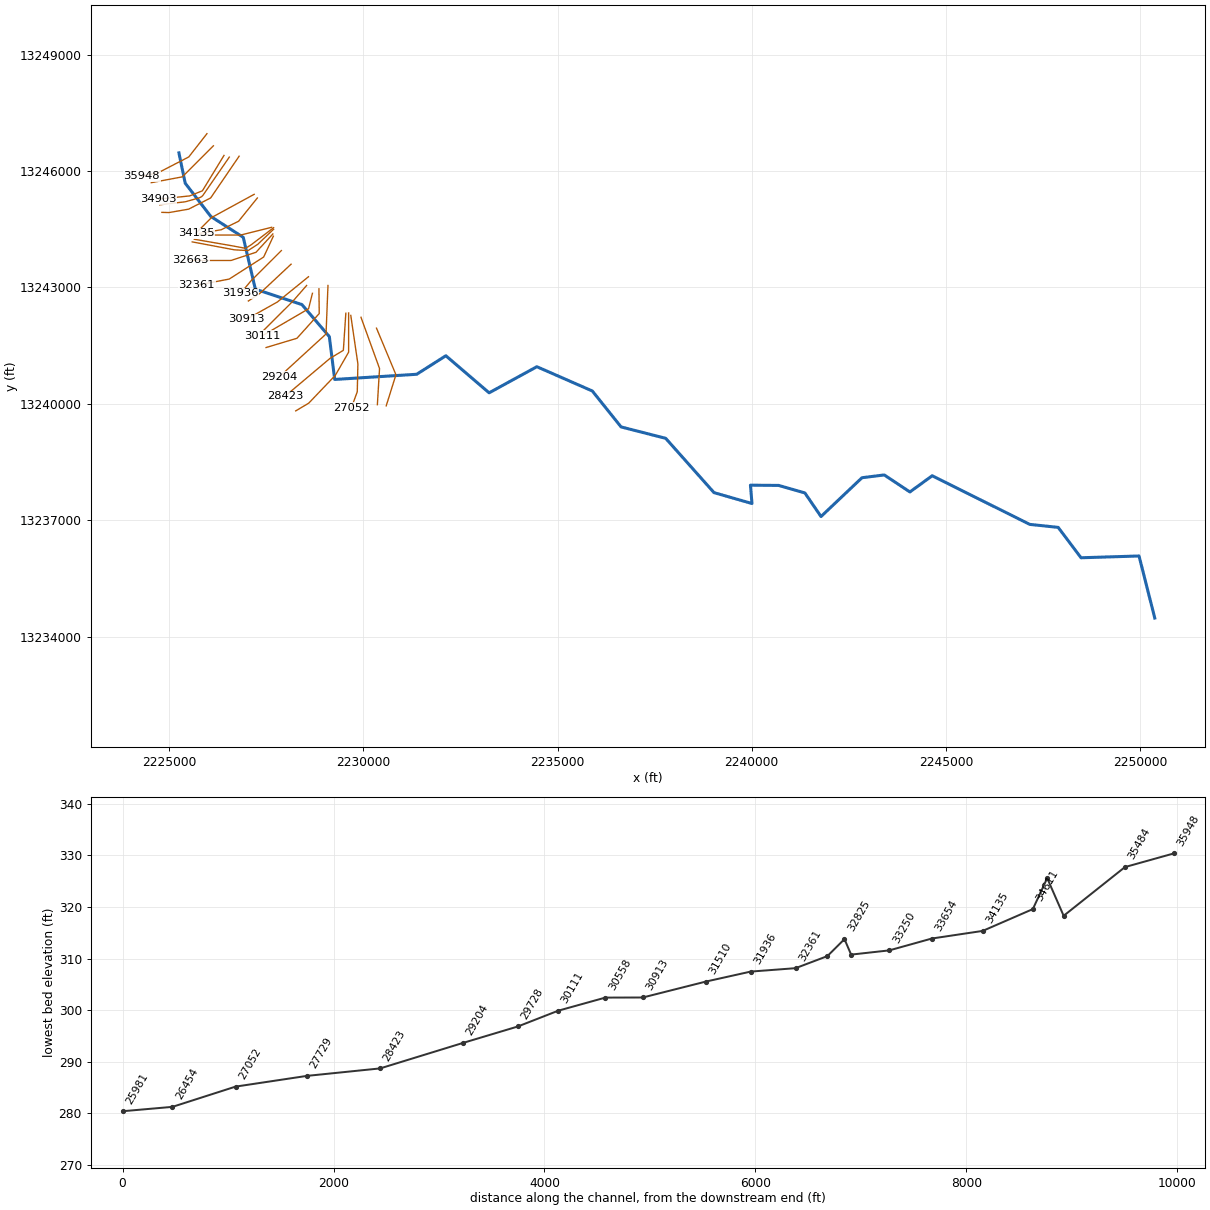
--- ELM CREEK.prj (project) ---

Proj Title=ELM CREEK Base Level Engineering
Current Plan=p01
Default Exp/Contr=0.3,0.1
English Units
Geom File=g01
Geom File=g02
Flow File=f01
Plan File=p01
Plan File=p02
Y Axis Title=Elevation
X Axis Title(PF)=Main Channel Distance
X Axis Title(XS)=Station
BEGIN DESCRIPTION:
ELM CREEK
END DESCRIPTION:
DSS Export Rating Curves= 0
DSS Export Rating Curve Sorted= 0
DSS Export Volume Flow Curves= 0
DXF OffsetX= 0
DXF OffsetY= 0
DXF ScaleX= 1
DXF ScaleY= 10

--- ELM CREEK.p01 (plan) ---

Plan Title=Multiple Run
Program Version=4.10
Short Identifier=Multiple
Geom File=g01
Flow File=f01
Subcritical Flow
K Sum by GR= 0
Std Step Tol= 0.01
Critical Tol= 0.01
Num of Std Step Trials= 20
Max Error Tol= 0.3
Flow Tol Ratio= 0.001
Split Flow NTrial= 30
Split Flow Tol= 0.02
Split Flow Ratio= 0.02
Log Output Level= 0
Friction Slope Method= 1
Unsteady Friction Slope Method= 2
Unsteady Bridges Friction Slope Method= 1
Parabolic Critical Depth
Global Vel Dist= 1 , 1 , 1
Global Log Level= 0
CheckData=True
Encroach Param=-1 ,0,0, 0
BEGIN DESCRIPTION:
Multiple Run
END DESCRIPTION:
Computation Interval=1HOUR
Output Interval=1HOUR
Run HTab= 0
Run UNet= 0
Run PostProcess= 0
Run WQNet= 0
UNET Theta= 1
UNET Theta Warmup= 1
UNET ZTol= 0.02
UNET ZSATol= 0.05
UNET MxIter= 20
UNET MaxInSteps= 0
UNET DtIC= 0
UNET DtMin= 0
UNET MaxCRTS= 20
UNET WFStab= 2
UNET SFStab= 1
UNET WFX= 1
UNET SFX= 1
UNET DSS MLevel= 4
UNET DZMax Abort= 100
UNET Convert EG Bridges= 0
UNET Use Existing IB Tables=-1
UNET Froude Reduction=False
UNET Froude Limit= 1
UNET Froude Power= 10
UNET Time Slicing=0,0, 5
UNET Junction Losses=0
Instantaneous Interval=1HOUR
Write IC File= 0
Write IC File at Sim End=0
Echo Input=False
Echo Parameters=False
Echo Output=False
Write Detailed= 0
WQ AD Non Conservative
WQ ULTIMATE=-1
WQ Max Comp Step=1HOUR
WQ Output Interval=15MIN
WQ Output Selected Increments= 0
WQ Output face flow=0
WQ Output face velocity=0
WQ Output face area=0
WQ Output face dispersion=0
WQ Output cell volume=0
WQ Output cell surface area=0
WQ Output cell continuity=0
WQ Output cumulative cell continuity=0
WQ Output face conc=0
WQ Output face dconc_dx=0
WQ Output face courant=0
WQ Output face peclet=0
WQ Output face adv mass=0
WQ Output face disp mass=0
WQ Output cell mass=0
WQ Output cell source sink temp=0
WQ Output cell source sink nsm=0
WQ Output MaxMinRange=-1
WQ Daily Max Min Mean=-1
WQ Daily Range=0
WQ Daily Time=0
WQ Create Restart=0
WQ Fixed Restart=0
WQ System Summary=0
WQ Use Fixed Temperature=0
Sorting and Armoring Iterations= 10
XS Update Threshold= 0.02
Hydraulics Update Threshold= 0.02
Energy Slope Method= 1
Volume Change Method= 0
XS Weighting Method= 0
Number of US Weighted Cross Sections= 1
Number of DS Weighted Cross Sections= 1
Upstream XS Weight=0.25
Main XS Weight=0.5
Downstream XS Weight=0.25
Number of DS XS's Weighted with US Boundary= 1
Upstream Boundary Weight= 1
Weight of XSs Associated with US Boundary= 0
Number of US XS's Weighted with DS Boundary= 1
Downstream Boundary Weight= 0.5
Weight of XSs Associated with DS Boundary= 0.5
Sediment Output Level= 4
Mass or Volume Output= 0
Output Increment Type= 1
Profile and TS Output Increment= 10
XS Output Flag= 0
XS Output Increment= 10
Disregard all LS=0
Disregard all Conn=0
Disregard all Breaches=0
Disregard all Pumps=0

--- ELM CREEK.p02 (plan) ---

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Plan Title=DUMMY
Short Identifier=DUM
Geom File=g02
Flow File=f01

--- ELM CREEK.f01 (steady flow) ---

Flow Title=Multiple
Program Version=4.10
Number of Profiles= 7
Profile Names=10-year,25-year,50-year,1pct_min,100-year,1pct_plu,500-year
River Rch & RM=ELM CREEK,Reach-1         ,35948
     259     366     457     420     568     768     891
River Rch & RM=ELM CREEK,Reach-1         ,34903
     359     516     650     604     817    1104    1307
River Rch & RM=ELM CREEK,Reach-1         ,32888
     467     678     861     804    1087    1471    1762
River Rch & RM=ELM CREEK,Reach-1         ,30111
     520     755     960     897    1213    1641    1967
River Rch & RM=ELM CREEK,Reach-1         ,25440
     563     818    1041     972    1315    1778    2132
River Rch & RM=ELM CREEK,Reach-1         ,21233
     966    1427    1833    1725    2333    3156    3842
River Rch & RM=ELM CREEK,Reach-1         ,16076
    1093    1615    2075    1953    2641    3572    4347
River Rch & RM=ELM CREEK,Reach-1         ,15223
    1093    1615    2075    1953    2641    3572    4347
River Rch & RM=ELM CREEK,Reach-1         ,8146
    1160    1719    2213    2086    2821    3815    4658
River Rch & RM=ELM CREEK,Reach-1         ,7619
    1189    1760    2264    2133    2885    3901    4757
River Rch & RM=ELM CREEK,Reach-1         ,1071
    1360    2023    2609    2464    3333    4507    5524
Boundary for River Rch & Prof#=ELM CREEK,Reach-1         , 1
Up Type= 0
Dn Type= 3
Dn Slope=0.00369
Boundary for River Rch & Prof#=ELM CREEK,Reach-1         , 2
Up Type= 0
Dn Type= 3
Dn Slope=0.00369
Boundary for River Rch & Prof#=ELM CREEK,Reach-1         , 3
Up Type= 0
Dn Type= 3
Dn Slope=0.00369
Boundary for River Rch & Prof#=ELM CREEK,Reach-1         , 4
Up Type= 0
Dn Type= 3
Dn Slope=0.00369
Boundary for River Rch & Prof#=ELM CREEK,Reach-1         , 5
Up Type= 0
Dn Type= 3
Dn Slope=0.00369
Boundary for River Rch & Prof#=ELM CREEK,Reach-1         , 6
Up Type= 0
Dn Type= 3
Dn Slope=0.00369
Boundary for River Rch & Prof#=ELM CREEK,Reach-1         , 7
Up Type= 0
Dn Type= 3
Dn Slope=0.00369
DSS Import GetInterval= 0
DSS Import GetPeak= 0
DSS Import FillOption= 0

--- ELM CREEK.g01 (geometry) ---

Geom Title=Existing Conditions
Program Version=4.10

River Reach=ELM CREEK       ,Reach-1
Reach XY= 30
       2225249.7     13246463.66      2225411.07      13245683.4
      2226072.39     13244824.79        2226906.     13244288.62
      2227217.92     13242952.37      2228416.66     13242555.29
      2229122.69     13241729.37      2229260.77     13240625.71
      2231372.07     13240759.18      2232123.39     13241236.32
      2233237.15     13240281.08      2234466.61     13240954.19
      2235894.02     13240328.59      2236635.22      13239402.2
      2237784.12     13239108.51      2239028.47     13237708.66
      2240005.84     13237428.86      2239966.51     13237900.76
      2240692.12     13237894.76      2241367.53     13237701.39
      2241783.51     13237093.06      2242839.13     13238093.31
      2243411.82     13238164.76      2244072.73     13237726.73
      2244646.47     13238143.84      2247159.28     13236890.63
      2247891.05     13236813.24      2248479.17     13236030.41
      2249972.68     13236076.44      2250377.72     13234476.86

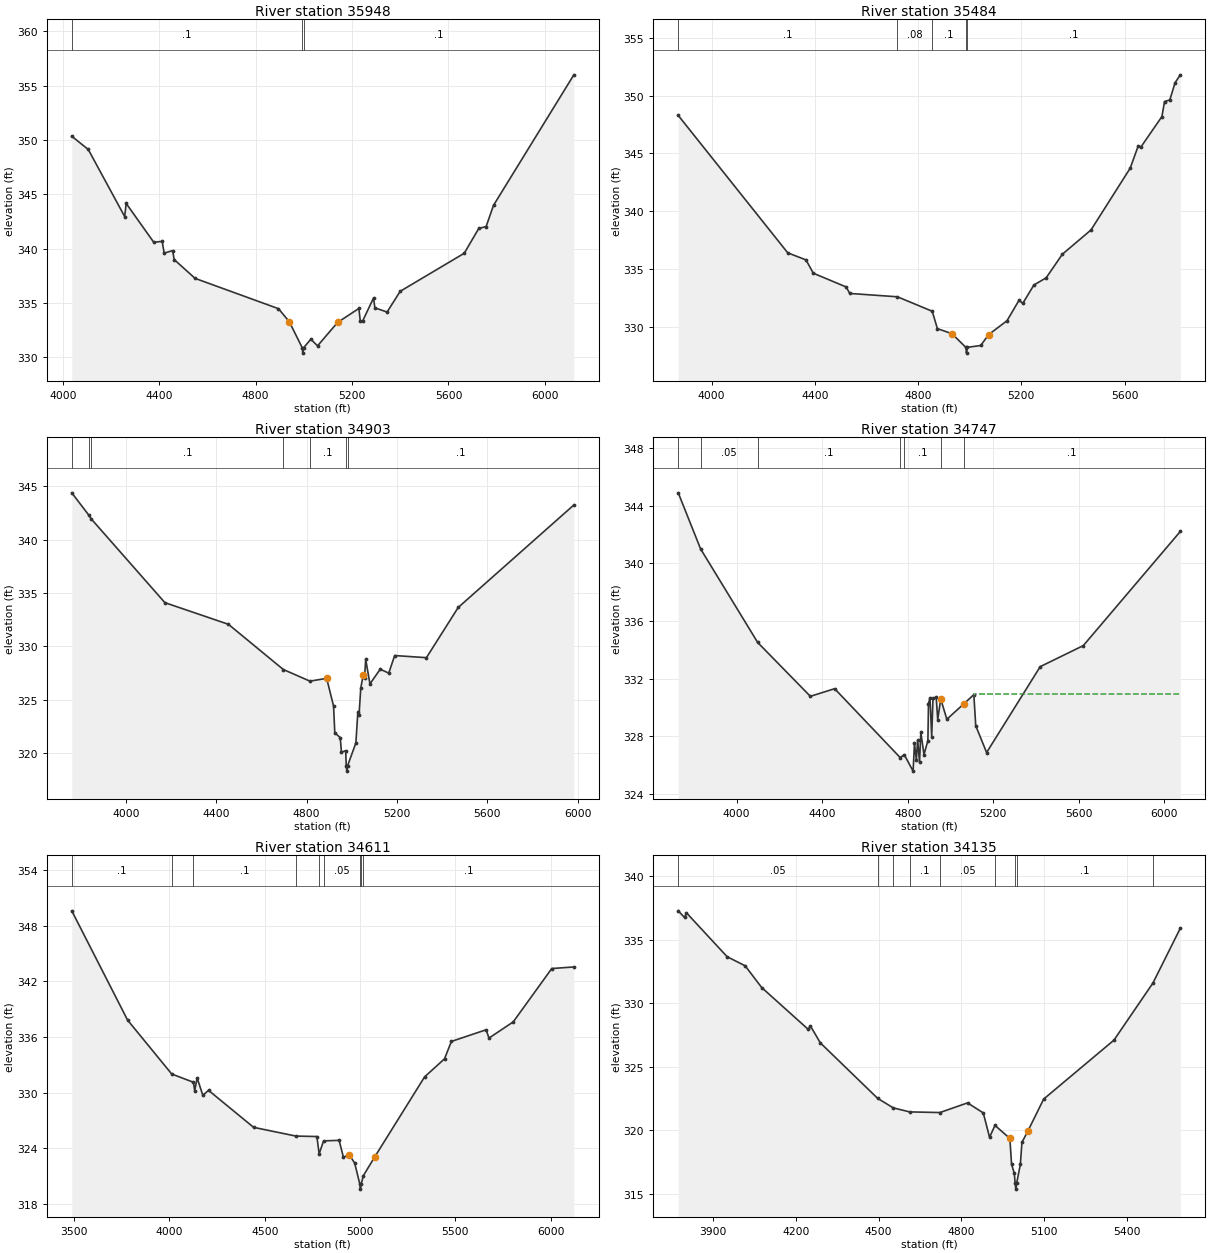
Type RM Length L Ch R = 1 ,35948   ,464,464,464
BEGIN DESCRIPTION:
ELM CREEK 65.0
END DESCRIPTION:
XS GIS Cut Line= 4
       2225971.5     13246960.03      2225503.44     13246360.32
      2224703.78     13245945.86      2224290.98      13245863.3
#Sta/Elev= 30
  4037.6  350.34    4106  349.12    4257  342.95  4263.4  344.15  4377.4  340.59
  4412.6  340.66  4420.8  339.59    4456  339.81  4462.4  338.99    4549  337.26
  4894.9  334.47  4939.9  333.27  4993.3  330.88    4996  330.38  4999.3  330.88
  5029.2  331.66    5057  331.05  5139.9   333.2  5228.4  334.49    5234  333.37
  5244.1  333.34  5289.1  335.45  5294.8  334.55  5345.4  334.16  5399.8  336.07
  5665.4  339.57  5725.6  341.85  5756.2  342.03  5786.8  343.98    6120  355.99
#Mann= 3 ,-1 , 0
  4037.6      .1       0  4993.3     .07       0  4999.3      .1       0
Bank Sta=4939.9,5139.9
XS Rating Curve= 0 ,0
Exp/Cntr=0.3,0.1

Type RM Length L Ch R = 1 ,35484   ,581,581,581
BEGIN DESCRIPTION:
ELM CREEK 64.0
END DESCRIPTION:
XS GIS Cut Line= 3
      2226137.75     13246646.89      2225337.72     13245846.85
      2224537.68     13245696.85
#Sta/Elev= 30
  3870.8  348.28  4295.1   336.4  4365.8  335.79  4394.1  334.64  4521.4  333.45
  4535.5  332.89  4720.2   332.6    4855  331.35  4874.9  329.85  4931.5  329.41
  4985.1  328.23  4987.8  327.73  4991.1  328.23  5042.9  328.39  5073.4  329.33
  5144.7  330.53  5191.3   332.3  5205.7  332.03  5248.9  333.62  5296.4  334.24
  5359.2  336.28  5470.2  338.38    5622  343.72  5653.4  345.66  5663.5  345.55
  5744.9  348.18  5755.1  349.48  5775.5  349.62  5795.8   351.1  5816.2  351.79
#Mann= 5 ,-1 , 0
  3870.8      .1       0  4720.2     .08       0    4855      .1       0
  4985.1     .07       0  4991.1      .1       0
Bank Sta=4931.5,5073.4
XS Rating Curve= 0 ,0
Exp/Cntr=0.3,0.1

Type RM Length L Ch R = 1 ,34903   ,156,156,156
BEGIN DESCRIPTION:
ELM CREEK 63.0
END DESCRIPTION:
XS GIS Cut Line= 4
      2226410.37     13246399.34      2225854.51     13245487.52
      2225527.82     13245355.87      2224728.21     13245272.99
#Sta/Elev= 30
  3759.7  344.39    3834  342.33  3845.7  341.95  4172.2  334.09  4453.6  332.06
  4696.8  327.82  4814.6  326.73  4888.8  326.99  4919.4  324.39  4924.8  321.89
  4948.9  321.43  4954.3  320.06  4973.1  320.21  4975.5  318.79  4978.2  318.29
  4981.5  318.79  5018.2  320.94  5026.8   323.8  5032.2  323.58  5039.8  326.06
  5050.5  327.31  5056.4  327.01  5061.7  328.77  5080.5  326.47    5126  327.85
  5163.8  327.48    5190  329.13  5330.7  328.93  5471.5  333.64  5983.7  343.25
#Mann= 7 ,-1 , 0
  3759.7      .1       0    3834     .05       0  3845.7      .1       0
  4696.8     .05       0  4814.6      .1       0  4975.5     .07       0
  4981.5      .1       0
Bank Sta=4888.8,5050.5
XS Rating Curve= 0 ,0
Exp/Cntr=0.3,0.1

Type RM Length L Ch R = 1 ,34747   ,136,136,136
BEGIN DESCRIPTION:
Mapping XS 04637d09
END DESCRIPTION:
XS GIS Cut Line= 6
      2226546.88     13246355.43      2225863.53      13245364.8
      2225834.89     13245337.02       2225780.2     13245308.38
      2225415.67     13245204.72      2224757.38      13245126.7
#Sta/Elev= 30
  3726.9   344.9  3831.4  341.01  4098.2  334.52  4344.6  330.78  4458.1  331.31
  4764.6  326.53  4783.6  326.73    4825  325.59  4831.3  327.53  4840.1  326.36
  4846.2  327.75    4855  326.21    4861  328.28  4875.9  326.74  4894.1  327.71
  4896.9  330.28  4903.8  330.68  4911.9  327.99  4917.9  330.63    4933   330.7
    4940  329.17  4954.2  330.59  4982.7  329.19    5063  330.27  5108.9   330.9
  5117.8  328.74  5168.6  326.88  5419.3  332.84  5620.7   334.3  6074.2  342.22
#Mann= 7 ,-1 , 0
  3726.9      .1       0  3831.4     .05       0  4098.2      .1       0
  4764.6     .05       0  4783.6      .1       0  4954.2     .07       0
    5063      .1       0
#XS Ineff= 2 , 0
       0 4902.98  330.63 5109.45       0  330.91
Permanent Ineff=
       T       T
Bank Sta=4954.2,5063
XS Rating Curve= 0 ,0
Exp/Cntr=0.3,0.1

Type RM Length L Ch R = 1 ,34611   ,476,476,476
BEGIN DESCRIPTION:
ELM CREEK 62.0
END DESCRIPTION:
XS GIS Cut Line= 5
      2226800.42      13246379.8      2226066.04     13245302.48
      2225498.56     13245014.56      2224996.34     13244926.79
      2224811.89     13244931.65
#Sta/Elev= 30
  3487.7  349.59  3780.6  337.81  4012.1     332  4126.1  331.11  4132.7  330.21
  4145.7  331.57  4175.5   329.7  4205.3  330.24  4441.8  326.25  4663.6  325.31
  4773.9  325.26  4785.7  323.39    4809  324.79  4890.5  324.85    4913  323.04
  4944.3  323.27  4972.2   322.4  4999.7  320.09  5002.4  319.59  5005.7  320.09
  5017.7  321.04  5077.9  323.08  5339.1  331.69  5443.7  333.64  5479.5  335.51
  5662.2  336.77  5676.7  335.87  5804.3  337.62  6006.3  343.37  6122.2  343.54
#Mann= 9 ,-1 , 0
  3487.7      .1       0  4012.1     .05       0  4126.1      .1       0
  4663.6     .05       0  4785.7      .1       0    4809     .05       0
  4999.7     .03       0  5005.7     .05       0  5017.7      .1       0
Bank Sta=4944.3,5077.9
XS Rating Curve= 0 ,0
Exp/Cntr=0.3,0.1

Type RM Length L Ch R = 1 ,34135   ,481,481,481
BEGIN DESCRIPTION:
ELM CREEK 61.0
END DESCRIPTION:
XS GIS Cut Line= 3
      2227187.69     13245396.84      2226087.72     13244796.85
      2225687.75     13244396.89
#Sta/Elev= 30
  3774.4  337.27  3797.1  336.75  3804.3  337.11  3951.4  333.66  4016.9  332.94
  4076.7  331.23  4245.7  327.93  4252.8  328.22  4289.3  326.87  4496.6  322.51
  4552.9  321.76  4612.4  321.44  4722.4  321.39  4822.3  322.15  4879.3  321.36
  4902.1  319.44  4921.7  320.38  4975.6  319.35  4981.8  317.31  4991.8   316.6
  4994.5  315.86  4997.2  315.36  5000.5  315.86  5013.6   317.3  5019.3  319.04
  5041.5  319.96  5098.1  322.45  5352.6  327.09  5493.7  331.58    5593   335.9
#Mann= 9 ,-1 , 0
  3774.4     .05       0  4496.6      .1       0  4552.9     .05       0
  4612.4      .1       0  4722.4     .05       0  4921.7      .1       0
  4994.5     .07       0  5000.5      .1       0  5493.7     .05       0
Bank Sta=4975.6,5041.5
XS Rating Curve= 0 ,0
Exp/Cntr=0.3,0.1

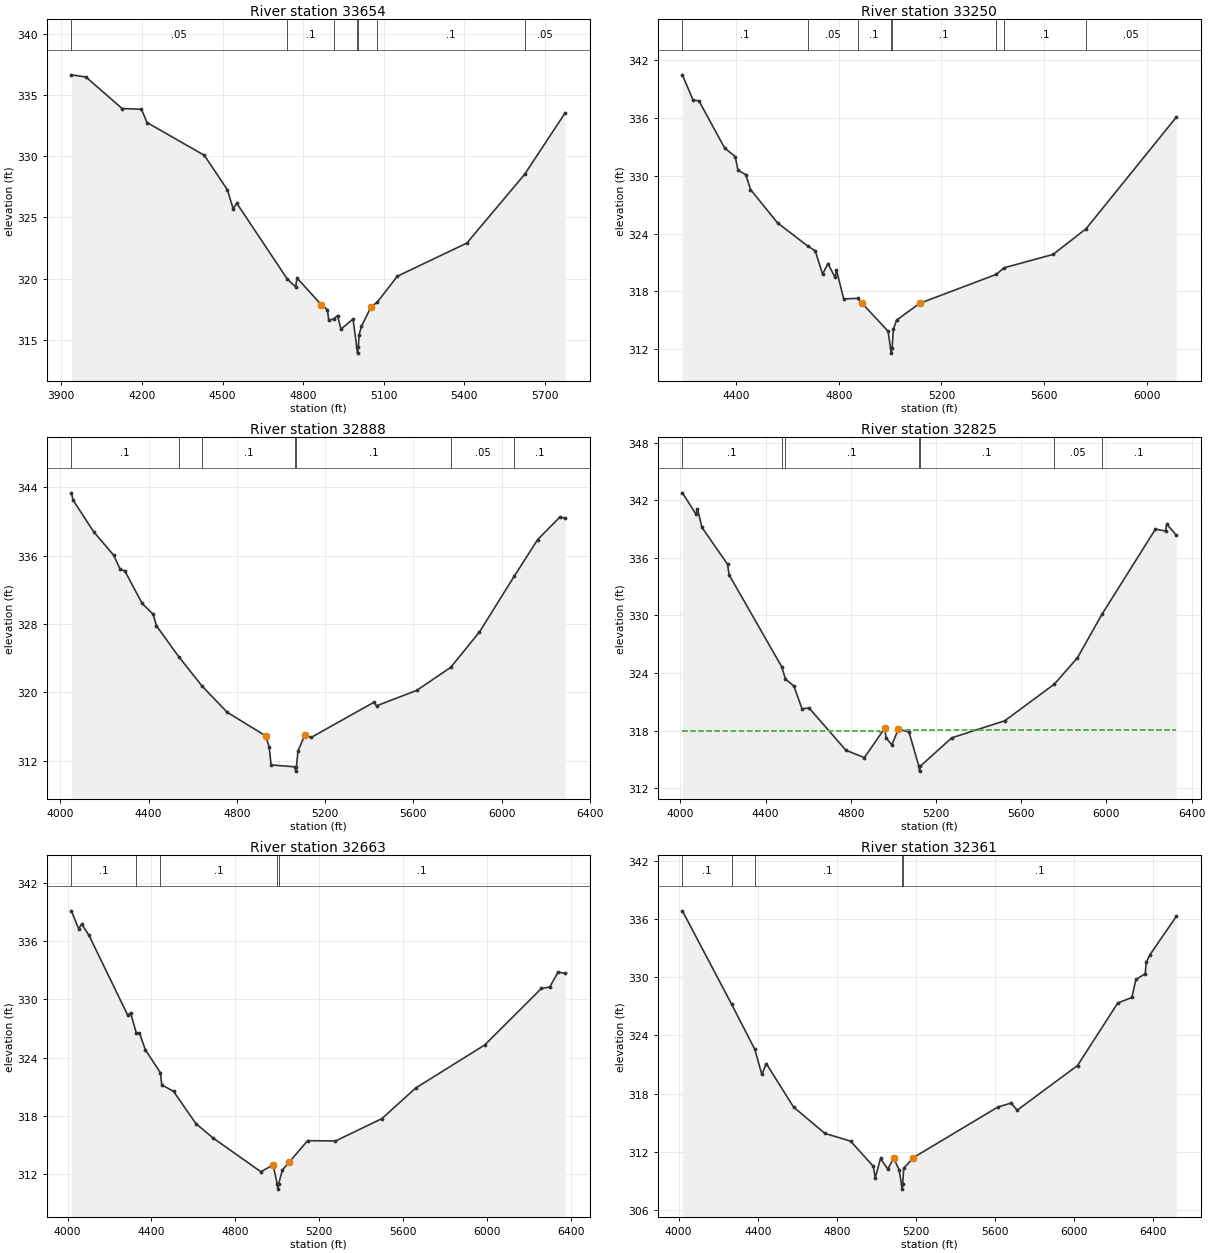
Type RM Length L Ch R = 1 ,33654   ,404,404,404
BEGIN DESCRIPTION:
ELM CREEK 60.0
END DESCRIPTION:
XS GIS Cut Line= 4
       2227268.5     13245302.21      2226785.81      13244702.5
      2226337.22     13244483.08      2225776.53     13244390.45
#Sta/Elev= 30
  3937.5  336.68  3991.9   336.5  4126.3  333.92  4198.3  333.86  4219.1  332.77
  4432.2  330.09  4518.2  327.26  4539.1  325.73  4553.4  326.15  4740.8  319.96
  4771.8  319.32  4777.3  320.03  4867.4  317.86  4889.9  317.46  4895.4  316.57
  4914.2   316.7  4927.9  316.97  4940.5  315.85  4985.5  316.68  4999.4  314.39
  5002.2  313.89  5005.4  314.39    5008  315.41  5016.9  316.08    5053   317.7
  5075.2  318.05  5150.5  320.19  5408.9   322.9  5623.6  328.52    5775  333.57
#Mann= 7 ,-1 , 0
  3937.5     .05       0  4740.8      .1       0  4914.2     .05       0
  4999.4     .03       0  5005.4     .05       0  5075.2      .1       0
  5623.6     .05       0
Bank Sta=4867.4,5053
XS Rating Curve= 0 ,0
Exp/Cntr=0.3,0.1

Type RM Length L Ch R = 1 ,33250   ,362,362,362
BEGIN DESCRIPTION:
ELM CREEK 59.0
END DESCRIPTION:
XS GIS Cut Line= 3
      2227637.68     13244546.84      2226837.72     13244346.85
       2225737.7     13244346.85
#Sta/Elev= 30
  4190.6  340.49  4231.8  337.89    4255  337.79  4355.5  332.88  4396.7     332
    4407   330.6  4437.9  330.12    4456  328.58  4561.6  325.11  4678.2  322.73
  4708.5  322.21  4736.9  319.79  4757.5  320.89  4785.8  319.45    4791  320.22
  4819.3  317.22  4873.3  317.28  4891.5  316.75    4992  313.87  5001.9  312.09
  5004.6  311.59  5007.9  312.09  5012.6  314.05  5025.2  315.01  5115.2  316.76
  5413.3  319.76  5444.2  320.45  5635.2  321.84    5764  324.51  6115.2  336.09
#Mann= 8 ,-1 , 0
  4190.6      .1       0  4678.2     .05       0  4873.3      .1       0
  5001.9     .07       0  5007.9      .1       0  5413.3     .05       0
  5444.2      .1       0    5764     .05       0
Bank Sta=4891.5,5115.2
XS Rating Curve= 0 ,0
Exp/Cntr=0.3,0.1

Type RM Length L Ch R = 1 ,32888   ,63,63,63
BEGIN DESCRIPTION:
Mapping XS 0be17355
END DESCRIPTION:
XS GIS Cut Line= 5
      2227687.88     13244536.73       2227112.5     13244097.88
      2226966.22     13244005.24      2226600.52      13244073.5
       2225644.8     13244239.29
#Sta/Elev= 30
  4049.9  343.34  4057.2  342.51  4150.7   338.8  4242.2  336.02  4271.3  334.38
  4292.1  334.21    4371  330.39  4420.9  329.12  4435.4  327.79  4536.2  324.18
  4642.3  320.73  4755.6  317.67  4930.7   314.9  4946.7  313.57  4955.3   311.5
  5064.2  311.27    5067  310.77  5070.2  311.27  5077.4  313.15  5107.9  314.97
  5138.4  314.73    5422  318.84  5433.2  318.41  5615.9  320.22  5769.7  322.92
  5900.1  327.06  6056.9  333.55  6163.9  337.87  6265.4  340.53  6288.7  340.35
#Mann= 7 ,-1 , 0
  4049.9      .1       0  4536.2     .05       0  4642.3      .1       0
  5064.2     .07       0  5070.2      .1       0  5769.7     .05       0
  6056.9      .1       0
Bank Sta=4930.7,5107.9
XS Rating Curve= 0 ,0
Exp/Cntr=0.3,0.1

Type RM Length L Ch R = 1 ,32825   ,162,162,162
BEGIN DESCRIPTION:
ELM CREEK 58.0
END DESCRIPTION:
XS GIS Cut Line= 5
      2227687.69     13244496.82      2227278.28     13244107.63
      2227029.61     13243946.73      2226678.54     13243966.23
      2225591.92     13244170.89
#Sta/Elev= 30
  4009.3  342.77    4073  340.55  4079.9  341.11  4101.3  339.16  4221.4  335.32
  4228.7  334.22  4475.7  324.64  4493.1  323.37  4532.8  322.63  4571.1  320.26
  4603.9  320.35  4777.3  315.94  4863.8  315.18  4960.1  318.27  4965.1  317.26
  4992.4   316.5  5022.5  318.11  5072.6  317.88  5119.6  314.27  5122.4  313.77
  5125.6  314.27  5273.7  317.24  5522.7  319.02  5755.1  322.83  5863.9  325.58
  5979.4  330.13  6230.2  338.99  6277.5  338.79  6282.5  339.53  6327.7  338.36
#Mann= 7 ,-1 , 0
  4009.3      .1       0  4475.7     .05       0  4493.1      .1       0
  5119.6     .07       0  5125.6      .1       0  5755.1     .05       0
  5979.4      .1       0
#XS Ineff= 2 , 0
       0 4937.68  317.92 5060.91       0  318.05
Permanent Ineff=
       T       T
Bank Sta=4960.1,5022.5
XS Rating Curve= 0 ,0
Exp/Cntr=0.3,0.1

Type RM Length L Ch R = 1 ,32663   ,302,302,302
BEGIN DESCRIPTION:
Mapping XS a471c164
END DESCRIPTION:
XS GIS Cut Line= 4
      2227668.47     13244375.19      2227234.03     13243902.42
      2226588.75     13243691.58      2225553.77     13243691.58
#Sta/Elev= 30
  4018.1  339.11    4053  337.27  4067.2  337.75  4102.3  336.58  4286.6  328.39
  4300.8   328.6  4327.7  326.56  4342.8  326.56  4371.1  324.81  4442.6  322.47
  4449.4  321.21  4505.5  320.54  4612.2  317.22  4693.6  315.75  4922.1  312.27
  4980.6  312.97  5000.5  310.98  5003.2  310.48  5006.5  310.98  5024.5  312.44
  5056.1  313.22  5145.2  315.47    5278  315.43    5500  317.74    5660  320.87
    5990  325.31    6260  331.12    6300  331.27    6340   332.8    6374  332.67
#Mann= 5 ,-1 , 0
  4018.1      .1       0  4327.7     .05       0  4442.6      .1       0
  5000.5     .07       0  5006.5      .1       0
Bank Sta=4980.6,5056.1
XS Rating Curve= 0 ,0
Exp/Cntr=0.3,0.1

Type RM Length L Ch R = 1 ,32361   ,425,425,425
BEGIN DESCRIPTION:
ELM CREEK 57.0
END DESCRIPTION:
XS GIS Cut Line= 4
      2227681.27     13244317.74      2227432.08     13243781.03
      2226544.03     13243212.42      2225707.06     13243052.69
#Sta/Elev= 30
    4019  336.85  4267.8  327.22  4384.8  322.58  4420.8  319.98  4443.7  321.09
  4581.1  316.61  4739.8  313.89    4870  313.09    4985  310.49  4994.3   309.3
  5021.4   311.3  5057.7  310.21  5088.2  311.33  5115.2  310.14  5127.5  308.64
  5130.2  308.14  5133.5  308.64  5138.4  310.28    5188   311.4    5615  316.61
  5681.8  317.02  5712.4  316.28  6017.8  320.89  6221.4  327.34  6292.7  327.91
  6313.2  329.77  6360.3  330.35  6365.4  331.54  6384.3  332.32  6517.3  336.27
#Mann= 5 ,-1 , 0
    4019      .1       0  4267.8     .05       0  4384.8      .1       0
  5127.5     .07       0  5133.5      .1       0
Bank Sta=5088.2,5188
XS Rating Curve= 0 ,0
Exp/Cntr=0.3,0.1

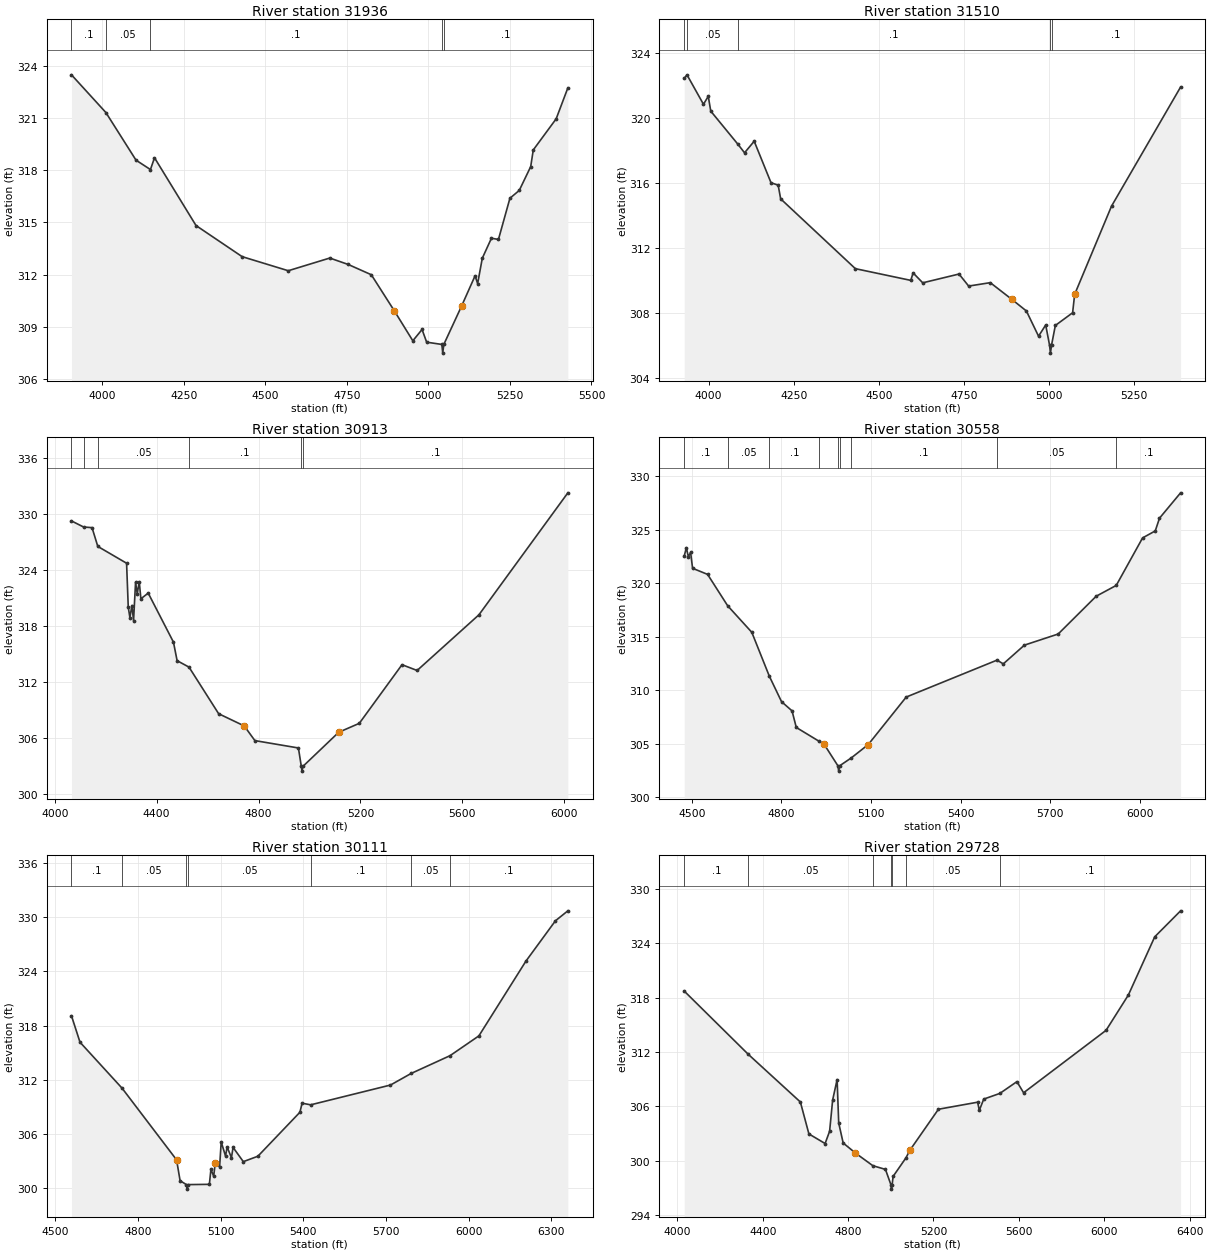
Type RM Length L Ch R = 1 ,31936   ,426,426,426
BEGIN DESCRIPTION:
ELM CREEK 56.0
END DESCRIPTION:
XS GIS Cut Line= 3
      2227887.69     13243946.83      2227087.72     13243146.85
      2226837.75     13242846.89
#Sta/Elev= 30
  3905.8  323.49  4011.3  321.32  4103.7  318.58  4147.9  318.04  4160.3  318.72
  4287.6  314.82    4429  313.03  4570.4  312.22  4697.7  312.95  4754.3  312.58
    4825  311.99  4895.7  309.91  4952.3  308.19  4980.6  308.84  4994.7  308.11
  5041.3  307.98    5044  307.48  5047.3  307.98  5101.6  310.18  5143.2  311.93
    5151  311.48  5165.3  312.94  5193.3  314.09  5214.8  314.02    5250  316.39
  5278.6  316.84  5313.7  318.21  5321.6  319.17  5391.8  320.96  5427.6  322.74
#Mann= 5 ,-1 , 0
  3905.8      .1       0  4011.3     .05       0  4147.9      .1       0
  5041.3     .07       0  5047.3      .1       0
Bank Sta=4895.7,5101.6
XS Rating Curve= 0 ,0
Exp/Cntr=0.3,0.1

Type RM Length L Ch R = 1 ,31510   ,597,597,597
BEGIN DESCRIPTION:
ELM CREEK 55.0
END DESCRIPTION:
XS GIS Cut Line= 3
      2228137.74     13243596.87      2227337.72     13242846.85
      2227037.69     13242646.84
#Sta/Elev= 30
  3928.6  322.42  3936.7  322.64  3985.1  320.83  3999.2  321.32  4006.5  320.41
    4086  318.38  4105.7  317.85    4134  318.56  4183.4  316.01  4204.4  315.86
  4211.7  315.02    4431  310.73  4593.7  310.01  4600.5  310.47  4628.8  309.86
  4735.3   310.4  4763.6  309.66  4827.1  309.87  4890.6  308.84  4933.1  308.13
  4968.8  306.58  4989.8  307.27    5001  306.04  5003.7  305.54    5007  306.04
  5018.1  307.24  5068.8  308.02  5074.8  309.15    5183  314.57  5385.8  321.89
#Mann= 5 ,-1 , 0
  3928.6      .1       0  3936.7     .05       0    4086      .1       0
    5001     .07       0    5007      .1       0
Bank Sta=4890.6,5074.8
XS Rating Curve= 0 ,0
Exp/Cntr=0.3,0.1

Type RM Length L Ch R = 1 ,30913   ,355,355,355
BEGIN DESCRIPTION:
ELM CREEK 54.0
END DESCRIPTION:
XS GIS Cut Line= 3
      2228585.58     13243272.53      2227785.58     13242622.53
      2226985.54     13242172.51
#Sta/Elev= 30
  4065.8  329.26  4113.2  328.61  4146.5  328.54  4169.1  326.53  4282.1  324.73
  4288.7  320.02  4295.1  318.91  4303.1   320.2  4309.5  318.58  4317.4   322.7
  4323.9  321.46  4331.8  322.75  4338.3  320.92    4367  321.53  4466.1  316.28
  4480.5  314.29  4527.2   313.6  4643.5  308.61  4744.1   307.3  4785.8  305.73
  4956.7  304.94  4968.1  302.96  4970.8  302.46  4974.1  302.96  5114.8  306.62
  5195.8  307.58  5363.4  313.86  5422.7  313.24  5665.6  319.21  6014.5  332.27
#Mann= 6 ,-1 , 0
  4065.8     .05       0  4113.2     .08       0  4169.1     .05       0
  4527.2      .1       0  4968.1     .07       0  4974.1      .1       0
Bank Sta=4744.1,5114.8
XS Rating Curve= 0 ,0
Exp/Cntr=0.3,0.1

Type RM Length L Ch R = 1 ,30558   ,447,447,447
BEGIN DESCRIPTION:
ELM CREEK 53.0
END DESCRIPTION:
XS GIS Cut Line= 3
      2228537.74     13243046.87      2228187.72     13242646.85
      2227387.72     13241846.86
#Sta/Elev= 30
  4474.4  322.53  4481.5  323.32  4488.2  322.47  4495.8  322.87  4502.4  321.39
  4552.7  320.82  4619.9  317.89  4700.8  315.41  4759.5  311.31  4800.4  308.93
  4835.6  308.07  4849.8  306.52  4927.3  305.21  4941.9     305  4989.2  302.94
  4991.9  302.44  4995.2  302.94  5034.3  303.68  5090.8  304.92  5218.1  309.36
  5522.3  312.81  5543.3  312.46    5614  314.21  5727.2  315.25  5854.5  318.78
  5921.7  319.79    6010  324.23  6052.4  324.88  6066.6  326.07  6137.3  328.44
#Mann= 9 ,-1 , 0
  4474.4      .1       0  4619.9     .05       0  4759.5      .1       0
  4927.3     .05       0  4989.2     .03       0  4995.2     .05       0
  5034.3      .1       0  5522.3     .05       0  5921.7      .1       0
Bank Sta=4941.9,5090.8
XS Rating Curve= 0 ,0
Exp/Cntr=0.3,0.1

Type RM Length L Ch R = 1 ,30111   ,383,383,383
BEGIN DESCRIPTION:
ELM CREEK 52.0
END DESCRIPTION:
XS GIS Cut Line= 3
      2228687.71     13242846.83      2228587.72     13242446.85
      2227387.74     13241746.87
#Sta/Elev= 30
  4558.7  319.08  4589.6  316.16  4742.6  311.06  4940.1  303.14  4952.9  300.83
  4975.8   300.4  4978.6   299.9  4981.8   300.4  5059.1  300.43  5064.8  302.09
  5074.8  301.33  5080.6  302.83  5096.3  302.38  5102.1  305.12  5117.8  303.56
  5123.6  304.56  5139.3  303.38  5145.1  304.52  5182.3  302.94  5235.2  303.54
  5387.8  308.41  5395.6  309.41  5426.8  309.23  5716.5  311.42  5791.3   312.7
  5932.6  314.67  6037.3  316.86  6207.7  325.12  6315.2   329.6  6360.2   330.7
#Mann= 7 ,-1 , 0
  4558.7      .1       0  4742.6     .05       0  4975.8     .03       0
  4981.8     .05       0  5426.8      .1       0  5791.3     .05       0
  5932.6      .1       0
Bank Sta=4940.1,5080.6
XS Rating Curve= 0 ,0
Exp/Cntr=0.3,0.1

Type RM Length L Ch R = 1 ,29728   ,524,524,524
BEGIN DESCRIPTION:
ELM CREEK 51.0
END DESCRIPTION:
XS GIS Cut Line= 4
      2228854.83     13242960.95      2228862.79     13242323.95
      2228289.52     13241686.98      2227493.29     13241448.11
#Sta/Elev= 30
  4032.4  318.73  4332.9  311.73  4576.5  306.47  4616.5  302.94  4692.4  301.88
  4713.5  303.24  4727.7  306.69  4748.6  308.95  4756.1  304.15    4777  301.94
  4833.9  300.84    4916  299.43  4975.1  299.02  5000.5  297.34  5003.3  296.84
  5006.5  297.34    5011  298.25  5071.5  300.31  5088.7  301.11  5223.3  305.67
  5407.1  306.45  5414.6  305.54  5435.5  306.79    5511  307.42  5590.9  308.72
  5622.2  307.49  6008.5  314.39  6112.9  318.29  6236.6  324.73  6357.7   327.6
#Mann= 7 ,-1 , 0
  4032.4      .1       0  4332.9     .05       0    4916      .1       0
  5000.5     .07       0  5006.5      .1       0  5071.5     .05       0
    5511      .1       0
Bank Sta=4833.9,5088.7
XS Rating Curve= 0 ,0
Exp/Cntr=0.3,0.1

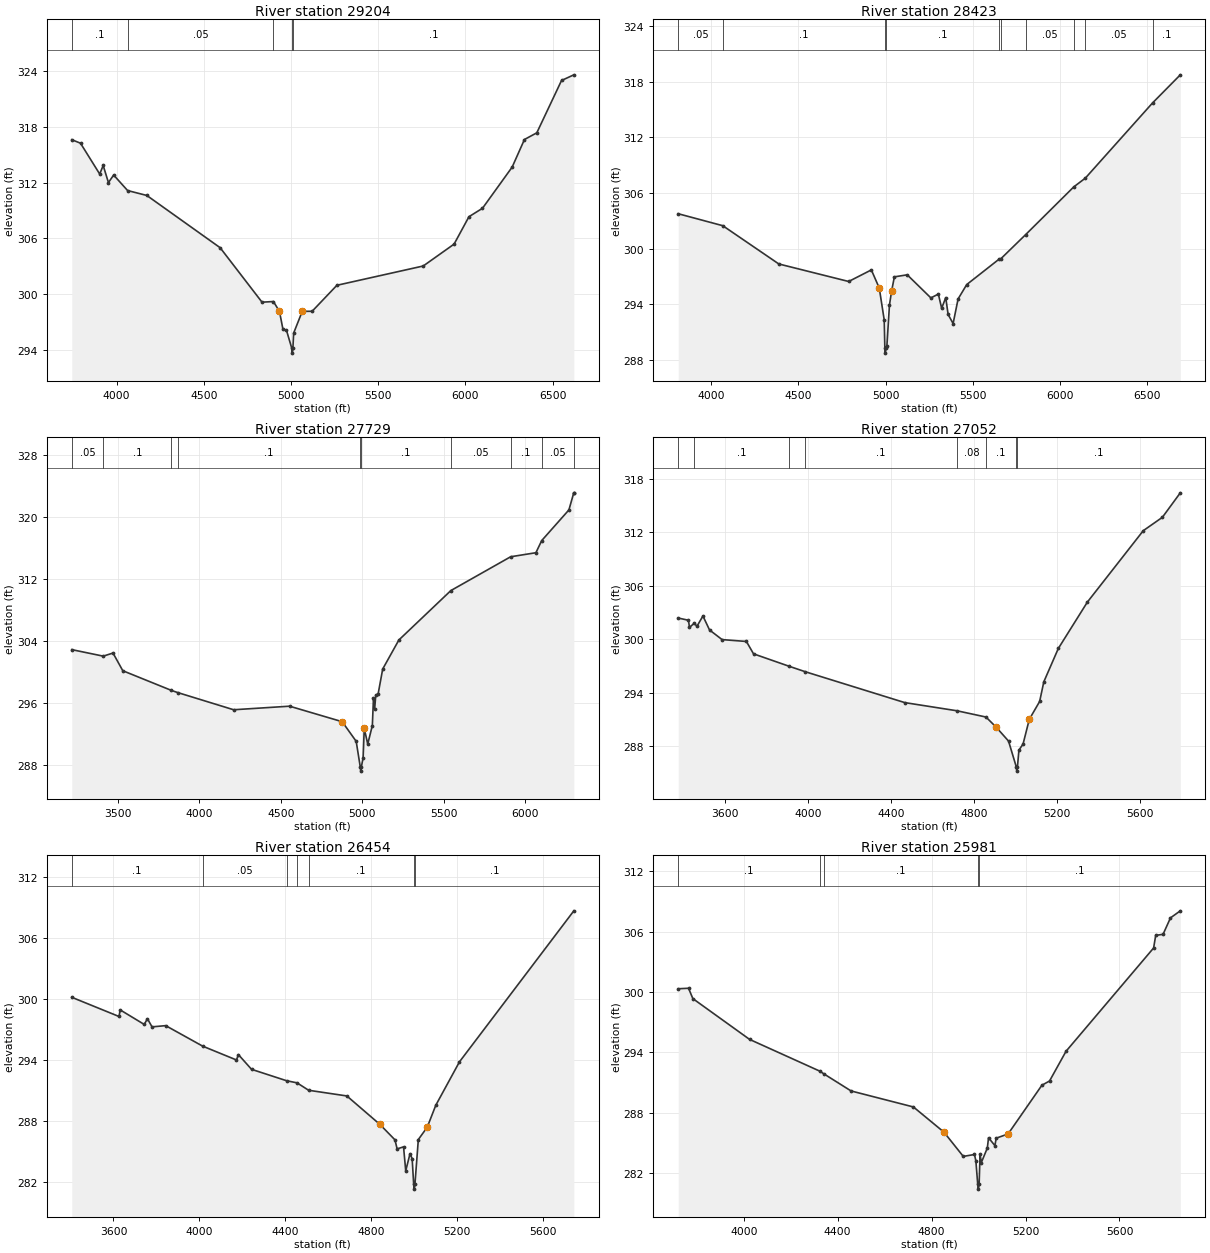
Type RM Length L Ch R = 1 ,29204   ,781,781,781
BEGIN DESCRIPTION:
ELM CREEK 50.0
END DESCRIPTION:
XS GIS Cut Line= 3
      2229087.72     13243046.87      2229037.72     13241796.85
      2227837.72     13240696.85
#Sta/Elev= 30
  3742.9  316.63    3793  316.25    3903  312.93  3923.1  313.85  3953.1  312.01
  3983.1  312.82  4063.1  311.15  4173.3  310.62  4593.6  304.99  4833.8  299.12
  4899.2  299.19  4933.9  298.12  4953.9  296.19  4973.9   296.1  5004.8  294.13
  5007.5  293.63  5010.8  294.13  5015.2  295.79  5064.5  298.13  5121.2  298.14
  5263.1  300.94  5758.2  303.02  5935.2  305.38  6020.3  308.33    6098  309.24
  6268.2  313.68  6338.5  316.65  6409.4  317.37  6551.2  323.01  6621.8  323.62
#Mann= 5 ,-1 , 0
  3742.9      .1       0  4063.1     .05       0  4899.2      .1       0
  5004.8     .07       0  5010.8      .1       0
Bank Sta=4933.9,5064.5
XS Rating Curve= 0 ,0
Exp/Cntr=0.3,0.1

Type RM Length L Ch R = 1 ,28423   ,694,694,694
BEGIN DESCRIPTION:
ELM CREEK 49.0
END DESCRIPTION:
XS GIS Cut Line= 4
      2229547.53     13242331.89      2229483.84     13241376.45
      2229141.47     13241169.44      2227980.04     13240190.97
#Sta/Elev= 30
  3812.3  303.76  4067.5  302.47  4388.6  298.34  4788.7  296.45  4918.6   297.7
    4964  295.74  4992.3  292.31    4996  289.22  4998.8  288.72    5002  289.22
  5007.8  289.54  5022.4  293.92    5035  295.45  5050.5  296.95  5124.2  297.17
  5259.6  294.68  5302.5  295.09  5321.4  293.56  5344.8  294.71  5358.4  292.89
    5387  291.91  5415.6  294.57  5465.1  296.12  5649.7  298.85    5662  298.93
  5803.2  301.52  6078.4  306.66  6144.4   307.6  6529.7  315.72  6688.6  318.75
#Mann= 10 ,-1 , 0
  3812.3     .05       0  4067.5      .1       0    4996     .07       0
    5002      .1       0  5649.7     .05       0    5662      .1       0
  5803.2     .05       0  6078.4      .1       0  6144.4     .05       0
  6529.7      .1       0
#XS Ineff= 2 , 0
       0 4916.98  297.67 5124.92       0  296.94
Permanent Ineff=
       F       T
Bank Sta=4964,5035
XS Rating Curve= 0 ,0
Exp/Cntr=0.3,0.1

Type RM Length L Ch R = 1 ,27729   ,677,677,677
BEGIN DESCRIPTION:
Mapping XS 100c5ddd
END DESCRIPTION:
XS GIS Cut Line= 5
      2229619.19     13242339.85      2229619.19     13241328.68
      2229276.82     13240731.52      2228592.08     13240014.93
      2228257.69     13239815.89
#Sta/Elev= 30
  3218.1  302.93  3411.1  302.09  3471.1  302.49  3531.1  300.21  3829.8  297.67
  3867.3   297.4  4211.1  295.18  4554.1  295.64  4876.9  293.64  4962.8  291.11
  4988.1  287.77  4990.9  287.27  4994.1  287.77  5005.3     289  5012.2  292.77
  5033.6  290.76  5061.9  293.15  5068.8  296.67    5076  295.27  5082.9  297.08
  5097.1  297.19  5125.4  300.43  5224.5  304.17  5543.4  310.54  5910.3   314.9
  6065.1  315.42    6101  316.99  6267.7  320.94  6297.4  323.14  6297.9  323.14
#Mann= 10 ,-1 , 0
  3218.1     .05       0  3411.1      .1       0  3829.8     .05       0
  3867.3      .1       0  4988.1     .07       0  4994.1      .1       0
  5543.4     .05       0  5910.3      .1       0    6101     .05       0
  6297.4      .1       0
Bank Sta=4876.9,5012.2
XS Rating Curve= 0 ,0
Exp/Cntr=0.3,0.1

Type RM Length L Ch R = 1 ,27052   ,598,598,598
BEGIN DESCRIPTION:
ELM CREEK 48.0
END DESCRIPTION:
XS GIS Cut Line= 4
      2229674.94     13242276.13      2229858.06     13241026.12
      2229842.13     13240309.53      2229690.86     13239895.52
#Sta/Elev= 30
  3372.5  302.37  3421.7  302.12  3426.8  301.32    3450  301.79  3462.7  301.44
  3491.6   302.6  3523.4  301.03    3584  299.95  3701.2  299.74  3735.6  298.35
  3904.4  296.98  3985.6  296.34  4464.7  292.88    4717  291.96  4856.3  291.26
  4905.2  290.13  4965.2  288.56  5002.2  285.69    5005  285.19  5008.2  285.69
  5015.2  287.55  5035.2  288.23  5065.2     291  5115.2  293.01  5135.2  295.21
  5205.3  298.96  5345.3  304.16  5614.7  312.17  5706.8  313.67  5793.4  316.42
#Mann= 8 ,-1 , 0
  3372.5     .05       0    3450      .1       0  3904.4     .05       0
  3985.6      .1       0    4717     .08       0  4856.3      .1       0
  5002.2     .07       0  5008.2      .1       0
Bank Sta=4905.2,5065.2
XS Rating Curve= 0 ,0
Exp/Cntr=0.3,0.1

Type RM Length L Ch R = 1 ,26454   ,473,473,473
BEGIN DESCRIPTION:
ELM CREEK 47.0
END DESCRIPTION:
XS GIS Cut Line= 3
       2229937.7     13242228.36      2230415.41     13240906.69
      2230359.67     13239975.11
#Sta/Elev= 30
  3405.7  300.15  3625.8  298.26  3631.2  298.91  3743.2  297.48  3758.2  298.04
  3779.5  297.24  3843.3  297.36  4015.6  295.34  4172.9  293.98  4181.8  294.51
  4243.1  293.06    4406  291.94  4454.9  291.73    4509     291    4687  290.44
  4840.9  287.64  4911.1  286.12  4921.1  285.23  4951.1  285.43  4961.2  283.07
  4981.2  284.76  4991.2  284.26  4998.2  281.77    5001  281.27  5004.2  281.77
  5019.9  286.15  5061.3  287.36  5101.4  289.53  5211.6   293.8  5744.3  308.66
#Mann= 7 ,-1 , 0
  3405.7      .1       0  4015.6     .05       0    4406      .1       0
  4454.9     .08       0    4509      .1       0  4998.2     .07       0
  5004.2      .1       0
Bank Sta=4840.9,5061.3
XS Rating Curve= 0 ,0
Exp/Cntr=0.3,0.1

Type RM Length L Ch R = 1 ,25981   ,541,541,541
BEGIN DESCRIPTION:
ELM CREEK 46.0
END DESCRIPTION:
XS GIS Cut Line= 3
      2230337.71     13241946.87      2230837.72     13240746.85
      2230587.71     13239946.83
#Sta/Elev= 30
    3721  300.32  3764.9  300.37  3783.3  299.34  4024.9  295.29  4324.6  292.13
  4340.4  291.88  4457.1  290.17  4722.6  288.58  4852.6  286.08  4934.9  283.67
  4982.6  283.86  4988.5  283.23  4996.4  280.92  4999.1  280.42  5002.4  280.92
  5006.4  283.87  5011.8  283.06  5037.3   284.5  5042.5  285.52  5069.7  284.74
    5075  285.48  5125.8   285.9  5269.8  290.74  5302.3  291.16  5372.5  294.11
  5745.5  304.37  5754.4  305.62  5785.8  305.73  5817.3  307.36  5859.2  308.06
#Mann= 5 ,-1 , 0
    3721      .1       0  4324.6     .08       0  4340.4      .1       0
  4996.4     .07       0  5002.4      .1       0
Bank Sta=4852.6,5125.8
XS Rating Curve= 0 ,0
Exp/Cntr=0.3,0.1