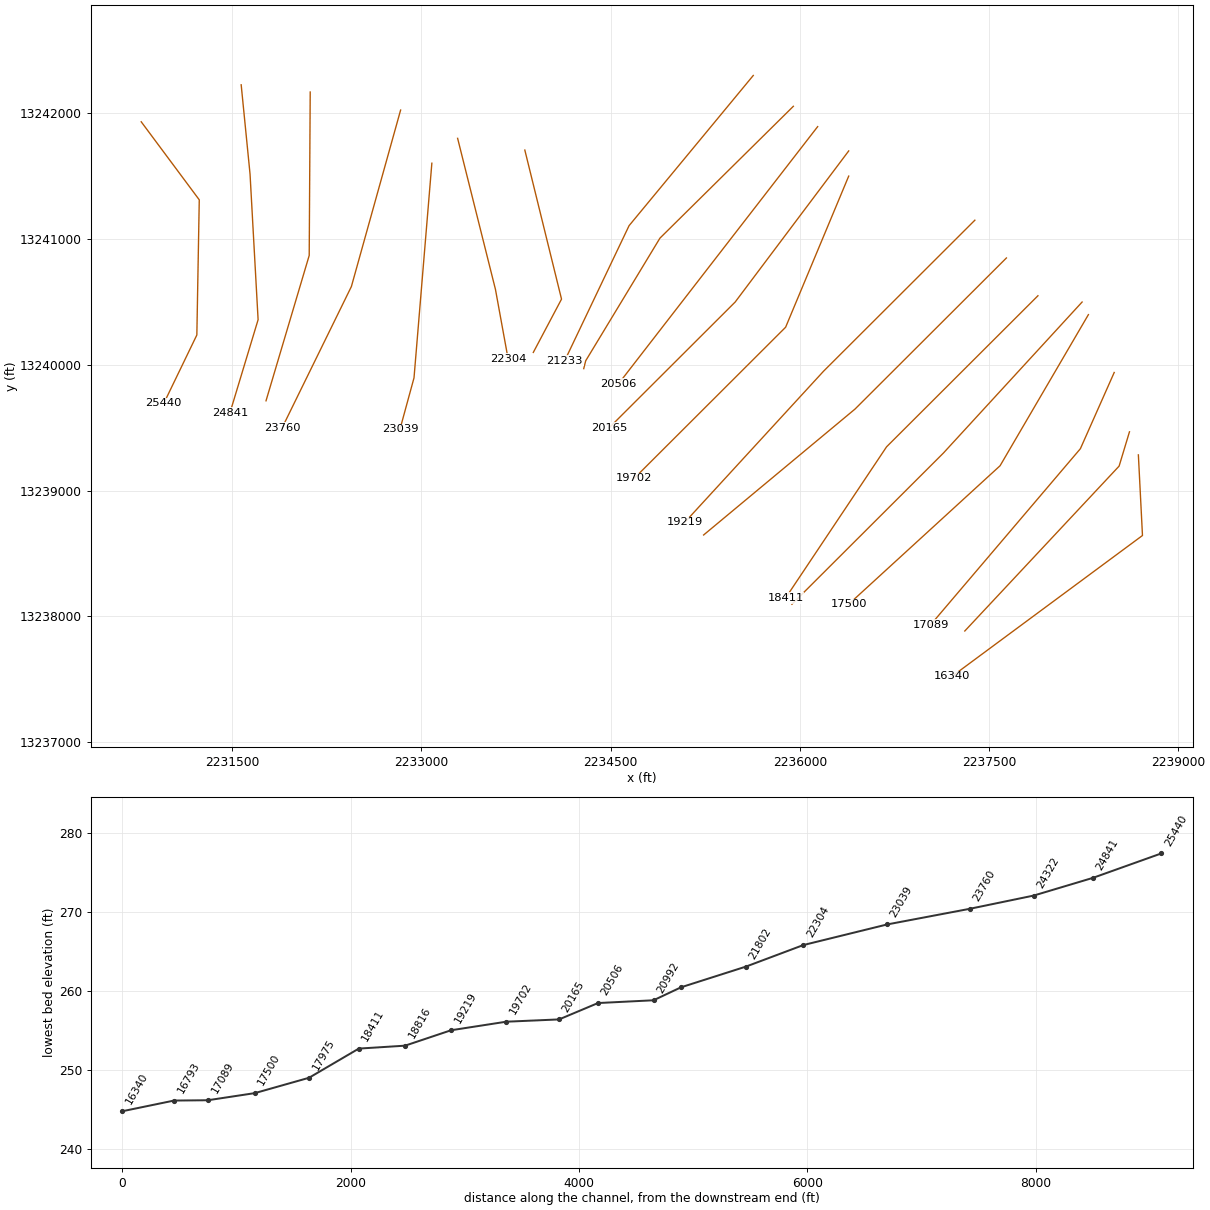
HEC-RAS study ELM CREEK.prj: ELM CREEK Base Level Engineering

--- ELM CREEK.g01 (geometry) --- (continued)

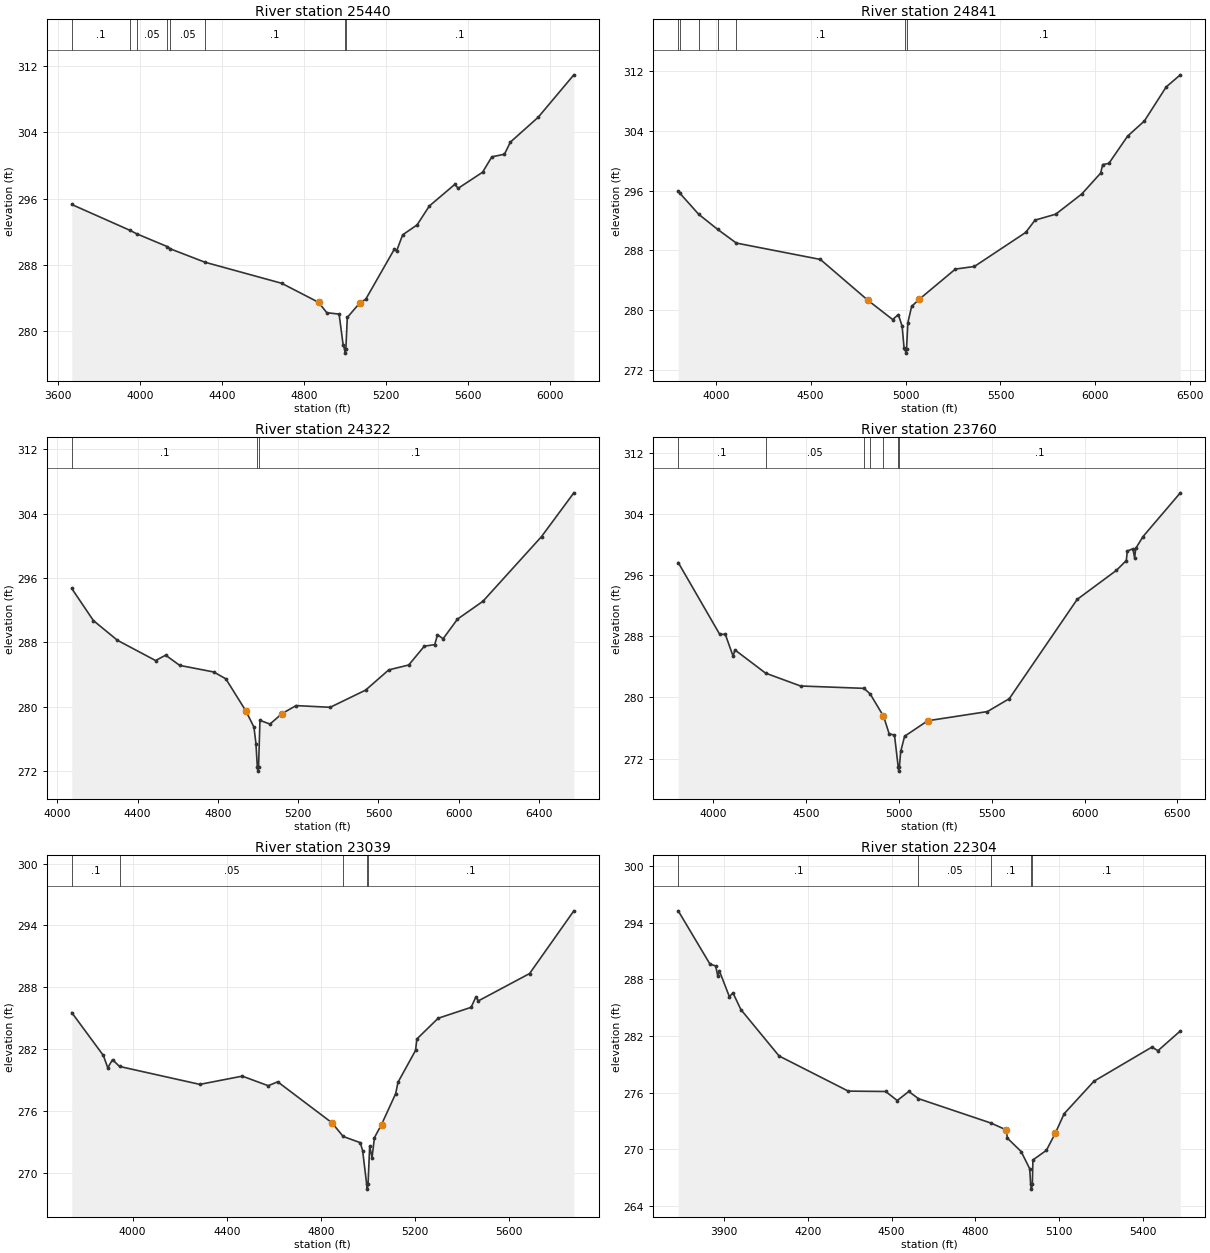
Type RM Length L Ch R = 1 ,25440   ,599,599,599
BEGIN DESCRIPTION:
ELM CREEK 45.0
END DESCRIPTION:
XS GIS Cut Line= 4
      2230779.83     13241928.29      2231239.86     13241308.53
       2231220.7     13240235.19      2230958.74     13239692.11
#Sta/Elev= 30
  3668.4  295.31  3952.2  292.19  3985.1  291.77  4134.1  290.23  4149.6  289.95
  4318.1  288.34  4691.9   285.8    4872   283.5    4912  282.25    4972  282.08
    4992  278.31    4999  277.87  5001.7  277.37    5005  277.87    5012  281.68
    5072   283.4    5102  283.88    5242  289.94    5252  289.68    5282  291.65
  5352.1  292.84  5412.1  295.13  5535.9  297.73  5552.9  297.27  5671.5   299.2
  5716.8  301.06  5778.4  301.38  5807.2  302.84  5942.9  305.84  6116.7  310.96
#Mann= 8 ,-1 , 0
  3668.4      .1       0  3952.2     .08       0  3985.1     .05       0
  4134.1      .1       0  4149.6     .05       0  4318.1      .1       0
    4999     .07       0    5005      .1       0
Bank Sta=4872,5072
XS Rating Curve= 0 ,0
Exp/Cntr=0.3,0.1

Type RM Length L Ch R = 1 ,24841   ,519,519,519
BEGIN DESCRIPTION:
ELM CREEK 44.0
END DESCRIPTION:
XS GIS Cut Line= 4
      2231572.09     13242222.11      2231642.36     13241512.97
      2231706.25     13240356.58      2231482.69     13239615.64
#Sta/Elev= 30
  3802.5  295.89  3811.5  295.64  3910.5  292.83  4009.5  290.83  4108.4  288.99
  4551.3   286.8  4801.7  281.34  4931.9  278.77  4961.9  279.43  4981.9  277.88
    4992  274.99    4999  274.78  5001.7  274.28    5005  274.78    5012  278.34
    5032  280.53  5072.1  281.48  5262.4  285.51  5362.5  285.86  5632.9  290.41
  5681.8  292.05  5791.2  292.85  5928.4  295.55  6027.3  298.33  6038.6  299.48
  6070.7  299.63  6169.6  303.28  6257.9   305.3  6372.7  309.85  6447.2  311.47
#Mann= 7 ,-1 , 0
  3802.5     .05       0  3811.5     .08       0  3910.5      .1       0
  4009.5     .05       0  4108.4      .1       0    4999     .07       0
    5005      .1       0
Bank Sta=4801.7,5072.1
XS Rating Curve= 0 ,0
Exp/Cntr=0.3,0.1

Type RM Length L Ch R = 1 ,24322   ,562,562,562
BEGIN DESCRIPTION:
ELM CREEK 43.0
END DESCRIPTION:
XS GIS Cut Line= 3
       2232119.3     13242164.66      2232111.34     13240866.88
      2231768.97     13239712.38
#Sta/Elev= 30
  4071.7   294.7  4179.5  290.72  4299.5  288.27  4489.5  285.76  4539.5  286.43
  4609.5  285.16  4779.5  284.34  4839.5  283.49  4939.5   279.5  4979.5   277.5
  4989.5  275.46  4996.5  272.54  4999.3  272.04  5002.5  272.54  5009.5  278.34
  5059.5  277.88  5119.5  279.18  5189.5  280.17  5359.5  279.96  5535.9  282.09
  5651.2   284.6  5750.9  285.21  5828.5  287.54  5880.6  287.74  5894.2  288.96
  5922.3  288.47  5993.9   290.9  6120.5  293.11  6412.6  301.14  6573.7  306.57
#Mann= 3 ,-1 , 0
  4071.7      .1       0  4996.5     .07       0  5002.5      .1       0
Bank Sta=4939.5,5119.5
XS Rating Curve= 0 ,0
Exp/Cntr=0.3,0.1

Type RM Length L Ch R = 1 ,23760   ,721,721,721
BEGIN DESCRIPTION:
Mapping XS 40f5742b
END DESCRIPTION:
XS GIS Cut Line= 3
      2232835.89     13242021.39      2232445.75     13240620.05
      2231896.37     13239497.41
#Sta/Elev= 30
  3811.2  297.65  4033.9  288.29    4065  288.24  4106.6   285.4  4116.5  286.22
  4281.8  283.18  4469.9   281.5  4811.6  281.19  4845.1  280.46    4915  277.62
  4916.2  277.62  4947.4  275.24  4976.1  275.08  4996.3  270.86    4999  270.36
  5002.3  270.86  5009.6  272.93  5030.4  274.92    5155  276.95  5476.4  278.15
  5594.5  279.84  5960.2  292.83  6171.2  296.62  6224.8  297.91  6230.3  299.16
  6260.3  299.45  6269.8  298.24  6275.3  299.49  6314.8  301.05  6515.7  306.77
#Mann= 7 ,-1 , 0
  3811.2      .1       0  4281.8     .05       0  4811.6      .1       0
  4845.1     .05       0    4915      .1       0  4996.3     .07       0
  5002.3      .1       0
Bank Sta=4916.2,5155
XS Rating Curve= 0 ,0
Exp/Cntr=0.3,0.1

Type RM Length L Ch R = 1 ,23039   ,735,735,735
BEGIN DESCRIPTION:
ELM CREEK 42.0
END DESCRIPTION:
XS GIS Cut Line= 3
      2233083.51     13241599.43      2232942.06     13239894.65
      2232830.41     13239485.24
#Sta/Elev= 30
  3741.2  285.53  3875.4  281.37  3894.3  280.17  3914.4  280.96  3944.2   280.3
  4285.6  278.56  4466.3  279.36  4576.6  278.43  4616.8  278.81  4847.6  274.83
  4895.6   273.5    4968   272.9    4978  272.13  4995.1  268.89  4997.8  268.39
  5001.1  268.89  5008.1  272.58  5018.1  271.45  5028.2  273.39  5058.3  274.66
  5118.5  277.66  5128.5  278.77  5202.9  281.85  5208.8  282.97  5299.1  284.98
  5439.2  286.04  5459.9  287.06  5470.3  286.67    5688  289.32  5876.2  295.41
#Mann= 5 ,-1 , 0
  3741.2      .1       0  3944.2     .05       0  4895.6      .1       0
  4995.1     .07       0  5001.1      .1       0
Bank Sta=4847.6,5058.3
XS Rating Curve= 0 ,0
Exp/Cntr=0.3,0.1

Type RM Length L Ch R = 1 ,22304   ,502,502,502
BEGIN DESCRIPTION:
ELM CREEK 41.0
END DESCRIPTION:
XS GIS Cut Line= 3
      2233287.73     13241796.82      2233587.72     13240596.85
      2233687.72     13240046.87
#Sta/Elev= 30
  3736.9  295.25  3850.2  289.62  3870.9  289.41  3878.6   288.3  3883.7  288.92
  3919.8  286.16  3932.7  286.56  3961.1  284.79  4097.6  279.88    4345  276.16
    4479  276.12  4520.3  275.16  4561.5  276.12  4596.3  275.36  4856.1  272.77
  4909.4  272.06  4914.5  271.17  4963.5  269.76  4994.1  267.94  4997.5  266.28
  5000.2  265.78  5003.5  266.28  5005.6  268.87  5053.8  269.89  5085.6   271.7
  5117.4  273.77  5224.1  277.21  5431.2  280.82  5452.8  280.44  5532.8  282.53
#Mann= 5 ,-1 , 0
  3736.9      .1       0  4596.3     .05       0  4856.1      .1       0
  4997.5     .07       0  5003.5      .1       0
Bank Sta=4909.4,5085.6
XS Rating Curve= 0 ,0
Exp/Cntr=0.3,0.1

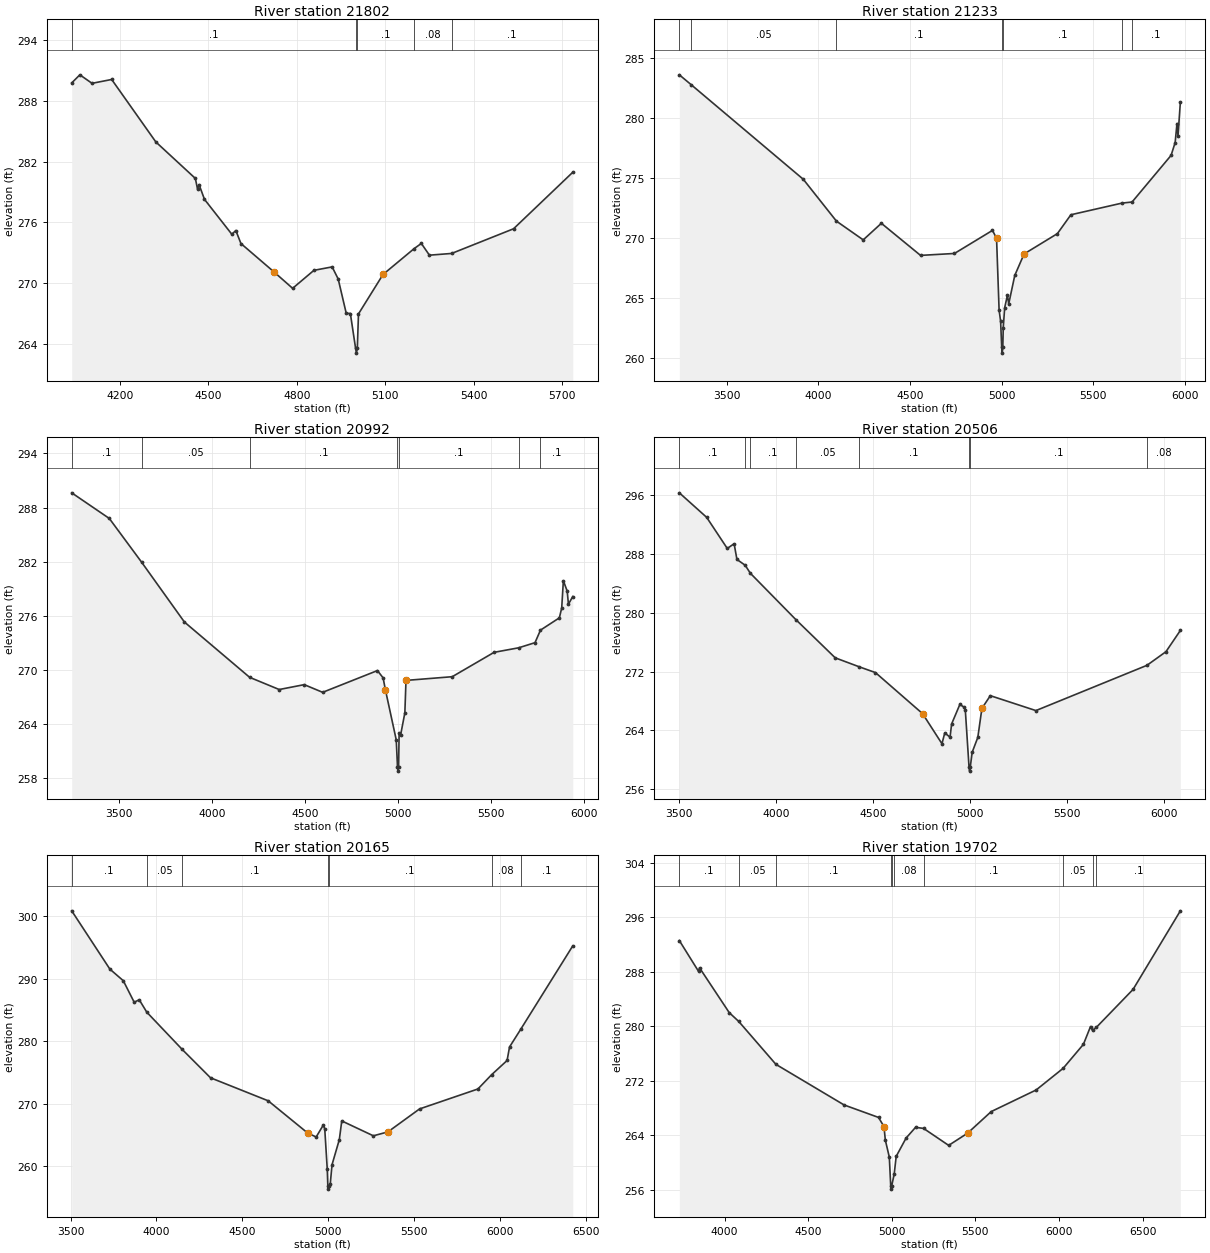
Type RM Length L Ch R = 1 ,21802   ,569,569,569
BEGIN DESCRIPTION:
ELM CREEK 40.0
END DESCRIPTION:
XS GIS Cut Line= 3
       2233820.5     13241703.63      2234111.33     13240519.95
      2233887.74     13240096.88
#Sta/Elev= 30
  4037.7  289.79  4065.3  290.59  4106.5  289.75  4173.1  290.13  4322.7  283.95
  4456.6  280.34  4463.9  279.29  4469.1  279.73  4487.5  278.27  4580.1  274.82
  4593.7  275.19    4611   273.9  4724.3  271.06  4786.1  269.47  4858.2  271.25
    4920  271.59  4940.5  270.39  4967.7     267  4981.7  266.98  4999.3  263.56
  5002.1  263.06  5005.3  263.56  5009.2  266.94  5092.3  270.84  5197.8   273.4
  5222.1  273.91  5249.5  272.75  5324.8  272.92  5534.5  275.36  5735.1  280.95
#Mann= 5 ,-1 , 0
  4037.7      .1       0  4999.3     .07       0  5005.3      .1       0
  5197.8     .08       0  5324.8      .1       0
Bank Sta=4724.3,5092.3
XS Rating Curve= 0 ,0
Exp/Cntr=0.3,0.1

Type RM Length L Ch R = 1 ,21233   ,241,241,241
BEGIN DESCRIPTION:
Mapping XS 1575e471
END DESCRIPTION:
XS GIS Cut Line= 3
      2235631.18     13242296.09       2234646.8     13241103.38
      2234136.73     13240031.19
#Sta/Elev= 30
  3241.8  283.59  3305.6  282.78  3918.2   274.9    4099  271.42  4245.2  269.86
  4344.2  271.24  4557.9  268.57    4743  268.73  4950.5  270.65  4972.7  269.99
  4986.6  264.01  4994.8   263.1  5000.8  260.94  5003.6  260.44  5006.8  260.94
  5009.3  262.57    5017  264.22  5032.1  265.26  5039.1  264.54    5072   266.9
  5122.9  268.69  5304.6  270.38  5378.3  271.95  5657.2  272.92  5712.1  273.01
    5925  276.89  5947.2  277.96  5957.2  279.54  5962.7  278.51  5975.6  281.32
#Mann= 7 ,-1 , 0
  3241.8      .1       0  3305.6     .05       0    4099      .1       0
  5000.8     .07       0  5006.8      .1       0  5657.2     .08       0
  5712.1      .1       0
Bank Sta=4972.7,5122.9
XS Rating Curve= 0 ,0
Exp/Cntr=0.3,0.1

Type RM Length L Ch R = 1 ,20992   ,486,486,486
BEGIN DESCRIPTION:
Mapping XS ec85255c
END DESCRIPTION:
XS GIS Cut Line= 4
      2235948.88      13242051.3      2234891.59     13241004.43
      2234303.05     13240030.47      2234287.42     13239967.95
#Sta/Elev= 30
  3248.2  289.63  3450.1  286.79  3623.7  281.94  3853.2  275.32  4203.6  269.19
  4362.3  267.84  4496.7  268.38  4595.7  267.53  4889.8  269.94  4920.2  269.13
  4932.5  267.81  4990.7  262.27  4997.4   259.3  5000.1   258.8  5003.4   259.3
  5006.2  262.98  5013.7  262.75    5037  265.26  5043.1  268.85  5291.4  269.26
  5516.1  271.96  5647.6  272.46  5735.8  273.03  5765.2  274.42  5866.6  275.78
  5879.2  276.87  5888.1  279.89  5908.7  278.74  5915.3   277.3  5938.5  278.14
#Mann= 7 ,-1 , 0
  3248.2      .1       0  3623.7     .05       0  4203.6      .1       0
  4997.4     .07       0  5003.4      .1       0  5647.6     .08       0
  5765.2      .1       0
Bank Sta=4932.5,5043.1
XS Rating Curve= 0 ,0
Exp/Cntr=0.3,0.1

Type RM Length L Ch R = 1 ,20506   ,341,341,341
BEGIN DESCRIPTION:
Mapping XS 2ba93f1e
END DESCRIPTION:
XS GIS Cut Line= 2
      2236141.61     13241889.87      2234563.48     13239848.19
#Sta/Elev= 30
  3502.8  296.33  3643.7  292.99  3749.7  288.76    3785   289.4  3799.5  287.26
  3842.1  286.47  3868.7  285.38  4103.1  279.07  4305.7  273.87  4430.3  272.64
  4513.1  271.86  4755.8  266.27  4855.4  262.18  4869.9  263.65  4897.1  263.07
  4905.2  264.87  4947.5  267.52  4969.5  267.16  4975.8  266.74    4995  258.95
  4997.8  258.45    5001  258.95  5011.2  261.03  5040.1  263.04  5061.2  266.99
  5104.5  268.72  5339.3  266.69  5911.2  272.85  6009.2  274.71  6083.3   277.6
#Mann= 8 ,-1 , 0
  3502.8      .1       0  3842.1     .05       0  3868.7      .1       0
  4103.1     .05       0  4430.3      .1       0    4995     .07       0
    5001      .1       0  5911.2     .08       0
Bank Sta=4755.8,5061.2
XS Rating Curve= 0 ,0
Exp/Cntr=0.3,0.1

Type RM Length L Ch R = 1 ,20165   ,463,463,463
BEGIN DESCRIPTION:
ELM CREEK 37.0
END DESCRIPTION:
XS GIS Cut Line= 3
       2236387.7     13241696.83      2235487.72     13240496.85
       2234487.7     13239496.84
#Sta/Elev= 30
  3506.9   300.9  3728.7  291.58  3806.9  289.72  3870.4  286.27  3899.6  286.68
  3943.4  284.69  4149.4  278.73  4314.2  274.19  4649.6  270.51  4878.7  265.37
  4928.7  264.72  4970.4  266.64  4978.7     266  4993.3  259.52  4996.6  256.88
  4999.3  256.38  5002.6  256.88  5010.4  257.13    5021  260.29  5063.4   264.3
  5077.6  267.29  5261.4  264.91  5346.3  265.54  5530.1  269.21  5869.5   272.4
  5948.7  274.67  6039.2  276.96  6053.4  279.12  6118.9  281.97  6421.1  295.29
#Mann= 7 ,-1 , 0
  3506.9      .1       0  3943.4     .05       0  4149.4      .1       0
  4996.6     .07       0  5002.6      .1       0  5948.7     .08       0
  6118.9      .1       0
Bank Sta=4878.7,5346.3
XS Rating Curve= 0 ,0
Exp/Cntr=0.3,0.1

Type RM Length L Ch R = 1 ,19702   ,483,483,483
BEGIN DESCRIPTION:
ELM CREEK 36.0
END DESCRIPTION:
XS GIS Cut Line= 3
      2236387.72     13241496.86      2235887.72     13240296.85
      2234687.69     13239096.82
#Sta/Elev= 30
  3729.2  292.57  3844.6  288.03    3850  288.57  4027.7  281.99  4084.5   280.7
    4307   274.4    4715  268.44  4920.9  266.61  4953.4  265.26  4961.5  263.28
  4985.3  260.79  4993.7  256.59  4996.5  256.09  4999.7  256.59  5014.4  258.27
  5026.5   260.9  5085.8  263.59  5142.3  265.16  5190.3     265  5340.3  262.51
  5453.5   264.3  5594.9  267.47  5863.6  270.64  6025.2  273.82  6146.4  277.34
  6188.9  279.95    6201  279.38    6223  279.81  6443.4   285.4  6726.3  296.93
#Mann= 10 ,-1 , 0
  3729.2      .1       0  4084.5     .05       0    4307      .1       0
  4993.7     .07       0  4999.7      .1       0  5014.4     .08       0
  5190.3      .1       0  6025.2     .05       0    6201     .08       0
    6223      .1       0
Bank Sta=4953.4,5453.5
XS Rating Curve= 0 ,0
Exp/Cntr=0.3,0.1

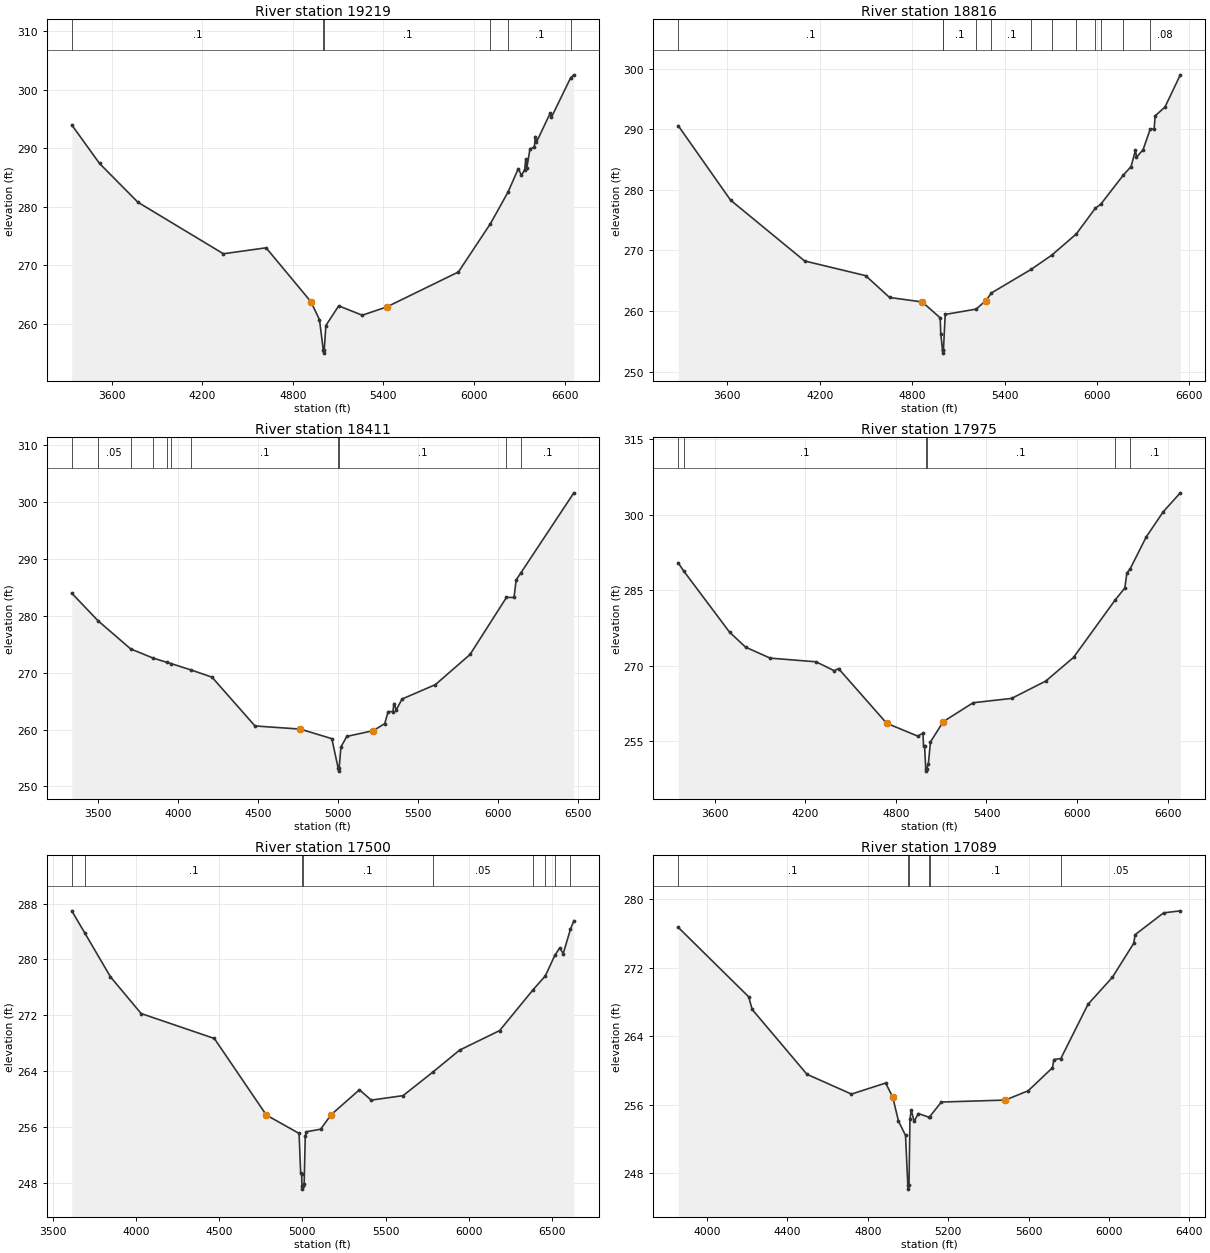
Type RM Length L Ch R = 1 ,19219   ,403,403,403
BEGIN DESCRIPTION:
ELM CREEK 35.0
END DESCRIPTION:
XS GIS Cut Line= 3
      2237387.74     13241146.88      2236187.72     13239946.85
       2235087.7     13238746.83
#Sta/Elev= 30
  3336.3  294.01  3520.2  287.42  3774.7  280.79  4340.4  271.99  4623.3  273.01
  4920.3  263.79  4976.8  260.72  5002.1  255.51  5004.9  255.01  5008.1  255.51
  5019.2  259.73    5104  263.09    5260  261.49  5422.8  262.91    5897  268.88
  6108.7  277.13  6225.9  282.56  6293.5  286.54  6314.4  285.38  6335.7  286.38
  6342.8  288.14  6349.6  286.63  6371.1  289.94  6399.5  290.17  6406.3  292.03
  6413.7  291.06  6505.6  296.07  6512.4  295.29  6639.4  302.03  6661.3  302.57
#Mann= 6 ,-1 , 0
  3336.3      .1       0  5002.1     .07       0  5008.1      .1       0
  6108.7     .08       0  6225.9      .1       0  6639.4     .08       0
Bank Sta=4920.3,5422.8
XS Rating Curve= 0 ,0
Exp/Cntr=0.3,0.1

Type RM Length L Ch R = 1 ,18816   ,405,405,405
BEGIN DESCRIPTION:
ELM CREEK 34.0
END DESCRIPTION:
XS GIS Cut Line= 3
      2237637.73     13240846.86      2236437.72     13239646.85
      2235237.73     13238646.86
#Sta/Elev= 30
  3281.5  290.57  3620.9   278.3  4101.8  268.26  4497.7  265.84  4653.3  262.24
  4865.4   261.5  4981.8  258.88  4985.7  256.26    4997  253.56  4999.8  253.06
    5003  253.56  5014.4  259.44    5215  260.32  5277.3  261.68  5314.8  262.99
  5572.8  266.88  5707.3  269.24  5865.6  272.72  5988.3  276.94  6025.6  277.66
  6168.7  282.36    6221  283.84  6249.7  286.54  6256.2  285.38  6299.1  286.62
  6345.8  290.05  6370.7  289.99  6377.3   292.2    6441  293.64  6540.6  298.96
#Mann= 12 ,-1 , 0
  3281.5      .1       0    4997     .07       0    5003      .1       0
    5215     .05       0  5314.8      .1       0  5572.8     .05       0
  5707.3      .1       0  5865.6     .05       0  5988.3      .1       0
  6025.6     .08       0  6168.7      .1       0  6345.8     .08       0
Bank Sta=4865.4,5277.3
XS Rating Curve= 0 ,0
Exp/Cntr=0.3,0.1

Type RM Length L Ch R = 1 ,18411   ,436,436,436
BEGIN DESCRIPTION:
ELM CREEK 33.0
END DESCRIPTION:
XS GIS Cut Line= 3
      2237887.69     13240546.83      2236687.72     13239346.85
      2235887.74     13238146.89
#Sta/Elev= 30
  3333.8  284.01  3496.6  279.19  3701.9   274.2    3843  272.58  3926.5  271.85
  3954.4  271.62  4078.1  270.51  4210.6  269.23  4479.3  260.64  4762.1  260.09
  4960.1   258.4  4999.5  253.19  5002.3  252.69  5005.5  253.19  5016.7  256.94
  5053.4   258.8  5218.6  259.81  5290.7  261.05  5311.7  263.17  5341.8  263.15
  5347.8  264.59  5362.8  263.48  5398.9  265.38  5607.7  267.92    5824  273.22
  6051.9  283.27    6099  283.25  6112.5  286.36    6141  287.55    6473  301.67
#Mann= 11 ,-1 , 0
  3333.8      .1       0  3496.6     .05       0  3701.9      .1       0
    3843     .05       0  3926.5      .1       0  3954.4     .05       0
  4078.1      .1       0  4999.5     .07       0  5005.5      .1       0
  6051.9     .08       0    6141      .1       0
Bank Sta=4762.1,5218.6
XS Rating Curve= 0 ,0
Exp/Cntr=0.3,0.1

Type RM Length L Ch R = 1 ,17975   ,475,475,475
BEGIN DESCRIPTION:
ELM CREEK 32.0
END DESCRIPTION:
XS GIS Cut Line= 3
      2238237.74     13240496.88      2237137.72     13239296.85
       2235937.7     13238096.83
#Sta/Elev= 30
  3358.8   290.4  3396.2  288.75  3698.3  276.65    3805  273.65  3967.7  271.47
  4271.7  270.74    4392  268.96  4420.3  269.39  4739.1  258.52  4944.5  255.97
  4979.6  256.54  4983.3  254.02  4990.2  254.02  4997.9   249.5  5000.6     249
  5003.9   249.5    5015  250.35  5029.1   254.8    5114  258.84    5312   262.6
  5566.5  263.46  5792.8  266.91  5976.7  271.61    6252  283.02  6316.1   285.4
  6330.2  288.41  6351.4  289.21  6457.5  295.54  6570.6  300.57  6683.8  304.34
#Mann= 6 ,-1 , 0
  3358.8     .05       0  3396.2      .1       0  4997.9     .07       0
  5003.9      .1       0    6252     .08       0  6351.4      .1       0
Bank Sta=4739.1,5114
XS Rating Curve= 0 ,0
Exp/Cntr=0.3,0.1

Type RM Length L Ch R = 1 ,17500   ,411,411,411
BEGIN DESCRIPTION:
ELM CREEK 31.0
END DESCRIPTION:
XS GIS Cut Line= 3
       2238287.7     13240396.82      2237587.72     13239196.85
      2236387.71     13238096.84
#Sta/Elev= 30
  3614.6  286.98  3693.1  283.79  3847.3  277.51  4031.3  272.25  4471.3  268.67
  4783.8  257.69  4980.6  255.05  4990.2  249.32  4995.9  249.24  4997.9  247.56
  5000.7  247.06  5003.9  247.56  5010.9  247.74  5017.7   254.7  5025.1  255.29
  5110.2  255.66  5173.7  257.75  5343.2  261.31  5414.2  259.83  5605.3  260.47
    5784  263.84  5945.1     267  6185.6   269.8  6387.8  275.69  6460.2  277.64
  6517.4  280.59  6546.9  281.67  6567.9  280.84  6611.4  284.35  6631.7  285.56
#Mann= 9 ,-1 , 0
  3614.6     .05       0  3693.1      .1       0  4997.9     .07       0
  5003.9      .1       0    5784     .05       0  6387.8      .1       0
  6460.2     .05       0  6517.4     .08       0  6611.4      .1       0
Bank Sta=4783.8,5173.7
XS Rating Curve= 0 ,0
Exp/Cntr=0.3,0.1

Type RM Length L Ch R = 1 ,17089   ,296,296,296
BEGIN DESCRIPTION:
ELM CREEK 30.0
END DESCRIPTION:
XS GIS Cut Line= 3
      2238492.22     13239937.29      2238224.25     13239332.19
      2237035.71     13237931.87
#Sta/Elev= 30
  3856.5  276.73    4207  268.62  4224.5  267.14  4497.1  259.57  4718.5  257.26
  4888.8  258.55  4923.9   256.9  4952.5  254.11  4987.6  252.43  4998.9  246.66
  5001.6  246.16  5004.9  246.66  5009.6  254.34  5016.2   255.4  5030.4  254.06
  5051.3  254.99  5102.5  254.57  5108.3  254.63  5165.6  256.33  5484.1  256.56
  5598.3  257.65  5718.9  260.34  5725.7  261.29  5760.4  261.41    5896  267.76
  6016.8  270.89  6123.4  274.88  6129.9  275.87  6271.6  278.42    6355  278.66
#Mann= 6 ,-1 , 0
  3856.5      .1       0  4998.9     .07       0  5004.9      .1       0
  5102.5     .05       0  5108.3      .1       0  5760.4     .05       0
Bank Sta=4923.9,5484.1
XS Rating Curve= 0 ,0
Exp/Cntr=0.3,0.1

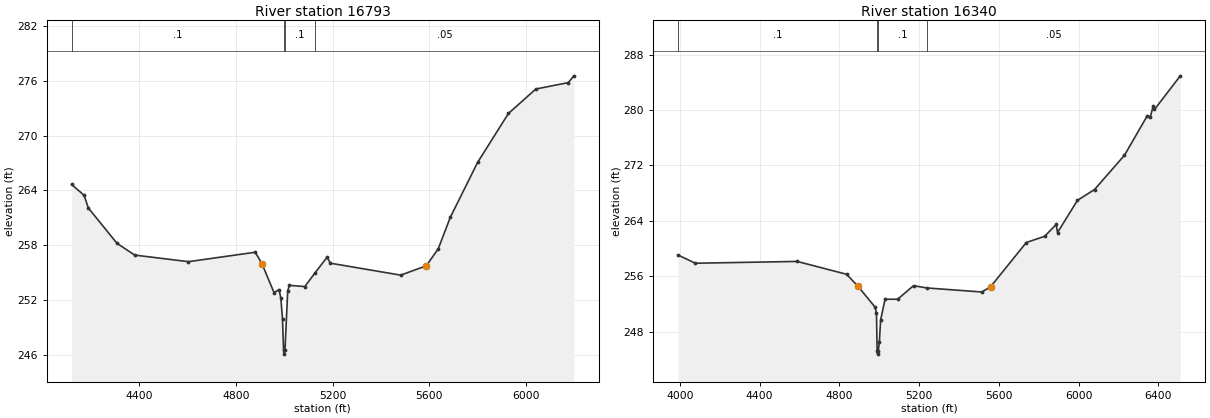
Type RM Length L Ch R = 1 ,16793   ,453,453,453
BEGIN DESCRIPTION:
ELM CREEK 29.0
END DESCRIPTION:
XS GIS Cut Line= 3
      2238613.23     13239466.18      2238531.11     13239193.89
      2237308.01     13237884.34
#Sta/Elev= 30
  4121.1  264.65  4172.6  263.47  4190.2  262.08  4308.4  258.23  4381.5  256.94
  4604.1  256.22  4880.1  257.25  4907.9     256  4957.7  252.85  4978.7  253.17
  4986.1  252.22  4992.9  249.95  4997.2  246.62    5000  246.12  5003.2  246.62
  5014.4  253.03  5021.2  253.63  5085.2   253.5  5127.8  255.01  5177.1   256.7
  5191.3  256.05  5481.4  254.75  5587.4  255.77  5636.8  257.63  5686.6  261.06
  5799.5  267.06    5927  272.41  6040.3  275.08  6174.6  275.78  6197.4  276.52
#Mann= 4 ,-1 , 0
  4121.1      .1       0  4997.2     .07       0  5003.2      .1       0
  5127.8     .05       0
Bank Sta=4907.9,5587.4
XS Rating Curve= 0 ,0
Exp/Cntr=0.3,0.1

Type RM Length L Ch R = 1 ,16340   ,264,264,264
BEGIN DESCRIPTION:
Mapping XS 4fe01abc
END DESCRIPTION:
XS GIS Cut Line= 3
      2238683.79     13239282.97      2238716.34     13238642.75
      2237208.06      13237525.1
#Sta/Elev= 30
  3991.6  259.07  4077.8  257.89  4588.5  258.15    4836   256.3  4892.3  254.61
  4979.4  251.55  4986.3  250.71  4989.5  245.27  4992.2  244.77  4995.5  245.27
  5000.9  246.55  5007.1   249.7  5029.2  252.69  5092.7   252.7    5172  254.65
  5239.4  254.32  5514.6  253.74  5558.1  254.48  5737.6  260.88  5829.3  261.77
  5887.8  263.49  5894.1  262.31  5994.2  266.97  6079.8  268.53    6230  273.48
  6344.8   279.2  6359.5     279  6373.4  280.53  6380.3  280.08  6509.9  284.94
#Mann= 4 ,-1 , 0
  3991.6      .1       0  4989.5     .07       0  4995.5      .1       0
  5239.4     .05       0
Bank Sta=4892.3,5558.1
XS Rating Curve= 0 ,0
Exp/Cntr=0.3,0.1