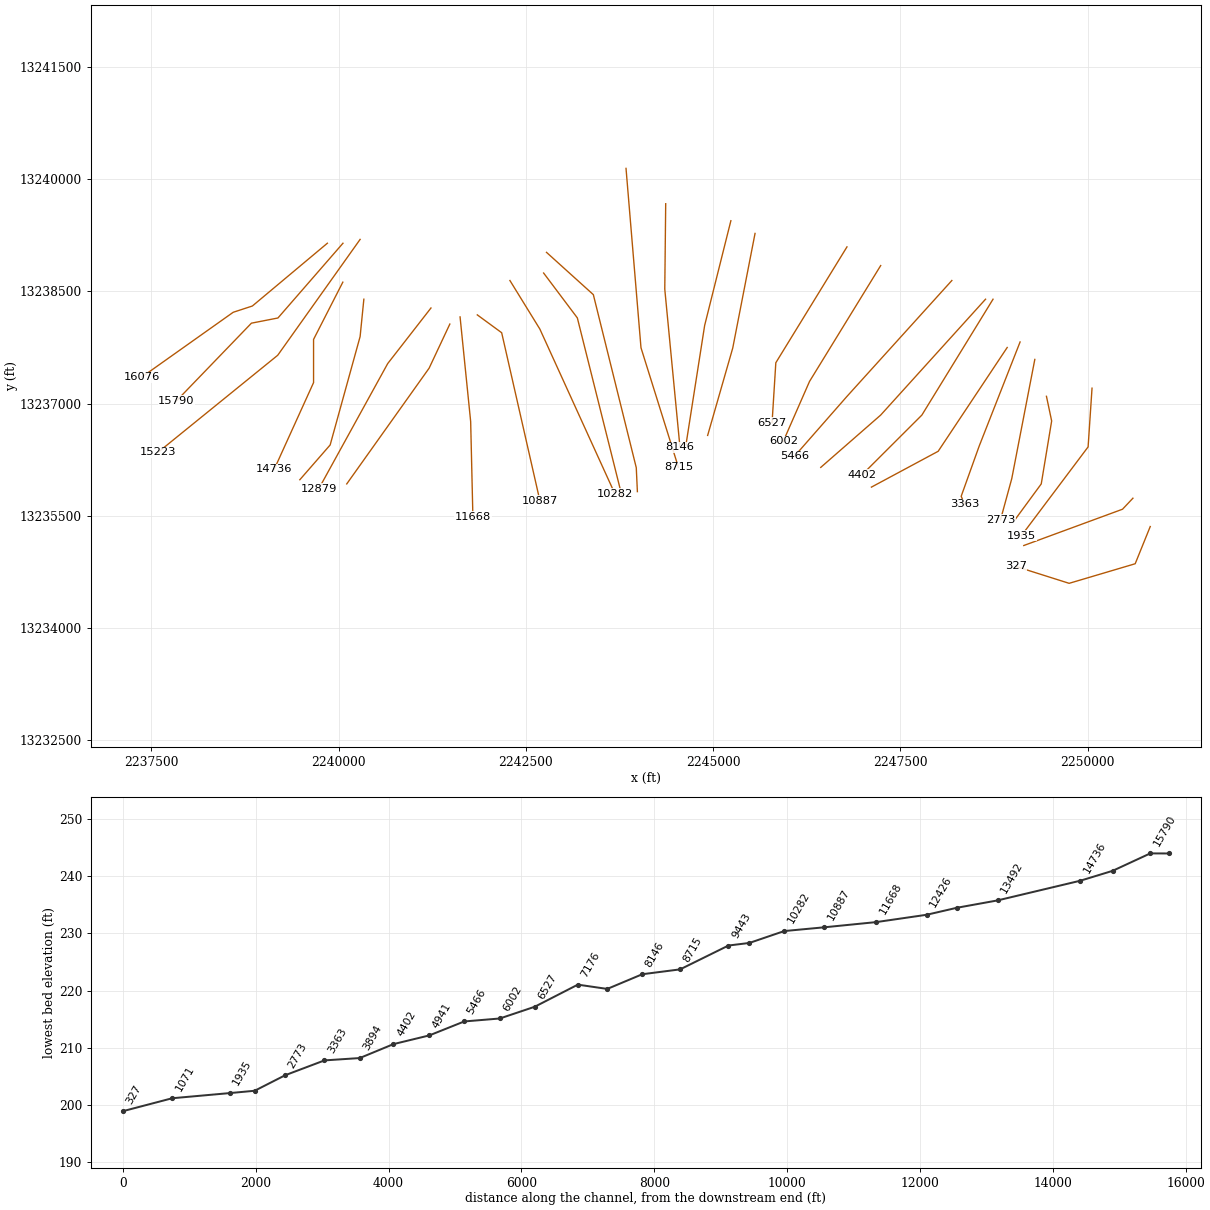
HEC-RAS study ELM CREEK.prj: ELM CREEK Base Level Engineering

--- ELM CREEK.g01 (geometry) --- (continued)

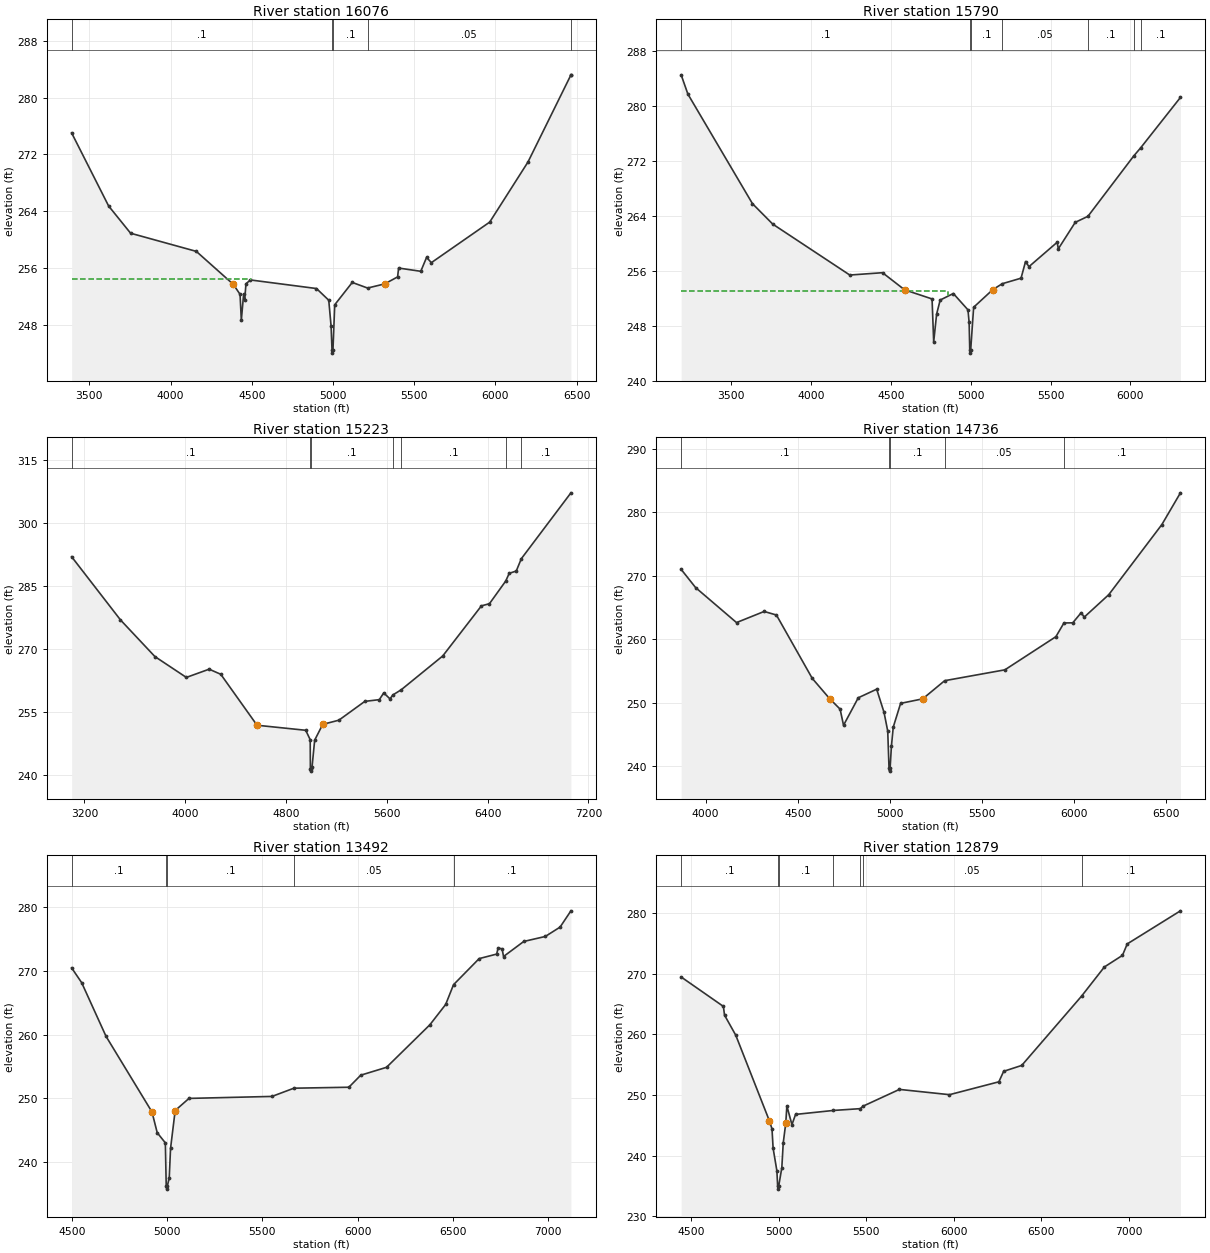
Type RM Length L Ch R = 1 ,16076   ,286,286,286
BEGIN DESCRIPTION:
Mapping XS 25e9e17d
END DESCRIPTION:
XS GIS Cut Line= 4
      2239850.49     13239145.59      2238849.28     13238305.77
      2238593.57     13238222.01        2237372.     13237354.41
#Sta/Elev= 30
  3391.2  275.04    3619  264.73  3754.3  260.89  4158.9  258.33  4386.6  253.68
  4428.2  252.27    4436  248.61  4450.3  252.33  4456.8  251.52  4464.6  253.76
    4492   254.3  4898.8  253.09  4974.3  251.44  4988.6  247.82  4994.3  244.48
    4997  243.98  5000.3  244.48  5011.1   250.8    5119  253.95  5213.4  253.16
  5318.3  253.74  5398.2  254.73  5404.4  255.98  5540.9  255.52  5576.6  257.48
  5606.1  256.74  5965.3  262.46  6200.8  270.93    6465   283.2  6465.4  283.23
#Mann= 5 ,-1 , 0
  3391.2      .1       0  4994.3     .07       0  5000.3      .1       0
  5213.4     .05       0    6465     .08       0
#XS Ineff= 2 , 0
          4493.2   254.4
Permanent Ineff=
       F       F
Bank Sta=4386.6,5318.3
XS Rating Curve= 0 ,0
Exp/Cntr=0.3,0.1

Type RM Length L Ch R = 1 ,15790   ,567,567,567
BEGIN DESCRIPTION:
Mapping XS af4b92af
END DESCRIPTION:
XS GIS Cut Line= 4
      2240058.84      13239145.6      2239190.79     13238145.62
      2238836.63     13238076.17      2237835.81     13237036.78
#Sta/Elev= 30
  3185.9  284.51  3228.2   281.7  3632.7  265.75    3760  262.77  4242.4  255.36
  4447.5   255.7  4585.6  253.21  4757.8  251.88    4768  245.63  4786.4  249.68
  4808.7  251.72    4891  252.67  4982.8  250.29    4990  248.46  4993.9  244.49
  4996.7  243.99  4999.9  244.49  5018.3  250.67  5138.4  253.24    5198   254.1
  5315.2   254.9  5343.5  257.33  5364.8  256.58  5541.6  260.13  5548.8  259.18
  5654.8  263.03  5734.4  263.91  6020.7  272.68    6066  273.92  6313.9  281.22
#Mann= 7 ,-1 , 0
  3185.9      .1       0  4993.9     .07       0  4999.9      .1       0
    5198     .05       0  5734.4      .1       0  6020.7     .05       0
    6066      .1       0
#XS Ineff= 2 , 0
         4860.63  253.05
Permanent Ineff=
       F       F
Bank Sta=4585.6,5138.4
XS Rating Curve= 0 ,0
Exp/Cntr=0.3,0.1

Type RM Length L Ch R = 1 ,15223   ,487,487,487
BEGIN DESCRIPTION:
ELM CREEK 26.0
END DESCRIPTION:
XS GIS Cut Line= 3
       2240287.7     13239196.83      2239187.72     13237646.85
      2237587.71     13236346.84
#Sta/Elev= 30
    3099  291.96  3486.5  276.93  3759.6  268.21  4009.3  263.24  4190.2   265.2
  4282.4  263.99  4570.3  251.86  4956.6  250.66  4992.2  248.42  4993.6  241.44
  4996.3  240.94  4999.6  241.44  5006.8  241.93  5027.6  248.31  5091.6  252.07
  5219.4  253.06  5425.6  257.54  5540.5  257.95  5575.7  259.55  5625.3  258.14
  5648.2  259.07  5714.4   260.3    6044  268.35  6350.8  280.27  6414.7  280.79
    6544  286.19  6571.3  288.01  6627.3  288.56  6667.5  291.49  7061.2  307.17
#Mann= 7 ,-1 , 0
    3099      .1       0  4993.6     .07       0  4999.6      .1       0
  5648.2     .05       0  5714.4      .1       0    6544     .08       0
  6667.5      .1       0
Bank Sta=4570.3,5091.6
XS Rating Curve= 0 ,0
Exp/Cntr=0.3,0.1

Type RM Length L Ch R = 1 ,14736   ,1244,1244,1244
BEGIN DESCRIPTION:
ELM CREEK 25.0
END DESCRIPTION:
XS GIS Cut Line= 4
      2240056.86     13238624.71      2239666.22     13237859.05
      2239666.22     13237280.93      2239140.72     13236120.66
#Sta/Elev= 30
  3866.9  270.98  3945.4  268.11  4167.6   262.6  4317.6  264.35  4384.3  263.79
  4578.7  253.82  4673.3  250.62  4730.1  248.97  4748.7  246.43  4828.7  250.76
  4928.7  252.11  4968.7  248.46  4988.7  245.52  4995.7  239.71  4998.4  239.21
  5001.7  239.71  5008.7  243.11  5018.7  246.14  5058.7  249.88  5178.7  250.59
  5297.9  253.45    5625  255.16  5901.9  260.38  5945.6  262.54  5993.5  262.56
  6039.6  264.17  6055.5  263.45  6189.2     267  6477.3  278.03  6578.3  283.03
#Mann= 5 ,-1 , 0
  3866.9      .1       0  4995.7     .07       0  5001.7      .1       0
  5297.9     .05       0  5945.6      .1       0
Bank Sta=4673.3,5178.7
XS Rating Curve= 0 ,0
Exp/Cntr=0.3,0.1

Type RM Length L Ch R = 1 ,13492   ,613,613,613
BEGIN DESCRIPTION:
ELM CREEK 24.0
END DESCRIPTION:
XS GIS Cut Line= 4
      2240337.72     13238396.83      2240287.72     13237896.85
      2239887.72     13236446.85      2239482.92     13235981.65
#Sta/Elev= 30
  4497.7  270.45  4550.4  268.13  4678.6  259.71  4919.8  247.87  4947.4  244.61
  4990.1  243.02  4994.7  236.27  4997.4  235.77  5000.7  236.27  5010.5  237.53
  5017.4  242.15  5041.7  248.09  5114.3  249.99  5550.3   250.3  5665.5  251.59
  5954.2  251.74  6016.8  253.63    6152  254.86  6379.9  261.53  6462.8  264.71
  6504.1  267.81  6638.7   271.9  6730.8  272.61  6738.4  273.56  6759.3  273.43
  6766.9  272.23  6873.2  274.59  6986.2  275.37    7064  276.84    7121  279.39
#Mann= 5 ,-1 , 0
  4497.7      .1       0  4994.7     .07       0  5000.7      .1       0
  5665.5     .05       0  6504.1      .1       0
Bank Sta=4919.8,5041.7
XS Rating Curve= 0 ,0
Exp/Cntr=0.3,0.1

Type RM Length L Ch R = 1 ,12879   ,453,453,453
BEGIN DESCRIPTION:
ELM CREEK 23.0
END DESCRIPTION:
XS GIS Cut Line= 3
      2241233.72     13238279.25      2240656.16      13237535.8
      2239734.49     13235858.36
#Sta/Elev= 30
  4441.3  269.43    4683  264.58  4689.3  263.15  4753.6  259.84  4946.4   245.7
  4960.9   244.4  4967.2  241.22  4988.8   237.5  4993.2  234.98  4995.9  234.48
  4999.2  234.98    5017     238  5025.1  242.09  5039.5  245.33  5045.9  248.18
  5074.9   245.1  5095.7  246.79  5311.3  247.44  5466.2  247.74    5481  248.14
  5689.6  250.91  5975.9  250.04  6258.2  252.16  6285.7  253.89    6389  254.86
  6731.3  266.28  6861.7  271.08    6965  272.99  6992.5  274.88  7296.7  280.33
#Mann= 7 ,-1 , 0
  4441.3      .1       0  4993.2     .07       0  4999.2      .1       0
  5311.3     .05       0  5466.2      .1       0    5481     .05       0
  6731.3      .1       0
Bank Sta=4946.4,5039.5
XS Rating Curve= 0 ,0
Exp/Cntr=0.3,0.1

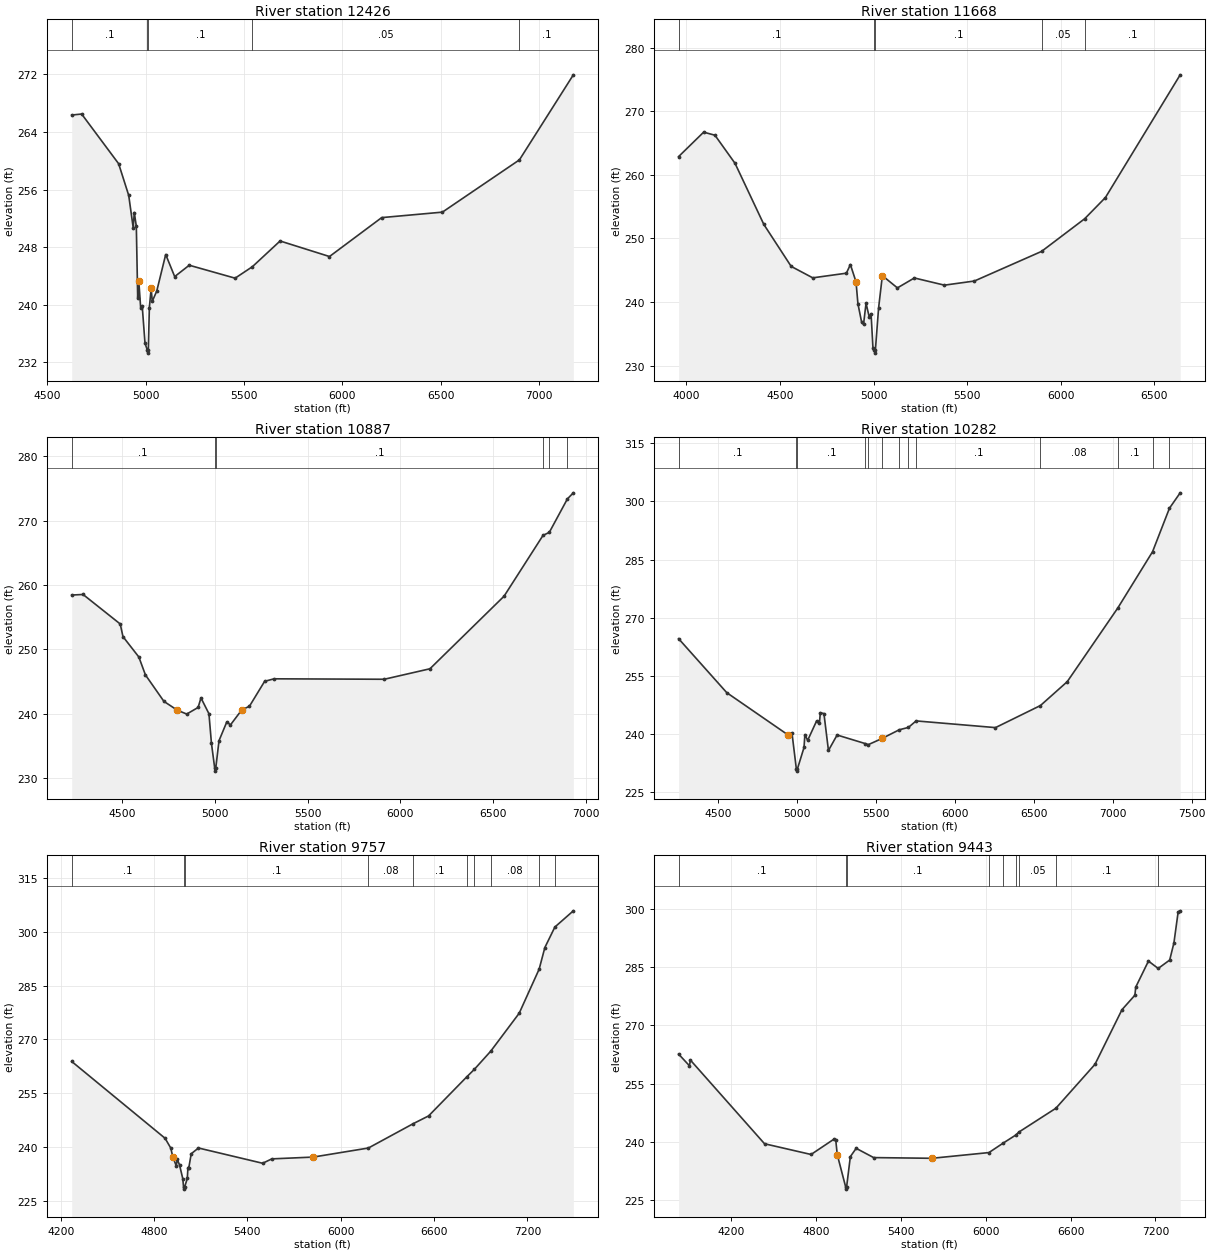
Type RM Length L Ch R = 1 ,12426   ,758,758,758
BEGIN DESCRIPTION:
ELM CREEK 22.0
END DESCRIPTION:
XS GIS Cut Line= 3
      2241485.67     13238064.21      2241209.17     13237474.35
      2240109.27     13235925.89
#Sta/Elev= 30
  4623.5  266.36  4673.9   266.5    4862  259.59  4913.2  255.19    4936   250.7
  4941.6  252.81  4951.9  250.88  4958.9  240.97  4964.4  243.31    4974  239.56
  4981.7  239.87  4996.1  234.62    5007  233.76  5009.8  233.26    5013  233.76
  5018.2   239.6  5027.3  242.25  5032.9  240.46  5055.7  241.88  5101.3  246.97
    5147   243.9    5221  245.48  5454.3  243.68  5541.9  245.27    5683  248.85
  5934.2  246.69  6199.6   252.1  6508.4  252.86  6900.2  260.13  7174.3  271.95
#Mann= 5 ,-1 , 0
  4623.5      .1       0    5007     .07       0    5013      .1       0
  5541.9     .05       0  6900.2      .1       0
Bank Sta=4964.4,5027.3
XS Rating Curve= 0 ,0
Exp/Cntr=0.3,0.1

Type RM Length L Ch R = 1 ,11668   ,781,781,781
BEGIN DESCRIPTION:
ELM CREEK 21.0
END DESCRIPTION:
XS GIS Cut Line= 3
      2241622.21     13238160.07      2241763.64     13236760.57
      2241793.42     13235487.55
#Sta/Elev= 30
  3958.5  262.86  4092.4   266.7  4152.7  266.22  4260.1   261.8    4414   252.2
    4560  245.61  4675.3  243.81    4855  244.54  4876.4   245.9  4906.5  243.18
  4916.6  239.75  4936.7   236.8  4946.7  236.52    4960  239.81  4976.9   237.7
  4986.9  238.18    4997  232.78    5004  232.48  5006.8  231.98    5010  232.48
  5027.1  239.08  5047.2  244.15  5127.6  242.23  5218.1  243.79  5378.8  242.66
  5538.9  243.31  5897.6  247.96    6128  253.09  6239.1  256.43  6638.5  275.71
#Mann= 5 ,-1 , 0
  3958.5      .1       0    5004     .07       0    5010      .1       0
  5897.6     .05       0    6128      .1       0
Bank Sta=4906.5,5047.2
XS Rating Curve= 0 ,0
Exp/Cntr=0.3,0.1

Type RM Length L Ch R = 1 ,10887   ,605,605,605
BEGIN DESCRIPTION:
ELM CREEK 20.0
END DESCRIPTION:
XS GIS Cut Line= 3
      2241852.18     13238187.03      2242177.71      13237948.3
      2242687.68     13235702.25
#Sta/Elev= 30
  4227.4  258.44  4288.5  258.53  4489.1  253.94  4503.8  251.98  4589.5  248.81
    4625  246.03  4724.9  241.91  4796.6  240.55  4847.9  239.94  4909.4  240.97
  4924.8  242.45  4967.8  239.99  4981.2  235.43  4998.7  231.57  5001.5  231.07
  5004.7  231.57  5022.2  235.81  5064.3  238.73  5083.8  238.25  5145.3   240.6
  5186.3  241.15  5268.3  245.03  5319.6  245.42  5913.8  245.35  6160.5  246.98
  6560.4  258.26  6770.8  267.72  6804.5  268.18  6902.3  273.39  6934.3  274.33
#Mann= 6 ,-1 , 0
  4227.4      .1       0  4998.7     .07       0  5004.7      .1       0
  6770.8     .08       0  6804.5     .05       0  6902.3      .1       0
Bank Sta=4796.6,5145.3
XS Rating Curve= 0 ,0
Exp/Cntr=0.3,0.1

Type RM Length L Ch R = 1 ,10282   ,525,525,525
BEGIN DESCRIPTION:
ELM CREEK 19.0
END DESCRIPTION:
XS GIS Cut Line= 3
      2242287.71     13238646.87      2242687.72     13237996.85
       2243687.7      13235796.9
#Sta/Elev= 30
  4247.9  264.59  4553.2  250.66  4939.6  239.81  4966.7  240.23  4994.6  230.91
  4997.3  230.41  5000.6  230.91    5043  236.51  5048.5  239.83  5066.1  238.35
  5123.2   243.4  5140.8  242.76  5146.2  245.49  5169.3  245.25  5197.9  235.74
  5252.8  239.73  5432.6   237.5    5451  237.25  5538.4  238.85  5539.6  238.88
  5646.7  241.08  5704.8  241.69  5753.7  243.37  6256.8  241.64  6541.9  247.34
  6711.6  253.49  7032.8  272.55  7252.5  287.03  7359.6  298.25  7427.7  302.23
#Mann= 13 ,-1 , 0
  4247.9      .1       0  4994.6     .07       0  5000.6      .1       0
  5432.6     .08       0    5451      .1       0  5539.6     .08       0
  5646.7      .1       0  5704.8     .08       0  5753.7      .1       0
  6541.9     .08       0  7032.8      .1       0  7252.5     .05       0
  7359.6      .1       0
Bank Sta=4939.6,5538.4
XS Rating Curve= 0 ,0
Exp/Cntr=0.3,0.1

Type RM Length L Ch R = 1 ,9757    ,314,314,314
BEGIN DESCRIPTION:
ELM CREEK 18.0
END DESCRIPTION:
XS GIS Cut Line= 3
      2242737.72     13238746.85      2243187.72     13238146.85
      2243787.73     13235746.82
#Sta/Elev= 30
  4271.3  263.86  4871.3  242.48  4907.8  239.75  4921.3  237.24  4943.2   234.8
  4949.4  236.66    4964  235.07  4984.8  231.27  4990.2  228.83  4992.9  228.33
  4996.2  228.83    5014   231.3  5018.2  234.34  5023.9  234.34  5039.3  238.18
  5085.7  239.78    5498  235.53  5557.3  236.75  5822.7  237.25  6177.7  239.77
  6466.9  246.57  6564.9  248.71  6810.4  259.59  6858.9  261.67  6964.3  266.73
  7147.3   277.3  7275.5  289.57  7312.2  295.59  7376.6  301.29  7495.2   305.8
#Mann= 10 ,-1 , 0
  4271.3      .1       0  4990.2     .07       0  4996.2      .1       0
  6177.7     .08       0  6466.9      .1       0  6810.4     .05       0
  6858.9      .1       0  6964.3     .08       0  7275.5     .05       0
  7376.6      .1       0
Bank Sta=4921.3,5822.7
XS Rating Curve= 0 ,0
Exp/Cntr=0.3,0.1

Type RM Length L Ch R = 1 ,9443    ,728,728,728
BEGIN DESCRIPTION:
ELM CREEK 17.0
END DESCRIPTION:
XS GIS Cut Line= 4
      2242776.11     13239023.63      2243401.41     13238457.88
      2243974.62     13236142.68      2243989.51     13235822.59
#Sta/Elev= 30
  3826.8  262.61  3903.6   259.6  3910.3  261.07  4434.8  239.55  4763.9  236.79
  4924.3  240.69    4939  240.41  4949.3  236.75  5009.3  228.38  5012.1  227.88
  5015.3  228.38    5042  236.24  5083.2  238.37  5206.8  235.99  5618.9  235.81
  6022.4  237.28  6123.4  239.72  6212.5  241.79  6233.7  242.54  6496.2  248.68
  6772.7  259.97  6963.7  274.02  7055.2  277.75    7061  279.82  7151.1  286.53
  7219.9  284.63  7301.3  286.79  7331.3  291.21  7361.3   299.2  7375.6  299.45
#Mann= 9 ,-1 , 0
  3826.8      .1       0  5009.3     .07       0  5015.3      .1       0
  6022.4     .16       0  6123.4     .08       0  6212.5      .1       0
  6233.7     .05       0  6496.2      .1       0  7219.9     .08       0
Bank Sta=4949.3,5618.9
XS Rating Curve= 0 ,0
Exp/Cntr=0.3,0.1

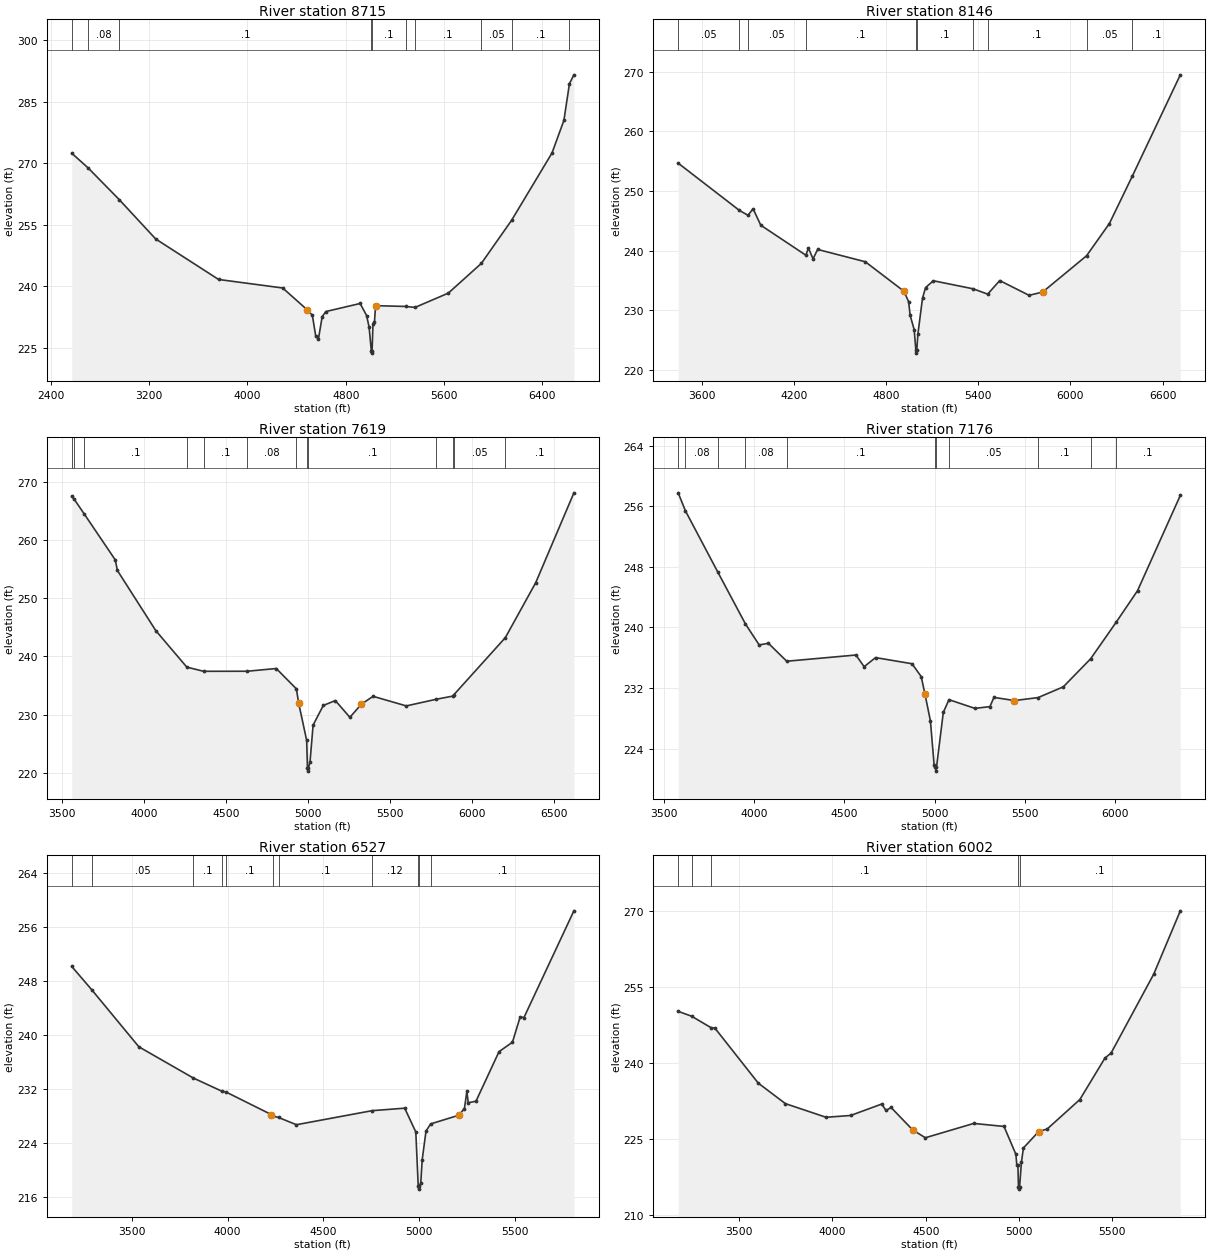
Type RM Length L Ch R = 1 ,8715    ,569,569,569
BEGIN DESCRIPTION:
ELM CREEK 16.0
END DESCRIPTION:
XS GIS Cut Line= 3
      2243837.72     13240146.86      2244037.72     13237746.85
      2244537.71     13236146.88
#Sta/Elev= 30
  2571.2  272.44  2704.7  268.85  2958.1  261.11  3253.6  251.55  3765.3  241.67
  4287.1  239.59  4487.8  234.23    4528  232.96  4555.6   227.9  4578.1  227.22
  4608.2  232.62  4638.3  233.85  4916.8  235.81  4969.5  232.88    4990  230.01
    5008  224.21  5010.7  223.71    5014  224.21  5021.4  230.82  5033.5  231.28
  5042.4  235.28  5286.7  235.09  5363.6  234.86  5633.8  238.33  5902.7  245.58
  6148.2  256.06  6477.7   272.5  6574.6  280.47  6619.7  289.42  6655.8  291.56
#Mann= 10 ,-1 , 0
  2571.2     .05       0  2704.7     .08       0  2958.1      .1       0
    5008     .07       0    5014      .1       0  5286.7     .08       0
  5363.6      .1       0  5902.7     .05       0  6148.2      .1       0
  6619.7     .05       0
Bank Sta=4487.8,5042.4
XS Rating Curve= 0 ,0
Exp/Cntr=0.3,0.1

Type RM Length L Ch R = 1 ,8146    ,527,527,527
BEGIN DESCRIPTION:
ELM CREEK 15.0
END DESCRIPTION:
XS GIS Cut Line= 3
      2244367.48     13239674.15      2244355.19     13238531.22
      2244557.95     13236417.52
#Sta/Elev= 30
  3448.2  254.67  3846.9  246.75  3902.4  245.94  3935.5  247.03  3985.5  244.28
  4278.6  239.26  4295.5  240.45  4325.5  238.65  4355.5  240.22  4665.5  238.16
    4917  233.22  4947.2  231.48  4957.2  229.17  4983.3  226.81  4994.4  223.36
  4997.2  222.86  5000.4  223.36  5007.5  226.03  5037.6  232.07  5057.7  233.84
  5107.9  234.98  5366.9  233.63  5461.5  232.74  5539.9  235.01  5730.8  232.54
  5819.1  233.09  6104.6  239.16  6253.2  244.56    6403  252.53  6714.6  269.46
#Mann= 10 ,-1 , 0
  3448.2     .05       0  3846.9      .1       0  3902.4     .05       0
  4278.6      .1       0  4994.4     .07       0  5000.4      .1       0
  5366.9     .08       0  5461.5      .1       0  6104.6     .05       0
    6403      .1       0
Bank Sta=4917,5819.1
XS Rating Curve= 0 ,0
Exp/Cntr=0.3,0.1

Type RM Length L Ch R = 1 ,7619    ,443,443,443
BEGIN DESCRIPTION:
ELM CREEK 14.0
END DESCRIPTION:
XS GIS Cut Line= 3
      2245237.71     13239446.82      2244887.72     13238046.85
      2244637.71     13236446.82
#Sta/Elev= 30
  3557.6  267.53  3571.6  267.06  3632.8  264.53    3823   256.6  3835.9  254.78
  4070.4  244.43  4259.2  238.17  4361.8  237.45    4628  237.46  4804.8  237.93
  4927.5  234.43  4941.4  231.98  4990.3  225.57  4995.1  220.79  4997.8  220.29
  5001.1  220.79  5010.8  221.93  5029.5  228.21  5091.7  231.58  5165.1  232.42
  5253.7  229.54  5324.5  231.81  5395.4  233.15  5597.8   231.5  5781.6  232.65
  5882.1  233.19  5886.3  233.37    6202  243.24  6387.3  252.69  6620.1  268.13
#Mann= 13 ,-1 , 0
  3557.6      .1       0  3571.6     .08       0  3632.8      .1       0
  4259.2     .08       0  4361.8      .1       0    4628     .08       0
  4927.5      .1       0  4995.1     .07       0  5001.1      .1       0
  5781.6     .05       0  5882.1      .1       0  5886.3     .05       0
    6202      .1       0
Bank Sta=4941.4,5324.5
XS Rating Curve= 0 ,0
Exp/Cntr=0.3,0.1

Type RM Length L Ch R = 1 ,7176    ,649,649,649
BEGIN DESCRIPTION:
ELM CREEK 13.0
END DESCRIPTION:
XS GIS Cut Line= 3
      2245560.27     13239276.76       2245262.5     13237743.22
      2244927.51     13236574.47
#Sta/Elev= 30
  3580.7  257.76  3620.5   255.4  3800.9  247.26  3953.1  240.45  4028.8  237.69
  4079.8  237.91  4181.2  235.54  4564.1  236.36  4609.5  234.82  4672.6  236.02
  4874.3  235.21  4925.3  233.51  4945.6  231.25  4976.2  227.67  4996.6  221.89
  5003.8  221.54  5006.5  221.04  5009.8  221.54  5047.5  228.79  5078.8  230.47
  5222.3  229.32  5305.5  229.55  5327.6  230.77  5440.8  230.35  5571.3  230.74
  5711.3  232.16  5862.8  235.87  6003.4  240.67  6122.1  244.85  6358.7  257.42
#Mann= 11 ,-1 , 0
  3580.7      .1       0  3620.5     .08       0  3800.9      .1       0
  3953.1     .08       0  4181.2      .1       0  5003.8     .07       0
  5009.8      .1       0  5078.8     .05       0  5571.3      .1       0
  5862.8     .05       0  6003.4      .1       0
Bank Sta=4945.6,5440.8
XS Rating Curve= 0 ,0
Exp/Cntr=0.3,0.1

Type RM Length L Ch R = 1 ,6527    ,525,525,525
BEGIN DESCRIPTION:
ELM CREEK 12.0
END DESCRIPTION:
XS GIS Cut Line= 3
      2246787.73     13239096.87      2245837.72     13237546.85
      2245787.72      13236746.9
#Sta/Elev= 30
  3187.1  250.15    3293  246.64  3537.1  238.25  3821.7  233.62  3969.6  231.68
  3992.7  231.54  4227.6  228.22  4235.6  228.01  4265.9  227.78  4359.1  226.71
  4753.7  228.79  4923.9  229.16  4981.9  225.63  4994.4  217.67  4997.1  217.17
  5000.4  217.67  5007.6  218.02  5015.1  221.52  5035.1  225.77  5059.2  226.83
  5205.5  228.11  5235.5   229.1  5248.1  231.63  5255.6  229.97  5295.7  230.19
  5415.9  237.53    5486  238.93  5526.1  242.66  5546.1  242.59  5806.6  258.39
#Mann= 11 ,-1 , 0
  3187.1      .1       0    3293     .05       0  3821.7      .1       0
  3969.6     .05       0  3992.7      .1       0  4235.6     .05       0
  4265.9      .1       0  4753.7     .12       0  4994.4     .07       0
  5000.4     .12       0  5059.2      .1       0
Bank Sta=4227.6,5205.5
XS Rating Curve= 0 ,0
Exp/Cntr=0.3,0.1

Type RM Length L Ch R = 1 ,6002    ,536,536,536
BEGIN DESCRIPTION:
ELM CREEK 11.0
END DESCRIPTION:
XS GIS Cut Line= 3
      2247237.71     13238846.84      2246287.72     13237296.85
       2245937.7     13236496.82
#Sta/Elev= 30
  3173.3  250.14  3245.3  249.18  3348.6  246.94  3370.5  246.82  3602.6     236
    3748  231.96  3966.2  229.27  4097.7  229.63  4264.1  231.88  4287.2  230.61
  4314.4   231.2  4430.4  226.78    4498  225.24  4757.3  228.06  4919.6  227.47
  4983.5  221.96  4988.3  219.82    4994  219.82  4997.2  215.62    5000  215.12
  5003.2  215.62  5013.1  220.44  5023.6  223.23  5104.7  226.43  5151.5  226.98
  5326.1  232.77  5460.6  240.94  5493.3  241.91  5722.2  257.48  5864.5  269.94
#Mann= 5 ,-1 , 0
  3173.3      .1       0  3245.3     .05       0  3348.6      .1       0
  4997.2     .07       0  5003.2      .1       0
Bank Sta=4430.4,5104.7
XS Rating Curve= 0 ,0
Exp/Cntr=0.3,0.1

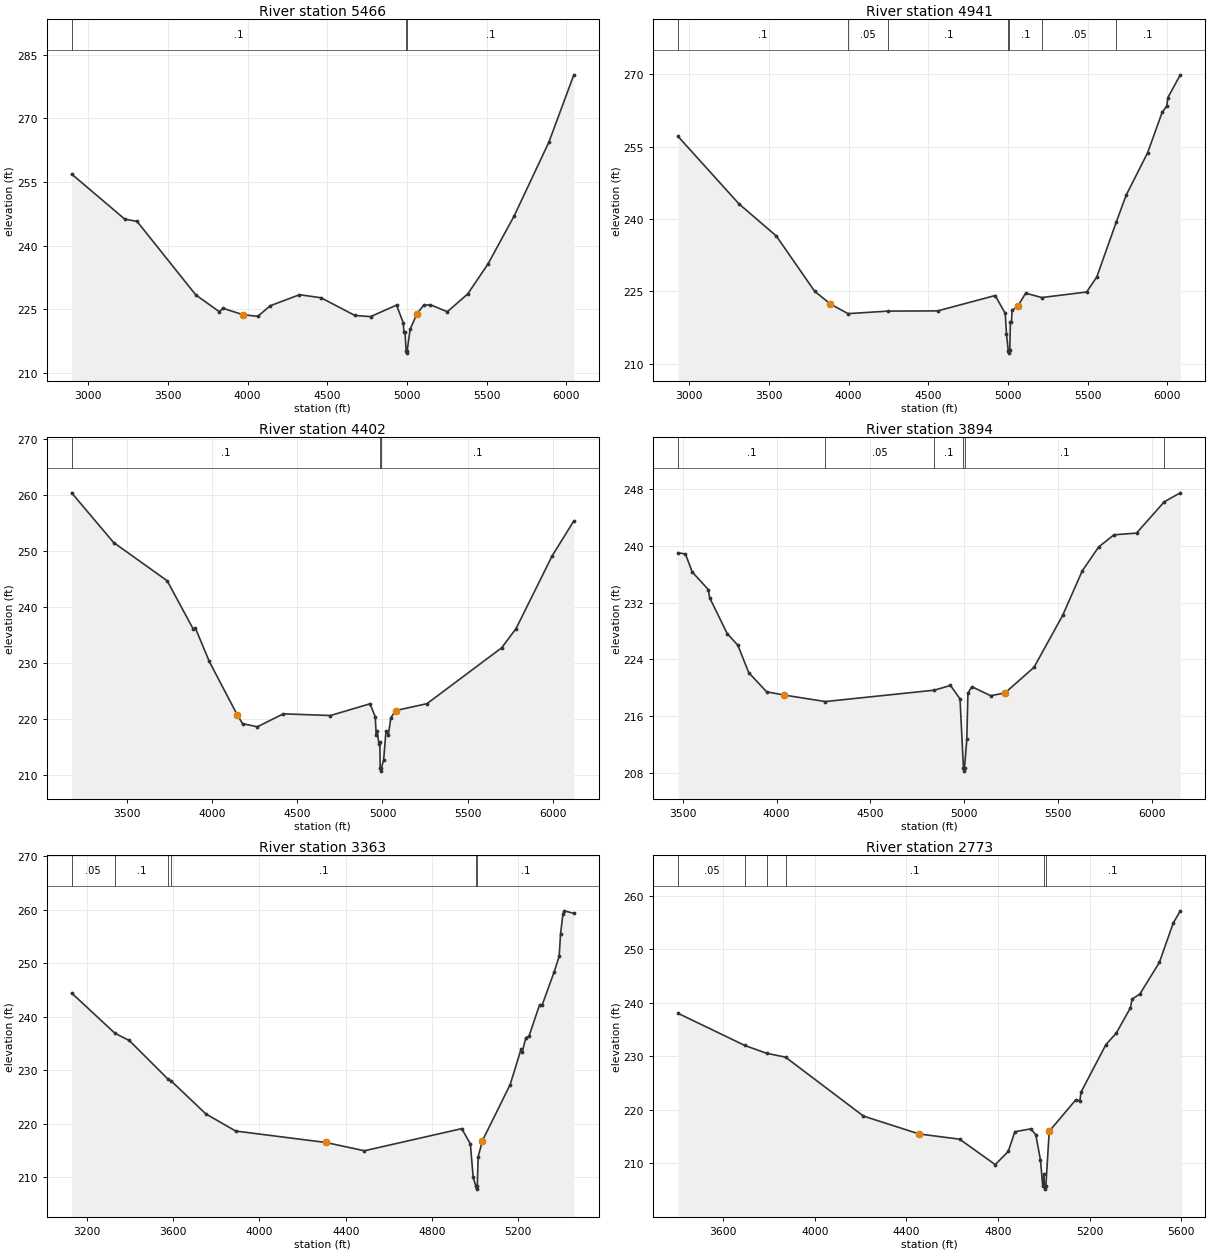
Type RM Length L Ch R = 1 ,5466    ,525,525,525
BEGIN DESCRIPTION:
ELM CREEK 10.0
END DESCRIPTION:
XS GIS Cut Line= 3
      2248187.73     13238646.86      2246787.72     13237096.85
      2246087.71     13236296.84
#Sta/Elev= 30
  2895.6  256.88  3228.5  246.25  3306.2   245.7  3674.6  228.35  3823.4  224.35
  3844.3   225.2  3972.1  223.66    4064  223.29  4141.7  225.78  4325.5  228.39
  4460.1  227.68    4673   223.5  4771.7  223.22  4934.6  225.94  4977.2   221.7
  4980.9  219.59  4987.6  219.59    4995   215.1  4997.8   214.6    5001   215.1
  5019.9  220.26  5062.6  223.87  5104.3   225.9    5147  226.03  5253.3  224.37
  5381.5  228.58  5508.7  235.67  5671.9  246.93  5891.2  264.46  6047.3  280.31
#Mann= 3 ,-1 , 0
  2895.6      .1       0    4995     .07       0    5001      .1       0
Bank Sta=3972.1,5062.6
XS Rating Curve= 0 ,0
Exp/Cntr=0.3,0.1

Type RM Length L Ch R = 1 ,4941    ,539,539,539
BEGIN DESCRIPTION:
ELM CREEK 9.0
END DESCRIPTION:
XS GIS Cut Line= 3
      2248637.73     13238396.87      2247237.72     13236846.85
      2246437.72     13236146.85
#Sta/Elev= 30
  2930.1   257.1  3312.4  243.11  3546.2  236.47  3786.9     225  3886.3  222.34
  3996.5  220.35  4249.3  220.88  4558.8  220.92  4919.8  224.11  4983.3   220.4
  4990.7   216.2  5001.9  212.66  5004.7  212.16  5007.9  212.66  5011.7  212.91
  5015.4  218.55  5022.1  218.55  5025.9  221.04    5061  221.86  5111.3   224.6
  5212.1  223.69  5493.8  224.84  5557.4  227.94  5679.1  239.27  5741.5  244.89
  5876.3   253.7  5968.4  262.15  5996.8  263.41  6003.5  265.15  6081.8  269.89
#Mann= 7 ,-1 , 0
  2930.1      .1       0  3996.5     .05       0  4249.3      .1       0
  5001.9     .07       0  5007.9      .1       0  5212.1     .05       0
  5679.1      .1       0
Bank Sta=3886.3,5061
XS Rating Curve= 0 ,0
Exp/Cntr=0.3,0.1

Type RM Length L Ch R = 1 ,4402    ,508,508,508
BEGIN DESCRIPTION:
ELM CREEK 8.0
END DESCRIPTION:
XS GIS Cut Line= 3
      2248737.72     13238396.85      2247787.72     13236846.85
      2246987.74     13236046.87
#Sta/Elev= 30
  3174.7  260.44    3421  251.55  3735.5  244.71  3888.3  236.09  3901.9   236.2
  3983.1  230.26  4148.2  220.65  4178.4  219.13  4265.5  218.58  4417.9  220.89
  4694.8  220.59  4926.9  222.69  4957.5  220.39  4963.6  217.03  4969.5  217.87
  4979.1  215.44  4984.9  215.88  4986.7  211.14  4989.5  210.64  4992.7  211.14
  5006.8  212.57  5020.9  217.86  5035.1  217.18  5049.2   220.2  5077.5  221.48
  5261.4  222.71  5699.8   232.7  5784.6  236.15  5996.7  249.16    6124  255.42
#Mann= 3 ,-1 , 0
  3174.7      .1       0  4986.7     .07       0  4992.7      .1       0
Bank Sta=4148.2,5077.5
XS Rating Curve= 0 ,0
Exp/Cntr=0.3,0.1

Type RM Length L Ch R = 1 ,3894    ,531,531,531
BEGIN DESCRIPTION:
ELM CREEK 7.0
END DESCRIPTION:
XS GIS Cut Line= 3
      2248926.72     13237750.84      2248005.05     13236362.19
      2247114.06      13235882.9
#Sta/Elev= 30
  3474.7  239.06  3513.8  238.87  3549.9  236.34  3635.5  233.86  3643.1  232.69
  3736.3  227.64  3793.4  225.98  3851.5  222.11  3946.8  219.41    4040  218.95
  4259.7  218.03  4841.6  219.64  4927.2  220.31  4978.3   218.4  4996.3   208.7
  4999.1   208.2  5002.3   208.7  5014.4  212.68  5020.4  219.22  5041.4  220.13
  5141.4  218.86  5217.8  219.24  5372.7  222.86  5526.1  230.23  5629.9  236.48
  5717.6  239.87  5799.5  241.59  5919.6  241.83  6067.8  246.26  6153.1  247.52
#Mann= 6 ,-1 , 0
  3474.7      .1       0  4259.7     .05       0  4841.6      .1       0
  4996.3     .07       0  5002.3      .1       0  6067.8     .05       0
Bank Sta=4040,5217.8
XS Rating Curve= 0 ,0
Exp/Cntr=0.3,0.1

Type RM Length L Ch R = 1 ,3363    ,590,590,590
BEGIN DESCRIPTION:
ELM CREEK 6.0
END DESCRIPTION:
XS GIS Cut Line= 4
      2249098.79     13237824.61      2248551.92     13236429.78
      2248312.28     13235760.02      2248360.88     13235650.68
#Sta/Elev= 30
  3128.9  244.45  3329.7  236.93  3396.2  235.58  3573.8  228.44  3590.4  228.02
  3751.5  221.85  3889.8  218.65    4308  216.51  4486.6  214.96  4938.2   219.1
  4978.2  216.24  4991.3  209.98  5004.2  208.29    5007  207.79  5010.2  208.29
  5014.2  213.81  5033.8  216.82  5162.8  227.34  5213.7  234.01    5219  233.47
  5235.6  236.11  5249.8  236.35  5299.3  242.27  5311.4  242.24  5366.7  248.39
    5390   251.3  5396.6  255.56  5407.6  259.23  5413.2  259.82  5458.1  259.35
#Mann= 6 ,-1 , 0
  3128.9     .05       0  3329.7      .1       0  3573.8     .05       0
  3590.4      .1       0  5004.2     .07       0  5010.2      .1       0
Bank Sta=4308,5033.8
XS Rating Curve= 0 ,0
Exp/Cntr=0.3,0.1

Type RM Length L Ch R = 1 ,2773    ,460,460,460
BEGIN DESCRIPTION:
ELM CREEK 5.0
END DESCRIPTION:
XS GIS Cut Line= 3
       2249295.4     13237591.07      2248987.72     13235996.85
      2248837.73     13235446.88
#Sta/Elev= 30
  3402.5  238.03  3693.6  232.04  3789.2  230.57  3871.7  229.85  4212.3  218.84
  4455.8   215.5  4632.2  214.53  4787.7  209.78  4844.7  212.24  4873.4  215.92
  4943.3  216.46    4965  215.35  4985.4  210.63  4995.1  205.81  5000.2  208.01
  5002.8   205.7  5005.5   205.2  5008.8   205.7  5023.6     216  5140.2  221.91
  5157.4  221.66  5162.6  223.32  5271.4   232.2  5316.4  234.34  5378.6  239.08
  5385.5  240.68    5420  241.67  5504.7  247.54  5565.1  254.88  5596.2  257.18
#Mann= 6 ,-1 , 0
  3402.5     .05       0  3693.6      .1       0  3789.2     .05       0
  3871.7      .1       0  5002.8     .07       0  5008.8      .1       0
Bank Sta=4455.8,5023.6
XS Rating Curve= 0 ,0
Exp/Cntr=0.3,0.1

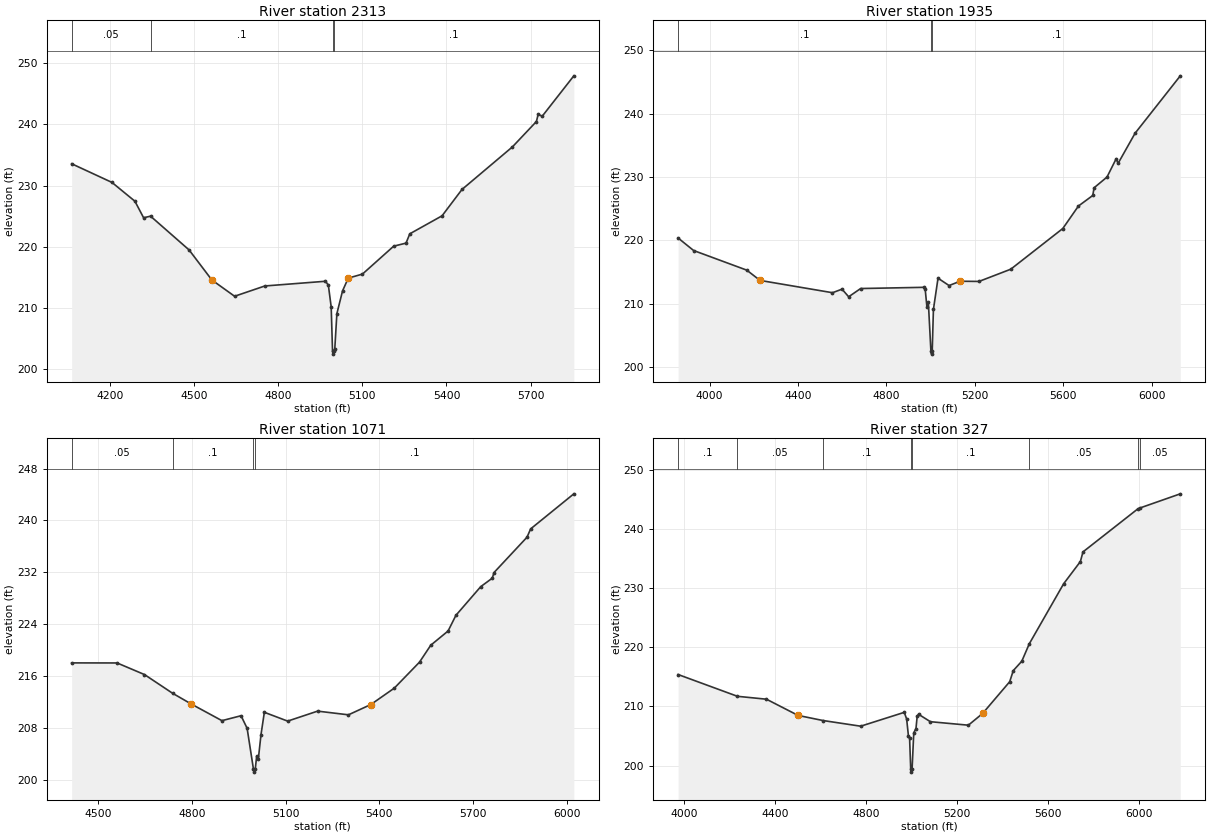
Type RM Length L Ch R = 1 ,2313    ,378,378,378
BEGIN DESCRIPTION:
ELM CREEK 4.0
END DESCRIPTION:
XS GIS Cut Line= 4
      2249450.83     13237097.67      2249520.27     13236767.83
      2249381.38     13235925.81      2249026.27     13235440.78
#Sta/Elev= 30
  4062.9  233.57  4206.8  230.52  4288.6  227.45  4319.6  224.75  4344.4  225.01
    4482  219.49  4563.1  214.59  4644.2  211.93  4752.1  213.61  4968.5  214.38
  4978.7  213.75  4988.8   210.2  4993.6  202.98  4996.4  202.48  4999.6  202.98
  5001.7  203.36  5009.1  209.09  5029.3   212.8  5049.6  214.89  5100.3  215.55
  5211.8  220.11  5255.8  220.61  5269.3  222.13  5384.4  225.07  5455.4  229.37
  5635.3  236.32    5721  240.47  5727.2  241.63  5741.8  241.34  5854.5  247.93
#Mann= 4 ,-1 , 0
  4062.9     .05       0  4344.4      .1       0  4993.6     .07       0
  4999.6      .1       0
Bank Sta=4563.1,5049.6
XS Rating Curve= 0 ,0
Exp/Cntr=0.3,0.1

Type RM Length L Ch R = 1 ,1935    ,864,864,864
BEGIN DESCRIPTION:
ELM CREEK 3.0
END DESCRIPTION:
XS GIS Cut Line= 3
       2250059.3     13237206.73      2250006.91     13236420.83
      2249116.24     13235233.27
#Sta/Elev= 30
  3857.2  220.39  3927.2  218.42  4167.8  215.32  4227.9   213.7  4555.6  211.76
  4598.7  212.32  4628.8  211.12  4683.1  212.42  4968.5  212.61  4974.8  212.41
  4983.1  209.44  4989.4  210.22  5000.9  202.57  5003.7  202.07  5006.9  202.57
  5012.3  209.12  5033.1  214.05  5083.1  212.89  5133.1  213.57  5218.5  213.54
  5362.3  215.47  5597.7  221.89  5668.5  225.44  5733.1   227.1  5739.4  228.32
  5797.7  230.01  5839.4  232.92  5847.7  232.16  5924.8  236.93  6129.3  245.98
#Mann= 3 ,-1 , 0
  3857.2      .1       0  5000.9     .07       0  5006.9      .1       0
Bank Sta=4227.9,5133.1
XS Rating Curve= 0 ,0
Exp/Cntr=0.3,0.1

Type RM Length L Ch R = 1 ,1071    ,744,744,744
BEGIN DESCRIPTION:
ELM CREEK 2.0
END DESCRIPTION:
XS GIS Cut Line= 3
      2250605.31     13235734.81      2250466.45     13235587.27
      2249147.99     13235101.52
#Sta/Elev= 30
  4414.8  218.02  4560.3  218.01    4648  216.22  4737.8  213.34  4797.2  211.69
  4895.9  209.11  4957.1  209.87  4976.6  207.92  4996.7  201.67  4999.5  201.17
  5002.7  201.67  5007.1  203.62  5012.4  203.18    5021  206.96  5031.7   210.4
  5106.3  209.04  5202.2  210.58  5300.9  210.01  5372.7   211.6  5447.8  214.13
  5528.5  218.14  5564.5  220.75  5619.9  222.94    5645  225.36  5724.4  229.78
  5761.4  231.09    5767  231.96  5872.6  237.41  5884.2  238.69  6022.5   244.1
#Mann= 4 ,-1 , 0
  4414.8     .05       0  4737.8      .1       0  4996.7     .07       0
  5002.7      .1       0
Bank Sta=4797.2,5372.7
XS Rating Curve= 0 ,0
Exp/Cntr=0.3,0.1

Type RM Length L Ch R = 1 ,327     ,0,0,0
BEGIN DESCRIPTION:
ELM CREEK 1.0
END DESCRIPTION:
XS GIS Cut Line= 4
      2250836.43     13235355.53       2250635.6     13234857.83
      2249753.69     13234595.88      2249039.32     13234822.39
#Sta/Elev= 30
  3975.5  215.39  4236.1  211.71  4363.6  211.22  4502.5  208.48  4611.7  207.62
  4777.5  206.66    4969     209  4979.4  207.88  4987.2  205.05  4992.4  204.63
  4997.3   199.4    5000   198.9  5003.3   199.4  5010.7  205.55  5020.4  206.25
  5025.6   208.3  5031.6  208.68  5083.7  207.42  5250.6  206.83  5313.2  208.81
  5432.2  214.18  5447.8  216.05  5485.3  217.64  5518.3  220.59  5669.2  230.73
  5742.7  234.48  5754.1  236.11  5993.7  243.34  6005.1  243.54  6181.6  245.92
#Mann= 8 ,-1 , 0
  3975.5      .1       0  4236.1     .05       0  4611.7      .1       0
  4997.3     .07       0  5003.3      .1       0  5518.3     .05       0
  5993.7      .1       0  6005.1     .05       0
Bank Sta=4502.5,5313.2
XS Rating Curve= 0 ,0
Exp/Cntr=0.3,0.1

Chan Stop Cuts=-1
Use User Specified Reach Order=0
Composite Channel Slope=5

--- ELM CREEK.g02 (geometry) ---

Geom Title=DUMMY
Program Version=4.10

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
River Reach=ELM CREEK       ,Reach-1