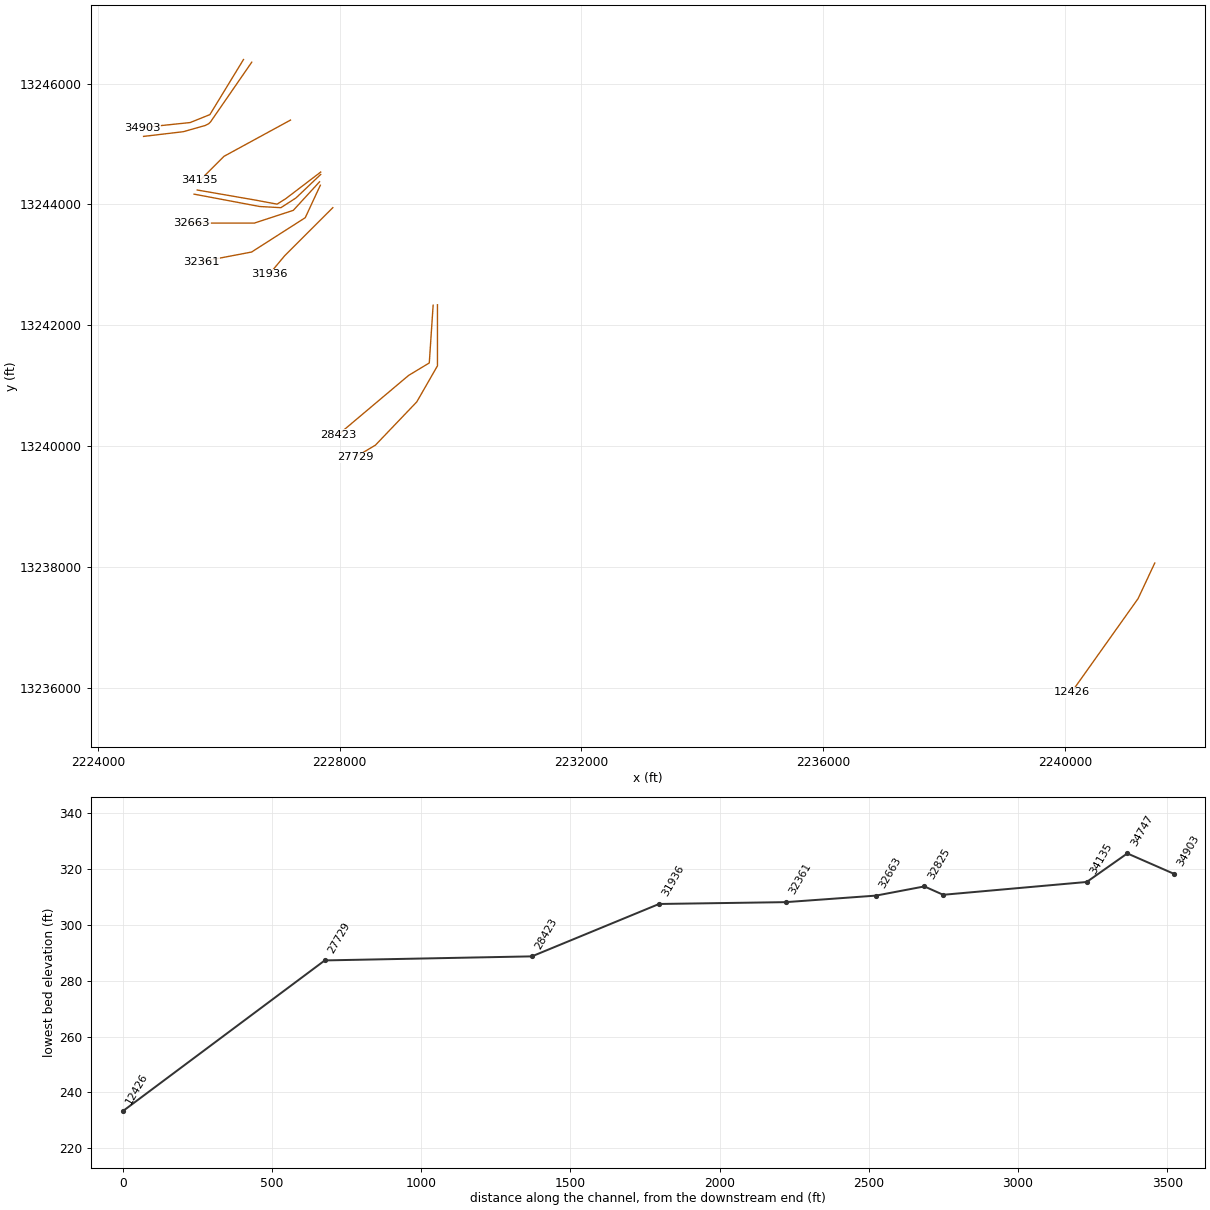
HEC-RAS study ELM CREEK.prj: ELM CREEK Base Level Engineering

--- ELM CREEK.g02 (geometry) --- (continued)

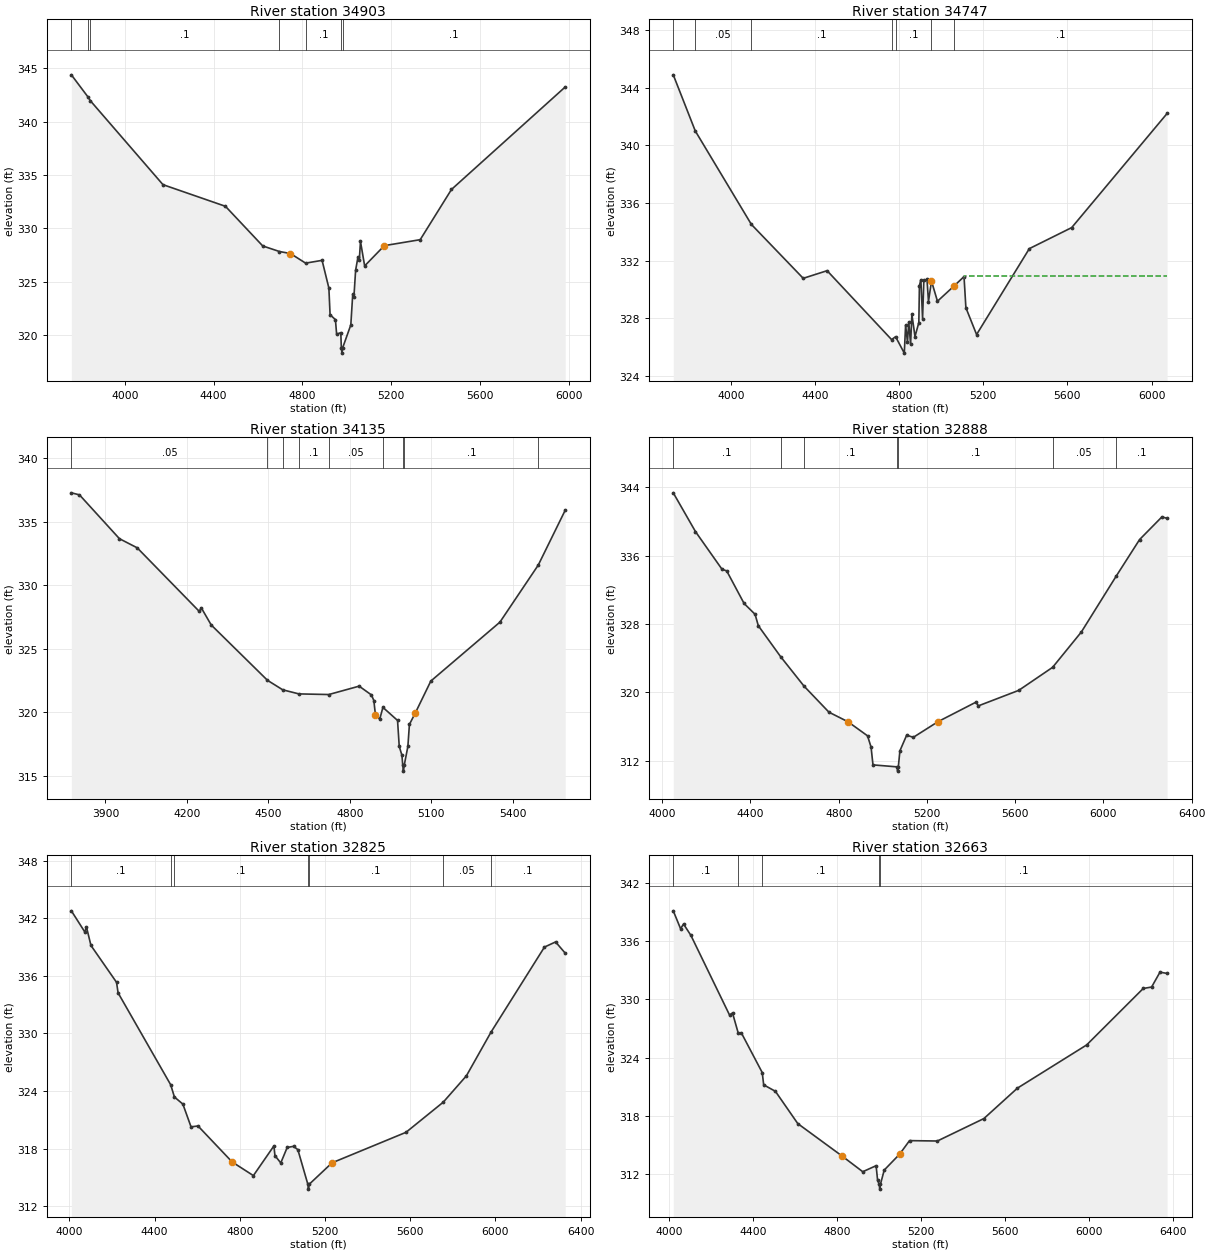
Type RM Length L Ch R = 1 ,34903   ,156,156,156
BEGIN DESCRIPTION:
ELM CREEK 63.0
END DESCRIPTION:
XS GIS Cut Line= 4
      2226410.37     13246399.34      2225854.51     13245487.52
      2225527.82     13245355.87      2224728.21     13245272.99
#Sta/Elev= 30
  3759.7  344.39    3834  342.33  3845.7  341.95  4172.2  334.09  4453.6  332.06
  4621.6  328.34  4696.8  327.82  4746.4  327.63  4814.6  326.73  4888.8  326.99
  4919.4  324.39  4924.8  321.89  4948.9  321.43  4954.3  320.06  4973.1  320.21
  4975.5  318.79  4978.2  318.29  4981.5  318.79  5018.2  320.94  5026.8   323.8
  5032.2  323.58  5039.8  326.06  5050.5  327.31  5056.4  327.01  5061.7  328.77
  5080.5  326.47  5169.2  328.37  5330.7  328.93  5471.5  333.64  5983.7  343.25
#Mann= 7 ,-1 , 0
  3759.7      .1       0    3834     .05       0  3845.7      .1       0
  4696.8     .05       0  4814.6      .1       0  4975.5     .07       0
  4981.5      .1       0
Bank Sta=4746.4,5169.2
XS Rating Curve= 0 ,0
Exp/Cntr=0.3,0.1

Type RM Length L Ch R = 1 ,34747   ,136,136,136
BEGIN DESCRIPTION:
Mapping XS 04637d09
END DESCRIPTION:
XS GIS Cut Line= 6
      2226546.88     13246355.43      2225863.53      13245364.8
      2225834.89     13245337.02       2225780.2     13245308.38
      2225415.67     13245204.72      2224757.38      13245126.7
#Sta/Elev= 30
  3726.9   344.9  3831.4  341.01  4098.2  334.52  4344.6  330.78  4458.1  331.31
  4764.6  326.53  4783.6  326.73    4825  325.59  4831.3  327.53  4840.1  326.36
  4846.2  327.75    4855  326.21    4861  328.28  4875.9  326.74  4894.1  327.71
  4896.9  330.28  4903.8  330.68  4911.9  327.99  4917.9  330.63    4933   330.7
    4940  329.17  4954.2  330.59  4982.7  329.19    5063  330.27  5108.9   330.9
  5117.8  328.74  5168.6  326.88  5419.3  332.84  5620.7   334.3  6074.2  342.22
#Mann= 7 ,-1 , 0
  3726.9      .1       0  3831.4     .05       0  4098.2      .1       0
  4764.6     .05       0  4783.6      .1       0  4954.2     .07       0
    5063      .1       0
#XS Ineff= 2 , 0
         4902.98  330.63 5109.45          330.91
Permanent Ineff=
       F       F
Bank Sta=4954.2,5063
XS Rating Curve= 0 ,0
Exp/Cntr=0.3,0.1

Type RM Length L Ch R = 1 ,34135   ,481,481,481
BEGIN DESCRIPTION:
ELM CREEK 61.0
END DESCRIPTION:
XS GIS Cut Line= 3
      2227187.69     13245396.84      2226087.72     13244796.85
      2225687.75     13244396.89
#Sta/Elev= 30
  3774.4  337.27  3804.3  337.11  3951.4  333.66  4016.9  332.94  4245.7  327.93
  4252.8  328.22  4289.3  326.87  4496.6  322.51  4552.9  321.76  4612.4  321.44
  4722.4  321.39  4834.2  322.05  4879.3  321.36  4888.3  320.92    4894  319.81
  4910.1  319.46  4921.7  320.38  4975.6  319.35  4981.8  317.31  4991.8   316.6
  4994.5  315.86  4997.2  315.36  5000.5  315.86  5013.6   317.3  5019.3  319.04
  5041.5  319.96  5098.1  322.45  5352.6  327.09  5493.7  331.58    5593   335.9
#Mann= 9 ,-1 , 0
  3774.4     .05       0  4496.6      .1       0  4552.9     .05       0
  4612.4      .1       0  4722.4     .05       0  4921.7      .1       0
  4994.5     .07       0  5000.5      .1       0  5493.7     .05       0
Bank Sta=4894,5041.5
XS Rating Curve= 0 ,0
Exp/Cntr=0.3,0.1

Type RM Length L Ch R = 1 ,32888   ,63,63,63
BEGIN DESCRIPTION:
Mapping XS 0be17355
END DESCRIPTION:
XS GIS Cut Line= 5
      2227687.88     13244536.73       2227112.5     13244097.88
      2226966.22     13244005.24      2226600.52      13244073.5
       2225644.8     13244239.29
#Sta/Elev= 30
  4049.9  343.34  4150.7   338.8  4271.3  334.38  4292.1  334.21    4371  330.39
  4420.9  329.12  4435.4  327.79  4536.2  324.18  4642.3  320.73  4755.6  317.67
  4842.6  316.54  4930.7   314.9  4946.7  313.57  4955.3   311.5  5064.2  311.27
    5067  310.77  5070.2  311.27  5077.4  313.15  5107.9  314.97  5138.4  314.73
  5250.2  316.56    5422  318.84  5433.2  318.41  5615.9  320.22  5769.7  322.92
  5900.1  327.06  6056.9  333.55  6163.9  337.87  6265.4  340.53  6288.7  340.35
#Mann= 7 ,-1 , 0
  4049.9      .1       0  4536.2     .05       0  4642.3      .1       0
  5064.2     .07       0  5070.2      .1       0  5769.7     .05       0
  6056.9      .1       0
Bank Sta=4842.6,5250.2
XS Rating Curve= 0 ,0
Exp/Cntr=0.3,0.1

Type RM Length L Ch R = 1 ,32825   ,162,162,162
BEGIN DESCRIPTION:
ELM CREEK 58.0
END DESCRIPTION:
XS GIS Cut Line= 5
      2227687.69     13244496.82      2227278.28     13244107.63
      2227029.61     13243946.73      2226678.54     13243966.23
      2225591.92     13244170.89
#Sta/Elev= 30
  4009.3  342.77    4073  340.55  4079.9  341.11  4101.3  339.16  4221.4  335.32
  4228.7  334.22  4475.7  324.64  4493.1  323.37  4532.8  322.63  4571.1  320.26
  4603.9  320.35  4764.2   316.6  4863.8  315.18  4960.1  318.27  4965.1  317.26
  4992.4   316.5  5022.5  318.11  5052.5  318.23  5072.6  317.88  5119.6  314.27
  5122.4  313.77  5125.6  314.27    5233  316.51  5580.3  319.69  5755.1  322.83
  5863.9  325.58  5979.4  330.13  6230.2  338.99  6282.5  339.53  6327.7  338.36
#Mann= 7 ,-1 , 0
  4009.3      .1       0  4475.7     .05       0  4493.1      .1       0
  5119.6     .07       0  5125.6      .1       0  5755.1     .05       0
  5979.4      .1       0
Bank Sta=4764.2,5233
XS Rating Curve= 0 ,0
Exp/Cntr=0.3,0.1

Type RM Length L Ch R = 1 ,32663   ,302,302,302
BEGIN DESCRIPTION:
Mapping XS a471c164
END DESCRIPTION:
XS GIS Cut Line= 4
      2227668.47     13244375.19      2227234.03     13243902.42
      2226588.75     13243691.58      2225553.77     13243691.58
#Sta/Elev= 30
  4018.1  339.11    4053  337.27  4067.2  337.75  4102.3  336.58  4286.6  328.39
  4300.8   328.6  4327.7  326.56  4342.8  326.56  4442.6  322.47  4449.4  321.21
  4505.5  320.54  4612.2  317.22  4821.2  313.92  4922.1  312.27  4985.8  312.89
  4992.9  311.39  5000.5  310.98  5003.2  310.48  5006.5  310.98  5024.5  312.44
  5098.1  314.08  5145.2  315.47    5278  315.43    5500  317.74    5660  320.87
    5990  325.31    6260  331.12    6300  331.27    6340   332.8    6374  332.67
#Mann= 5 ,-1 , 0
  4018.1      .1       0  4327.7     .05       0  4442.6      .1       0
  5000.5     .07       0  5006.5      .1       0
Bank Sta=4821.2,5098.1
XS Rating Curve= 0 ,0
Exp/Cntr=0.3,0.1

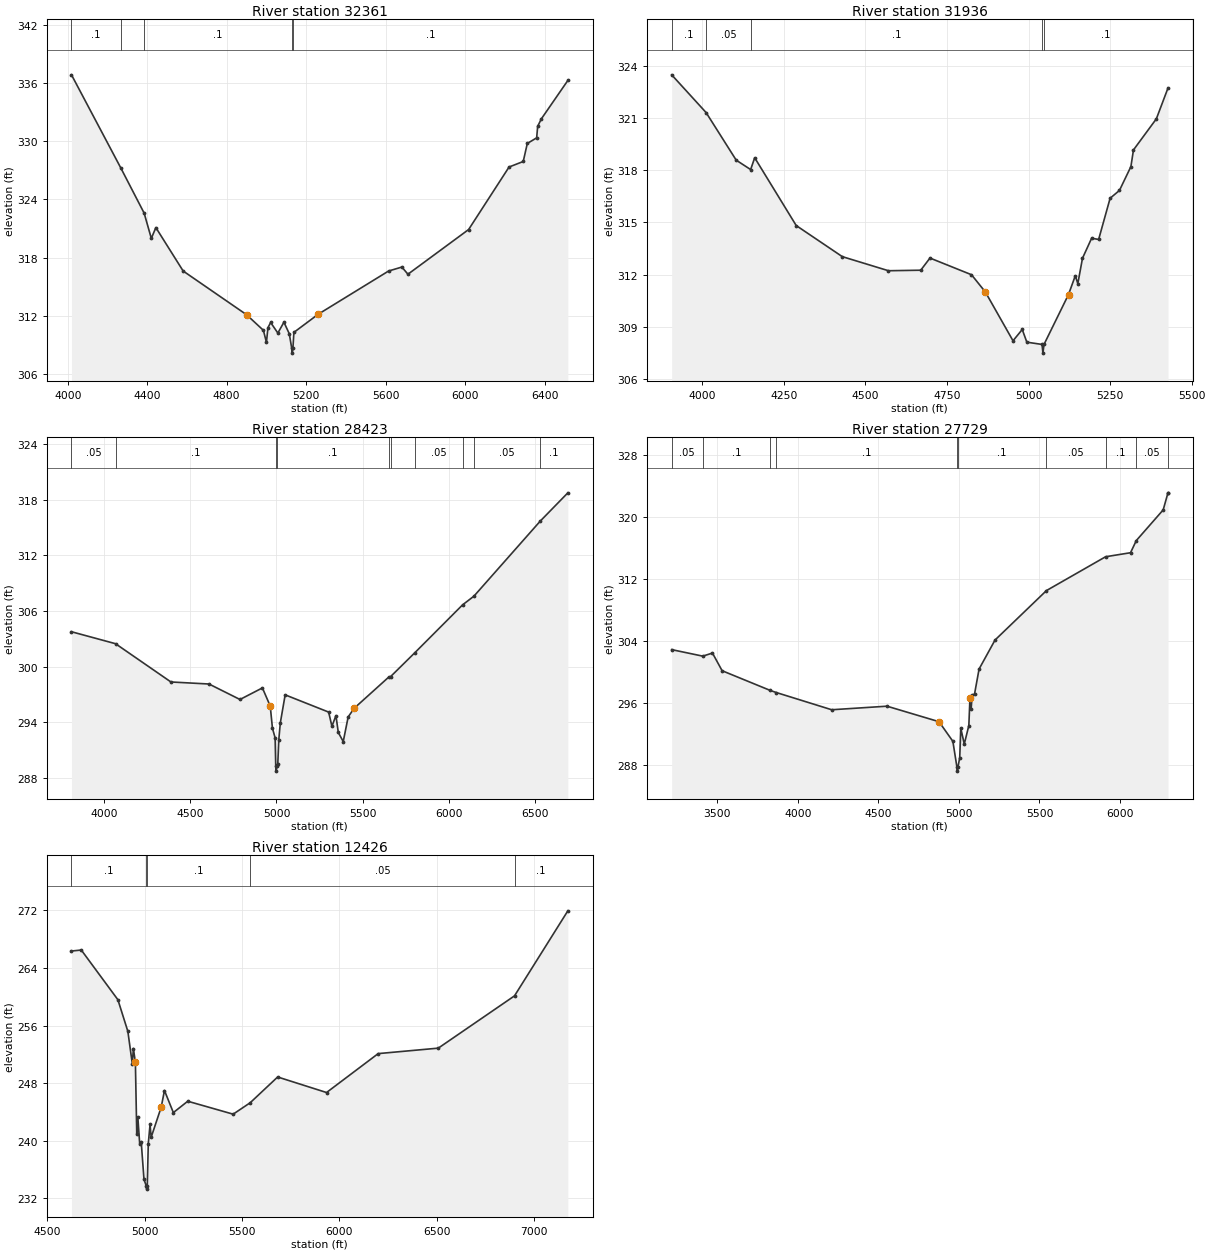
Type RM Length L Ch R = 1 ,32361   ,425,425,425
BEGIN DESCRIPTION:
ELM CREEK 57.0
END DESCRIPTION:
XS GIS Cut Line= 4
      2227681.27     13244317.74      2227432.08     13243781.03
      2226544.03     13243212.42      2225707.06     13243052.69
#Sta/Elev= 30
    4019  336.85  4267.8  327.22  4384.8  322.58  4420.8  319.98  4443.7  321.09
  4581.1  316.61  4900.4   312.1    4985  310.49  5000.2  309.25  5007.8  310.76
  5021.4   311.3  5057.7  310.21  5088.2  311.33  5115.2  310.14  5127.5  308.64
  5130.2  308.14  5133.5  308.64  5138.4  310.28  5260.7  312.15    5615  316.61
  5681.8  317.02  5712.4  316.28  6017.8  320.89  6221.4  327.34  6292.7  327.91
  6313.2  329.77  6360.3  330.35  6365.4  331.54  6384.3  332.32  6517.3  336.27
#Mann= 5 ,-1 , 0
    4019      .1       0  4267.8     .05       0  4384.8      .1       0
  5127.5     .07       0  5133.5      .1       0
Bank Sta=4900.4,5260.7
XS Rating Curve= 0 ,0
Exp/Cntr=0.3,0.1

Type RM Length L Ch R = 1 ,31936   ,426,426,426
BEGIN DESCRIPTION:
ELM CREEK 56.0
END DESCRIPTION:
XS GIS Cut Line= 3
      2227887.69     13243946.83      2227087.72     13243146.85
      2226837.75     13242846.89
#Sta/Elev= 30
  3905.8  323.49  4011.3  321.32  4103.7  318.58  4147.9  318.04  4160.3  318.72
  4287.6  314.82    4429  313.03  4570.4  312.22  4669.4  312.25  4697.7  312.95
    4825  311.99  4867.4     311  4952.3  308.19  4980.6  308.84  4994.7  308.11
  5041.3  307.98    5044  307.48  5047.3  307.98  5122.4  310.85  5143.2  311.93
    5151  311.48  5165.3  312.94  5193.3  314.09  5214.8  314.02    5250  316.39
  5278.6  316.84  5313.7  318.21  5321.6  319.17  5391.8  320.96  5427.6  322.74
#Mann= 5 ,-1 , 0
  3905.8      .1       0  4011.3     .05       0  4147.9      .1       0
  5041.3     .07       0  5047.3      .1       0
Bank Sta=4867.4,5122.4
XS Rating Curve= 0 ,0
Exp/Cntr=0.3,0.1

Type RM Length L Ch R = 1 ,28423   ,694,694,694
BEGIN DESCRIPTION:
ELM CREEK 49.0
END DESCRIPTION:
XS GIS Cut Line= 4
      2229547.53     13242331.89      2229483.84     13241376.45
      2229141.47     13241169.44      2227980.04     13240190.97
#Sta/Elev= 30
  3812.3  303.76  4067.5  302.47  4388.6  298.34  4609.1  298.12  4788.7  296.45
  4918.6   297.7    4964  295.74  4976.8  293.35  4992.3  292.31    4996  289.22
  4998.8  288.72    5002  289.22  5007.8  289.54  5013.6  292.11  5022.4  293.92
  5050.5  296.95  5302.5  295.09  5321.4  293.56  5344.8  294.71  5358.4  292.89
    5387  291.91  5415.6  294.57  5450.8  295.51  5649.7  298.85    5662  298.93
  5803.2  301.52  6078.4  306.66  6144.4   307.6  6529.7  315.72  6688.6  318.75
#Mann= 10 ,-1 , 0
  3812.3     .05       0  4067.5      .1       0    4996     .07       0
    5002      .1       0  5649.7     .05       0    5662      .1       0
  5803.2     .05       0  6078.4      .1       0  6144.4     .05       0
  6529.7      .1       0
Bank Sta=4964,5450.8
XS Rating Curve= 0 ,0
Exp/Cntr=0.3,0.1

Type RM Length L Ch R = 1 ,27729   ,677,677,677
BEGIN DESCRIPTION:
Mapping XS 100c5ddd
END DESCRIPTION:
XS GIS Cut Line= 5
      2229619.19     13242339.85      2229619.19     13241328.68
      2229276.82     13240731.52      2228592.08     13240014.93
      2228257.69     13239815.89
#Sta/Elev= 30
  3218.1  302.93  3411.1  302.09  3471.1  302.49  3531.1  300.21  3829.8  297.67
  3867.3   297.4  4211.1  295.18  4554.1  295.64  4876.9  293.64  4962.8  291.11
  4988.1  287.77  4990.9  287.27  4994.1  287.77  5005.3     289  5012.2  292.77
  5033.6  290.76  5061.9  293.15  5068.8  296.67    5076  295.27  5082.9  297.08
  5097.1  297.19  5125.4  300.43  5224.5  304.17  5543.4  310.54  5910.3   314.9
  6065.1  315.42    6101  316.99  6267.7  320.94  6297.4  323.14  6297.9  323.14
#Mann= 10 ,-1 , 0
  3218.1     .05       0  3411.1      .1       0  3829.8     .05       0
  3867.3      .1       0  4988.1     .07       0  4994.1      .1       0
  5543.4     .05       0  5910.3      .1       0    6101     .05       0
  6297.4      .1       0
Bank Sta=4876.9,5068.8
XS Rating Curve= 0 ,0
Exp/Cntr=0.3,0.1

Type RM Length L Ch R = 1 ,12426   ,758,758,758
BEGIN DESCRIPTION:
ELM CREEK 22.0
END DESCRIPTION:
XS GIS Cut Line= 3
      2241485.67     13238064.21      2241209.17     13237474.35
      2240109.27     13235925.89
#Sta/Elev= 30
  4623.5  266.36  4673.9   266.5    4862  259.59  4913.2  255.19    4936   250.7
  4941.6  252.81  4951.9  250.88  4958.9  240.97  4964.4  243.31    4974  239.56
  4981.7  239.87  4996.1  234.62    5007  233.76  5009.8  233.26    5013  233.76
  5018.2   239.6  5027.3  242.25  5032.9  240.46  5084.4  244.64  5101.3  246.97
    5147   243.9    5221  245.48  5454.3  243.68  5541.9  245.27    5683  248.85
  5934.2  246.69  6199.6   252.1  6508.4  252.86  6900.2  260.13  7174.3  271.95
#Mann= 5 ,-1 , 0
  4623.5      .1       0    5007     .07       0    5013      .1       0
  5541.9     .05       0  6900.2      .1       0
Bank Sta=4951.9,5084.4
XS Rating Curve= 0 ,0
Exp/Cntr=0.3,0.1