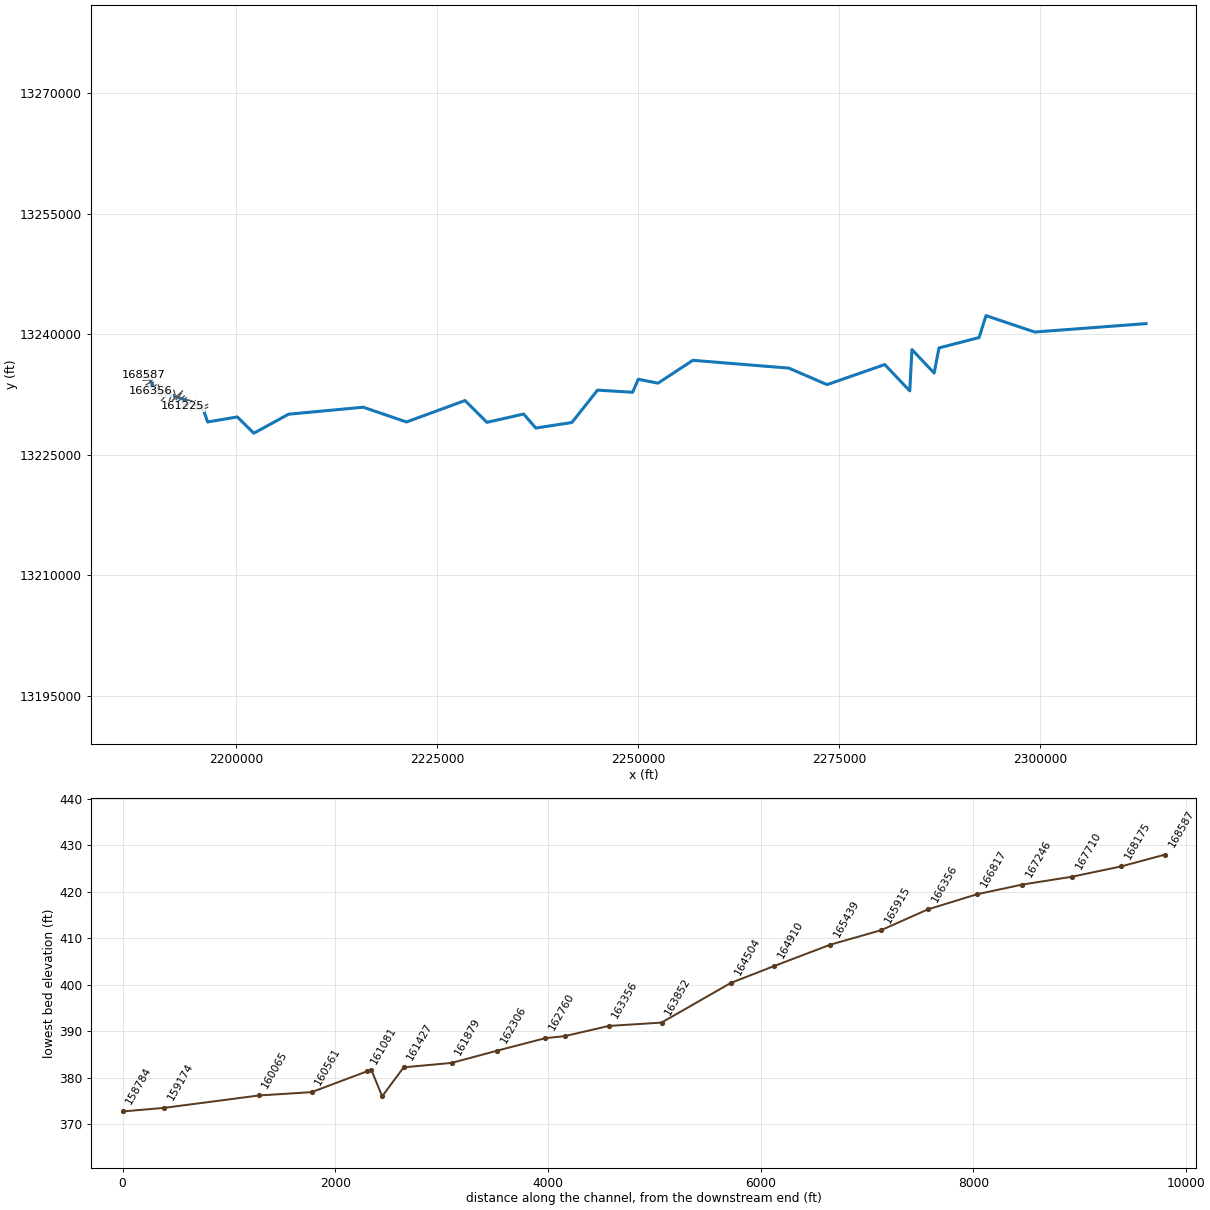
--- RAMIRENA CREEK.prj (project) ---

Proj Title=RAMIRENA CREEK Base Level Engineering
Current Plan=p01
Default Exp/Contr=0.3,0.1
English Units
Geom File=g01
Flow File=f01
Plan File=p01
Y Axis Title=Elevation
X Axis Title(PF)=Main Channel Distance
X Axis Title(XS)=Station
BEGIN DESCRIPTION:
RAMIRENA CREEK
END DESCRIPTION:
DSS Export Rating Curves= 0
DSS Export Rating Curve Sorted= 0
DSS Export Volume Flow Curves= 0
DXF OffsetX= 0
DXF OffsetY= 0
DXF ScaleX= 1
DXF ScaleY= 10

--- RAMIRENA CREEK.p01 (plan) ---

Plan Title=Multiple Run
Program Version=4.10
Short Identifier=Multiple
Geom File=g01
Flow File=f01
Subcritical Flow
K Sum by GR= 0
Std Step Tol= 0.01
Critical Tol= 0.01
Num of Std Step Trials= 20
Max Error Tol= 0.3
Flow Tol Ratio= 0.001
Split Flow NTrial= 30
Split Flow Tol= 0.02
Split Flow Ratio= 0.02
Log Output Level= 0
Friction Slope Method= 1
Unsteady Friction Slope Method= 2
Unsteady Bridges Friction Slope Method= 1
Parabolic Critical Depth
Global Vel Dist= 1 , 1 , 1
Global Log Level= 0
CheckData=True
Encroach Param=-1 ,0,0, 0
BEGIN DESCRIPTION:
Multiple Run
END DESCRIPTION:
Computation Interval=1HOUR
Output Interval=1HOUR
Run HTab= 0
Run UNet= 0
Run PostProcess= 0
Run WQNet= 0
UNET Theta= 1
UNET Theta Warmup= 1
UNET ZTol= 0.02
UNET ZSATol= 0.05
UNET MxIter= 20
UNET MaxInSteps= 0
UNET DtIC= 0
UNET DtMin= 0
UNET MaxCRTS= 20
UNET WFStab= 2
UNET SFStab= 1
UNET WFX= 1
UNET SFX= 1
UNET DSS MLevel= 4
UNET DZMax Abort= 100
UNET Convert EG Bridges= 0
UNET Use Existing IB Tables=-1
UNET Froude Reduction=False
UNET Froude Limit= 1
UNET Froude Power= 10
UNET Time Slicing=0,0, 5
UNET Junction Losses=0
Instantaneous Interval=1HOUR
Write IC File= 0
Write IC File at Sim End=0
Echo Input=False
Echo Parameters=False
Echo Output=False
Write Detailed= 0
WQ AD Non Conservative
WQ ULTIMATE=-1
WQ Max Comp Step=1HOUR
WQ Output Interval=15MIN
WQ Output Selected Increments= 0
WQ Output face flow=0
WQ Output face velocity=0
WQ Output face area=0
WQ Output face dispersion=0
WQ Output cell volume=0
WQ Output cell surface area=0
WQ Output cell continuity=0
WQ Output cumulative cell continuity=0
WQ Output face conc=0
WQ Output face dconc_dx=0
WQ Output face courant=0
WQ Output face peclet=0
WQ Output face adv mass=0
WQ Output face disp mass=0
WQ Output cell mass=0
WQ Output cell source sink temp=0
WQ Output cell source sink nsm=0
WQ Output MaxMinRange=-1
WQ Daily Max Min Mean=-1
WQ Daily Range=0
WQ Daily Time=0
WQ Create Restart=0
WQ Fixed Restart=0
WQ System Summary=0
WQ Use Fixed Temperature=0
Sorting and Armoring Iterations= 10
XS Update Threshold= 0.02
Hydraulics Update Threshold= 0.02
Energy Slope Method= 1
Volume Change Method= 0
XS Weighting Method= 0
Number of US Weighted Cross Sections= 1
Number of DS Weighted Cross Sections= 1
Upstream XS Weight=0.25
Main XS Weight=0.5
Downstream XS Weight=0.25
Number of DS XS's Weighted with US Boundary= 1
Upstream Boundary Weight= 1
Weight of XSs Associated with US Boundary= 0
Number of US XS's Weighted with DS Boundary= 1
Downstream Boundary Weight= 0.5
Weight of XSs Associated with DS Boundary= 0.5
Sediment Output Level= 4
Mass or Volume Output= 0
Output Increment Type= 1
Profile and TS Output Increment= 10
XS Output Flag= 0
XS Output Increment= 10
Disregard all LS=0
Disregard all Conn=0
Disregard all Breaches=0
Disregard all Pumps=0

--- RAMIRENA CREEK.f01 (steady flow) ---

Flow Title=Multiple
Program Version=4.10
Number of Profiles= 7
Profile Names=10-year,25-year,50-year,1pct_min,100-year,1pct_plu,500-year
River Rch & RM=RAMIRENA CREEK,Reach-1         ,168587
     208     290     358     326     441     596     679
River Rch & RM=RAMIRENA CREEK,Reach-1         ,164504
     369     531     669     621     839    1135    1342
River Rch & RM=RAMIRENA CREEK,Reach-1         ,162760
     399     574     724     671     907    1227    1449
River Rch & RM=RAMIRENA CREEK,Reach-1         ,157936
     624     912    1163    1088    1472    1990    2395
River Rch & RM=RAMIRENA CREEK,Reach-1         ,157067
     624     912    1163    1088    1472    1990    2395
River Rch & RM=RAMIRENA CREEK,Reach-1         ,150023
     822    1215    1560    1469    1986    2686    3275
River Rch & RM=RAMIRENA CREEK,Reach-1         ,149127
     822    1215    1560    1469    1986    2686    3275
River Rch & RM=RAMIRENA CREEK,Reach-1         ,147669
     853    1260    1617    1521    2057    2782    3386
River Rch & RM=RAMIRENA CREEK,Reach-1         ,143195
     893    1318    1691    1590    2150    2907    3533
River Rch & RM=RAMIRENA CREEK,Reach-1         ,139592
    1112    1652    2130    2010    2718    3676    4502
River Rch & RM=RAMIRENA CREEK,Reach-1         ,137884
    1112    1652    2130    2010    2718    3676    4502
River Rch & RM=RAMIRENA CREEK,Reach-1         ,134696
    1241    1846    2381    2249    3041    4112    5041
River Rch & RM=RAMIRENA CREEK,Reach-1         ,134121
    1241    1846    2381    2249    3041    4112    5041
River Rch & RM=RAMIRENA CREEK,Reach-1         ,126160
    1277    1899    2450    2312    3127    4229    5181
River Rch & RM=RAMIRENA CREEK,Reach-1         ,124680
    1990    2982    3867    3666    4958    6705    8279
River Rch & RM=RAMIRENA CREEK,Reach-1         ,123300
    1990    2982    3867    3666    4958    6705    8279
River Rch & RM=RAMIRENA CREEK,Reach-1         ,121104
    2054    3080    3994    3787    5122    6927    8556
River Rch & RM=RAMIRENA CREEK,Reach-1         ,120699
    2054    3080    3994    3787    5122    6927    8556
River Rch & RM=RAMIRENA CREEK,Reach-1         ,118877
    2127    3190    4140    3927    5310    7181    8877
River Rch & RM=RAMIRENA CREEK,Reach-1         ,118259
    2127    3190    4140    3927    5310    7181    8877
River Rch & RM=RAMIRENA CREEK,Reach-1         ,113234
    2396    3598    4673    4435    5998    8112   10038
River Rch & RM=RAMIRENA CREEK,Reach-1         ,111648
    2396    3598    4673    4435    5998    8112   10038
River Rch & RM=RAMIRENA CREEK,Reach-1         ,109947
    2409    3616    4695    4455    6024    8147   10074
River Rch & RM=RAMIRENA CREEK,Reach-1         ,103419
    2457    3687    4786    4540    6140    8304   10262
River Rch & RM=RAMIRENA CREEK,Reach-1         ,99800
    2470    3703    4805    4555    6160    8331   10283
River Rch & RM=RAMIRENA CREEK,Reach-1         ,97854
    2489    3730    4838    4585    6200    8385   10342
River Rch & RM=RAMIRENA CREEK,Reach-1         ,92180
    2555    3824    4956    4692    6345    8581   10562
River Rch & RM=RAMIRENA CREEK,Reach-1         ,91076
    2555    3824    4956    4692    6345    8581   10562
River Rch & RM=RAMIRENA CREEK,Reach-1         ,86524
    3084    4629    6012    5702    7712   10429   12882
River Rch & RM=RAMIRENA CREEK,Reach-1         ,78416
    3145    4726    6143    5832    7887   10667   13198
River Rch & RM=RAMIRENA CREEK,Reach-1         ,76710
    3201    4812    6257    5942    8035   10867   13453
River Rch & RM=RAMIRENA CREEK,Reach-1         ,75823
    3240    4866    6322    6000    8114   10973   13565
River Rch & RM=RAMIRENA CREEK,Reach-1         ,67156
    3356    5041    6553    6220    8412   11376   14069
River Rch & RM=RAMIRENA CREEK,Reach-1         ,65396
    3467    5210    6773    6430    8696   11761   14547
River Rch & RM=RAMIRENA CREEK,Reach-1         ,64026
    3496    5250    6822    6474    8756   11841   14634
River Rch & RM=RAMIRENA CREEK,Reach-1         ,62111
    3496    5250    6822    6474    8756   11841   14634
River Rch & RM=RAMIRENA CREEK,Reach-1         ,58285
    3564    5352    6954    6600    8925   12070   14916
River Rch & RM=RAMIRENA CREEK,Reach-1         ,52708
    3592    5387    6994    6631    8967   12127   14954
River Rch & RM=RAMIRENA CREEK,Reach-1         ,44494
    3692    5526    7167    6786    9177   12411   15264
River Rch & RM=RAMIRENA CREEK,Reach-1         ,34838
    3733    5592    7254    6872    9293   12568   15471
River Rch & RM=RAMIRENA CREEK,Reach-1         ,30118
    3749    5616    7286    6901    9333   12622   15538
River Rch & RM=RAMIRENA CREEK,Reach-1         ,27432
    3764    5635    7308    6920    9358   12656   15564
River Rch & RM=RAMIRENA CREEK,Reach-1         ,23866
    3843    5752    7459    7060    9548   12913   15870
River Rch & RM=RAMIRENA CREEK,Reach-1         ,23100
    3843    5752    7459    7060    9548   12913   15870
River Rch & RM=RAMIRENA CREEK,Reach-1         ,18686
    3897    5833    7564    7159    9682   13094   16086
River Rch & RM=RAMIRENA CREEK,Reach-1         ,15919
    3963    5932    7693    7280    9845   13315   16352
River Rch & RM=RAMIRENA CREEK,Reach-1         ,14448
    3993    5975    7745    7326    9908   13399   16441
River Rch & RM=RAMIRENA CREEK,Reach-1         ,11008
    4023    6019    7802    7380    9980   13497   16554
River Rch & RM=RAMIRENA CREEK,Reach-1         ,9452
    4006    5983    7747    7318    9897   13385   16375
Boundary for River Rch & Prof#=RAMIRENA CREEK,Reach-1         , 1
Up Type= 0
Dn Type= 3
Dn Slope=0.005
Boundary for River Rch & Prof#=RAMIRENA CREEK,Reach-1         , 2
Up Type= 0
Dn Type= 3
Dn Slope=0.005
Boundary for River Rch & Prof#=RAMIRENA CREEK,Reach-1         , 3
Up Type= 0
Dn Type= 3
Dn Slope=0.005
Boundary for River Rch & Prof#=RAMIRENA CREEK,Reach-1         , 4
Up Type= 0
Dn Type= 3
Dn Slope=0.005
Boundary for River Rch & Prof#=RAMIRENA CREEK,Reach-1         , 5
Up Type= 0
Dn Type= 3
Dn Slope=0.005
Boundary for River Rch & Prof#=RAMIRENA CREEK,Reach-1         , 6
Up Type= 0
Dn Type= 3
Dn Slope=0.005
Boundary for River Rch & Prof#=RAMIRENA CREEK,Reach-1         , 7
Up Type= 0
Dn Type= 3
Dn Slope=0.005
DSS Import GetInterval= 0
DSS Import GetPeak= 0
DSS Import FillOption= 0

--- RAMIRENA CREEK.g01 (geometry) ---

Geom Title=Existing Conditions
Program Version=4.10

River Reach=RAMIRENA CREEK  ,Reach-1
Reach XY= 30
      2188816.78     13235222.61        2189841.     13233195.81
        2195766.     13231036.49      2196444.11     13229065.15
       2200136.6      13229693.7      2202187.72     13227666.85
       2206513.3     13230034.83      2215791.93     13230905.28
      2221172.87     13229067.64      2228456.72     13231736.99
       2231179.3     13229020.67      2235746.46     13230053.83
      2237258.31     13228310.66      2241743.52     13228996.87
      2244935.33      13233031.3      2249297.72     13232766.85
      2250002.45     13234385.48      2252456.61     13233899.53
      2256793.27     13236745.15      2268726.13     13235773.36
      2273476.65     13233718.26      2280656.57     13236214.15
       2283767.5     13232938.22      2284039.88     13238083.12
       2286796.5      13235159.9      2287405.15     13238287.87
      2292387.84     13239578.12      2293248.52     13242306.89
      2299317.76     13240268.07      2313162.72      13241315.4

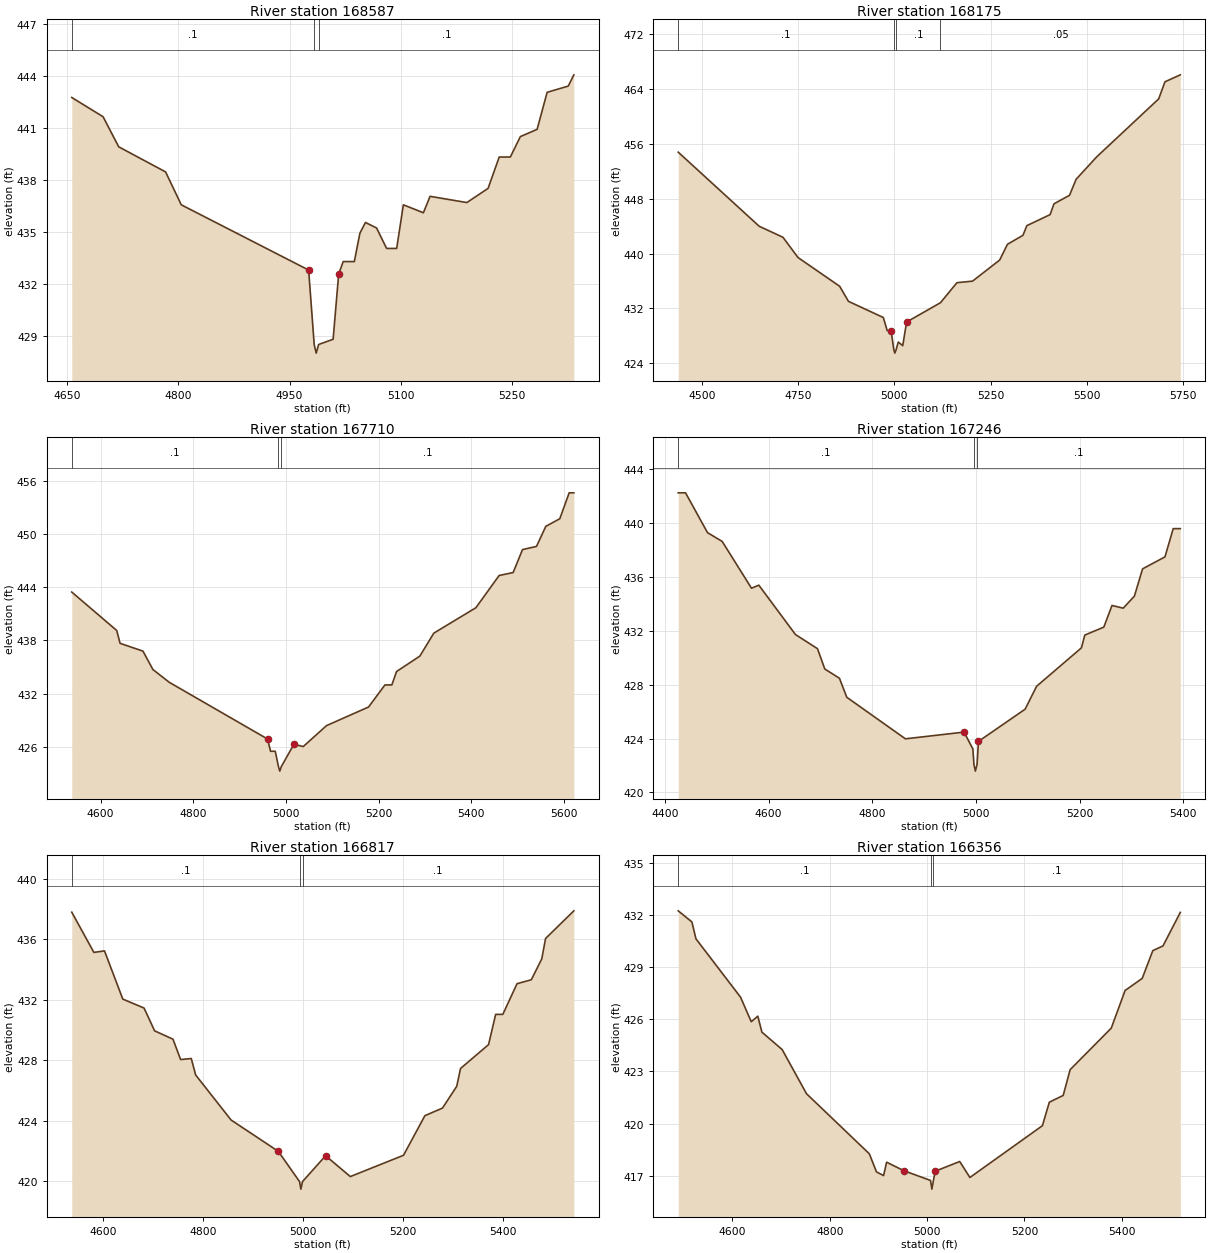
Type RM Length L Ch R = 1 ,168587  ,412,412,412
BEGIN DESCRIPTION:
RAMIRENA CREEK 209.0
END DESCRIPTION:
XS GIS Cut Line= 3
      2189137.76     13235246.87      2188837.72     13235146.85
      2188537.74     13234946.87
#Sta/Elev= 30
  4656.4  442.78  4698.6  441.67  4719.7  439.93  4782.9  438.48    4804  436.58
  4975.7  432.81  4983.2  428.51  4985.9  428.01  4989.2  428.51  5008.7  428.81
  5016.2  432.58  5022.3   433.3  5037.3   433.3  5044.8  434.94  5052.3  435.56
  5067.3  435.24  5080.8  434.06  5094.4  434.06  5103.4  436.58  5130.4  436.12
  5139.4  437.07    5189  436.71  5217.6  437.53  5232.6  439.34  5247.6  439.34
  5261.1  440.52  5283.7  440.94  5297.2  443.08  5325.7  443.44  5333.2  444.09
#Mann= 3 ,-1 , 0
  4656.4      .1       0  4983.2     .07       0  4989.2      .1       0
Bank Sta=4975.7,5016.2
XS Rating Curve= 0 ,0
Exp/Cntr=0.3,0.1

Type RM Length L Ch R = 1 ,168175  ,465,465,465
BEGIN DESCRIPTION:
RAMIRENA CREEK 208.0
END DESCRIPTION:
XS GIS Cut Line= 2
       2189516.5     13234836.86      2188222.03     13234666.81
#Sta/Elev= 30
  4437.8  454.82  4648.4     444  4710.2  442.39  4749.2  439.44  4857.6  435.24
  4880.4  433.04  4971.1  430.68  4981.2  428.77  4991.3  428.77  4998.4  425.98
  5001.1  425.48  5004.4  425.98    5010   427.1  5021.6  426.57  5031.6  430.02
  5119.7  432.84  5162.5  435.76  5203.1  435.99  5273.7  439.07  5293.9  441.37
  5334.2  442.68  5344.3  444.09  5404.8   445.7  5414.9  447.28  5455.3  448.52
  5472.3  450.85  5525.9  454.13  5687.2   462.6  5703.5  465.09  5743.4  466.11
#Mann= 4 ,-1 , 0
  4437.8      .1       0  4998.4     .07       0  5004.4      .1       0
  5119.7     .05       0
Bank Sta=4991.3,5031.6
XS Rating Curve= 0 ,0
Exp/Cntr=0.3,0.1

Type RM Length L Ch R = 1 ,167710  ,464,464,464
BEGIN DESCRIPTION:
RAMIRENA CREEK 207.0
END DESCRIPTION:
XS GIS Cut Line= 3
      2189436.76     13234515.17      2189252.33     13234341.59
      2188427.67     13234243.93
#Sta/Elev= 30
  4537.6  443.44  4634.6  439.11  4641.9  437.66  4691.3  436.78  4712.7  434.71
  4747.9  433.27  4960.2  426.87  4966.7  425.49  4976.8  425.49  4983.8  423.75
  4986.6  423.25  4989.8  423.75  5017.1  426.28  5037.2  426.02  5087.5  428.38
  5178.2  430.48  5213.6  432.97  5228.5  432.97  5238.6  434.48  5288.9  436.22
  5319.1  438.81  5409.8  441.67  5460.1  445.31  5490.3  445.64  5510.5  448.23
  5540.7  448.59  5560.8  450.85    5591  451.71  5611.2  454.63  5621.3  454.63
#Mann= 3 ,-1 , 0
  4537.6      .1       0  4983.8     .07       0  4989.8      .1       0
Bank Sta=4960.2,5017.1
XS Rating Curve= 0 ,0
Exp/Cntr=0.3,0.1

Type RM Length L Ch R = 1 ,167246  ,429,429,429
BEGIN DESCRIPTION:
RAMIRENA CREEK 206.0
END DESCRIPTION:
XS GIS Cut Line= 3
      2189537.69     13234296.82      2189137.72     13233896.85
      2188787.68     13233696.83
#Sta/Elev= 30
  4425.7  442.26  4439.8  442.26  4482.2   439.3  4510.5  438.65  4567.1  435.17
  4581.2   435.4  4651.9  431.73  4694.4  430.68  4708.5  429.17  4736.8  428.48
  4750.9  427.07  4864.1  423.98  4977.2  424.48  4994.2  423.23  4996.3  422.08
    4999  421.58  5002.3  422.08    5005  423.79    5095  426.18  5117.3  427.89
  5203.7  430.74  5210.2  431.69  5246.9  432.28  5262.7  433.89  5284.3  433.69
  5305.9  434.58  5321.7  436.61  5364.9   437.5  5380.8   439.6  5394.5   439.6
#Mann= 3 ,-1 , 0
  4425.7      .1       0  4996.3     .07       0  5002.3      .1       0
Bank Sta=4977.2,5005
XS Rating Curve= 0 ,0
Exp/Cntr=0.3,0.1

Type RM Length L Ch R = 1 ,166817  ,461,461,461
BEGIN DESCRIPTION:
RAMIRENA CREEK 205.0
END DESCRIPTION:
XS GIS Cut Line= 3
       2189687.7     13233996.82      2189437.72     13233596.85
      2189037.69     13233246.83
#Sta/Elev= 30
  4537.5   437.8  4581.7  435.14  4602.9  435.24  4639.5  432.05  4681.9  431.46
  4703.1  429.95  4739.7   429.4    4755  428.05  4776.3  428.12  4785.1  427.03
  4855.9  424.05  4950.2  421.98  4992.6  419.98  4995.3  419.48  4998.6  419.98
  5044.7  421.69  5094.1  420.31  5200.4  421.72  5243.1  424.34  5278.2  424.84
  5306.7  426.28  5314.3  427.46  5370.3  429.04  5384.5  431.04  5398.8  431.04
  5427.2  433.07  5455.7  433.33  5476.6  434.71  5484.2  436.06  5540.7  437.89
#Mann= 3 ,-1 , 0
  4537.5      .1       0  4992.6     .07       0  4998.6      .1       0
Bank Sta=4950.2,5044.7
XS Rating Curve= 0 ,0
Exp/Cntr=0.3,0.1

Type RM Length L Ch R = 1 ,166356  ,441,441,441
BEGIN DESCRIPTION:
RAMIRENA CREEK 204.0
END DESCRIPTION:
XS GIS Cut Line= 3
      2190037.71     13233696.84      2189737.72     13233296.85
      2189387.72     13232896.85
#Sta/Elev= 30
  4488.8  432.24  4516.9   431.6  4525.2  430.63  4616.9  427.27  4638.8  425.86
  4652.3  426.18  4660.7  425.26  4702.3  424.26  4752.3  421.72  4881.5  418.26
  4896.1  417.22  4910.7  417.01  4916.9  417.78  4952.3  417.29  5007.1  416.73
  5009.9  416.23  5013.1  416.73  5016.8  417.26  5067.1  417.82    5088   416.9
    5237  419.88  5251.2  421.23  5279.7  421.62  5293.9   423.1  5378.4  425.49
  5406.9  427.66    5442  428.35  5463.8  429.95  5484.7  430.22  5520.3  432.15
#Mann= 3 ,-1 , 0
  4488.8      .1       0  5007.1     .07       0  5013.1      .1       0
Bank Sta=4952.3,5016.8
XS Rating Curve= 0 ,0
Exp/Cntr=0.3,0.1

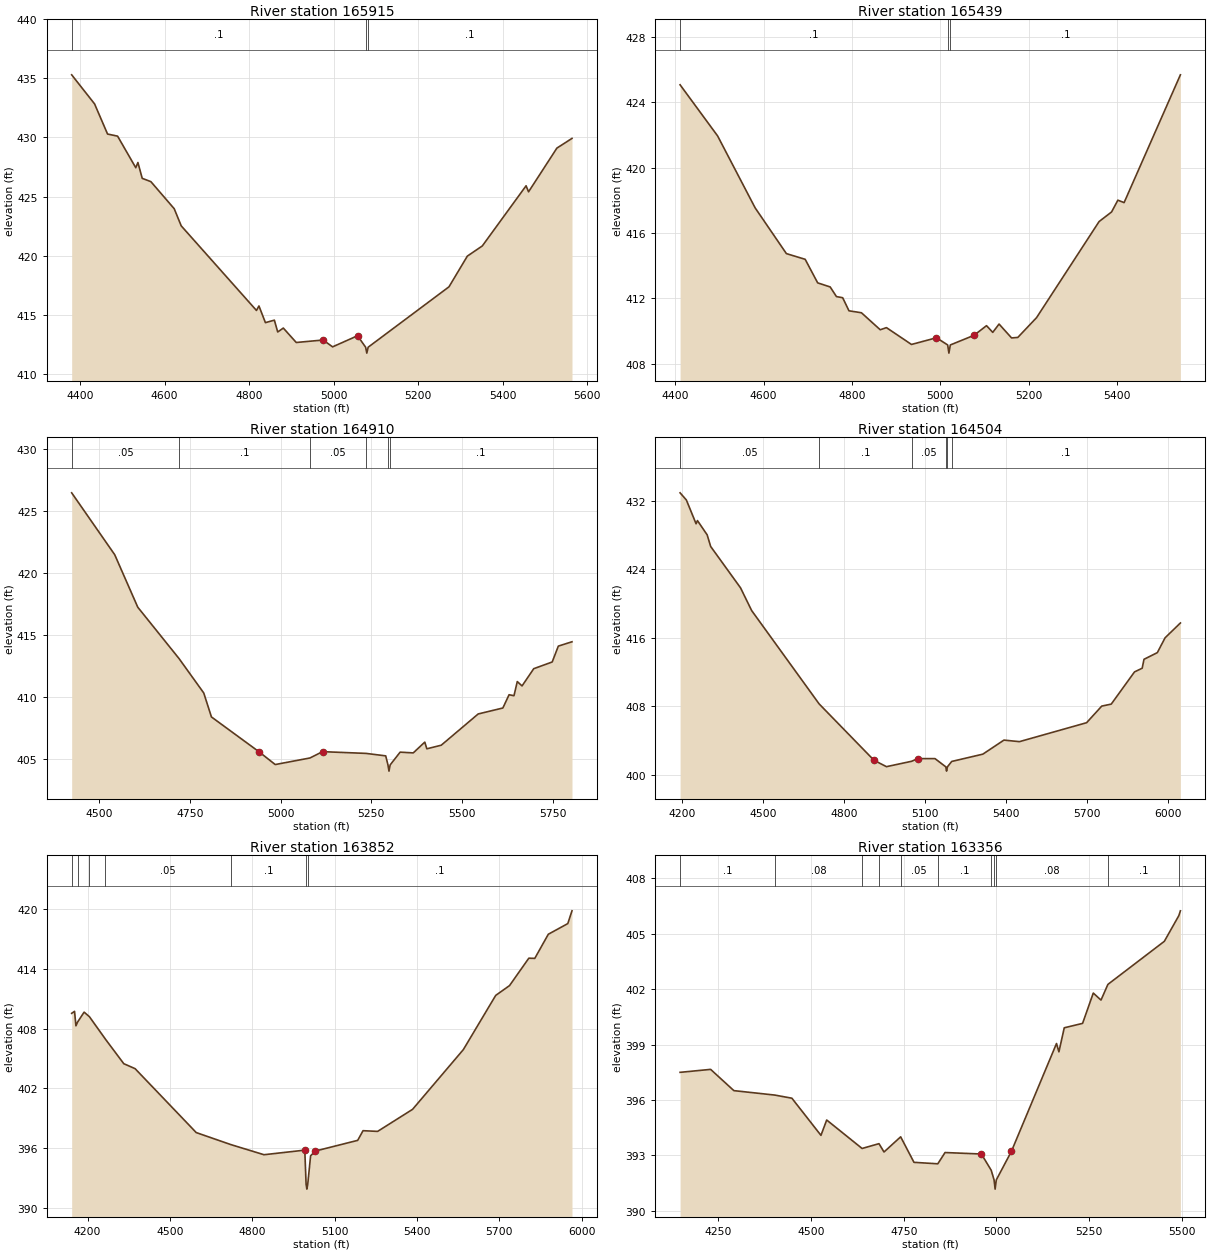
Type RM Length L Ch R = 1 ,165915  ,476,476,476
BEGIN DESCRIPTION:
RAMIRENA CREEK 203.0
END DESCRIPTION:
XS GIS Cut Line= 3
      2190326.54     13233679.65      2190239.75     13233299.92
      2189816.57     13232627.17
#Sta/Elev= 30
  4379.9   435.3  4434.1  432.84  4464.8  430.29  4488.6  430.11  4531.6  427.44
  4536.7  427.88  4546.9  426.54  4567.4  426.26  4622.6  423.97  4639.2  422.52
  4817.3  415.36  4823.2  415.74  4838.5  414.33  4859.7  414.54  4867.6  413.54
  4880.9  413.87  4911.5  412.65  4975.1  412.86  4997.5  412.28  5056.6  413.22
  5075.7  412.25  5078.5  411.75  5081.7  412.25    5273  417.36  5316.5  419.96
  5351.9  420.82  5455.5  425.91  5461.4   425.4  5528.5   429.1  5564.2  429.92
#Mann= 3 ,-1 , 0
  4379.9      .1       0  5075.7     .07       0  5081.7      .1       0
Bank Sta=4975.1,5056.6
XS Rating Curve= 0 ,0
Exp/Cntr=0.3,0.1

Type RM Length L Ch R = 1 ,165439  ,529,529,529
BEGIN DESCRIPTION:
RAMIRENA CREEK 202.0
END DESCRIPTION:
XS GIS Cut Line= 3
      2190937.73     13233346.87      2190537.72     13232946.85
      2190137.71     13232546.85
#Sta/Elev= 30
  4411.3  425.07  4496.2  421.94    4581  417.54  4651.7  414.74  4694.2  414.39
  4722.4  412.95  4750.7   412.7  4764.9  412.11    4779  412.04  4793.2  411.24
  4821.4  411.12  4863.9  410.08    4878  410.21  4934.6  409.18  4991.1  409.59
  5016.4  409.15  5019.2  408.65  5022.4  409.15    5076  409.74  5104.3  410.33
  5118.4  409.92  5132.6  410.43  5160.9  409.58    5175  409.61  5217.4  410.82
  5358.8   416.7  5387.1  417.29  5401.3  418.01  5415.4  417.86  5542.7  425.68
#Mann= 3 ,-1 , 0
  4411.3      .1       0  5016.4     .07       0  5022.4      .1       0
Bank Sta=4991.1,5076
XS Rating Curve= 0 ,0
Exp/Cntr=0.3,0.1

Type RM Length L Ch R = 1 ,164910  ,406,406,406
BEGIN DESCRIPTION:
RAMIRENA CREEK 201.0
END DESCRIPTION:
XS GIS Cut Line= 3
      2191288.07     13233179.44      2190858.43     13232510.18
       2190333.8      13232258.2
#Sta/Elev= 30
  4425.1  426.49  4543.6   421.5    4607  417.27  4720.8  413.12  4788.7  410.35
  4809.8  408.42  4939.9  405.63  4985.5  404.58    5081  405.11  5115.7  405.62
  5235.2  405.48  5289.6  405.28  5295.8  404.55  5298.6  404.05  5301.8  404.55
  5329.3  405.58  5365.4  405.52  5397.2  406.39  5402.8  405.85  5442.5  406.14
  5544.2  408.66  5612.1  409.14  5629.2  410.21  5642.7  410.13  5651.8  411.27
  5664.9  410.92  5697.1  412.31  5747.9  412.85  5764.8  414.13  5802.4  414.48
#Mann= 6 ,-1 , 0
  4425.1     .05       0  4720.8      .1       0    5081     .05       0
  5235.2      .1       0  5295.8     .07       0  5301.8      .1       0
Bank Sta=4939.9,5115.7
XS Rating Curve= 0 ,0
Exp/Cntr=0.3,0.1

Type RM Length L Ch R = 1 ,164504  ,652,652,652
BEGIN DESCRIPTION:
RAMIRENA CREEK 200.0
END DESCRIPTION:
XS GIS Cut Line= 3
      2191487.72     13233246.85      2191287.72     13232446.85
      2190637.72     13231646.85
#Sta/Elev= 30
  4191.7  432.91  4214.9  432.08    4251   429.3  4256.1  429.67  4292.2     428
  4305.1  426.65  4415.9  421.82  4457.1  419.17  4707.2  408.28  4910.7   401.7
    4957  400.95  5050.5  401.58  5073.1  401.89    5137  401.89  5177.1  400.93
  5179.9  400.43  5183.1  400.93  5199.1  401.56  5314.4  402.41  5392.7  404.05
  5450.2  403.87  5699.2  406.08  5755.5  408.02  5790.6  408.25  5876.9  412.01
  5905.4  412.44  5912.1  413.48  5961.6  414.26  5990.3  415.99  6047.1  417.72
#Mann= 6 ,-1 , 0
  4191.7     .05       0  4707.2      .1       0  5050.5     .05       0
  5177.1     .07       0  5183.1     .05       0  5199.1      .1       0
Bank Sta=4910.7,5073.1
XS Rating Curve= 0 ,0
Exp/Cntr=0.3,0.1

Type RM Length L Ch R = 1 ,163852  ,496,496,496
BEGIN DESCRIPTION:
RAMIRENA CREEK 199.0
END DESCRIPTION:
XS GIS Cut Line= 4
      2191849.85     13233030.73      2191977.92     13232530.84
      2191630.92     13231555.93      2191428.51     13231374.17
#Sta/Elev= 30
  4142.3  409.53  4152.7  409.73  4157.8  408.28  4163.8  408.65  4187.6  409.65
    4207  409.19    4265  406.95  4332.1  404.48  4373.4  403.98  4596.2  397.57
  4721.8  396.37    4843  395.35  4991.6  395.81  4996.4   392.4  4999.2   391.9
  5002.4   392.4  5012.8  395.24  5030.2  395.72  5184.4  396.79  5203.9  397.76
    5257  397.69  5384.3   399.9  5569.3  405.89  5687.3  411.33  5737.6  412.31
  5807.9  415.06  5829.6  415.04  5878.9  417.46  5949.9  418.53  5965.2  419.81
#Mann= 7 ,-1 , 0
  4142.3     .08       0  4163.8     .05       0    4207     .08       0
    4265     .05       0  4721.8      .1       0  4996.4     .07       0
  5002.4      .1       0
Bank Sta=4991.6,5030.2
XS Rating Curve= 0 ,0
Exp/Cntr=0.3,0.1

Type RM Length L Ch R = 1 ,163356  ,416,416,416
BEGIN DESCRIPTION:
RAMIRENA CREEK 198.0
END DESCRIPTION:
XS GIS Cut Line= 4
      2192234.06     13233005.86       2192374.5     13232534.97
      2192300.14     13232022.73      2192085.36     13231758.38
#Sta/Elev= 30
  4146.5   397.5  4228.9  397.66  4291.6  396.51  4401.8  396.27  4448.1   396.1
  4526.5  394.09    4542  394.92  4637.5  393.38    4683  393.64  4696.6  393.19
  4741.5  394.01  4777.4  392.63  4841.7  392.55  4861.2  393.16  4959.3  393.08
  4985.8   392.2  4993.5  391.68  4996.3  391.18  4999.5  391.68  5040.2  393.22
  5161.9  399.06  5168.4  398.61  5182.8  399.91  5232.3  400.15  5261.1  401.79
  5281.9  401.41  5300.6  402.26  5452.8  404.59  5491.9  405.98  5496.1  406.24
#Mann= 11 ,-1 , 0
  4146.5      .1       0  4401.8     .08       0  4637.5      .1       0
    4683     .08       0  4741.5     .05       0  4841.7      .1       0
  4985.8     .08       0  4993.5     .07       0  4999.5     .08       0
  5300.6      .1       0  5491.9     .08       0
Bank Sta=4959.3,5040.2
XS Rating Curve= 0 ,0
Exp/Cntr=0.3,0.1

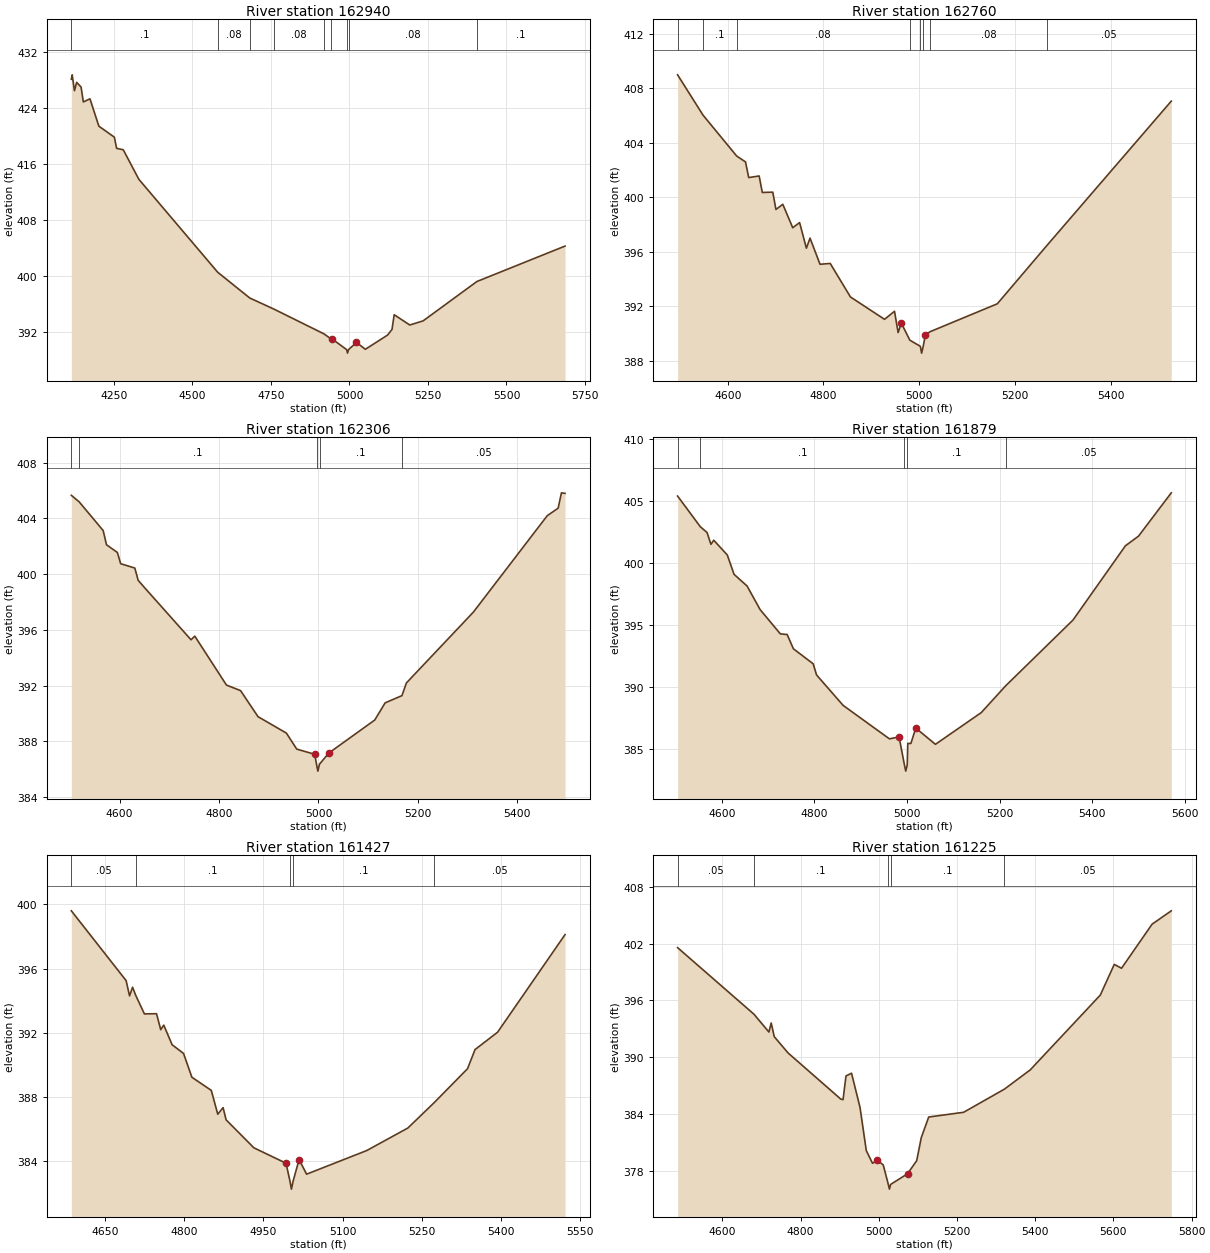
Type RM Length L Ch R = 1 ,162940  ,180,180,180
BEGIN DESCRIPTION:
RAMIRENA CREEK 197.0
END DESCRIPTION:
XS GIS Cut Line= 2
      2193325.48     13232942.96      2192194.92     13231850.55
#Sta/Elev= 30
  4114.4  428.13  4117.1  428.76  4124.3  426.49  4131.3  427.68  4145.4  427.01
  4152.6  424.88  4173.7  425.33    4202  421.42  4251.4  419.85  4258.6  418.25
  4279.7  418.05  4329.3  413.83  4580.5  400.54  4682.5  396.86  4759.2  395.28
  4918.5  391.74  4941.7     391  4944.7  391.01  4991.1  389.48  4993.8  388.98
  4997.1  389.48  5022.4  390.51  5050.7  389.53  5121.4  391.56  5135.5  392.37
  5142.5  394.47  5192.1     393  5234.6  393.59    5406  399.22  5686.5  404.28
#Mann= 9 ,-1 , 0
  4114.4      .1       0  4580.5     .08       0  4682.5      .1       0
  4759.2     .08       0  4918.5      .1       0  4941.7     .08       0
  4991.1     .07       0  4997.1     .08       0    5406      .1       0
Bank Sta=4944.7,5022.4
XS Rating Curve= 0 ,0
Exp/Cntr=0.3,0.1

Type RM Length L Ch R = 1 ,162760  ,454,454,454
BEGIN DESCRIPTION:
RAMIRENA CREEK 196.0
END DESCRIPTION:
XS GIS Cut Line= 3
      2193187.74     13232646.88      2192837.72     13232246.85
      2192537.74     13231846.89
#Sta/Elev= 30
  4495.3  408.98  4548.3  406.03  4618.8  403.02  4637.2  402.59  4643.9  401.44
  4665.7  401.56  4672.3  400.35  4694.2  400.37  4700.8   399.1  4715.1  399.48
  4735.9  397.76  4750.2  398.14  4764.4  396.26    4772     397  4792.9  395.08
  4814.2  395.14  4856.5  392.68  4927.7  391.04  4948.5  391.63  4956.1  390.07
  4962.8  390.76  4980.6  389.51  5002.5  389.06  5005.2  388.56  5008.5  389.06
  5013.1  389.91  5023.4  390.14  5163.3  392.18  5266.5  396.44  5526.8  407.05
#Mann= 8 ,-1 , 0
  4495.3     .08       0  4548.3      .1       0  4618.8     .08       0
  4980.6      .1       0  5002.5     .07       0  5008.5      .1       0
  5023.4     .08       0  5266.5     .05       0
Bank Sta=4962.8,5013.1
XS Rating Curve= 0 ,0
Exp/Cntr=0.3,0.1

Type RM Length L Ch R = 1 ,162306  ,427,427,427
BEGIN DESCRIPTION:
RAMIRENA CREEK 195.0
END DESCRIPTION:
XS GIS Cut Line= 3
       2193537.7     13232296.83      2193137.72     13231946.85
      2192787.69     13231646.83
#Sta/Elev= 30
  4503.2  405.66    4519  405.19  4567.2  403.13  4573.9  402.11  4595.7  401.56
  4602.4  400.75  4630.8  400.44  4637.5  399.56  4651.7  398.98  4743.8  395.29
  4751.4  395.55    4815  392.04  4843.4  391.64  4878.5  389.77  4935.5  388.59
  4956.4  387.44  4992.4  387.07  4996.1  386.36  4998.8  385.86  5002.1  386.36
  5020.9  387.16  5113.2  389.53    5134  390.76  5167.8  391.28  5176.8  392.19
  5311.3  397.27    5460   404.2  5481.9  404.74  5488.5  405.84  5495.7   405.8
#Mann= 5 ,-1 , 0
  4503.2     .05       0    4519      .1       0  4996.1     .07       0
  5002.1      .1       0  5167.8     .05       0
Bank Sta=4992.4,5020.9
XS Rating Curve= 0 ,0
Exp/Cntr=0.3,0.1

Type RM Length L Ch R = 1 ,161879  ,452,452,452
BEGIN DESCRIPTION:
RAMIRENA CREEK 194.0
END DESCRIPTION:
XS GIS Cut Line= 3
      2193787.73     13232096.87      2193487.72     13231696.85
      2193087.73     13231296.86
#Sta/Elev= 30
  4504.7  405.41  4553.7  402.94  4568.3  402.47  4576.6  401.52  4582.8  401.85
    4612  400.66  4626.6   399.1  4654.7  398.16  4682.8  396.26  4726.6   394.3
  4741.2  394.25  4754.7   393.1  4797.4  391.89  4804.7  390.99    4862  388.54
    4962  385.84  4982.8     386  4994.4  383.74  4997.2  383.24  5000.4  383.74
  5001.6  385.47  5008.3  385.47  5018.9  386.71  5061.3   385.4  5160.3  387.96
    5213  390.12  5358.3  395.42  5471.4   401.4  5499.7  402.18  5570.4  405.67
#Mann= 5 ,-1 , 0
  4504.7     .05       0  4553.7      .1       0  4994.4     .07       0
  5000.4      .1       0    5213     .05       0
Bank Sta=4982.8,5018.9
XS Rating Curve= 0 ,0
Exp/Cntr=0.3,0.1

Type RM Length L Ch R = 1 ,161427  ,202,202,202
BEGIN DESCRIPTION:
RAMIRENA CREEK 193.0
END DESCRIPTION:
XS GIS Cut Line= 3
      2194037.74      13231796.9      2193837.72     13231446.85
       2193437.7     13231096.83
#Sta/Elev= 30
  4586.5  399.59  4690.2  395.25  4696.7   394.3  4702.4  394.84  4708.3  394.34
  4724.8  393.18  4747.8  393.19  4755.7   392.2  4761.5  392.48  4777.3  391.26
  4798.9  390.72  4814.7  389.24  4851.5  388.42  4863.7  386.94  4873.8  387.35
  4879.5  386.59  4932.1  384.85    4993  383.89  5000.4  382.78  5003.2  382.28
  5006.4  382.78  5017.7  384.12  5031.9  383.21  5145.8  384.68  5223.6  386.08
  5273.8  387.67  5336.6  389.77  5350.8  390.96  5393.5  392.04  5521.2  398.11
#Mann= 5 ,-1 , 0
  4586.5     .05       0  4708.3      .1       0  5000.4     .07       0
  5006.4      .1       0  5273.8     .05       0
Bank Sta=4993,5017.7
XS Rating Curve= 0 ,0
Exp/Cntr=0.3,0.1

Type RM Length L Ch R = 1 ,161225  ,102,102,102
BEGIN DESCRIPTION:
Mapping XS b10dfa31
END DESCRIPTION:
XS GIS Cut Line= 3
      2194238.67     13231762.39      2193964.37     13231272.83
      2193312.15      13231016.1
#Sta/Elev= 30
  4485.8  401.57  4680.9  394.54  4719.3  392.65  4725.1  393.61  4732.9  392.16
  4768.5  390.43  4903.1  385.56  4908.8  385.51  4916.3  388.01  4930.5   388.3
  4952.2  384.68  4968.2  380.12  4984.1  378.78  4996.5  379.11  5011.6   378.6
  5024.5  376.55  5027.3  376.05  5030.5  376.55  5073.6  377.67  5097.1  379.06
  5108.7  381.48  5127.8  383.67  5217.1  384.17  5321.1  386.61  5387.3  388.65
  5566.5  396.56  5602.2   399.8  5620.7  399.39  5698.9  404.05  5747.9  405.46
#Mann= 5 ,-1 , 0
  4485.8     .05       0  4680.9      .1       0  5024.5     .07       0
  5030.5      .1       0  5321.1     .05       0
Bank Sta=4996.5,5073.6
XS Rating Curve= 0 ,0
Exp/Cntr=0.3,0.1

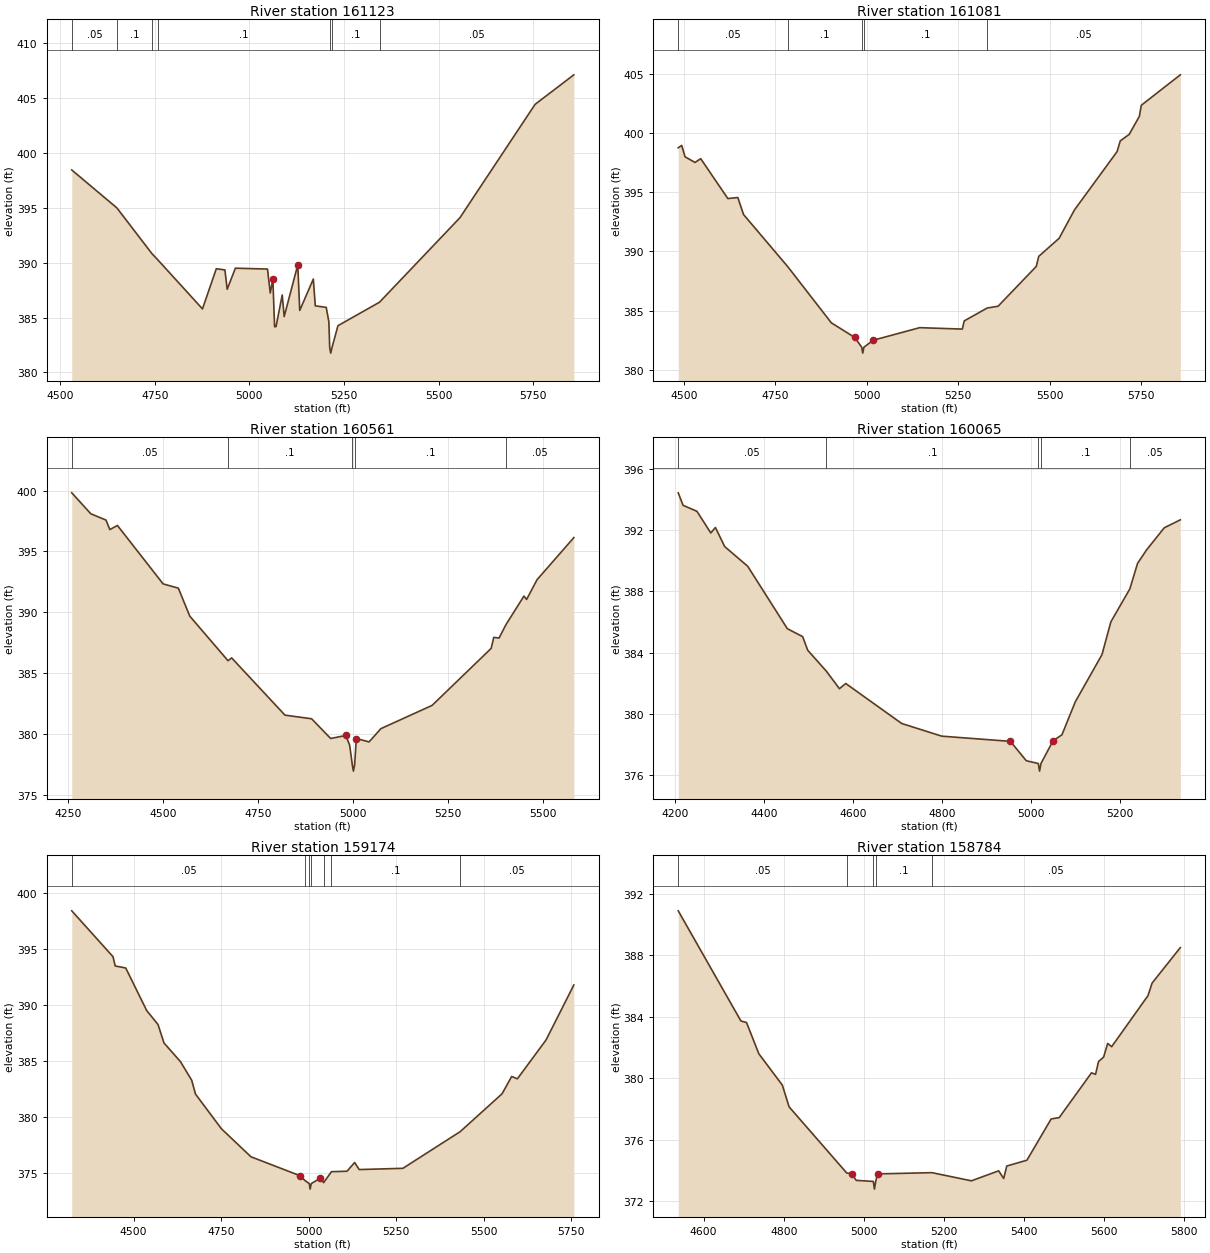
Type RM Length L Ch R = 1 ,161123  ,42,42,42
BEGIN DESCRIPTION:
RAMIRENA CREEK 192.0
END DESCRIPTION:
XS GIS Cut Line= 5
      2194301.17     13231651.27      2194096.32     13231279.77
      2194016.46     13231196.44      2193547.71     13231078.38
       2193266.5     13230963.81
#Sta/Elev= 30
  4530.8  398.45  4650.1  394.99  4742.8  390.82  4757.4  390.29  4876.2  385.79
  4912.7  389.45  4935.5  389.34  4941.5  387.58  4963.1   389.5    5048  389.42
  5055.3  387.24  5062.2  388.47  5066.7  384.17  5070.5  384.17  5086.9  387.06
  5092.1  385.09    5128   389.8  5133.2  385.65  5169.1  388.51  5174.3  386.07
  5203.2  385.93  5210.2  384.61  5212.4  382.26  5215.1  381.76  5218.4  382.26
  5234.2  384.26    5344   386.4  5556.5   394.1  5755.1  404.43  5857.5  407.12
#Mann= 7 ,-1 , 0
  4530.8     .05       0  4650.1      .1       0  4742.8     .05       0
  4757.4      .1       0  5212.4     .07       0  5218.4      .1       0
    5344     .05       0
Bank Sta=5062.2,5128
XS Rating Curve= 0 ,0
Exp/Cntr=0.3,0.1

Type RM Length L Ch R = 1 ,161081  ,520,520,520
BEGIN DESCRIPTION:
Mapping XS cb01e646
END DESCRIPTION:
XS GIS Cut Line= 4
      2194373.88     13231655.04      2194159.08     13231291.54
      2193977.32     13231084.99      2193330.44     13230891.34
#Sta/Elev= 30
  4484.7  398.75  4494.2  398.95  4503.3  397.99  4530.6  397.51  4546.2  397.83
  4620.4  394.46  4647.6  394.55  4663.3  393.11  4783.9  388.72  4903.2  383.97
  4967.5  382.73  4986.3  381.91  4989.1  381.41  4992.3  381.91  5017.8   382.5
  5144.9  383.56  5261.3  383.44  5266.6  384.13  5329.4  385.22  5359.1  385.37
  5463.5  388.73  5470.3  389.58  5526.1  391.11  5567.9   393.5  5684.5  398.43
  5693.1  399.33  5717.6  399.88  5745.3   401.4  5750.7  402.34  5857.3  404.91
#Mann= 5 ,-1 , 0
  4484.7     .05       0  4783.9      .1       0  4986.3     .07       0
  4992.3      .1       0  5329.4     .05       0
Bank Sta=4967.5,5017.8
XS Rating Curve= 0 ,0
Exp/Cntr=0.3,0.1

Type RM Length L Ch R = 1 ,160561  ,496,496,496
BEGIN DESCRIPTION:
RAMIRENA CREEK 191.0
END DESCRIPTION:
XS GIS Cut Line= 3
      2194487.72     13231696.82      2194537.72     13230946.85
      2194387.72     13230396.87
#Sta/Elev= 30
  4260.5  399.81  4310.6  398.09  4350.7  397.57  4360.7  396.79  4380.7  397.13
    4501  392.33  4541.1  391.98  4571.2  389.68  4671.8  386.02  4681.4  386.25
  4821.7  381.55  4891.9  381.25    4942  379.63  4982.1  379.88  4992.1  379.07
  4999.1  377.45  5001.9  376.95  5005.1  377.45  5009.6  379.63  5043.2  379.35
  5074.3  380.44  5209.1  382.35  5364.5  387.03  5371.5  387.94  5385.3  387.88
  5403.4  388.98  5450.9  391.33  5457.8  391.05  5485.5  392.68  5582.2  396.13
#Mann= 5 ,-1 , 0
  4260.5     .05       0  4671.8      .1       0  4999.1     .07       0
  5005.1      .1       0  5403.4     .05       0
Bank Sta=4982.1,5009.6
XS Rating Curve= 0 ,0
Exp/Cntr=0.3,0.1

Type RM Length L Ch R = 1 ,160065  ,891,891,891
BEGIN DESCRIPTION:
RAMIRENA CREEK 190.0
END DESCRIPTION:
XS GIS Cut Line= 3
      2194927.24     13231737.46      2195014.05     13231422.75
      2194992.38     13230620.81
#Sta/Elev= 30
  4207.2  394.46  4218.2  393.64  4249.3  393.25  4280.4  391.83  4290.8  392.19
  4311.6  390.94  4363.4  389.65  4452.5  385.56  4486.9  385.04  4498.3  384.15
  4540.1  382.78  4569.6  381.63  4583.8  381.97  4709.6  379.35  4799.7  378.52
  4953.9  378.18  4989.7  376.91  5016.7  376.73  5019.5  376.23  5022.7  376.73
  5049.8  378.22  5069.8  378.61  5099.8  380.77  5159.8  383.86  5179.8  386.01
  5222.5  388.17  5239.8  389.84  5259.8  390.71  5299.8  392.17  5335.9  392.69
#Mann= 5 ,-1 , 0
  4207.2     .05       0  4540.1      .1       0  5016.7     .07       0
  5022.7      .1       0  5222.5     .05       0
Bank Sta=4953.9,5049.8
XS Rating Curve= 0 ,0
Exp/Cntr=0.3,0.1

Type RM Length L Ch R = 1 ,159174  ,390,390,390
BEGIN DESCRIPTION:
RAMIRENA CREEK 189.0
END DESCRIPTION:
XS GIS Cut Line= 3
      2196437.68     13231246.84      2195787.72     13230996.85
      2195137.74     13230646.86
#Sta/Elev= 30
  4323.1  398.45  4440.9  394.35  4447.3  393.52  4477.3  393.34  4537.3  389.53
  4569.5  388.29  4586.6  386.64  4633.8  384.96  4665.9   383.3  4676.6  382.07
  4750.6  378.97  4835.2  376.46  4974.5  374.78  4990.3  374.32  5001.5  374.07
  5004.2  373.57  5007.5  374.07  5033.3  374.54  5042.7  374.15  5065.2  375.13
  5109.5  375.17  5131.4  375.95  5144.4  375.32  5269.3  375.43    5433  378.71
  5552.5  382.09  5580.1  383.64  5596.3  383.43  5678.2   386.9  5757.7  391.82
#Mann= 7 ,-1 , 0
  4323.1     .05       0  4990.3      .1       0  5001.5     .07       0
  5007.5      .1       0  5042.7     .05       0  5065.2      .1       0
    5433     .05       0
Bank Sta=4974.5,5033.3
XS Rating Curve= 0 ,0
Exp/Cntr=0.3,0.1

Type RM Length L Ch R = 1 ,158784  ,473,473,473
BEGIN DESCRIPTION:
RAMIRENA CREEK 188.0
END DESCRIPTION:
XS GIS Cut Line= 3
       2196437.7     13230896.84      2196037.72     13230696.85
      2195237.73     13230596.86
#Sta/Elev= 30
  4536.6  390.89  4693.1  383.73  4707.1  383.63  4737.8   381.6  4796.5  379.56
  4813.3  378.15  4957.2  373.85  4969.8  373.79    4981  373.37  5023.6   373.3
  5026.4   372.8  5029.6   373.3  5034.2  373.79    5170  373.87  5268.5  373.34
  5336.5  373.99  5349.1  373.49  5356.7   374.3  5407.1  374.68  5467.5  377.36
  5487.7  377.45  5568.3  380.36  5578.4  380.26  5585.9   381.1  5598.5  381.38
  5608.6  382.27  5618.7  382.06  5709.4  385.38  5719.5  386.19    5790   388.5
#Mann= 5 ,-1 , 0
  4536.6     .05       0  4957.2      .1       0  5023.6     .07       0
  5029.6      .1       0    5170     .05       0
Bank Sta=4969.8,5034.2
XS Rating Curve= 0 ,0
Exp/Cntr=0.3,0.1