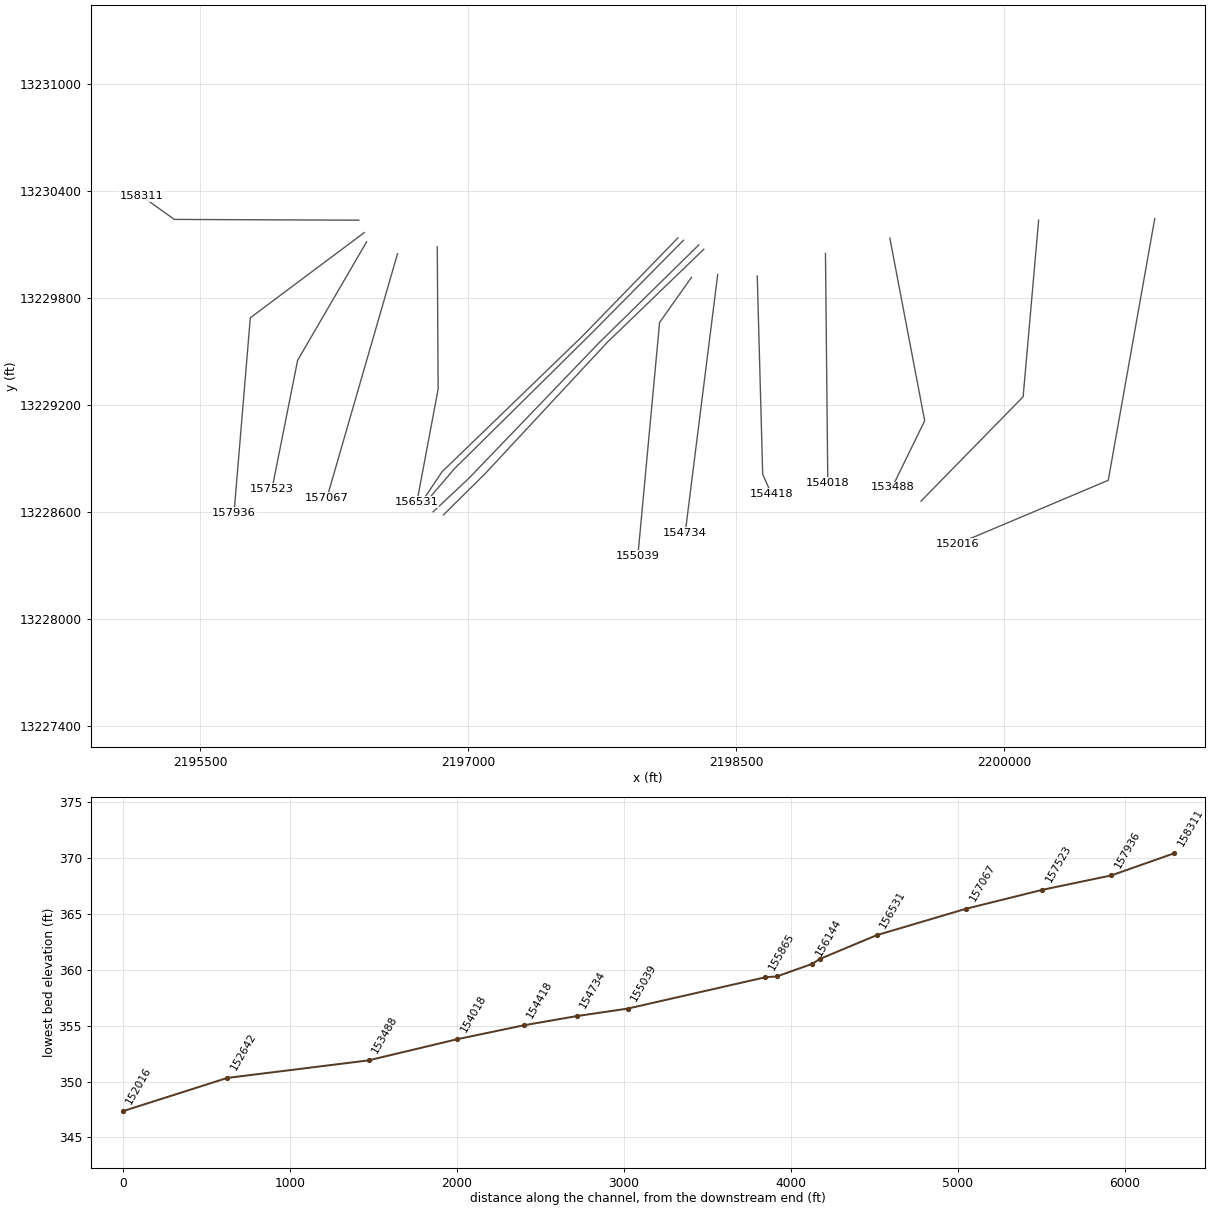
HEC-RAS study RAMIRENA CREEK.prj: RAMIRENA CREEK Base Level Engineering

--- RAMIRENA CREEK.g01 (geometry) --- (continued)

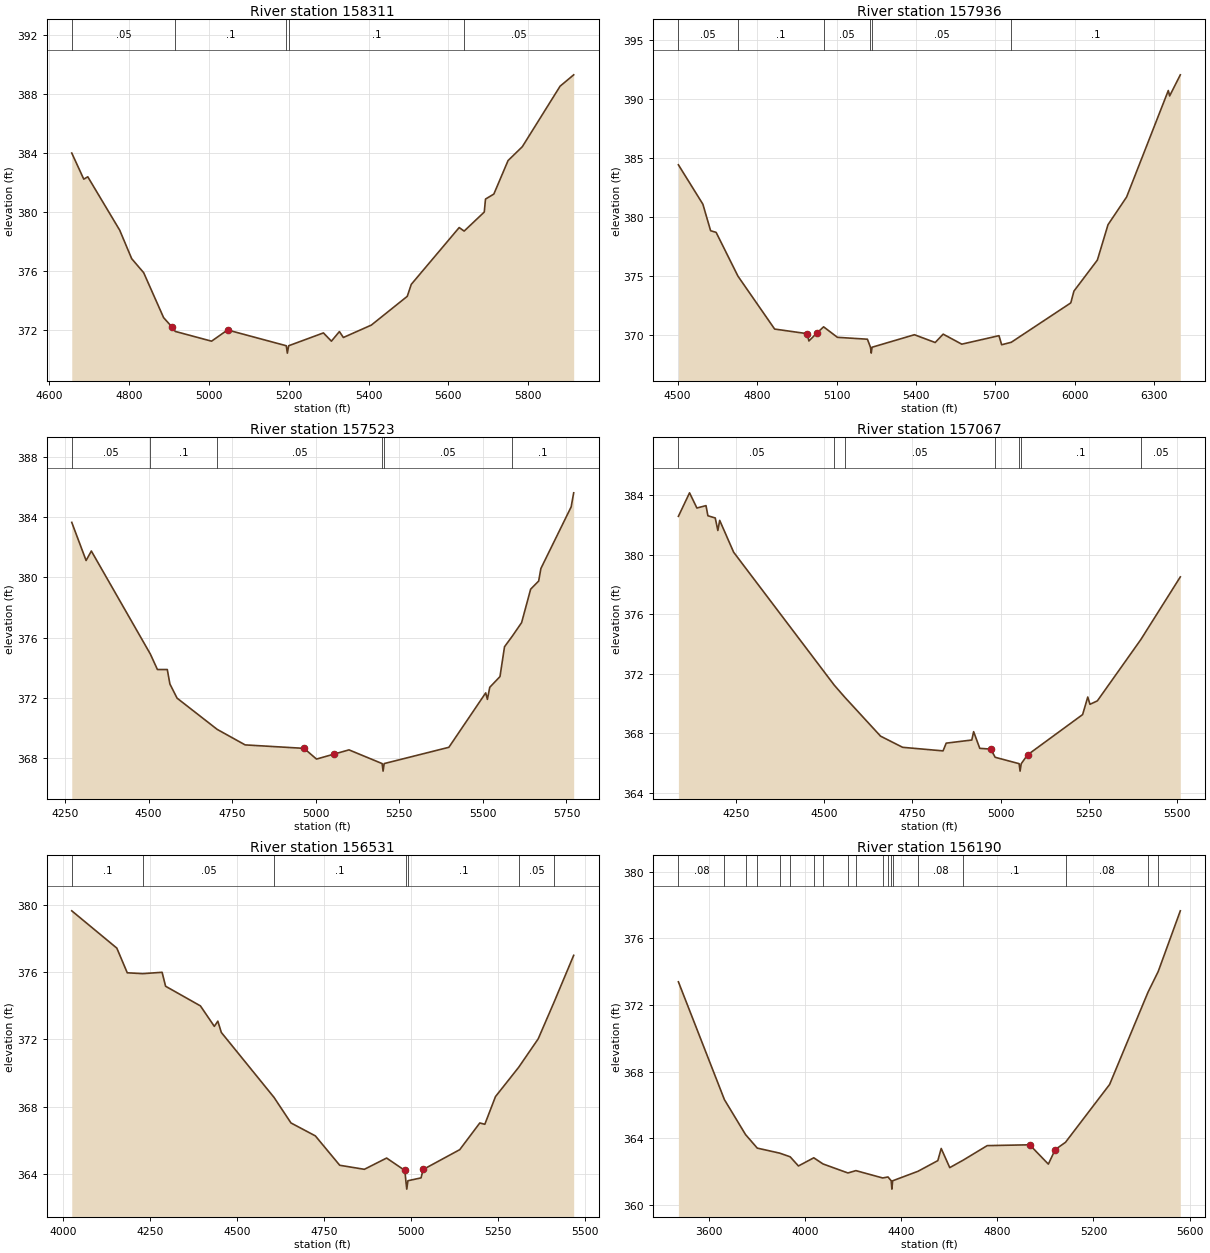
Type RM Length L Ch R = 1 ,158311  ,375,375,375
BEGIN DESCRIPTION:
Mapping XS 2931d8e6
END DESCRIPTION:
XS GIS Cut Line= 3
      2196387.87     13230235.43      2195354.91     13230239.77
      2195172.69     13230369.93
#Sta/Elev= 30
  4656.9  383.97    4687   382.2    4697  382.36    4777  378.74    4807  376.81
    4837  375.86    4887  372.81    4907  372.21  4916.1  371.88    5007  371.22
    5047  371.98  5194.1  370.91  5196.8  370.41  5200.1  370.91  5287.1  371.78
  5307.1  371.22  5327.1  371.87  5337.1  371.47  5407.1  372.31  5497.1  374.26
  5507.1  375.07  5627.1  378.92  5639.5  378.68  5689.9  379.97    5693  380.85
  5713.9  381.19  5749.5  383.46  5785.2   384.4  5879.8   388.5  5913.8  389.27
#Mann= 5 ,-1 , 0
  4656.9     .05       0  4916.1      .1       0  5194.1     .07       0
  5200.1      .1       0  5639.5     .05       0
Bank Sta=4907,5047
XS Rating Curve= 0 ,0
Exp/Cntr=0.3,0.1

Type RM Length L Ch R = 1 ,157936  ,413,413,413
BEGIN DESCRIPTION:
Mapping XS a39aebea
END DESCRIPTION:
XS GIS Cut Line= 3
       2196418.3     13230166.01      2195780.25     13229688.56
      2195689.11     13228594.86
#Sta/Elev= 30
  4503.2  384.41  4595.6  381.07  4624.8  378.82  4645.6  378.68  4728.2  374.96
  4866.5  370.48  4989.5  370.09  4995.7  369.47  5024.9  370.12  5051.2  370.67
  5103.4  369.78  5216.6  369.62  5228.2  368.94    5231  368.44  5234.2  368.94
    5394     370  5472.4  369.34  5502.5  370.05  5572.8   369.2  5713.2  369.92
  5723.3  369.15  5759.6  369.36  5984.2   372.7  5996.1   373.7  6084.5  376.33
  6124.7  379.33  6194.9  381.68  6352.3  390.71  6357.3  390.25  6397.6  392.04
#Mann= 6 ,-1 , 0
  4503.2     .05       0  4728.2      .1       0  5051.2     .05       0
  5228.2     .07       0  5234.2     .05       0  5759.6      .1       0
Bank Sta=4989.5,5024.9
XS Rating Curve= 0 ,0
Exp/Cntr=0.3,0.1

Type RM Length L Ch R = 1 ,157523  ,456,456,456
BEGIN DESCRIPTION:
Mapping XS 46c6d0f1
END DESCRIPTION:
XS GIS Cut Line= 3
      2196431.32     13230113.94      2196045.01     13229449.84
      2195902.03      13228730.6
#Sta/Elev= 30
  4269.9  383.65  4312.8  381.12  4328.5  381.75  4504.9  374.92  4526.2  373.89
  4555.7  373.89  4563.5  372.93    4585  371.99  4704.9  369.92  4788.6  368.89
  4964.8  368.66  5002.1  367.95  5053.2  368.27  5099.3  368.56  5198.5  367.65
  5201.3  367.15  5204.5  367.65  5398.1  368.73  5508.3  372.34  5513.4  371.91
  5520.4  372.71    5551  373.42  5564.6   375.4  5588.1  376.11  5615.7     377
  5642.8  379.22  5666.8  379.76  5673.4  380.59    5764  384.68  5771.5  385.61
#Mann= 6 ,-1 , 0
  4269.9     .05       0  4504.9      .1       0  4704.9     .05       0
  5198.5     .03       0  5204.5     .05       0  5588.1      .1       0
Bank Sta=4964.8,5053.2
XS Rating Curve= 0 ,0
Exp/Cntr=0.3,0.1

Type RM Length L Ch R = 1 ,157067  ,536,536,536
BEGIN DESCRIPTION:
Mapping XS a4ac167f
END DESCRIPTION:
XS GIS Cut Line= 2
      2196604.37     13230047.19      2196209.68     13228680.96
#Sta/Elev= 30
  4087.3  382.58  4118.9  384.16  4139.7  383.14  4165.5   383.3  4170.9  382.62
  4191.7  382.47  4199.1  381.63  4204.3  382.31  4243.8  380.17  4529.1  371.23
  4559.7   370.4  4660.1  367.81  4722.6  367.06  4837.1  366.82  4846.1  367.34
  4918.6  367.55  4923.8  368.11  4941.2  366.99  4972.4  366.94  4984.8  366.39
  5052.7  365.96  5055.4  365.46  5058.7  365.96  5076.5  366.55  5232.6  369.26
  5247.2  370.44  5253.4  369.95  5274.3  370.18  5397.5   374.3  5509.4  378.51
#Mann= 7 ,-1 , 0
  4087.3     .05       0  4529.1      .1       0  4559.7     .05       0
  4984.8      .1       0  5052.7     .07       0  5058.7      .1       0
  5397.5     .05       0
Bank Sta=4972.4,5076.5
XS Rating Curve= 0 ,0
Exp/Cntr=0.3,0.1

Type RM Length L Ch R = 1 ,156531  ,341,341,341
BEGIN DESCRIPTION:
RAMIRENA CREEK 183.0
END DESCRIPTION:
XS GIS Cut Line= 3
      2196827.18      13230086.2      2196831.93     13229288.39
       2196713.1     13228656.19
#Sta/Elev= 30
  4025.5  379.66  4154.9  377.44  4184.9  375.97  4229.3  375.92  4284.9     376
  4294.9  375.17  4394.9     374  4434.9  372.78  4444.9  373.09  4454.9  372.42
  4606.3  368.55  4654.9  367.03  4724.9  366.26  4794.9  364.51  4865.6  364.27
  4929.5  364.94    4982   364.2  4984.7  363.59  4987.4  363.09  4990.7  363.59
  5028.4  363.76  5034.5  364.26  5139.5  365.44  5197.1  367.03  5211.5  366.95
  5242.1   368.6  5308.9  370.35  5364.8  372.04    5410  374.21  5466.6  377.01
#Mann= 7 ,-1 , 0
  4025.5      .1       0  4229.3     .05       0  4606.3      .1       0
  4984.7     .07       0  4990.7      .1       0  5308.9     .05       0
    5410     .08       0
Bank Sta=4982,5034.5
XS Rating Curve= 0 ,0
Exp/Cntr=0.3,0.1

Type RM Length L Ch R = 1 ,156190  ,46,46,46
BEGIN DESCRIPTION:
Mapping XS e5fe3090
END DESCRIPTION:
XS GIS Cut Line= 4
      2198174.32     13230135.96      2197639.72     13229585.22
      2196854.13     13228825.67      2196727.36     13228637.21
#Sta/Elev= 30
  3473.7   373.4  3665.1  366.33  3753.1  364.23  3801.8  363.42    3895  363.12
  3938.5   362.9  3972.9  362.35  4036.8  362.84  4075.2  362.47  4178.7  361.93
  4211.9  362.07  4323.3  361.63  4345.4  361.69  4358.7  361.46  4361.5  360.96
  4364.7  361.46    4470  362.03  4552.6  362.67  4566.7   363.4  4602.2  362.25
  4658.2   362.7  4757.9  363.57  4934.6  363.62  5012.3  362.46  5040.6  363.33
  5083.6  363.77    5267  367.24  5426.5  372.77  5469.2  374.02  5561.1  377.66
#Mann= 19 ,-1 , 0
  3473.7     .08       0  3665.1      .1       0  3753.1     .08       0
  3801.8     .05       0    3895     .08       0  3938.5     .05       0
  4036.8     .08       0  4075.2      .1       0  4178.7     .08       0
  4211.9      .1       0  4323.3     .08       0  4345.4      .1       0
  4358.7     .07       0  4364.7      .1       0    4470     .08       0
  4658.2      .1       0  5083.6     .08       0  5426.5     .05       0
  5469.2     .08       0
Bank Sta=4934.6,5040.6
XS Rating Curve= 0 ,0
Exp/Cntr=0.3,0.1

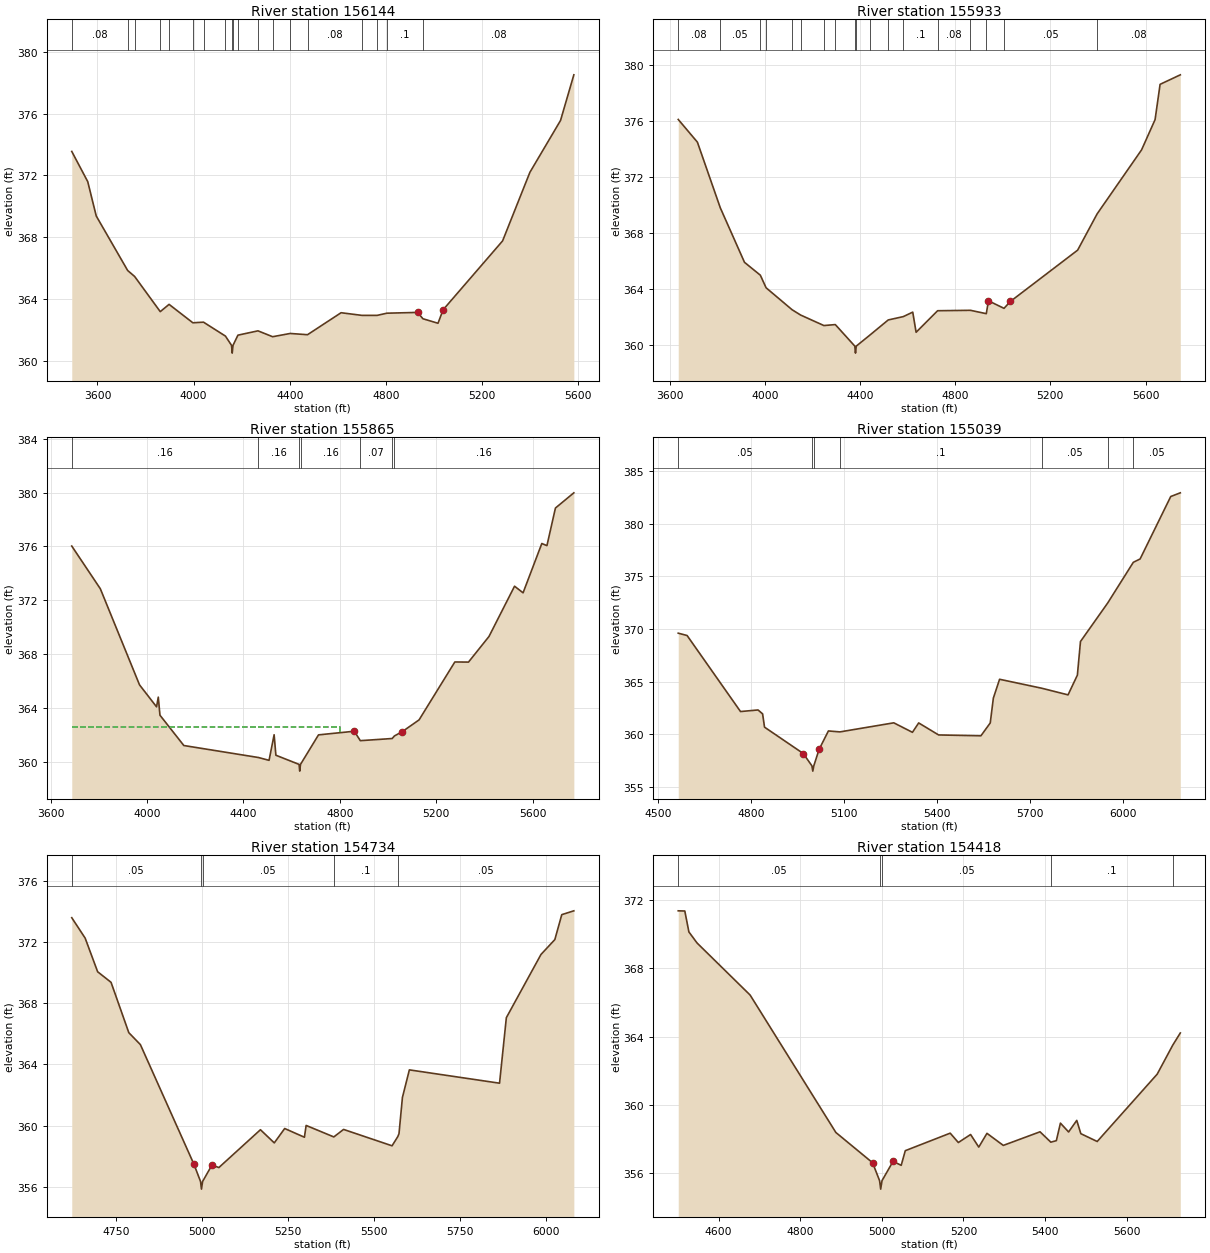
Type RM Length L Ch R = 1 ,156144  ,211,211,211
BEGIN DESCRIPTION:
Mapping XS 0f266a3b
END DESCRIPTION:
XS GIS Cut Line= 4
      2198205.55     13230122.91      2197687.46     13229598.24
      2196923.57     13228843.03      2196744.13     13228632.72
#Sta/Elev= 30
  3493.3  373.55  3559.7   371.6  3595.1  369.38  3725.7  365.86  3754.9  365.47
  3861.3   363.2    3898  363.67  3996.9  362.48  4041.2  362.52  4132.4  361.62
  4157.8  361.02  4160.5  360.52  4163.8  361.02  4184.3  361.68  4267.6  361.96
  4328.7  361.58  4401.7  361.79  4473.7  361.71  4613.3  363.13  4699.3  362.96
  4763.6  362.96  4803.8   363.1  4931.5  363.15  4953.8  362.74  5016.4  362.45
  5037.6  363.32    5285  367.77  5398.5   372.2  5525.9  375.55  5581.3   378.5
#Mann= 19 ,-1 , 0
  3493.3     .08       0  3725.7      .1       0  3754.9     .08       0
  3861.3     .05       0    3898     .08       0  3996.9     .05       0
  4041.2     .08       0  4132.4      .1       0  4157.8     .07       0
  4163.8      .1       0  4184.3     .08       0  4267.6      .1       0
  4328.7     .08       0  4401.7      .1       0  4473.7     .08       0
  4699.3      .1       0  4763.6     .08       0  4803.8      .1       0
  4953.8     .08       0
Bank Sta=4931.5,5037.6
XS Rating Curve= 0 ,0
Exp/Cntr=0.3,0.1

Type RM Length L Ch R = 1 ,155933  ,68,68,68
BEGIN DESCRIPTION:
Mapping XS b992636e
END DESCRIPTION:
XS GIS Cut Line= 4
      2198291.52      13230096.9      2197735.21     13229550.49
       2197001.7     13228786.61      2196803.49     13228601.08
#Sta/Elev= 30
  3635.9   376.1  3716.4  374.48  3812.6  369.79  3914.4  365.89    3981  364.97
  4005.2  364.07  4114.6   362.5  4150.6  362.12  4248.3  361.37  4296.1  361.44
  4378.1   359.9  4380.9   359.4  4384.1   359.9  4440.8  360.68  4518.4  361.77
  4581.9  362.01  4621.6  362.33  4635.7  360.89    4726  362.43  4864.1  362.46
  4930.7  362.22  4939.8  363.14  5005.2   362.6  5031.7  363.09  5314.7  366.76
  5396.5  369.35  5583.5  373.93  5640.2  376.09  5661.2  378.61  5746.2  379.29
#Mann= 18 ,-1 , 0
  3635.9     .08       0  3812.6     .05       0    3981     .08       0
  4005.2     .05       0  4114.6     .08       0  4150.6     .05       0
  4248.3     .08       0  4296.1     .05       0  4378.1     .07       0
  4384.1     .05       0  4440.8      .1       0  4518.4     .08       0
  4581.9      .1       0    4726     .08       0  4864.1     .05       0
  4930.7     .08       0  5005.2     .05       0  5396.5     .08       0
Bank Sta=4939.8,5031.7
XS Rating Curve= 0 ,0
Exp/Cntr=0.3,0.1

Type RM Length L Ch R = 1 ,155865  ,826,826,826
BEGIN DESCRIPTION:
Mapping XS 554749d8
END DESCRIPTION:
XS GIS Cut Line= 4
      2198319.64     13230072.64      2197778.61     13229550.49
      2197097.19     13228816.99      2196862.28     13228584.33
#Sta/Elev= 30
  3687.8  376.03  3806.4  372.86    3969  365.73  4039.7   364.1  4046.9  364.82
  4053.8  363.48  4152.9  361.23  4462.6  360.34  4506.6  360.13  4527.6  362.03
  4534.9  360.51  4631.1  359.83  4633.9  359.33  4637.1  359.83  4711.8  362.02
  4860.4  362.29  4885.3  361.59  5017.6  361.75  5026.9  361.94  5058.7  362.25
  5129.1  363.13  5277.6  367.43  5334.3  367.42  5419.3  369.32  5525.4  373.05
  5560.8  372.56  5638.6  376.22  5659.8  376.06  5695.1  378.85  5771.5  379.98
#Mann= 7 ,-1 , 0
  3687.8     .16       0  4462.6     .16       0  4631.1     .16       0
  4637.1     .16       0  4885.3     .07       0  5017.6     .16       0
  5026.9     .16       0
#XS Ineff= 2 , 0
         4802.61  362.57
Permanent Ineff=
       F       F
Bank Sta=4860.4,5058.7
XS Rating Curve= 0 ,0
Exp/Cntr=0.3,0.1

Type RM Length L Ch R = 1 ,155039  ,305,305,305
BEGIN DESCRIPTION:
Mapping XS fe4f35f8
END DESCRIPTION:
XS GIS Cut Line= 3
       2198249.9     13229914.29      2198071.92     13229662.52
      2197950.39     13228356.08
#Sta/Elev= 30
  4565.6   369.6  4594.2  369.38  4766.6  362.17  4823.2  362.32  4837.9  361.95
  4844.1  360.69  4969.1  358.19  4997.1  357.02  4999.9  356.52  5003.1  357.02
  5020.2  358.58  5050.3  360.33  5087.4  360.24  5261.3   361.1  5321.5   360.2
  5341.6  361.09    5406  359.95  5542.5  359.87  5572.6  361.09  5582.6  363.44
  5602.7  365.23  5738.9  364.38  5823.7  363.75  5853.8  365.62  5863.8  368.81
  5951.6  372.46  6034.3  376.32  6056.3  376.64  6155.1  382.56    6186  382.91
#Mann= 7 ,-1 , 0
  4565.6     .05       0  4997.1    .035       0  5003.1     .05       0
  5087.4      .1       0  5738.9     .05       0  5951.6      .1       0
  6034.3     .05       0
Bank Sta=4969.1,5020.2
XS Rating Curve= 0 ,0
Exp/Cntr=0.3,0.1

Type RM Length L Ch R = 1 ,154734  ,316,316,316
BEGIN DESCRIPTION:
Mapping XS 95adb2b8
END DESCRIPTION:
XS GIS Cut Line= 2
      2198397.44     13229931.58      2198215.16       13228482.
#Sta/Elev= 30
  4621.2  373.58  4660.1  372.25  4696.5  370.05  4735.5  369.36  4787.2  366.07
  4820.9  365.29  4976.6  357.48  4995.9  356.35  4998.6  355.85  5001.9  356.35
  5029.1  357.42  5049.3  357.26  5170.2  359.73  5210.5  358.87  5240.8  359.81
  5298.2  359.24  5303.2  360.01  5383.8  359.26  5412.1  359.75  5553.2  358.68
  5569.9  359.28  5573.4  359.47  5583.4  361.84  5603.6  363.64    5866  362.77
  5885.8  367.05  5986.6  371.18  6026.9  372.15  6047.1  373.78  6082.2  374.03
#Mann= 5 ,-1 , 0
  4621.2     .05       0  4995.9     .03       0  5001.9     .05       0
  5383.8      .1       0  5569.9     .05       0
Bank Sta=4976.6,5029.1
XS Rating Curve= 0 ,0
Exp/Cntr=0.3,0.1

Type RM Length L Ch R = 1 ,154418  ,400,400,400
BEGIN DESCRIPTION:
Mapping XS 434d05d0
END DESCRIPTION:
XS GIS Cut Line= 3
       2198618.8     13229922.92      2198649.18     13228811.82
      2198696.94     13228703.28
#Sta/Elev= 30
  4501.1  371.39  4517.2  371.38  4527.2  370.15  4547.2   369.5  4677.2  366.44
  4887.3  358.36  4977.3  356.58  4994.4  355.53  4997.1  355.03  5000.4  355.53
  5027.4  356.66  5047.4  356.43  5057.4  357.29  5167.4  358.32  5187.4  357.77
  5217.4  358.24  5237.4   357.5  5257.5  358.31  5297.5   357.6  5387.5   358.4
    5414  357.79  5427.5  357.88  5437.5  358.91  5457.5  358.39  5477.5  359.07
  5487.5  358.29  5527.6  357.83  5674.6  361.79  5712.6  363.49  5731.2  364.21
#Mann= 5 ,-1 , 0
  4501.1     .05       0  4994.4    .035       0  5000.4     .05       0
    5414      .1       0  5712.6     .05       0
Bank Sta=4977.3,5027.4
XS Rating Curve= 0 ,0
Exp/Cntr=0.3,0.1

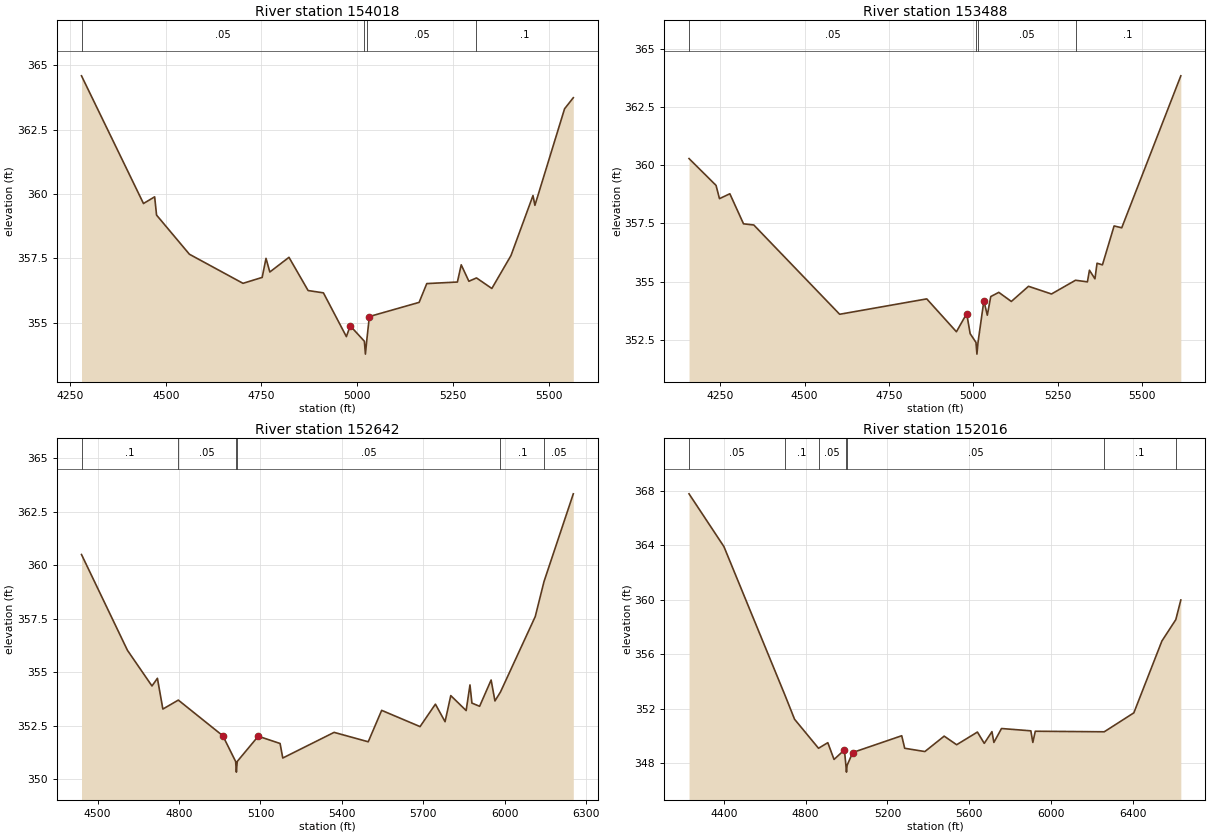
Type RM Length L Ch R = 1 ,154018  ,530,530,530
BEGIN DESCRIPTION:
Mapping XS c67934db
END DESCRIPTION:
XS GIS Cut Line= 2
      2199000.74     13230048.78      2199013.76     13228764.05
#Sta/Elev= 30
  4279.8  364.59  4441.7  359.63  4470.9  359.89  4475.9  359.18  4561.7  357.66
  4701.7  356.53  4751.8  356.76  4761.8   357.5  4771.8  356.97  4821.8  357.54
  4871.8  356.25  4911.8  356.16  4971.8  354.46  4981.8  354.88  5018.8  354.28
  5021.5  353.78  5024.8  354.28  5031.8  355.24  5161.8  355.79  5181.8  356.52
  5261.8  356.58  5271.8  357.25  5291.8  356.61  5311.7  356.74  5351.8  356.33
  5401.8  357.61  5459.3  359.94  5464.3  359.56  5541.8  363.31  5564.6  363.74
#Mann= 4 ,-1 , 0
  4279.8     .05       0  5018.8    .035       0  5024.8     .05       0
  5311.7      .1       0
Bank Sta=4981.8,5031.8
XS Rating Curve= 0 ,0
Exp/Cntr=0.3,0.1

Type RM Length L Ch R = 1 ,153488  ,846,846,846
BEGIN DESCRIPTION:
Mapping XS 6f6c7748
END DESCRIPTION:
XS GIS Cut Line= 3
      2199360.99     13230135.58       2199556.3      13229111.3
      2199374.02     13228738.07
#Sta/Elev= 30
  4157.3  360.28  4237.4  359.13  4247.6  358.56  4278.3  358.77  4318.9  357.48
  4349.4  357.43  4603.9   353.6  4862.1  354.26  4950.1  352.85  4980.6  353.63
  4990.8  352.77  5008.1  352.39  5010.9  351.89  5014.1  352.39  5031.5  354.18
  5041.7  353.56  5051.9  354.36  5075.7  354.54  5112.9  354.15  5163.8   354.8
  5231.9  354.47  5303.2  355.06  5338.5  354.99  5344.5  355.49  5360.8  355.12
    5367  355.79    5383  355.72  5417.6  357.39  5440.2  357.31  5615.4  363.83
#Mann= 4 ,-1 , 0
  4157.3     .05       0  5008.1    .035       0  5014.1     .05       0
  5303.2      .1       0
Bank Sta=4980.6,5031.5
XS Rating Curve= 0 ,0
Exp/Cntr=0.3,0.1

Type RM Length L Ch R = 1 ,152642  ,626,626,626
BEGIN DESCRIPTION:
Mapping XS f19e88e7
END DESCRIPTION:
XS GIS Cut Line= 3
      2200194.32     13230235.42      2200107.51     13229245.85
      2199535.54     13228660.88
#Sta/Elev= 30
  4440.9   360.5  4610.1  356.02  4700.5  354.35  4720.5  354.71  4740.6  353.27
  4797.5  353.69  4961.5  352.02  5008.6  350.82  5011.4  350.32  5014.6  350.82
    5092     352  5172.3  351.66  5182.3  350.98  5371.3  352.18  5497.1  351.74
  5546.5  353.21  5687.9  352.45  5744.5   353.5    5780  352.68  5801.1   353.9
  5857.7   353.2  5871.8   354.4    5879  353.55  5907.3   353.4  5949.7  354.63
  5963.8  353.65  5984.2  354.07  6112.3   357.6  6144.6  359.24  6252.4  363.34
#Mann= 6 ,-1 , 0
  4440.9      .1       0  4797.5     .05       0  5008.6     .03       0
  5014.6     .05       0  5984.2      .1       0  6144.6     .05       0
Bank Sta=4961.5,5092
XS Rating Curve= 0 ,0
Exp/Cntr=0.3,0.1

Type RM Length L Ch R = 1 ,152016  ,724,724,724
BEGIN DESCRIPTION:
Mapping XS 8e58487b
END DESCRIPTION:
XS GIS Cut Line= 3
      2200844.56     13230244.71      2200584.13     13228777.65
      2199742.52     13228421.92
#Sta/Elev= 30
  4230.3  367.76  4400.8  363.89  4699.4  352.98  4746.1  351.22  4863.2  349.09
  4908.6   349.5  4939.1  348.27  4989.8  348.97    4997  347.84  4999.8  347.34
    5003  347.84  5030.5  348.78  5269.9  350.01  5284.4  349.09    5383  348.85
  5477.4  349.98  5538.3  349.35  5639.9  350.28  5673.3  349.45  5710.9  350.31
  5720.3  349.52  5757.6  350.54    5901  350.37  5910.7  349.52  5922.7  350.34
  6259.8   350.3  6404.4  351.69  6541.5  356.96  6609.5  358.53    6634  359.97
#Mann= 7 ,-1 , 0
  4230.3     .05       0  4699.4      .1       0  4863.2     .05       0
    4997    .035       0    5003     .05       0  6259.8      .1       0
  6609.5     .05       0
Bank Sta=4989.8,5030.5
XS Rating Curve= 0 ,0
Exp/Cntr=0.3,0.1