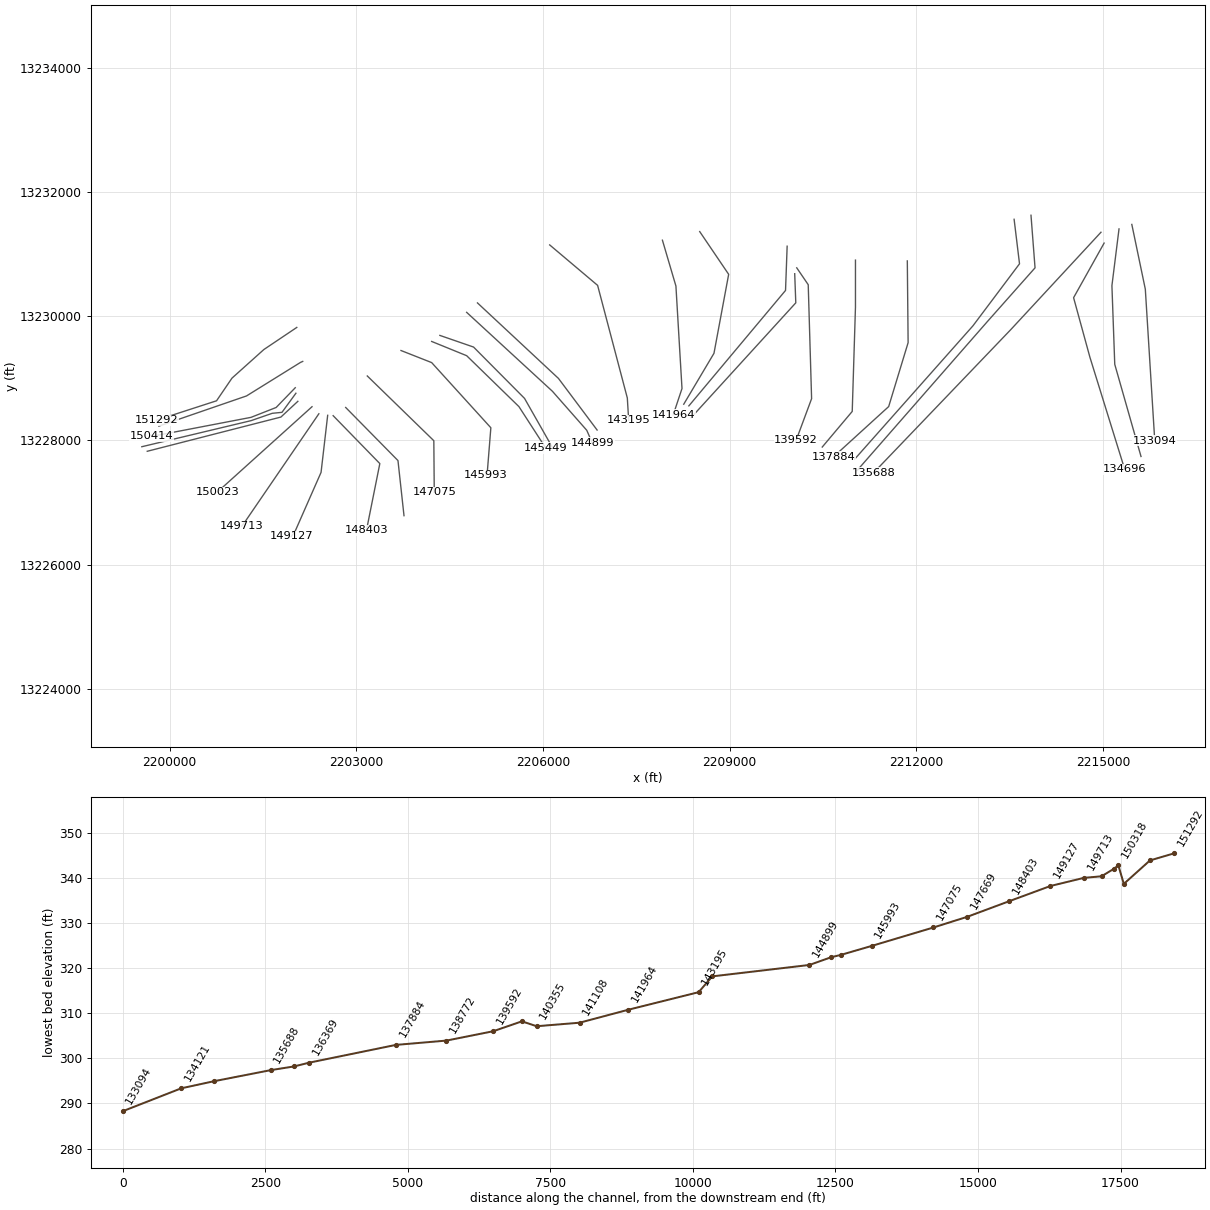
HEC-RAS study RAMIRENA CREEK.prj: RAMIRENA CREEK Base Level Engineering

--- RAMIRENA CREEK.g01 (geometry) --- (continued)

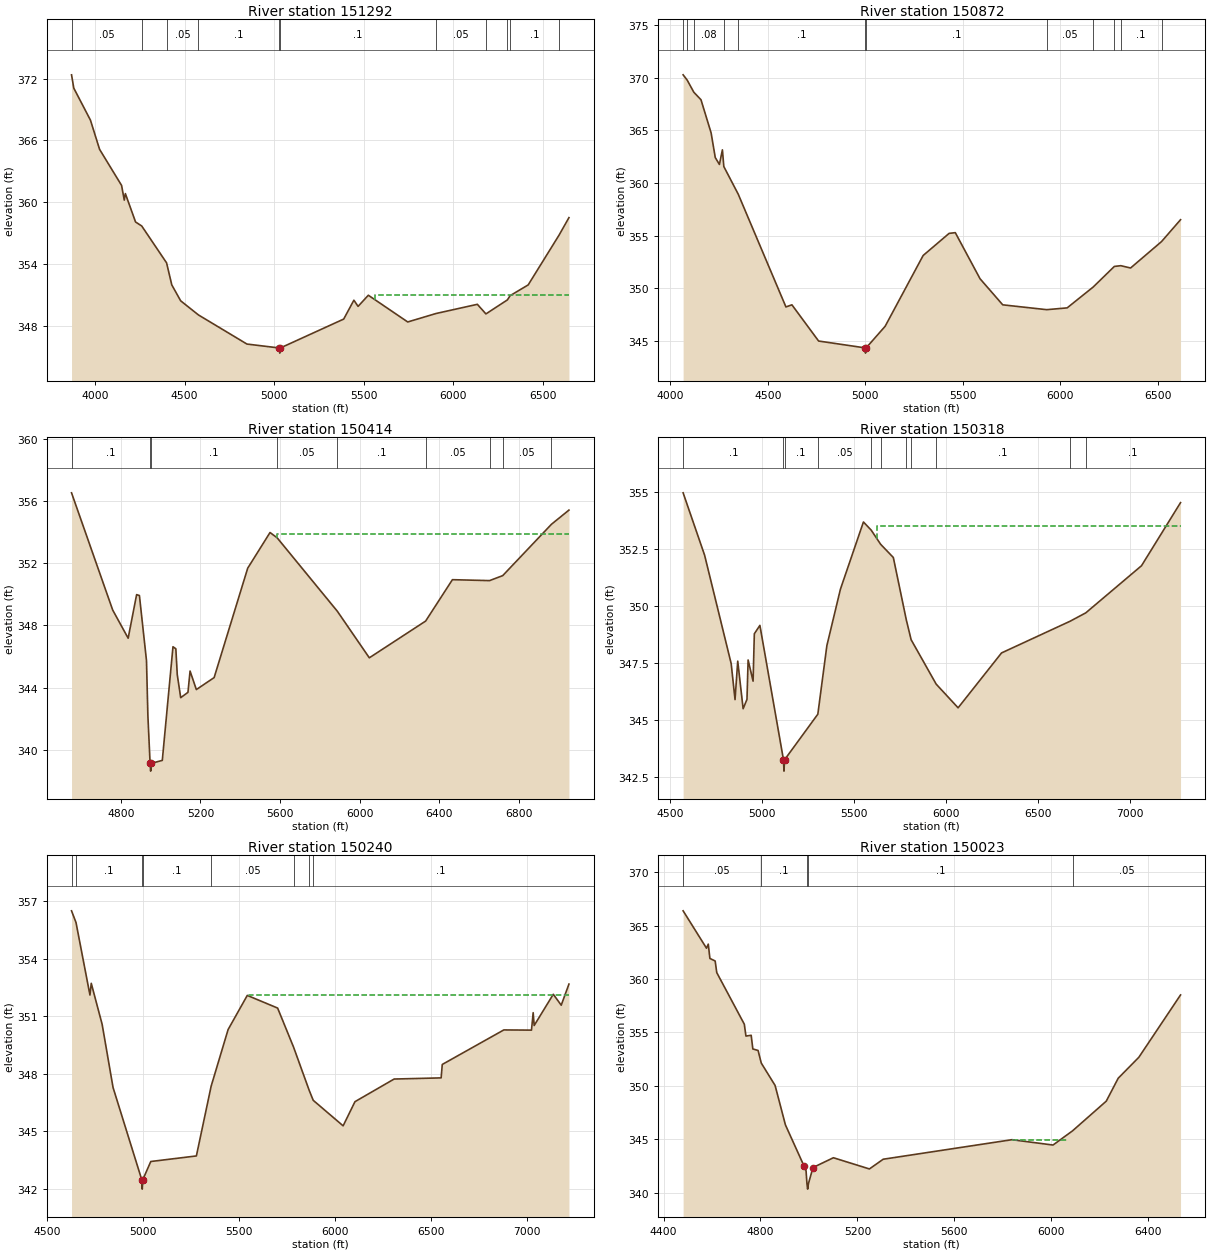
Type RM Length L Ch R = 1 ,151292  ,420,420,420
BEGIN DESCRIPTION:
Mapping XS 0f7b8d0c
END DESCRIPTION:
XS GIS Cut Line= 5
      2202042.47     13229819.32      2201512.95     13229463.42
       2201000.8     13229003.35      2200752.99     13228638.99
      2199791.12     13228327.04
#Sta/Elev= 30
  3868.1  372.36  3880.7  371.07  3973.7  367.97  4024.7  365.14  4147.7  361.64
  4162.6  360.22  4168.7  360.85  4225.7   358.1  4260.2  357.71  4398.9  354.14
  4428.1     352  4477.7  350.46    4577  349.09  4847.6  346.27  5028.4  345.89
  5031.2  345.39  5034.4  345.89  5388.3  348.69  5445.2  350.52  5468.5  349.92
  5525.9     351  5745.9  348.41  5904.1  349.23  6134.8  350.12  6182.6  349.19
  6302.7  350.55  6317.9  350.96  6418.7     352  6590.6  356.81  6646.4  358.52
#Mann= 11 ,-1 , 0
  3868.1     .05       0  4260.2     .08       0  4398.9     .05       0
    4577      .1       0  5028.4     .07       0  5034.4      .1       0
  5904.1     .05       0  6182.6      .1       0  6302.7     .05       0
  6317.9      .1       0  6590.6     .05       0
#XS Ineff= 2 , 0
                         5561.32          351.04
Permanent Ineff=
       F       F
Bank Sta=5028.4,5034.4
XS Rating Curve= 0 ,0
Exp/Cntr=0.3,0.1

Type RM Length L Ch R = 1 ,150872  ,458,458,458
BEGIN DESCRIPTION:
Mapping XS aae3e594
END DESCRIPTION:
XS GIS Cut Line= 4
      2202137.99     13229272.46      2202101.42       13229256.
      2201234.76     13228717.12      2199825.44     13228231.45
#Sta/Elev= 30
  4065.4  370.28  4086.2  369.78  4120.1  368.63    4157  367.91    4209  364.76
  4230.2  362.42  4251.5  361.76  4266.8  363.15  4274.2  361.56  4348.2  358.93
  4592.7  348.22  4623.4  348.42  4760.3  344.98  4998.2  344.33  5000.9  343.83
  5004.2  344.33  5101.5  346.38  5296.5  353.11  5429.6  355.21  5461.4  355.28
  5588.3   350.9  5704.7  348.42    5930  347.96  6035.1  348.13  6168.5  350.11
  6277.2  352.07  6310.4  352.14  6360.4  351.92  6519.1  354.43  6616.7  356.51
#Mann= 12 ,-1 , 0
  4065.4     .08       0  4086.2     .05       0  4120.1     .08       0
  4274.2     .05       0  4348.2      .1       0  4998.2     .07       0
  5004.2      .1       0    5930     .05       0  6168.5      .1       0
  6277.2     .05       0  6310.4      .1       0  6519.1     .05       0
#XS Ineff= 2 , 0
                         5463.41          355.21
Permanent Ineff=
       F       F
Bank Sta=4998.2,5004.2
XS Rating Curve= 0 ,0
Exp/Cntr=0.3,0.1

Type RM Length L Ch R = 1 ,150414  ,96,96,96
BEGIN DESCRIPTION:
Mapping XS e50ce3b8
END DESCRIPTION:
XS GIS Cut Line= 4
        2202018.       13228849.       2201710.7     13228531.29
      2201306.81      13228372.5      2199712.75     13228066.27
#Sta/Elev= 30
  4552.1  356.52  4758.9  348.99  4836.6  347.18  4879.1  349.98  4893.2  349.92
  4928.7  345.74  4935.7  342.21  4946.8  339.14  4949.6  338.64  4952.8  339.14
  5008.1  339.33  5061.8  346.63  5076.2   346.5  5083.3  344.84  5100.6  343.36
    5137   343.7  5147.7  345.07  5179.2  343.88  5268.6  344.65  5437.3  351.68
  5549.4  353.97  5585.2  353.63  5887.7  348.91  6048.3  345.92  6331.2  348.28
  6465.8  350.94  6652.3  350.88  6718.5   351.2  6963.4   354.5  7051.3  355.41
#Mann= 9 ,-1 , 0
  4552.1      .1       0  4946.8     .07       0  4952.8      .1       0
  5585.2     .05       0  5887.7      .1       0  6331.2     .05       0
  6652.3      .1       0  6718.5     .05       0  6963.4      .1       0
#XS Ineff= 2 , 0
                         5583.54          353.89
Permanent Ineff=
       F       F
Bank Sta=4946.8,4952.8
XS Rating Curve= 0 ,0
Exp/Cntr=0.3,0.1

Type RM Length L Ch R = 1 ,150318  ,78,78,78
BEGIN DESCRIPTION:
Mapping XS 4345e4a8
END DESCRIPTION:
XS GIS Cut Line= 5
      2202028.41     13228760.45      2201804.45     13228453.16
       2201648.2     13228437.54      2201308.11     13228319.55
      2199551.54     13227899.71
#Sta/Elev= 30
  4569.8  354.97  4686.6  352.23    4831  347.47  4851.9  345.89  4866.6  347.58
  4895.9  345.49  4916.8   345.9    4923  347.63    4950   346.7  4956.8  348.78
    4987  349.15  5115.2  343.25  5117.9  342.75  5121.2  343.25  5301.9  345.25
    5351  348.26  5424.7  350.74  5549.7  353.69  5592.1  353.33  5643.3  352.71
  5712.2  352.13  5782.8  349.39  5808.9  348.52  5945.1  346.57  6064.2  345.53
  6300.3  347.94  6672.4  349.33  6758.2   349.7  7061.1  351.77  7273.1  354.54
#Mann= 11 ,-1 , 0
  4569.8      .1       0  5115.2     .07       0  5121.2      .1       0
  5301.9     .05       0  5592.1      .1       0  5643.3     .05       0
  5782.8      .1       0  5808.9     .05       0  5945.1      .1       0
  6672.4     .05       0  6758.2      .1       0
#XS Ineff= 2 , 0
                         5624.38          353.53
Permanent Ineff=
       F       F
Bank Sta=5115.2,5121.2
XS Rating Curve= 0 ,0
Exp/Cntr=0.3,0.1

Type RM Length L Ch R = 1 ,150240  ,217,217,217
BEGIN DESCRIPTION:
Mapping XS da6abbcc
END DESCRIPTION:
XS GIS Cut Line= 3
      2202059.64     13228630.22      2201787.26     13228377.16
      2199638.81     13227826.48
#Sta/Elev= 30
  4628.2  356.49  4651.5  355.88  4724.1   352.1  4730.9  352.71  4787.6  350.57
  4844.3  347.28  4993.5  342.48  4996.3  341.98  4999.5  342.48  5040.8  343.42
  5278.2  343.71  5355.1  347.35  5443.4   350.3  5543.2  352.08  5701.2  351.42
  5783.9  349.39  5866.3  347.11  5886.6  346.61  6042.2  345.28  6103.9  346.54
  6307.8  347.72  6552.5  347.78  6558.3  348.48  6878.8  350.28  7022.9  350.27
  7031.6  351.18  7036.8  350.51  7136.4  352.14  7177.7  351.57  7217.9  352.67
#Mann= 8 ,-1 , 0
  4628.2     .05       0  4651.5      .1       0  4993.5     .07       0
  4999.5      .1       0  5355.1     .05       0  5783.9      .1       0
  5866.3     .05       0  5886.6      .1       0
#XS Ineff= 2 , 0
                         5549.75          352.12
Permanent Ineff=
       F       F
Bank Sta=4993.5,4999.5
XS Rating Curve= 0 ,0
Exp/Cntr=0.3,0.1

Type RM Length L Ch R = 1 ,150023  ,310,310,310
BEGIN DESCRIPTION:
Mapping XS 17fc6891
END DESCRIPTION:
XS GIS Cut Line= 2
      2202287.48     13228543.49      2200763.26     13227168.15
#Sta/Elev= 30
  4480.8  366.39  4577.2  362.89  4584.6  363.27  4591.3  361.93    4613  361.69
  4619.7   360.6  4733.3  355.77  4740.1  354.66  4761.7  354.73  4768.5  353.45
  4790.1  353.31  4803.3  352.13  4860.4  350.03    4903  346.34  4980.7  342.44
  4988.2  342.03  4991.9  340.82  4994.7  340.32  4997.9  340.82  5016.6  342.34
    5101  343.26  5249.7  342.21  5306.5  343.12  5837.9  344.95  6007.5  344.45
  6088.1  345.78  6227.2  348.56  6276.6  350.71  6361.7  352.67  6533.8  358.51
#Mann= 5 ,-1 , 0
  4480.8     .05       0  4803.3      .1       0  4991.9     .07       0
  4997.9      .1       0  6088.1     .05       0
#XS Ineff= 1 ,-1
 5838.29 6070.92  344.95
Permanent Ineff=
       F
Bank Sta=4980.7,5016.6
XS Rating Curve= 0 ,0
Exp/Cntr=0.3,0.1

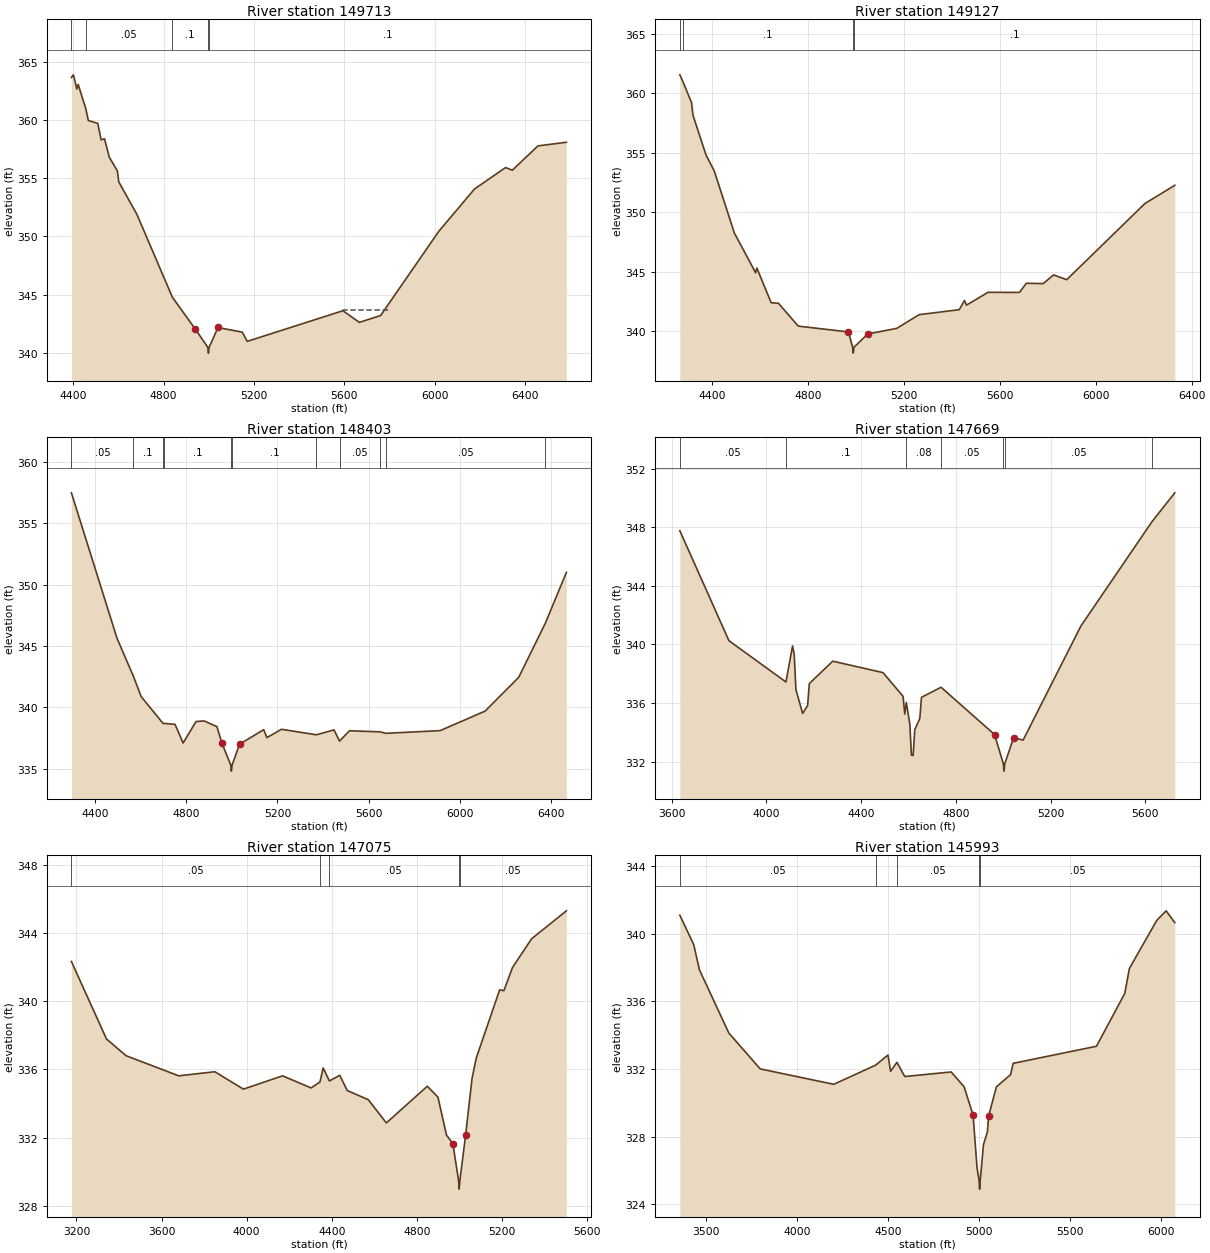
Type RM Length L Ch R = 1 ,149713  ,586,586,586
BEGIN DESCRIPTION:
Mapping XS 1638c2e3
END DESCRIPTION:
XS GIS Cut Line= 3
      2202397.39      13228430.1      2201213.46     13226696.74
      2201156.73     13226622.29
#Sta/Elev= 30
  4391.3  363.63  4400.4  363.86  4415.3  362.65  4421.4  363.03    4455  360.96
  4466.2  359.94  4508.1  359.69    4523  358.28    4538  358.37  4558.9   356.8
  4594.8  355.61  4601.1  354.67  4681.5  351.88  4838.5  344.77  4940.2  342.03
  4995.5  340.47  4998.3  339.97  5001.5  340.47  5040.5  342.17  5148.2  341.77
  5170.3  340.98  5594.1  343.61  5666.8  342.61  5761.2   343.2  6018.5  350.42
    6177  354.06  6314.5   355.9  6344.4  355.67  6458.1  357.76    6584  358.07
#Mann= 5 ,-1 , 0
  4391.3      .1       0    4455     .05       0  4838.5      .1       0
  4995.5     .07       0  5001.5      .1       0
#XS Ineff= 1 ,-1
 5593.97 5795.68  343.63
Permanent Ineff=
       F
Bank Sta=4940.2,5040.5
XS Rating Curve= 0 ,0
Exp/Cntr=0.3,0.1

Type RM Length L Ch R = 1 ,149127  ,724,724,724
BEGIN DESCRIPTION:
Mapping XS d6912afa
END DESCRIPTION:
XS GIS Cut Line= 4
      2202539.15     13228405.23      2202432.82      13227487.2
      2202018.09     13226544.32       2201954.3     13226455.72
#Sta/Elev= 30
  4266.4  361.55  4277.6  361.06  4315.1  359.22  4321.2  358.16  4375.5  354.82
    4410  353.47  4493.7  348.26  4582.5  344.92  4587.5  345.32  4647.3   342.4
  4677.5  342.36    4760  340.44  4969.4  339.95  4986.6  338.67  4989.3  338.17
  4992.6  338.67    5050  339.78  5170.8  340.25  5263.6   341.4  5431.3  341.82
  5453.1  342.59  5461.3   342.2  5551.5  343.28  5682.3  343.27  5711.1  344.04
  5780.9  344.01  5824.6  344.74  5879.2  344.34  6205.3  350.74  6329.8  352.27
#Mann= 4 ,-1 , 0
  4266.4     .05       0  4277.6      .1       0  4986.6     .07       0
  4992.6      .1       0
Bank Sta=4969.4,5050
XS Rating Curve= 0 ,0
Exp/Cntr=0.3,0.1

Type RM Length L Ch R = 1 ,148403  ,734,734,734
BEGIN DESCRIPTION:
Mapping XS 9c9f5f5d
END DESCRIPTION:
XS GIS Cut Line= 3
      2202627.35     13228399.36      2203377.37     13227628.51
      2203162.41     13226553.72
#Sta/Elev= 30
  4296.1  357.48  4496.1  345.63  4567.4  342.56  4602.3  340.87  4697.7   338.7
  4701.3  338.69  4750.7  338.61  4786.2  337.09  4842.7  338.84    4878  338.89
  4934.6  338.43  4955.7  337.11  4995.2   335.3  4997.9   334.8  5001.2   335.3
  5033.6  336.99  5139.6  338.18  5153.8  337.53  5217.5  338.21  5370.8  337.76
  5448.1  338.16  5472.4  337.25  5516.1  338.09  5650.3     338  5675.1  337.88
  5913.8   338.1  6110.9  339.69  6258.8  342.45    6376  346.88  6467.7     351
#Mann= 11 ,-1 , 0
  4296.1     .05       0  4567.4      .1       0  4697.7     .05       0
  4701.3      .1       0  4995.2     .07       0  5001.2      .1       0
  5370.8     .08       0  5472.4     .05       0  5650.3      .1       0
  5675.1     .05       0    6376      .1       0
Bank Sta=4955.7,5033.6
XS Rating Curve= 0 ,0
Exp/Cntr=0.3,0.1

Type RM Length L Ch R = 1 ,147669  ,594,594,594
BEGIN DESCRIPTION:
Mapping XS 291d699c
END DESCRIPTION:
XS GIS Cut Line= 3
      2202828.78     13228531.26      2203669.04     13227677.12
      2203766.06     13226790.07
#Sta/Elev= 30
    3634  347.77  3841.4  340.26  4082.2  337.44  4110.1   339.9  4117.2   339.3
  4124.3  336.92  4152.6  335.29  4173.7  335.83  4180.9  337.33  4279.9  338.86
    4492  338.08  4576.9  336.46  4583.9  335.25  4590.5  336.04  4605.2   334.6
  4612.2  332.44  4619.3  332.42  4626.3  334.18  4647.6  334.95  4654.6  336.39
  4737.2  337.08  4963.2  333.85  5000.4  331.85  5003.2  331.35  5006.4  331.85
  5043.7  333.63  5083.9  333.47  5328.2  341.27  5627.7  348.38  5724.5  350.36
#Mann= 7 ,-1 , 0
    3634     .05       0  4082.2      .1       0  4590.5     .08       0
  4737.2     .05       0  5000.4    .035       0  5006.4     .05       0
  5627.7      .1       0
Bank Sta=4963.2,5043.7
XS Rating Curve= 0 ,0
Exp/Cntr=0.3,0.1

Type RM Length L Ch R = 1 ,147075  ,1082,1082,1082
BEGIN DESCRIPTION:
Mapping XS 43aa9ab2
END DESCRIPTION:
XS GIS Cut Line= 3
      2203176.01     13229038.21      2204245.42     13227996.57
      2204252.37     13227163.27
#Sta/Elev= 30
  3176.3  342.32  3341.1  337.78    3433   336.8  3680.6  335.62  3850.2  335.86
  3984.7  334.84  4168.6  335.62  4302.9  334.91  4344.3  335.26  4359.5  336.08
  4388.8  335.32  4437.2  335.65  4472.6  334.76  4571.6  334.22  4656.5  332.86
  4848.9  335.01  4898.9  334.37  4938.9  332.15  4968.9  331.65  4995.9  329.48
  4998.6  328.98  5001.9  329.48  5028.9  332.14  5058.9  335.45  5078.9  336.66
  5188.9  340.66  5208.9  340.61  5248.9  341.96  5338.9  343.65  5502.5  345.29
#Mann= 5 ,-1 , 0
  3176.3     .05       0  4344.3     .08       0  4388.8     .05       0
  4995.9    .035       0  5001.9     .05       0
Bank Sta=4968.9,5028.9
XS Rating Curve= 0 ,0
Exp/Cntr=0.3,0.1

Type RM Length L Ch R = 1 ,145993  ,544,544,544
BEGIN DESCRIPTION:
Mapping XS 9bfe001b
END DESCRIPTION:
XS GIS Cut Line= 5
      2203717.61     13229447.97       2204210.7     13229253.51
      2205162.09      13228204.9      2205106.54     13227510.45
      2205085.82      13227441.4
#Sta/Elev= 30
    3359   341.1    3435  339.37  3466.6  337.87  3627.9  334.13  3799.9  332.01
  4203.2   331.1  4432.5  332.23  4500.6  332.83  4514.8  331.87  4549.8   332.4
  4592.5  331.56  4847.2  331.83  4918.2  330.95  4967.5  329.27  4989.2  326.14
  5000.4   325.4  5003.1   324.9  5006.4   325.4  5024.3  327.53  5045.8  328.28
  5052.7  329.23  5095.3  330.95    5173  331.67  5187.2  332.34  5644.1  333.35
  5799.1  336.47  5824.6  337.95  5975.1   340.8  6026.2  341.36  6073.7  340.66
#Mann= 5 ,-1 , 0
    3359     .05       0  4432.5     .08       0  4549.8     .05       0
  5000.4    .035       0  5006.4     .05       0
Bank Sta=4967.5,5052.7
XS Rating Curve= 0 ,0
Exp/Cntr=0.3,0.1

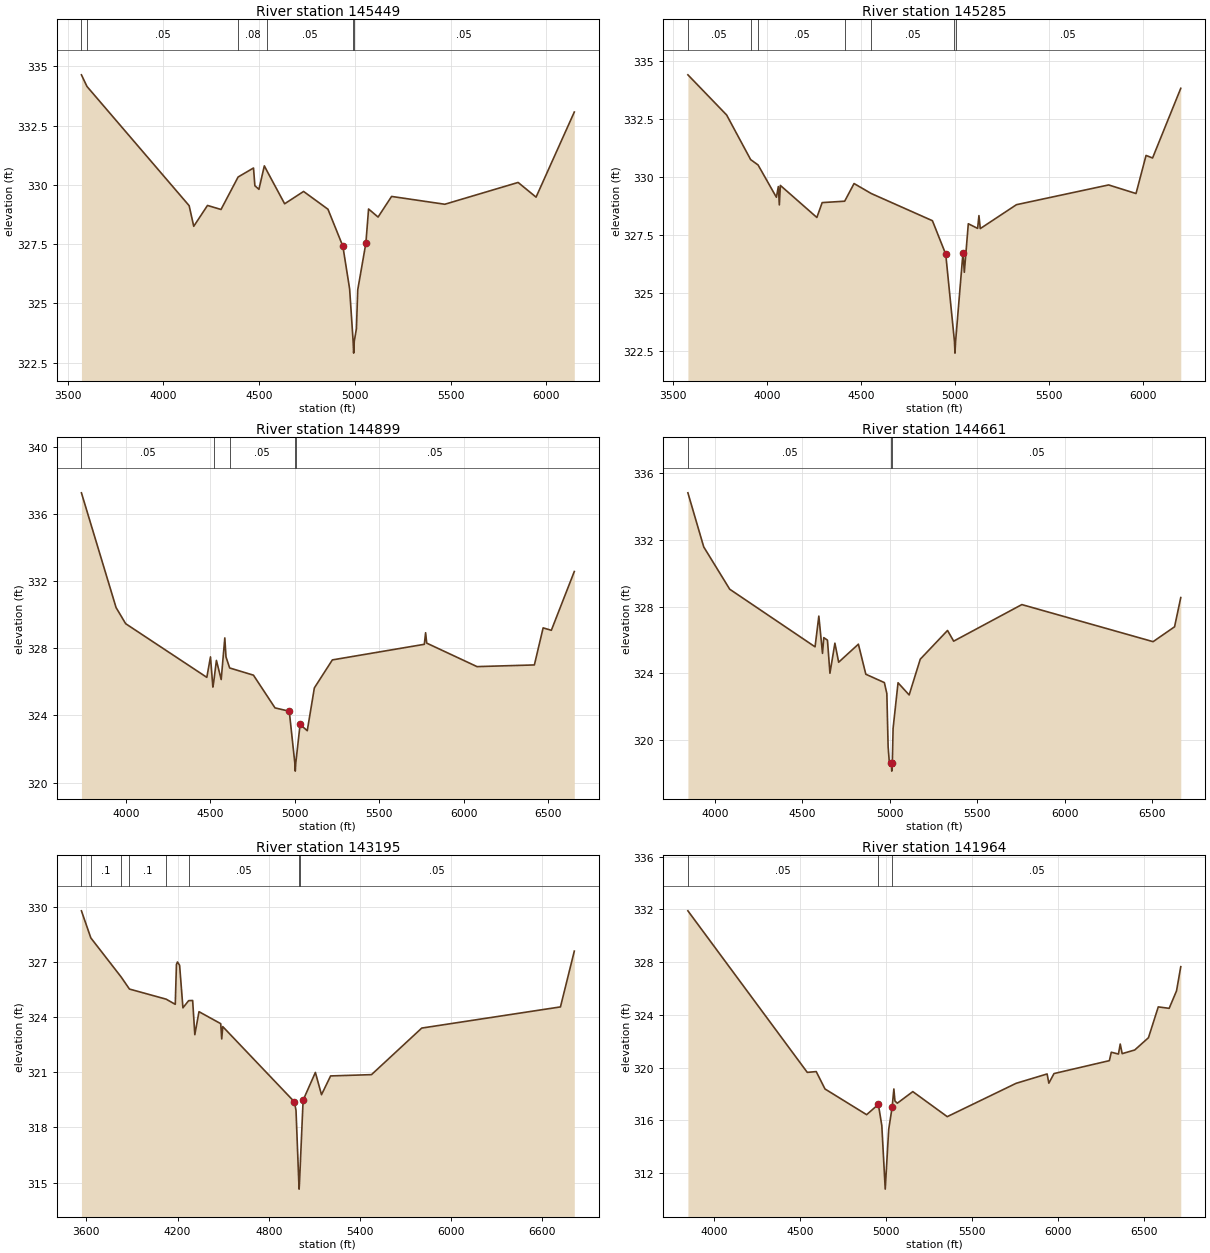
Type RM Length L Ch R = 1 ,145449  ,164,164,164
BEGIN DESCRIPTION:
Mapping XS 55a5a6d6
END DESCRIPTION:
XS GIS Cut Line= 4
       2204210.7     13229593.79       2204773.2     13229364.62
      2205613.48     13228545.18      2206044.04     13227878.51
#Sta/Elev= 30
  3571.8  334.64  3600.7  334.15  4134.5  329.12  4158.5  328.25  4230.3  329.13
    4301  328.96  4390.3  330.33  4470.7  330.71  4477.9  329.96    4499  329.81
  4527.3   330.8  4543.4  330.55  4633.3   329.2  4732.3  329.72  4859.6  328.97
  4937.5  327.41  4972.8  325.61  4991.1   323.4  4993.9   322.9  4997.1   323.4
  5008.3  323.93  5015.2  325.57  5057.7  327.54  5071.8  328.98  5121.4  328.64
    5192  329.51  5469.9  329.18    5853   330.1  5946.7  329.48  6146.5  333.07
#Mann= 6 ,-1 , 0
  3571.8     .08       0  3600.7     .05       0  4390.3     .08       0
  4543.4     .05       0  4991.1    .035       0  4997.1     .05       0
Bank Sta=4937.5,5057.7
XS Rating Curve= 0 ,0
Exp/Cntr=0.3,0.1

Type RM Length L Ch R = 1 ,145285  ,386,386,386
BEGIN DESCRIPTION:
Mapping XS e965f09a
END DESCRIPTION:
XS GIS Cut Line= 4
      2204342.65     13229691.01      2204884.31     13229503.51
      2205703.76     13228677.12      2206141.25     13227906.31
#Sta/Elev= 30
  3577.6  334.39  3783.9  332.66  3911.7  330.74  3951.1  330.51  4048.6  329.12
    4059  329.58  4064.3  328.79  4069.7  329.63    4264  328.25  4292.3  328.89
  4412.1  328.95    4462  329.71  4553.6  329.28  4879.1  328.11  4949.9  326.67
  4996.4  322.91  4999.1  322.41  5002.4  322.91  5041.8  326.74  5048.9  325.89
  5070.1  327.98  5119.6  327.78  5126.7  328.33  5133.7  327.77  5326.4   328.8
    5817  329.65  5962.7  329.28  6016.1  330.92  6050.8  330.81  6200.9  333.81
#Mann= 7 ,-1 , 0
  3577.6     .05       0  3911.7      .1       0  3951.1     .05       0
  4412.1     .08       0  4553.6     .05       0  4996.4    .035       0
  5002.4     .05       0
Bank Sta=4949.9,5041.8
XS Rating Curve= 0 ,0
Exp/Cntr=0.3,0.1

Type RM Length L Ch R = 1 ,144899  ,1704,1704,1704
BEGIN DESCRIPTION:
Mapping XS ac23d729
END DESCRIPTION:
XS GIS Cut Line= 4
      2204773.19     13230062.11      2206151.24     13228792.57
      2206703.68     13228164.31     2206791.292    13227964.034
#Sta/Elev= 30
  3735.6  337.27  3940.8  330.43  3997.5  329.47  4478.3  326.27  4499.9  327.49
  4514.1  325.69  4518.7  325.96  4535.1  327.28  4563.4  326.14  4584.8  328.62
  4591.8  327.49  4613.5  326.83  4754.5   326.4  4882.1  324.45  4966.6  324.25
  4999.3  321.18  5002.1  320.68  5005.3  321.18  5030.7  323.46  5073.2  323.09
  5115.2  325.64  5221.8  327.31  5766.5  328.24  5774.1  328.93  5780.7  328.31
  6078.7  326.91  6418.3  327.016470.238329.21996518.818329.07496654.845332.5787
#Mann= 5 ,-1 , 0
  3735.6     .05       0  4518.7      .1       0  4613.5     .05       0
  4999.3    .035       0  5005.3     .05       0
Bank Sta=4966.6,5030.7
XS Rating Curve= 0 ,0
Exp/Cntr=0.3,0.1

Type RM Length L Ch R = 1 ,144661  ,238,238,238
BEGIN DESCRIPTION:
Mapping XS df2b3163
END DESCRIPTION:
XS GIS Cut Line= 3
      2204946.84     13230213.98       2206248.9     13228998.74
      2206870.02      13228168.4
#Sta/Elev= 30
  3845.6  334.81  3936.2  331.57  4084.7  329.04  4572.7  325.59  4594.2  327.43
  4615.2   325.2  4622.6  326.14  4643.6  325.99  4657.7  324.01  4686.1  325.81
  4707.6  324.67  4820.4  325.75  4862.9  323.95  4968.9  323.45  4983.1  322.79
  4990.4  319.61  4997.3  318.67  5008.4  318.65  5011.2  318.15  5014.4  318.65
  5018.8  320.71  5047.1  323.44  5110.6  322.71  5174.1  324.85    5330  326.57
  5365.2  325.93    5755  328.12  6505.3   325.9  6628.1  326.79  6663.6  328.54
#Mann= 3 ,-1 , 0
  3845.6     .05       0  5008.4    .035       0  5014.4     .05       0
Bank Sta=5008.4,5014.4
XS Rating Curve= 0 ,0
Exp/Cntr=0.3,0.1

Type RM Length L Ch R = 1 ,143195  ,1231,1231,1231
BEGIN DESCRIPTION:
Mapping XS 2f4f06b1
END DESCRIPTION:
XS GIS Cut Line= 4
      2206107.85     13231147.16      2206878.24     13230496.13
      2207355.67     13228684.07      2207377.37     13228325.96
#Sta/Elev= 30
  3567.9  329.77  3629.6   328.3  3829.6  326.17  3883.6  325.52  4125.2  324.97
    4185  324.69  4192.7  326.86  4199.3  326.99  4213.6  326.81  4235.4   324.5
  4272.9  324.89  4299.3   324.9  4313.6  323.04    4341  324.29  4483.9  323.64
  4490.5  322.81  4497.3  323.48  4968.7  319.39  4979.1  318.92  4996.8  315.15
  4999.5  314.65  5002.8  315.15  5025.7  319.48  5106.4  320.99  5146.7  319.78
  5206.6   320.8  5475.5  320.87    5806   323.4  6718.1  324.55  6809.2  327.58
#Mann= 8 ,-1 , 0
  3567.9     .05       0  3629.6      .1       0  3829.6     .05       0
  3883.6      .1       0  4125.2     .08       0  4272.9     .05       0
  4996.8    .035       0  5002.8     .05       0
Bank Sta=4968.7,5025.7
XS Rating Curve= 0 ,0
Exp/Cntr=0.3,0.1

Type RM Length L Ch R = 1 ,141964  ,856,856,856
BEGIN DESCRIPTION:
Mapping XS 6664a9ba
END DESCRIPTION:
XS GIS Cut Line= 4
       2207919.9     13231223.14      2208136.92     13230485.28
      2208234.57     13228835.98      2208093.51     13228412.78
#Sta/Elev= 30
  3848.5  331.89    4543  319.63  4595.1  319.69  4646.1  318.37  4888.3  316.42
  4956.6   317.2  4976.7  315.59  4996.5  310.77  5016.7   315.3  5036.8  316.99
  5046.8  318.37    5053  317.46  5066.8  317.29    5157  318.17  5357.3  316.27
    5758   318.8  5938.3  319.51  5948.4  318.81  5978.4  319.54  6300.5  320.52
  6311.8  321.16  6353.2  321.02  6363.7  321.78    6375  321.05  6448.1  321.33
  6527.9  322.26  6585.1   324.6  6648.4  324.49  6691.3  325.82  6715.9  327.65
#Mann= 3 , 0 , 0
  3848.5     .05       0  4956.6    .035       0  5036.8     .05       0
Bank Sta=4956.6,5036.8
XS Rating Curve= 0 ,0
Exp/Cntr=0.3,0.1

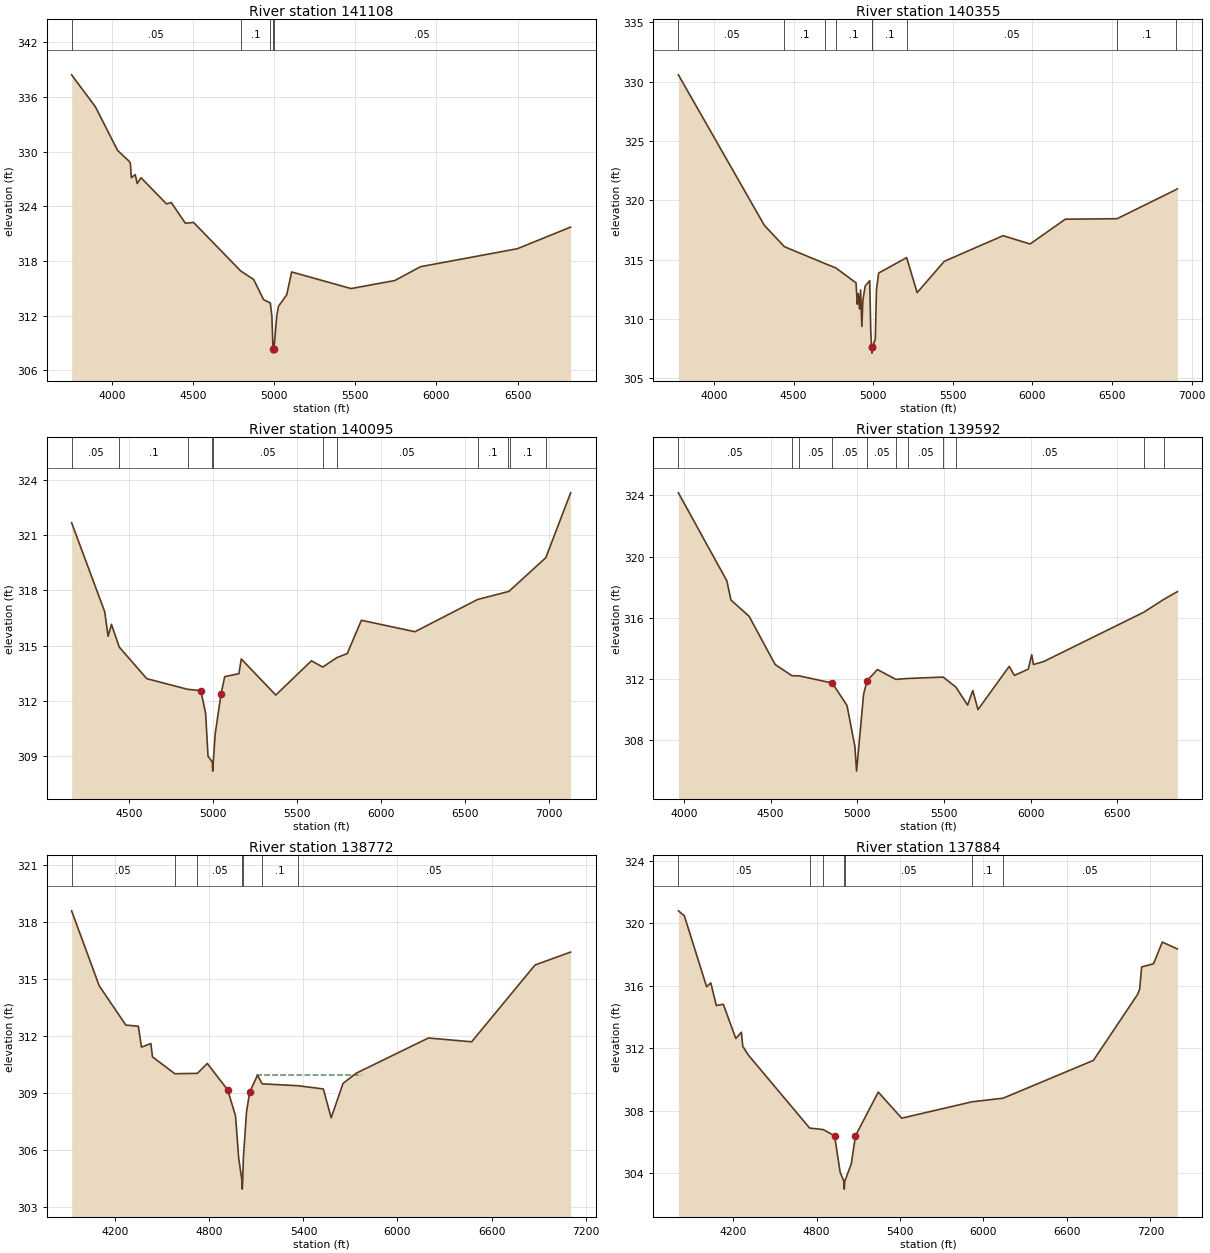
Type RM Length L Ch R = 1 ,141108  ,753,753,753
BEGIN DESCRIPTION:
Mapping XS 8aa6617f
END DESCRIPTION:
XS GIS Cut Line= 4
      2208519.47     13231361.48      2208984.75     13230673.98
      2208748.64     13229403.14      2208262.64     13228583.88
#Sta/Elev= 30
  3751.6  338.41  3898.1  334.91  4034.9  330.12  4107.4  328.91  4113.8  328.66
  4119.9  327.13  4143.6  327.47  4155.8  326.49  4179.7  327.12  4336.8  324.25
  4365.5  324.41  4452.4  322.14  4503.3  322.22  4793.1  316.91  4873.8  315.96
  4934.8  313.75  4976.3  313.39  4985.7  311.97  4992.8  308.39  4995.6  307.89
  4998.8  308.39  5016.2     312    5026  313.01  5077.2  314.28  5107.7  316.79
  5473.9  314.97    5743  315.85  5902.3  317.37  6498.6  319.34  6826.9  321.71
#Mann= 5 ,-1 , 0
  3751.6     .05       0  4793.1      .1       0  4976.3     .05       0
  4992.8    .035       0  4998.8     .05       0
Bank Sta=4992.8,4998.8
XS Rating Curve= 0 ,0
Exp/Cntr=0.3,0.1

Type RM Length L Ch R = 1 ,140355  ,260,260,260
BEGIN DESCRIPTION:
Mapping XS a0f2dd04
END DESCRIPTION:
XS GIS Cut Line= 3
      2209924.83     13231126.53      2209898.79     13230414.72
      2208344.97     13228557.08
#Sta/Elev= 30
  3776.6  330.57  4316.6  317.88  4442.8  316.08  4697.3  314.66    4766  314.29
  4892.4  313.03  4900.2  311.23  4906.7  312.13  4914.5  310.83    4921  312.44
  4928.8  309.35  4935.3  311.56  4949.6  312.76  4978.3  313.22  4984.8  308.99
  4989.6  307.61  4992.3  307.11  4995.6  307.61  5013.4  308.28  5020.6  312.44
  5034.2  313.86  5210.3  315.16  5276.2  312.21  5446.7  314.85  5815.9  317.01
  5985.5  316.31  6206.6   318.4  6531.5  318.44  6900.4  320.88  6910.7  320.96
#Mann= 9 ,-1 , 0
  3776.6     .05       0  4442.8      .1       0  4697.3     .05       0
    4766      .1       0  4989.6     .07       0  4995.6      .1       0
  5210.3     .05       0  6531.5      .1       0  6900.4     .05       0
Bank Sta=4989.6,4995.6
XS Rating Curve= 0 ,0
Exp/Cntr=0.3,0.1

Type RM Length L Ch R = 1 ,140095  ,503,503,503
BEGIN DESCRIPTION:
Mapping XS 193ec134
END DESCRIPTION:
XS GIS Cut Line= 3
      2210046.35     13230683.83      2210063.72     13230215.06
      2208379.69     13228366.11
#Sta/Elev= 30
  4160.2  321.68  4357.3  316.84  4377.3  315.51  4397.3  316.16  4444.1  314.92
  4607.5  313.21    4852  312.63  4929.5  312.56  4957.9  311.32  4972.1     309
  4997.4  308.69  5000.2  308.19  5003.4  308.69  5014.6   310.2  5049.8  312.39
  5071.4  313.32  5155.8  313.48    5170  314.28  5375.4  312.32  5587.6  314.18
  5654.9  313.84  5738.4  314.35  5800.4  314.57  5884.9  316.38  6203.8  315.76
  6576.8  317.51  6759.7  317.94  6766.7  317.98  6982.6  319.78  7130.2   323.3
#Mann= 11 ,-1 , 0
  4160.2     .05       0  4444.1      .1       0    4852     .05       0
  4997.4    .035       0  5003.4     .05       0  5654.9      .1       0
  5738.4     .05       0  6576.8      .1       0  6759.7     .05       0
  6766.7      .1       0  6982.6     .05       0
#XS Ineff= 2 , 0
                         5189.88          313.62
Permanent Ineff=
       F       F
Bank Sta=4929.5,5049.8
XS Rating Curve= 0 ,0
Exp/Cntr=0.3,0.1

Type RM Length L Ch R = 1 ,139592  ,820,820,820
BEGIN DESCRIPTION:
Mapping XS 79ab6bbc
END DESCRIPTION:
XS GIS Cut Line= 4
      2210079.19     13230778.25      2210263.65     13230506.98
      2210317.91     13228673.21       2210068.6     13228001.18
#Sta/Elev= 30
  3967.5  324.17  4247.3  318.42  4270.8  317.17  4375.7  316.11  4525.8  312.96
  4622.7  312.23  4664.1  312.22  4855.9  311.75  4940.6  310.28    4986  307.61
  4995.7     306    5036  311.01    5056   311.9    5116  312.63  5222.6  311.99
  5293.2  312.05  5495.1  312.14  5568.4  311.49  5636.3  310.31  5666.3  311.26
  5696.3  310.02  5876.4  312.84  5906.4  312.25  5986.4  312.66  6006.4   313.6
  6016.4  312.96  6076.5  313.16  6652.2  316.37  6770.7  317.23  6846.9  317.72
#Mann= 11 ,-1 , 0
  3967.5     .05       0  4622.7      .1       0  4664.1     .05       0
  4855.9     .05       0    5056     .05       0  5222.6      .1       0
  5293.2     .05       0  5495.1      .1       0  5568.4     .05       0
  6652.2      .1       0  6770.7     .05       0
Bank Sta=4855.9,5056
XS Rating Curve= 0 ,0
Exp/Cntr=0.3,0.1

Type RM Length L Ch R = 1 ,138772  ,888,888,888
BEGIN DESCRIPTION:
Mapping XS 50b553cc
END DESCRIPTION:
XS GIS Cut Line= 4
        2211023.     13230902.79        2211023.     13230147.57
      2210970.92     13228467.88      2210489.13     13227894.94
#Sta/Elev= 30
  3920.6  318.57  4096.5  314.63  4266.5  312.56  4346.5   312.5  4366.5   311.4
  4426.5  311.59  4436.5  310.89  4579.3     310  4723.3  310.02  4786.6  310.54
  4916.6  309.15  4966.7  307.78  4986.7  305.57  5006.6  304.43  5009.4  303.93
  5012.6  304.43  5016.7  305.58  5036.7  307.99  5056.7  309.03  5106.7  309.92
  5136.7  309.47  5364.1  309.37  5526.9   309.2    5577  307.68  5652.5  309.49
    5737  310.03  6197.3  311.88  6473.3  311.68  6877.8  315.72  7104.9   316.4
#Mann= 7 ,-1 , 0
  3920.6     .05       0  4579.3      .1       0  4723.3     .05       0
  5006.6    .035       0  5012.6     .05       0  5136.7      .1       0
  5364.1     .05       0
#XS Ineff= 1 ,-1
 5105.42 5774.45  309.92
Permanent Ineff=
       F
Bank Sta=4916.6,5056.7
XS Rating Curve= 0 ,0
Exp/Cntr=0.3,0.1

Type RM Length L Ch R = 1 ,137884  ,1515,1515,1515
BEGIN DESCRIPTION:
Mapping XS 6c1addda
END DESCRIPTION:
XS GIS Cut Line= 4
      2211856.34     13230889.76      2211869.36     13229574.65
      2211556.86     13228546.01      2210672.06     13227739.28
#Sta/Elev= 30
  3806.8  320.78  3849.7  320.46  4009.7  315.92  4039.7  316.17  4079.7  314.72
  4129.7   314.8  4219.7  312.61  4259.7  313.01  4269.7  312.11  4309.7  311.55
  4750.1  306.88  4848.5  306.78  4929.8  306.38  4969.8  304.05  4996.8  303.47
  4999.5  302.97  5002.8  303.47  5049.8  304.59  5079.8  306.38  5243.9  309.18
  5412.3  307.51  5918.6  308.56  6141.8  308.79  6790.7  311.21    7109  315.44
  7123.1  315.77  7137.3  317.19  7222.4  317.39    7286  318.78  7394.4  318.34
#Mann= 7 ,-1 , 0
  3806.8     .05       0  4750.1      .1       0  4848.5     .05       0
  4996.8    .035       0  5002.8     .05       0  5918.6      .1       0
  6141.8     .05       0
Bank Sta=4929.8,5079.8
XS Rating Curve= 0 ,0
Exp/Cntr=0.3,0.1

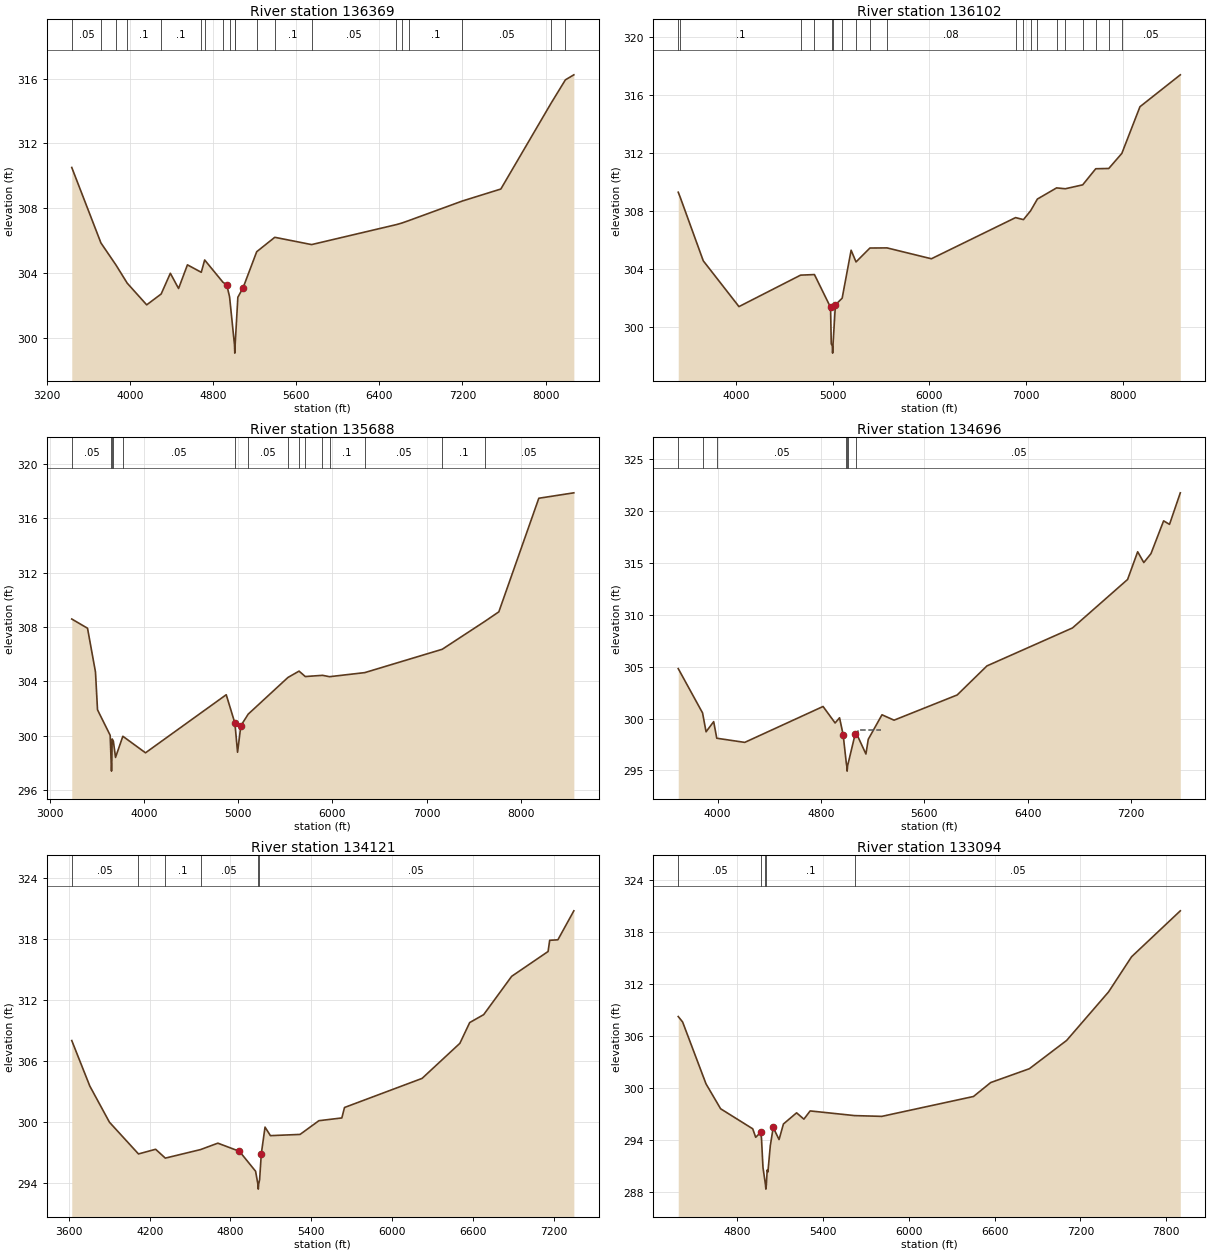
Type RM Length L Ch R = 1 ,136369  ,267,267,267
BEGIN DESCRIPTION:
Mapping XS 69bc8e48
END DESCRIPTION:
XS GIS Cut Line= 4
      2213573.11     13231559.51      2213659.92     13230843.35
      2212911.22     13229845.09      2211010.95     13227700.75
#Sta/Elev= 30
  3438.2  310.51  3719.2  305.85  3864.9  304.48    3972  303.37  4159.6  302.03
  4298.9   302.7  4387.4  303.98  4466.5  303.04  4551.9   304.5  4685.2  304.04
  4717.9   304.8  4893.2  303.43  4930.2  303.27  4957.6  302.53  5005.2  299.55
  5007.9  299.05  5011.2  299.55  5037.4   302.5  5087.4  303.08  5218.9  305.31
  5392.9   306.2  5747.7  305.75  6561.5  306.98  6616.4  307.08  6682.8  307.23
  7198.9  308.44  7569.6  309.18  8053.7  314.48  8191.2  315.92  8272.6  316.23
#Mann= 20 ,-1 , 0
  3438.2     .05       0  3719.2      .1       0  3864.9     .05       0
    3972      .1       0  4298.9      .1       0  4685.2     .05       0
  4717.9      .1       0  4893.2     .05       0  4957.6      .1       0
  5005.2     .07       0  5011.2      .1       0  5218.9     .05       0
  5392.9      .1       0  5747.7     .05       0  6561.5      .1       0
  6616.4     .05       0  6682.8      .1       0  7198.9     .05       0
  8053.7     .08       0  8191.2     .05       0
Bank Sta=4930.2,5087.4
XS Rating Curve= 0 ,0
Exp/Cntr=0.3,0.1

Type RM Length L Ch R = 1 ,136102  ,414,414,414
BEGIN DESCRIPTION:
Mapping XS 25e5495c
END DESCRIPTION:
XS GIS Cut Line= 4
      2213844.38     13231624.64      2213909.49     13230778.25
      2213132.58     13229901.51      2211049.04     13227517.36
#Sta/Elev= 30
  3405.4  309.31  3426.1  308.96  3663.9  304.58  4032.9  301.42  4669.3  303.59
  4812.5  303.63  4978.8  301.37  4986.3  298.85  4997.5  298.71  5000.3  298.21
  5003.5  298.71    5029  301.54  5098.8     302  5191.4  305.31    5242   304.5
  5385.2  305.46  5562.1  305.47  6020.5  304.72  6890.4  307.56  6971.4  307.42
  7044.6  308.02  7115.6  308.84  7314.1  309.61    7404  309.55  7583.6  309.82
  7718.4  310.93  7853.2  310.95    7988  311.99  8175.2  315.21    8592  317.41
#Mann= 20 ,-1 , 0
  3405.4     .05       0  3426.1      .1       0  4669.3      .1       0
  4812.5      .1       0  4997.5     .07       0  5003.5      .1       0
  5098.8     .05       0    5242      .1       0  5385.2     .05       0
  5562.1     .08       0  6890.4     .05       0  6971.4     .08       0
  7044.6     .05       0  7115.6     .08       0  7314.1     .05       0
    7404     .08       0  7583.6     .05       0  7718.4     .05       0
  7853.2     .05       0    7988     .05       0
Bank Sta=4978.8,5029
XS Rating Curve= 0 ,0
Exp/Cntr=0.3,0.1

Type RM Length L Ch R = 1 ,135688  ,992,992,992
BEGIN DESCRIPTION:
Mapping XS 6581b093
END DESCRIPTION:
XS GIS Cut Line= 3
      2214969.46     13231351.14      2213519.31     13229784.03
       2211311.5     13227477.79
#Sta/Elev= 30
  3234.5  308.59  3401.7  307.91  3486.2  304.68  3507.7   301.9  3642.1  300.02
  3653.3  297.88    3656  297.38  3659.3  297.88  3663.1  299.75  3675.8  299.59
  3698.8  298.39  3776.6  299.95  4016.9  298.73  4873.6  303.01  4965.5  300.92
  4965.6  300.92  4993.8  298.77    5029  300.73  5106.8  301.58    5528  304.28
  5646.4  304.75  5712.6  304.35  5895.1  304.44    5970  304.34  6343.8  304.64
  7165.6  306.36  7614.3   308.4  7766.4  309.12  8190.6  317.49  8562.3  317.89
#Mann= 15 ,-1 , 0
  3234.5     .05       0  3653.3     .07       0  3659.3     .05       0
  3675.8     .08       0  3776.6     .05       0  4965.6      .1       0
  5106.8     .05       0    5528      .1       0  5646.4     .05       0
  5712.6      .1       0  5895.1     .05       0    5970      .1       0
  6343.8     .05       0  7165.6      .1       0  7614.3     .05       0
Bank Sta=4965.5,5029
XS Rating Curve= 0 ,0
Exp/Cntr=0.3,0.1

Type RM Length L Ch R = 1 ,134696  ,575,575,575
BEGIN DESCRIPTION:
Mapping XS 1d9223d8
END DESCRIPTION:
XS GIS Cut Line= 4
      2215019.78     13231176.39      2214529.18     13230297.88
      2214791.58     13229339.54      2215350.61     13227536.97
#Sta/Elev= 30
  3695.3  304.81  3883.6  300.54  3910.8  298.72  3969.7   299.7  3993.7   298.1
  4210.2   297.7  4816.6  301.16  4909.9  299.57  4944.2  300.07  4972.1  298.44
  4996.6  295.69  5000.3  295.43    5003  294.93  5006.3  295.43  5065.5  298.52
  5074.7  298.57  5148.4  296.58  5166.6     298  5272.8  300.36  5366.1  299.84
    5855  302.27  6085.3  305.07  6747.8  308.73  7174.2   313.4  7252.3  316.07
  7299.8  315.03  7355.3  315.89  7453.1  319.05  7498.8  318.71  7582.4  321.75
#Mann= 7 ,-1 , 0
  3695.3     .05       0  3883.6     .08       0  3993.7     .05       0
  4996.6      .1       0  5000.3     .07       0  5006.3      .1       0
  5074.7     .05       0
#XS Ineff= 1 ,-1
 5085.17 5268.63  298.92
Permanent Ineff=
       F
Bank Sta=4972.1,5065.5
XS Rating Curve= 0 ,0
Exp/Cntr=0.3,0.1

Type RM Length L Ch R = 1 ,134121  ,1027,1027,1027
BEGIN DESCRIPTION:
Mapping XS 4ad28cfe
END DESCRIPTION:
XS GIS Cut Line= 4
      2215259.35     13231404.57      2215145.25     13230491.83
      2215190.89     13229225.46      2215612.85     13227742.88
#Sta/Elev= 30
  3621.5  307.97  3755.4   303.5  3901.4  299.94  4116.9  296.82  4244.2  297.28
  4316.2  296.41    4578  297.25  4706.4  297.88  4866.5  297.08  4986.6  295.12
  5003.6  293.86  5006.4  293.36  5009.6  293.86  5016.6   294.3    5029  296.83
  5056.7  299.46  5096.7  298.62  5316.8  298.74  5456.9  300.09    5627  300.36
    5647  301.39    6223  304.25  6503.7   307.7  6576.5  309.74  6680.4  310.52
  6888.4  314.29  7158.7  316.73  7170.6  317.83  7231.5  317.88    7350  320.73
#Mann= 6 ,-1 , 0
  3621.5     .05       0  4116.9     .08       0  4316.2      .1       0
    4578     .05       0  5003.6    .035       0  5009.6     .05       0
Bank Sta=4866.5,5029
XS Rating Curve= 0 ,0
Exp/Cntr=0.3,0.1

Type RM Length L Ch R = 1 ,133094  ,1123,1123,1123
BEGIN DESCRIPTION:
Mapping XS 8a6dda12
END DESCRIPTION:
XS GIS Cut Line= 3
      2215465.09     13231476.92      2215682.11     13230435.24
      2215834.02     13227993.81
#Sta/Elev= 30
  4388.5  308.23  4419.2   307.6  4582.7  300.45  4684.8  297.57  4909.5  295.25
    4930  294.27  4965.5  294.86  4970.5  294.15    4981  290.79  4998.5  288.78
  5001.2  288.28  5004.5  288.78  5010.4  290.49  5015.5  290.26  5032.1  293.29
  5052.5  295.41  5093.4  294.01    5124  295.81    5216   297.1    5267  296.37
  5310.7  297.32  5621.3  296.78  5811.6  296.69  6452.9  298.99  6573.1   300.6
  6843.6   302.2  7104.1  305.47  7397.2  311.08  7557.9  315.14  7898.7  320.45
#Mann= 5 ,-1 , 0
  4388.5     .05       0  4970.5      .1       0  4998.5     .07       0
  5004.5      .1       0  5621.3     .05       0
Bank Sta=4965.5,5052.5
XS Rating Curve= 0 ,0
Exp/Cntr=0.3,0.1