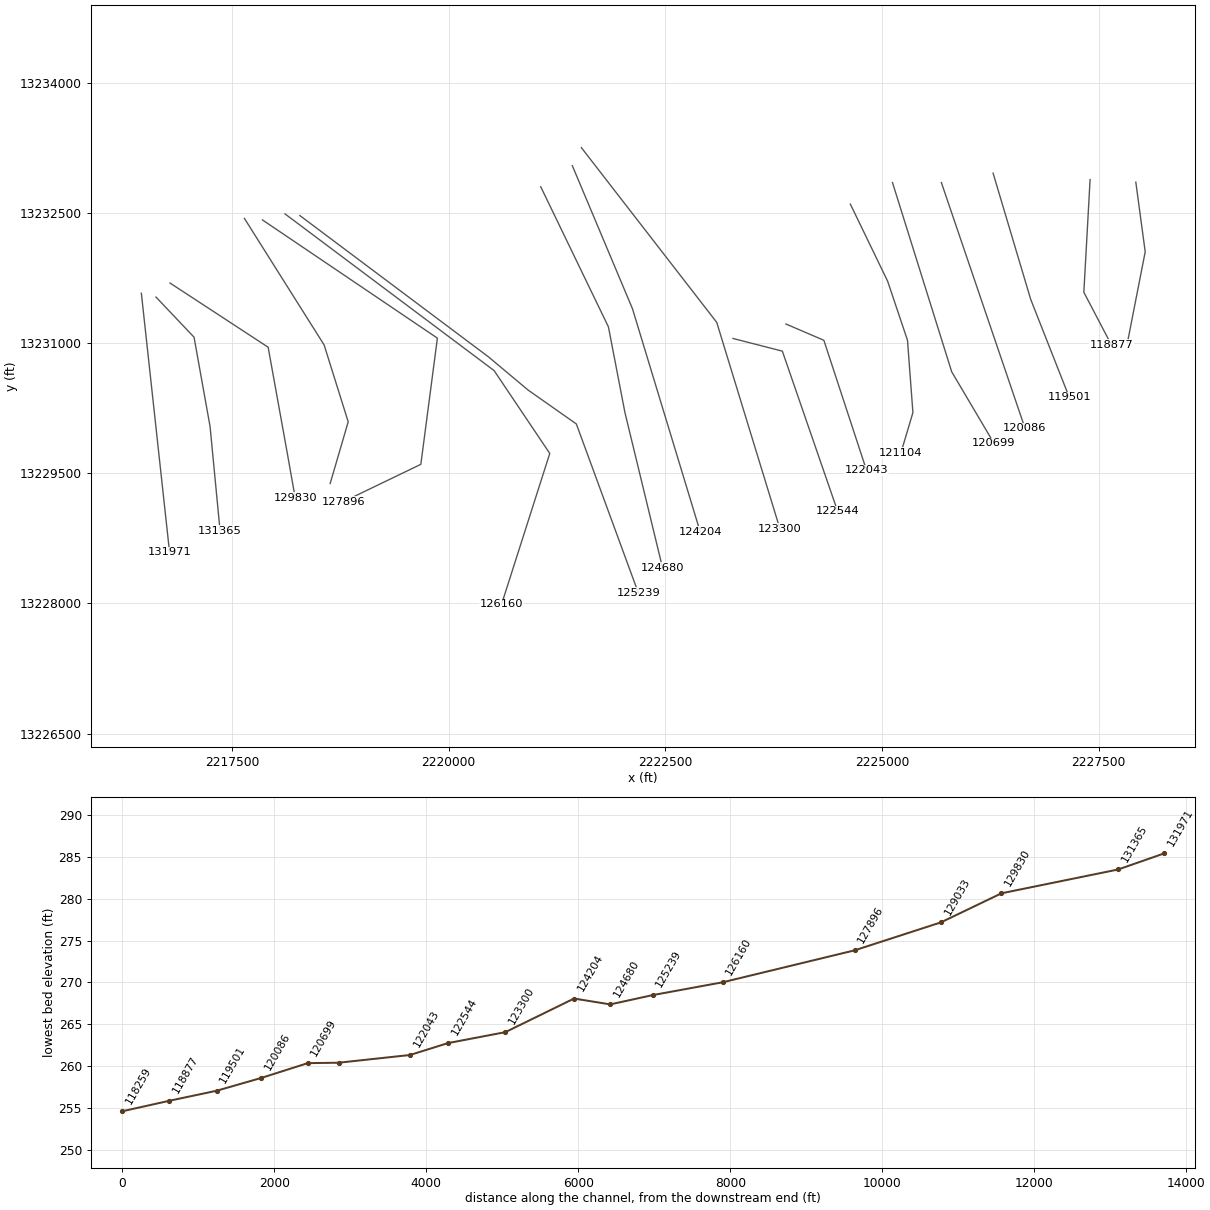
HEC-RAS study RAMIRENA CREEK.prj: RAMIRENA CREEK Base Level Engineering

--- RAMIRENA CREEK.g01 (geometry) --- (continued)

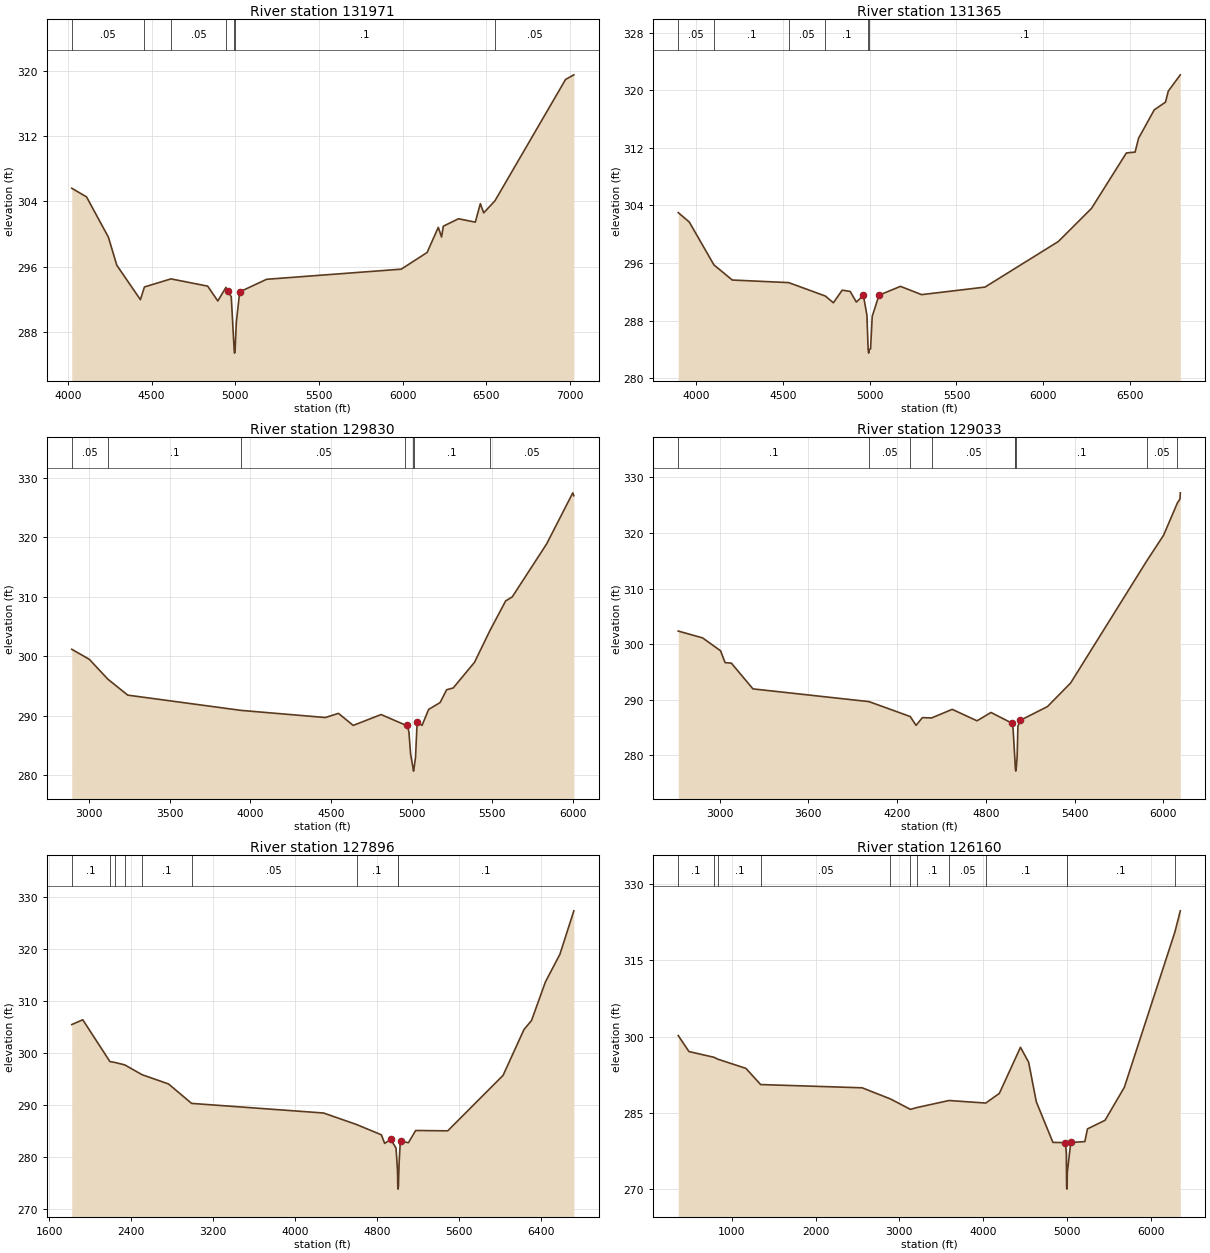
Type RM Length L Ch R = 1 ,131971  ,606,606,606
BEGIN DESCRIPTION:
Mapping XS 9d267993
END DESCRIPTION:
XS GIS Cut Line= 2
       2216452.5     13231574.59      2216777.95     13228591.29
#Sta/Elev= 30
  4023.1  305.61  4111.4  304.55  4242.1  299.61  4292.4  296.17  4433.3  291.95
  4457.4  293.51  4616.2   294.5  4835.6  293.61    4896  291.79  4944.4  293.45
  4956.3  293.01  4976.5   292.3  4993.6   285.9  4996.3   285.4  4999.6   285.9
  5006.6  289.16  5026.8  292.91  5187.7  294.45  5992.4  295.69  6147.2  297.74
  6213.8  300.82  6233.5  299.63  6243.9  300.96  6334.9  301.87  6435.1  301.45
  6465.2  303.72  6485.4  302.59  6552.8  304.08  6974.5  318.94  7024.1  319.51
#Mann= 7 ,-1 , 0
  4023.1     .05       0  4457.4      .1       0  4616.2     .05       0
  4944.4      .1       0  4993.6     .07       0  4999.6      .1       0
  6552.8     .05       0
Bank Sta=4956.3,5026.8
XS Rating Curve= 0 ,0
Exp/Cntr=0.3,0.1

Type RM Length L Ch R = 1 ,131365  ,1535,1535,1535
BEGIN DESCRIPTION:
RAMIRENA CREEK 150.0
END DESCRIPTION:
XS GIS Cut Line= 4
       2216621.3     13231530.61      2217060.46     13231068.34
      2217245.38     13230039.73      2217360.95     13228837.79
#Sta/Elev= 30
  3898.3  303.01    3962   301.7  4103.9  295.74  4209.5  293.64  4534.1  293.28
  4744.6  291.42  4791.4  290.48  4842.2  292.23  4887.9  292.06  4923.5  290.58
  4964.2  291.51  4984.5  288.75  4991.6  283.98  4994.4  283.48  4997.6  283.98
  5005.4  284.07    5015  288.59  5053.9  291.53  5177.5  292.76  5299.4  291.61
  5664.3  292.66  6086.2  298.99  6277.1  303.59    6478   311.3  6528.2  311.42
  6548.3  313.35  6638.7   317.3  6703.3  318.36  6719.1  319.89  6788.5  322.16
#Mann= 6 ,-1 , 0
  3898.3     .05       0  4103.9      .1       0  4534.1     .05       0
  4744.6      .1       0  4991.6     .07       0  4997.6      .1       0
Bank Sta=4964.2,5053.9
XS Rating Curve= 0 ,0
Exp/Cntr=0.3,0.1

Type RM Length L Ch R = 1 ,129830  ,797,797,797
BEGIN DESCRIPTION:
RAMIRENA CREEK 149.0
END DESCRIPTION:
XS GIS Cut Line= 4
      2216783.04     13231692.46       2217915.7     13230952.77
       2218135.3     13229739.24      2218227.51     13229220.51
#Sta/Elev= 30
  2892.8  301.17  3001.8  299.47    3117  296.12  3240.1  293.44    3943  290.87
    4465  289.67  4546.3  290.37  4637.8  288.34  4810.5  290.17  4961.8   288.4
  4973.1  288.34  4983.3  287.22  4993.5  283.52  5008.9  281.14  5011.7  280.64
  5014.9  281.14    5024  282.94  5034.1  288.88  5064.6  288.35  5105.3  291.03
  5176.4  292.19    5217  294.35  5257.7  294.65  5389.8  298.97  5484.9  304.29
  5583.1  309.32  5623.5  309.98  5836.7   318.9  5999.3  327.52  6005.7  327.03
#Mann= 7 ,-1 , 0
  2892.8     .05       0    3117      .1       0    3943     .05       0
  4961.8      .1       0  5008.9     .07       0  5014.9      .1       0
  5484.9     .05       0
Bank Sta=4973.1,5034.1
XS Rating Curve= 0 ,0
Exp/Cntr=0.3,0.1

Type RM Length L Ch R = 1 ,129033  ,1137,1137,1137
BEGIN DESCRIPTION:
RAMIRENA CREEK 148.0
END DESCRIPTION:
XS GIS Cut Line= 4
      2217641.86     13232436.89      2218562.02     13230978.53
       2218839.8     13230093.12      2218631.55     13229381.61
#Sta/Elev= 30
    2721  302.36    2886  301.13  3007.2  298.81  3037.8  296.68  3080.2  296.59
  3226.1  291.96  4010.5  289.67    4289  286.99  4328.7   285.4  4371.1  286.79
  4433.9  286.74  4572.9  288.28  4740.6  286.22  4834.9  287.72  4979.3  285.76
  4984.6  284.73  4997.4  278.86  4999.6  277.67  5002.4  277.17  5005.6  277.67
  5011.7  279.71    5017  285.28  5034.1  286.32  5216.8  288.78  5373.3  293.02
    5888  314.98  6001.8   319.6  6095.6  325.44  6112.5  326.11  6114.7  327.22
#Mann= 9 ,-1 , 0
    2721      .1       0  4010.5     .05       0    4289      .1       0
  4433.9     .05       0  4997.4      .1       0  4999.6     .07       0
  5005.6      .1       0    5888     .05       0  6095.6      .1       0
Bank Sta=4979.3,5034.1
XS Rating Curve= 0 ,0
Exp/Cntr=0.3,0.1

Type RM Length L Ch R = 1 ,127896  ,1736,1736,1736
BEGIN DESCRIPTION:
RAMIRENA CREEK 146.0
END DESCRIPTION:
XS GIS Cut Line= 4
      2217850.24     13232419.48      2219869.17     13231057.24
      2219678.06     13229603.08      2218782.55     13229171.91
#Sta/Elev= 30
  1819.8  305.48  1927.1  306.41    2192  298.36  2237.3  298.21  2336.3  297.73
  2505.4  295.84  2763.4  294.06  2988.5  290.32  4275.9  288.47  4596.4  286.26
  4838.9  284.28    4871  282.63  4931.5  283.39  4981.9  281.72  4996.3  277.43
  4999.1  274.33  5001.8  273.83  5005.1  274.33  5012.2  278.97  5022.3   282.5
  5032.3  283.04  5102.9  282.76  5173.5  285.11  5486.2  285.04    6026  295.72
  6229.7  304.53  6303.1  306.26  6438.8  313.69  6580.1  319.01  6715.9  327.36
#Mann= 9 ,-1 , 0
  1819.8      .1       0    2192     .05       0  2237.3      .1       0
  2336.3     .05       0  2505.4      .1       0  2988.5     .05       0
  4596.4      .1       0  4999.1     .07       0  5005.1      .1       0
Bank Sta=4931.5,5032.3
XS Rating Curve= 0 ,0
Exp/Cntr=0.3,0.1

Type RM Length L Ch R = 1 ,126160  ,921,921,921
BEGIN DESCRIPTION:
RAMIRENA CREEK 144.0
END DESCRIPTION:
XS GIS Cut Line= 4
      2218110.63     13232488.94      2220523.82     13230683.39
      2221166.19     13229728.53      2220610.64     13227992.46
#Sta/Elev= 30
   362.4  300.23   490.5  297.08     787  295.96   836.5  295.57  1169.9  293.77
  1344.9  290.59  2555.8  289.95  2893.2  287.76  3131.4  285.71  3209.3  286.07
  3592.1  287.45    4030  286.95  4191.7  288.85    4444  297.92  4541.5  294.96
  4632.8  287.19  4830.9  279.21  4980.3  279.17  4990.8  276.89    4994  270.52
  4996.7  270.02    5000  270.52  5002.2  273.28  5043.3   279.2  5211.3  279.37
  5242.8  281.87  5452.4  283.56  5682.7  290.06  6284.7  320.56  6349.9  324.76
#Mann= 12 ,-1 , 0
   362.4      .1       0     787     .05       0   836.5      .1       0
  1344.9     .05       0  2893.2      .1       0  3131.4     .05       0
  3209.3      .1       0  3592.1     .05       0    4030      .1       0
    4994     .07       0    5000      .1       0  6284.7     .05       0
Bank Sta=4980.3,5043.3
XS Rating Curve= 0 ,0
Exp/Cntr=0.3,0.1

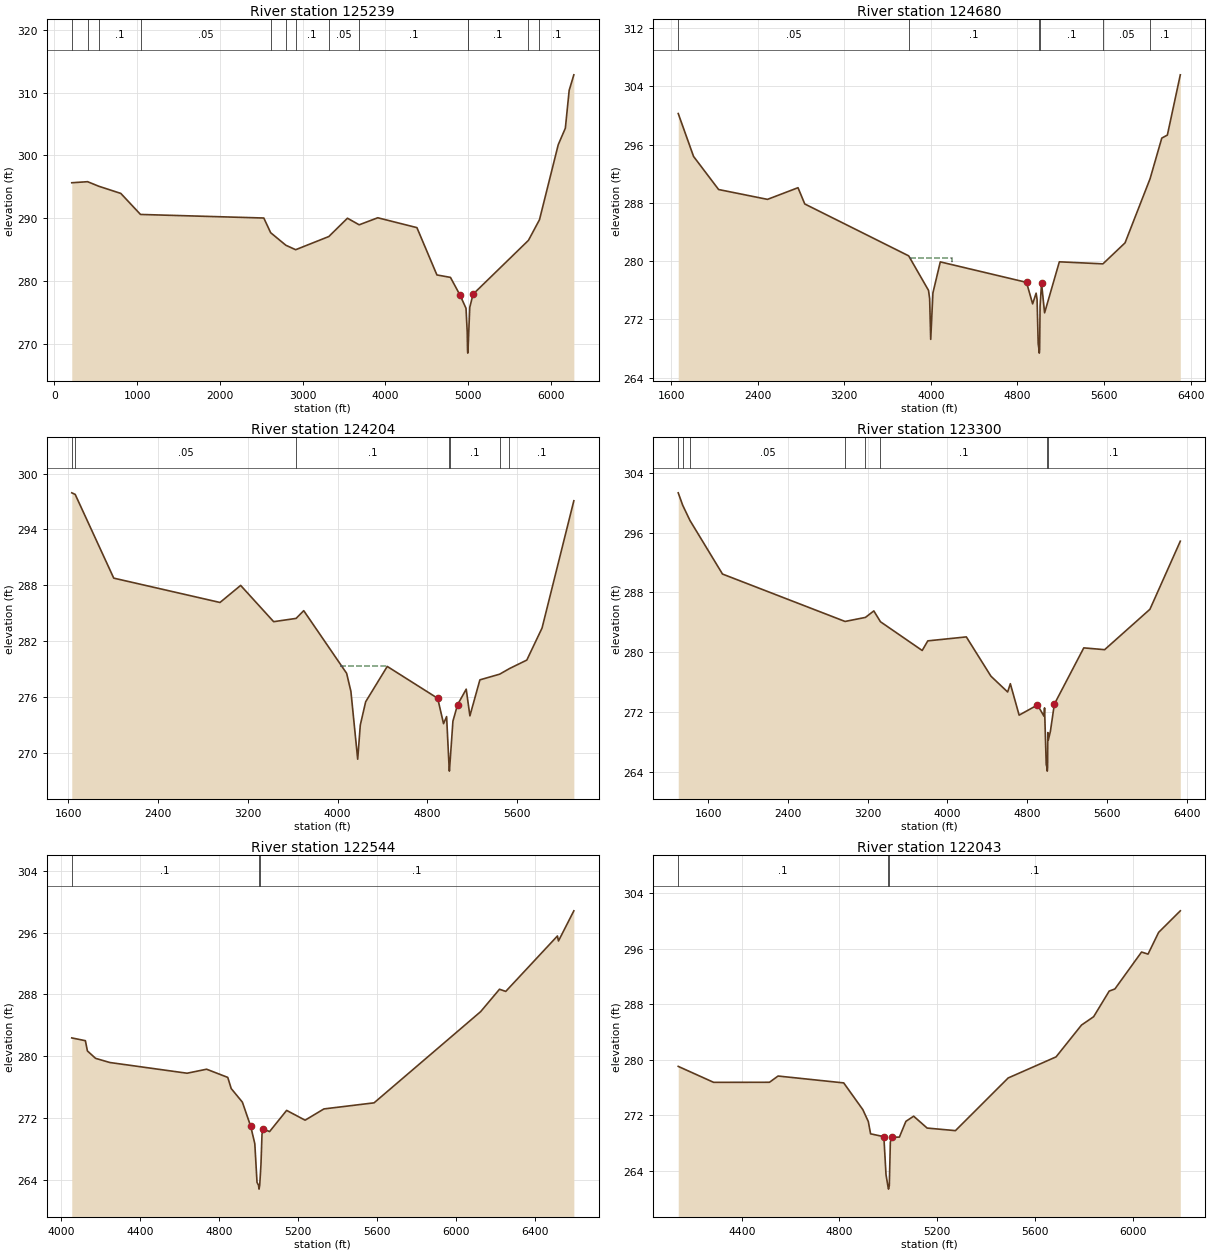
Type RM Length L Ch R = 1 ,125239  ,559,559,559
BEGIN DESCRIPTION:
RAMIRENA CREEK 142.0
END DESCRIPTION:
XS GIS Cut Line= 5
      2218282.04     13232469.87      2220459.15      13230841.2
      2220916.17     13230458.96      2221472.91     13230068.41
      2222187.51     13228124.03
#Sta/Elev= 30
   210.8  295.64   402.1  295.81     536  295.09   803.5  293.94  1041.3  290.59
  2531.2  290.02  2613.9  287.68  2797.7  285.68    2916  284.97  3316.6  287.07
  3541.8  289.99  3683.7  288.94  3907.9  290.06    4381  288.49  4622.7  280.95
  4786.3  280.56  4902.9  277.71  4974.3  275.63    4989   271.8  4992.6  268.99
  4995.4  268.49  4998.6  268.99  5019.5  275.78  5059.5  277.88  5728.5  286.46
  5861.9  289.75  6088.5   301.7  6174.6  304.34  6220.8  310.38  6277.1  312.84
#Mann= 13 ,-1 , 0
   210.8      .1       0   402.1     .05       0     536      .1       0
  1041.3     .05       0  2613.9      .1       0  2797.7     .05       0
    2916      .1       0  3316.6     .05       0  3683.7      .1       0
  4992.6     .07       0  4998.6      .1       0  5728.5     .05       0
  5861.9      .1       0
Bank Sta=4902.9,5059.5
XS Rating Curve= 0 ,0
Exp/Cntr=0.3,0.1

Type RM Length L Ch R = 1 ,124680  ,476,476,476
BEGIN DESCRIPTION:
RAMIRENA CREEK 141.0
END DESCRIPTION:
XS GIS Cut Line= 4
        2221062.     13232801.49      2221843.27     13231186.87
      2222034.24     13230197.28      2222467.92     13228410.51
#Sta/Elev= 30
  1665.2  300.26  1806.9  294.37  2038.4  289.83  2490.1  288.48  2772.3  290.08
  2834.5  287.85  3794.9  280.73  3978.3  275.99  3988.7  274.86  3998.7  269.27
  4019.1  275.65  4087.3   279.9  4884.1  277.09  4940.5  274.14  4972.8  275.61
  4981.7  274.73    4992  268.65  4999.3  267.88    5002  267.38  5005.3  267.88
  5009.4  273.84  5022.9  276.95  5051.2  272.91  5187.5  279.91  5590.3  279.63
  5794.6  282.51  6025.9  291.31  6134.2  296.89  6185.7   297.3  6305.4  305.57
#Mann= 6 ,-1 , 0
  1665.2     .05       0  3794.9      .1       0  4999.3     .07       0
  5005.3      .1       0  5590.3     .05       0  6025.9      .1       0
#XS Ineff= 1 ,-1
    3805 4192.19  280.43
Permanent Ineff=
       F
Bank Sta=4884.1,5022.9
XS Rating Curve= 0 ,0
Exp/Cntr=0.3,0.1

Type RM Length L Ch R = 1 ,124204  ,904,904,904
BEGIN DESCRIPTION:
RAMIRENA CREEK 140.0
END DESCRIPTION:
XS GIS Cut Line= 3
      2221426.59     13233044.53      2222121.05      13231395.2
      2222902.31     13228825.71
#Sta/Elev= 30
  1630.4  297.93    1661  297.76  2004.6  288.78  2951.6  286.17  3135.7     288
  3429.8  284.11  3629.5  284.46    3698  285.29  4080.4  278.57  4118.5  276.63
    4179  269.36  4202.1  273.02    4250  275.52  4442.5  279.31    4892  275.89
  4944.2  273.17  4971.5  273.93  4993.5  268.58  4996.2  268.08  4999.5  268.58
  5027.8  273.44  5069.7  275.22  5146.3  276.87  5179.1  274.01  5268.2  277.87
  5444.6  278.48  5531.7  279.08  5686.3  279.99  5822.2  283.43  6105.6  297.08
#Mann= 7 ,-1 , 0
  1630.4      .1       0    1661     .05       0  3629.5      .1       0
  4993.5     .07       0  4999.5      .1       0  5444.6     .05       0
  5531.7      .1       0
#XS Ineff= 1 ,-1
  4020.6 4441.45  279.31
Permanent Ineff=
       F
Bank Sta=4892,5069.7
XS Rating Curve= 0 ,0
Exp/Cntr=0.3,0.1

Type RM Length L Ch R = 1 ,123300  ,756,756,756
BEGIN DESCRIPTION:
RAMIRENA CREEK 139.0
END DESCRIPTION:
XS GIS Cut Line= 3
      2221530.75     13233252.86      2223093.27     13231238.95
      2223822.23     13228861.16
#Sta/Elev= 30
  1301.1  301.35  1345.8  299.69  1418.7  297.65  1745.1  290.47  2974.4  284.12
  3178.5  284.66    3263  285.53  3329.5  284.08  3748.2  280.23  3804.3  281.52
  4190.8  282.05    4438  276.78  4605.3  274.67  4632.2  275.78  4720.4  271.57
  4904.6  272.93  4970.1  271.42  4975.4  272.54  4992.3  264.93  4999.8  264.57
  5002.6  264.07  5005.8  264.57  5008.1  269.24  5013.3  268.23  5034.2  269.41
  5073.6  273.04  5368.9  280.58  5578.1  280.34  6032.4  285.75  6337.1  294.87
#Mann= 8 ,-1 , 0
  1301.1     .05       0  1345.8      .1       0  1418.7     .05       0
  2974.4      .1       0  3178.5     .05       0  3329.5      .1       0
  4999.8     .07       0  5005.8      .1       0
Bank Sta=4904.6,5073.6
XS Rating Curve= 0 ,0
Exp/Cntr=0.3,0.1

Type RM Length L Ch R = 1 ,122544  ,501,501,501
BEGIN DESCRIPTION:
RAMIRENA CREEK 137.0
END DESCRIPTION:
XS GIS Cut Line= 3
      2223281.01      13231053.4      2223850.49     13230907.55
       2224489.1     13229061.13
#Sta/Elev= 30
  4053.2  282.37  4122.1  282.01  4132.4  280.68  4173.7  279.72  4245.9  279.18
    4637  277.79  4735.7  278.31  4842.8  277.25  4860.4   275.8  4916.9  274.04
  4959.2  270.89  4979.8  268.65    4991  263.64  4998.6  263.26  5001.3  262.76
  5004.6  263.26  5010.9  265.92  5016.2  269.88  5022.7  270.58  5054.5  270.22
  5140.9  272.97  5234.4   271.7  5329.6  273.16  5583.5  273.95  6123.2  285.78
  6218.4  288.68  6250.1   288.4  6511.7  295.59    6517  294.94  6594.8  298.85
#Mann= 3 ,-1 , 0
  4053.2      .1       0  4998.6     .07       0  5004.6      .1       0
Bank Sta=4959.2,5022.7
XS Rating Curve= 0 ,0
Exp/Cntr=0.3,0.1

Type RM Length L Ch R = 1 ,122043  ,939,939,939
BEGIN DESCRIPTION:
RAMIRENA CREEK 136.0
END DESCRIPTION:
XS GIS Cut Line= 3
      2223892.14     13231220.06      2224329.65     13231032.55
      2224822.72     13229532.51
#Sta/Elev= 30
  4140.2  279.03  4285.1  276.73  4513.6  276.74  4548.8  277.64  4817.5  276.65
  4895.9  272.79  4918.2  271.08  4927.5  269.31  4981.8   268.9  4990.6  263.44
  4998.1  261.84  5000.9  261.34  5004.1  261.84  5008.4  268.12  5013.6   268.8
  5045.4  268.84    5072  271.11  5103.8  271.85    5159  270.14  5274.8  269.77
  5490.6  277.36  5686.7   280.4  5790.6  284.98  5840.5  286.19  5904.1  289.88
  5927.5  290.19  6036.5  295.51  6063.1  295.21  6106.4  298.34  6195.2  301.45
#Mann= 3 ,-1 , 0
  4140.2      .1       0  4998.1     .07       0  5004.1      .1       0
Bank Sta=4981.8,5013.6
XS Rating Curve= 0 ,0
Exp/Cntr=0.3,0.1

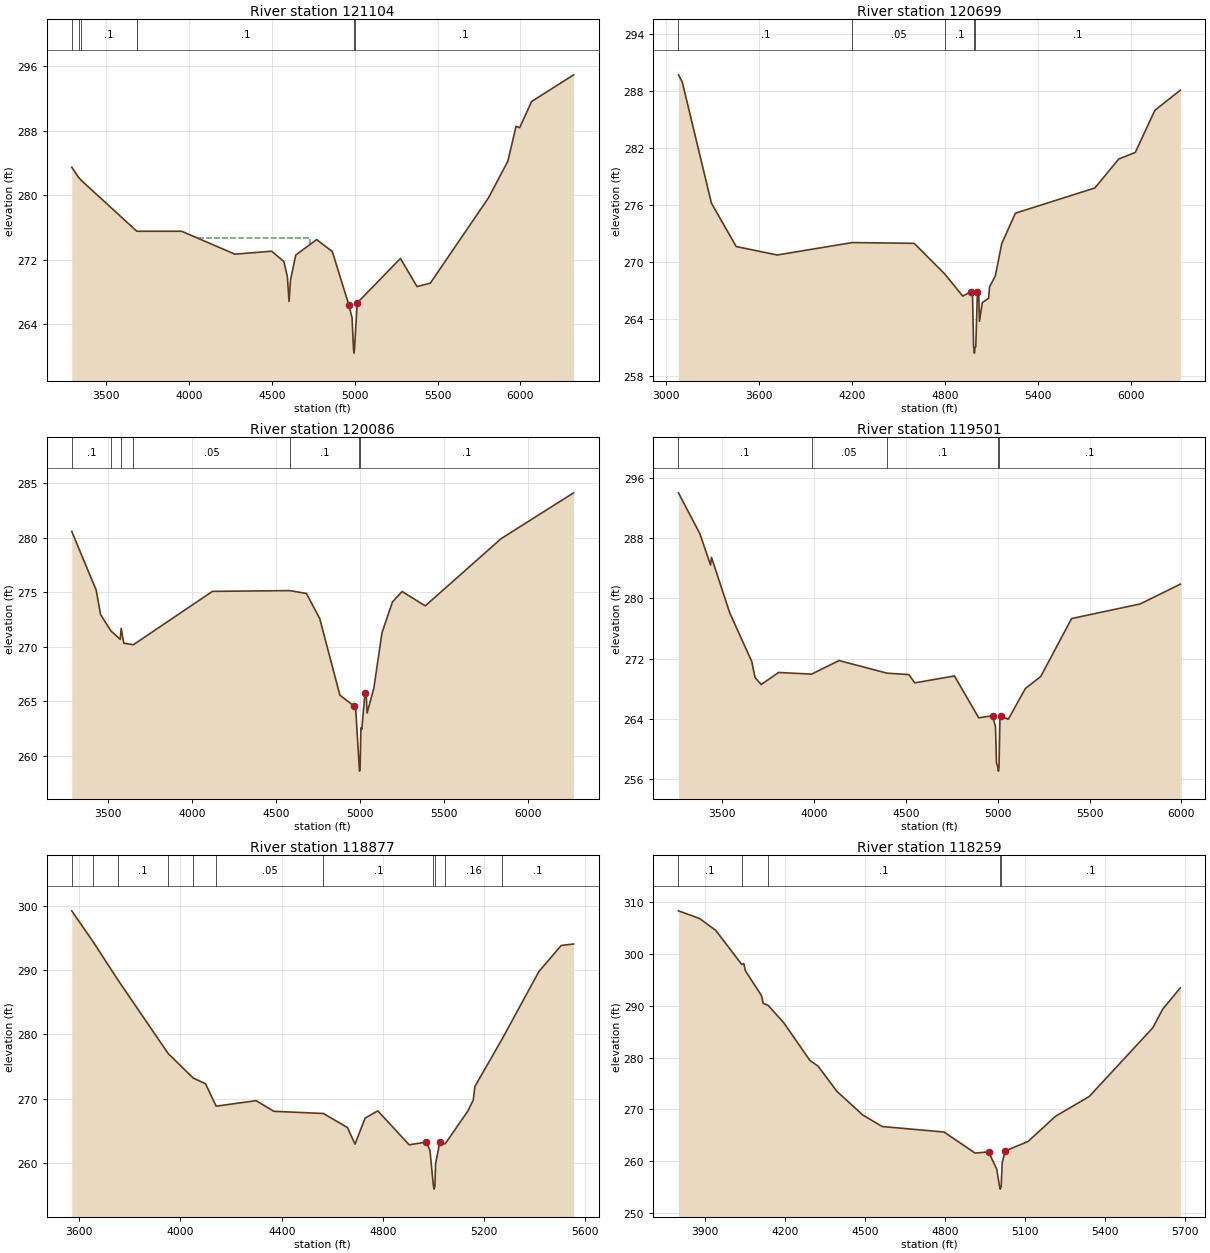
Type RM Length L Ch R = 1 ,121104  ,405,405,405
BEGIN DESCRIPTION:
RAMIRENA CREEK 135.0
END DESCRIPTION:
XS GIS Cut Line= 5
       2224635.2     13232602.01      2225065.76     13231713.11
      2225294.93     13231032.55      2225357.43     13230199.22
      2225218.55     13229733.97
#Sta/Elev= 30
  3293.9  283.46  3334.6  282.23  3352.2  281.83  3684.7  275.56  3687.8  275.53
  3957.1  275.53  4278.1  272.69  4499.2  273.06  4573.1  271.79  4594.2  269.92
  4604.7  266.82  4613.4   269.5  4644.9  272.58  4770.9   274.5  4865.3  273.02
  4965.1   266.4  4984.6   264.8  4993.2  260.92    4996  260.42  4999.2  260.92
  5015.4  266.64  5276.2  272.16  5376.4  268.67  5456.7   269.1  5807.7  279.69
  5924.1  284.22  5973.5  288.54  5995.6  288.38  6067.4  291.62  6320.9  294.93
#Mann= 7 ,-1 , 0
  3293.9      .1       0  3334.6     .16       0  3352.2      .1       0
  3684.7     .16       0  3687.8      .1       0  4993.2     .07       0
  4999.2      .1       0
#XS Ineff= 1 ,-1
 4054.72 4732.24  274.67
Permanent Ineff=
       F
Bank Sta=4965.1,5015.4
XS Rating Curve= 0 ,0
Exp/Cntr=0.3,0.1

Type RM Length L Ch R = 1 ,120699  ,613,613,613
BEGIN DESCRIPTION:
Mapping XS 80335fb4
END DESCRIPTION:
XS GIS Cut Line= 3
      2225121.64     13232850.28      2225805.23     13230669.32
      2226293.13     13229845.31
#Sta/Elev= 30
  3078.3  289.72  3102.9  288.97  3291.5  276.18  3451.8  271.61  3716.5  270.72
  4201.9  272.03  4601.4  271.95    4799  268.72  4915.7  266.38  4968.2  266.86
  4978.7  266.56  4985.8  260.94  4988.1  260.87  4990.8  260.37  4994.1  260.87
  4999.7  261.07  5010.2   266.8  5018.3  266.76  5023.5  263.73  5041.6  265.69
  5083.1  266.17  5088.4  267.34  5126.1  268.51  5167.3  271.91  5255.8  275.13
  5769.4  277.79  5923.5  280.84  6030.6  281.54    6157  285.98  6321.5   288.1
#Mann= 5 ,-1 , 0
  3078.3      .1       0  4201.9     .05       0    4799      .1       0
  4988.1     .07       0  4994.1      .1       0
Bank Sta=4968.2,5010.2
XS Rating Curve= 0 ,0
Exp/Cntr=0.3,0.1

Type RM Length L Ch R = 1 ,120086  ,585,585,585
BEGIN DESCRIPTION:
Mapping XS 63556f56
END DESCRIPTION:
XS GIS Cut Line= 2
      2225685.87     13232850.32      2226650.98     13230020.05
#Sta/Elev= 30
  3284.3  280.59    3430   275.2  3456.1  272.96  3517.7  271.46  3573.2  270.69
  3578.7  271.69  3594.4  270.33    3652   270.2  4122.6  275.09  4582.3  275.16
  4682.6   274.9  4761.8  272.59  4881.9  265.57  4967.9  264.55  4975.9  264.35
  4996.6   259.1  4999.3   258.6  5002.6   259.1  5007.2  262.57  5012.5  262.43
  5031.3  265.77  5038.6  265.67  5043.9  263.93  5084.1   266.2  5132.6  271.29
  5195.3  274.13  5252.7  275.08  5390.5  273.76  5842.9  279.93  6274.6  284.13
#Mann= 7 ,-1 , 0
  3284.3      .1       0  3517.7     .05       0  3578.7      .1       0
    3652     .05       0  4582.3      .1       0  4996.6     .07       0
  5002.6      .1       0
Bank Sta=4967.9,5031.3
XS Rating Curve= 0 ,0
Exp/Cntr=0.3,0.1

Type RM Length L Ch R = 1 ,119501  ,624,624,624
BEGIN DESCRIPTION:
Mapping XS 5088280f
END DESCRIPTION:
XS GIS Cut Line= 3
      2226282.66     13232958.83      2226716.69     13231504.82
      2227161.57     13230376.35
#Sta/Elev= 30
  3263.7  293.98  3380.6  288.55  3438.3  284.41  3443.6  285.41    3543  278.05
  3662.3  271.63  3680.7  269.48  3713.9  268.56  3808.4  270.16  3988.1  269.94
  4137.6  271.74  4398.1  270.07  4517.7  269.88  4549.4  268.78  4765.3   269.7
  4897.2  264.15  4972.4  264.42  4988.5  262.96  4993.9   258.2  5001.6  257.58
  5004.4  257.08  5007.6  257.58  5012.8  263.87  5018.2  264.35  5058.4  263.96
  5150.9  268.03  5234.8  269.63  5402.6  277.31  5776.2  279.25  5994.1  281.87
#Mann= 5 ,-1 , 0
  3263.7      .1       0  3988.1     .05       0  4398.1      .1       0
  5001.6     .07       0  5007.6      .1       0
Bank Sta=4972.4,5018.2
XS Rating Curve= 0 ,0
Exp/Cntr=0.3,0.1

Type RM Length L Ch R = 1 ,118877  ,618,618,618
BEGIN DESCRIPTION:
Mapping XS 8ae69e04
END DESCRIPTION:
XS GIS Cut Line= 3
      2227402.36      13232884.3      2227330.24     13231586.19
      2227647.16     13230981.18
#Sta/Elev= 30
  3570.5  299.26    3654  294.49  3753.1  288.48  3951.4  277.02  4050.5  273.19
  4098.8  272.32  4141.2  268.81  4299.1  269.67  4369.2  268.01  4564.7  267.67
  4659.6  265.49  4689.7   262.9  4729.7  266.95  4779.8  268.08  4903.7  262.79
  4971.5  263.22    4986   261.9  4999.5  256.38  5002.2  255.88  5005.5  256.38
  5008.1  259.83  5024.5  263.16  5046.3  262.95  5134.9  268.01  5156.9  269.75
  5163.4  271.88  5271.5  279.31  5416.1  289.78  5504.3  293.86  5553.6  294.09
#Mann= 11 ,-1 , 0
  3570.5      .1       0    3654     .08       0  3753.1      .1       0
  3951.4     .05       0  4050.5      .1       0  4141.2     .05       0
  4564.7      .1       0  4999.5     .07       0  5005.5      .1       0
  5046.3     .16       0  5271.5      .1       0
Bank Sta=4971.5,5024.5
XS Rating Curve= 0 ,0
Exp/Cntr=0.3,0.1

Type RM Length L Ch R = 1 ,118259  ,525,525,525
BEGIN DESCRIPTION:
RAMIRENA CREEK 129.0
END DESCRIPTION:
XS GIS Cut Line= 3
        2227930.     13232855.26      2228038.51      13232052.3
      2227832.74     13231001.82
#Sta/Elev= 30
  3801.3  308.29  3880.4  306.81    3941  304.53  4038.4  297.95  4046.3  298.12
    4052  296.74  4112.5  291.95  4118.9  290.45  4137.7  290.06  4196.6  286.66
  4294.1  279.44  4324.4  278.35  4395.1  273.49  4492.3  268.91  4564.9   266.7
  4796.6  265.64  4912.6  261.59  4963.6   261.8  4994.1  258.48  5004.6  255.13
  5007.4  254.63  5010.6  255.13  5014.5  259.67  5024.7  261.98  5110.6  263.79
  5213.6  268.65  5340.6  272.49  5579.1  285.75  5615.7  289.31    5682  293.44
#Mann= 5 ,-1 , 0
  3801.3      .1       0  4038.4     .05       0  4137.7      .1       0
  5004.6     .07       0  5010.6      .1       0
Bank Sta=4963.6,5024.7
XS Rating Curve= 0 ,0
Exp/Cntr=0.3,0.1