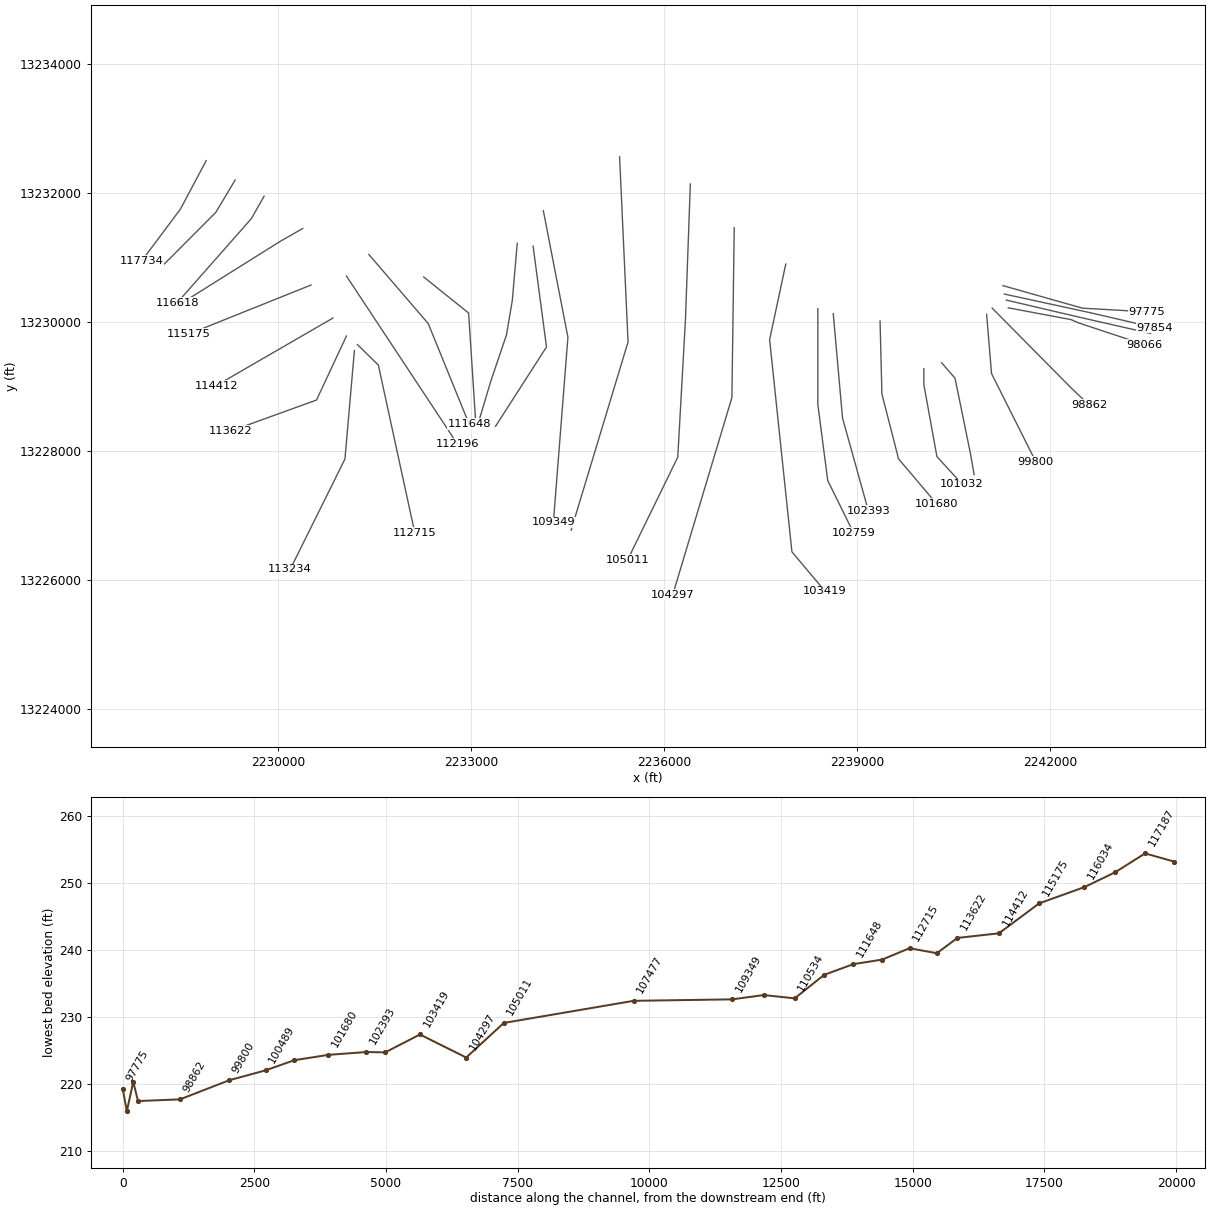
HEC-RAS study RAMIRENA CREEK.prj: RAMIRENA CREEK Base Level Engineering

--- RAMIRENA CREEK.g01 (geometry) --- (continued)

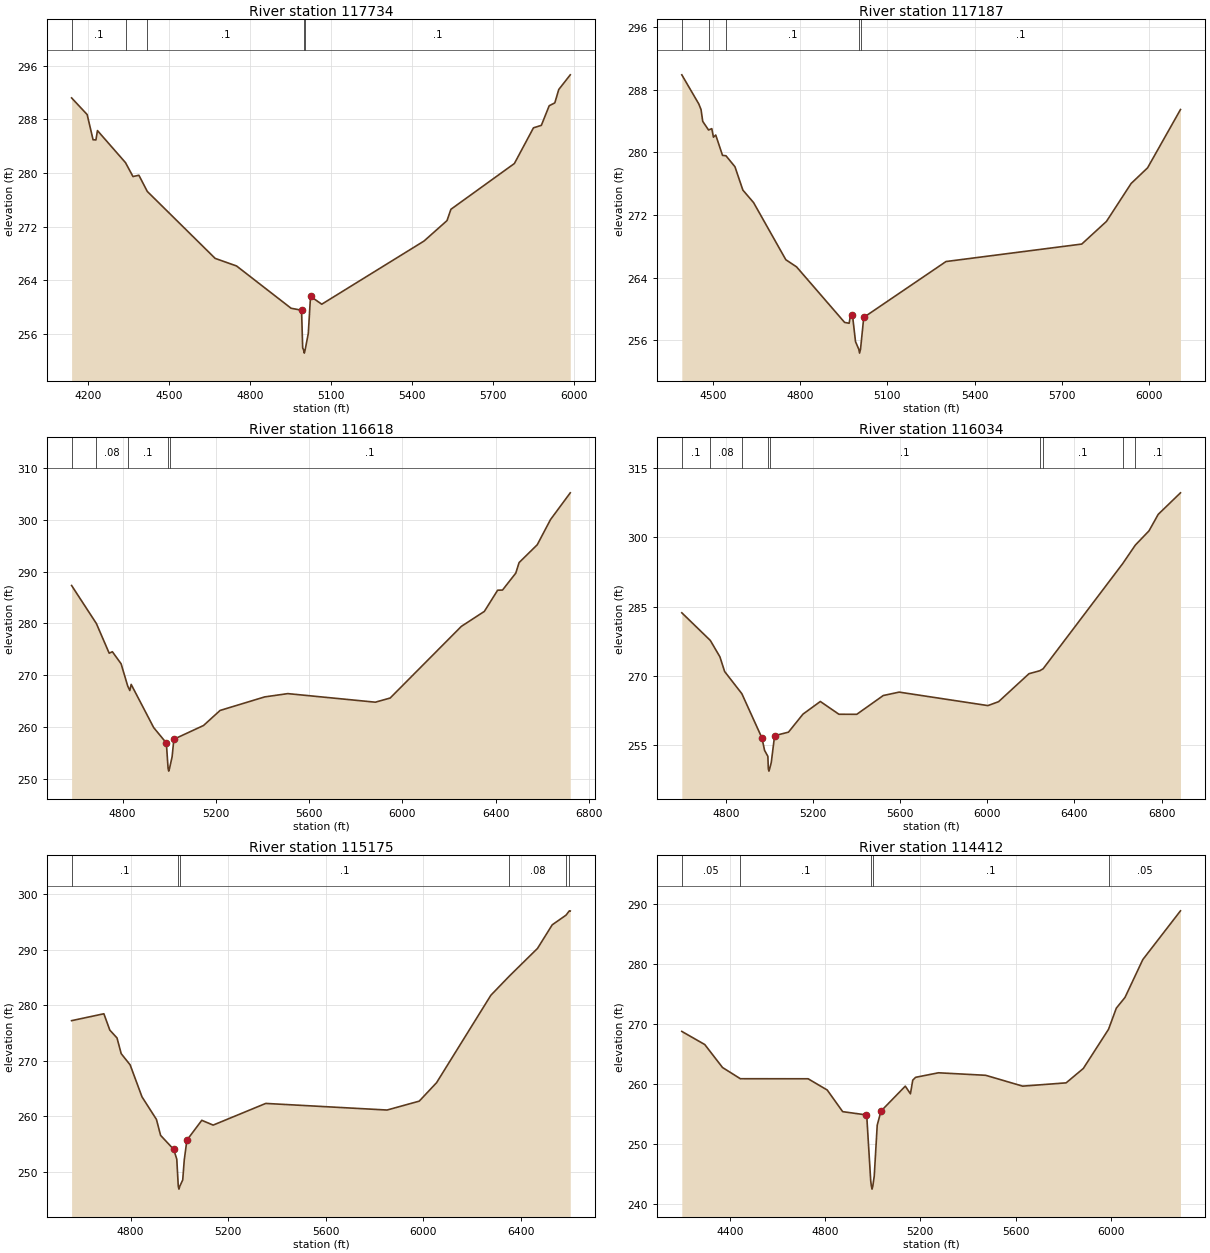
Type RM Length L Ch R = 1 ,117734  ,547,547,547
BEGIN DESCRIPTION:
RAMIRENA CREEK 128.0
END DESCRIPTION:
XS GIS Cut Line= 3
       2228887.7     13232496.83      2228487.72     13231746.85
       2227887.7     13230946.83
#Sta/Elev= 30
  4137.4   291.2  4195.1  288.72  4217.1  284.96  4227.7  284.94  4233.3  286.33
  4337.4  281.55  4365.1  279.48  4387.1  279.67  4418.2  277.26    4670  267.28
  4749.4  266.15  4951.6  259.85  4990.5  259.55  4994.7  253.94  4997.9  253.66
  5000.7  253.16  5003.9  253.66  5015.5  256.09  5023.8  261.62  5065.5  260.45
  5444.7  269.86  5530.1  272.91  5544.7   274.6  5780.1  281.42  5850.9  286.74
  5880.1  287.11  5909.2  290.03  5930.1  290.46  5944.7  292.45  5987.4  294.64
#Mann= 5 ,-1 , 0
  4137.4      .1       0  4337.4     .05       0  4418.2      .1       0
  4997.9     .07       0  5003.9      .1       0
Bank Sta=4990.5,5023.8
XS Rating Curve= 0 ,0
Exp/Cntr=0.3,0.1

Type RM Length L Ch R = 1 ,117187  ,569,569,569
BEGIN DESCRIPTION:
RAMIRENA CREEK 127.0
END DESCRIPTION:
XS GIS Cut Line= 3
      2229337.71     13232196.83      2229037.72     13231696.85
      2228237.75     13230896.88
#Sta/Elev= 30
  4393.4  289.89  4451.7  286.18  4459.5  285.46  4465.3  283.95  4485.3  282.85
  4496.4  283.02  4502.2  281.93    4510  282.21  4533.3  279.61  4545.2  279.56
  4576.1  278.16  4603.3  275.18  4640.2  273.58    4751  266.29  4787.9  265.38
  4953.1  258.29  4968.7  258.18  4973.6  259.26    4980  259.26  4990.6  255.83
  5001.8  254.87  5004.5  254.37  5007.8  254.87  5018.9  258.93  5301.7  266.06
  5768.4  268.29  5853.3  271.18  5938.1  276.02  5994.7  278.02  6107.8  285.46
#Mann= 5 ,-1 , 0
  4393.4      .1       0  4485.3     .05       0  4545.2      .1       0
  5001.8     .07       0  5007.8      .1       0
Bank Sta=4980,5018.9
XS Rating Curve= 0 ,0
Exp/Cntr=0.3,0.1

Type RM Length L Ch R = 1 ,116618  ,584,584,584
BEGIN DESCRIPTION:
RAMIRENA CREEK 126.0
END DESCRIPTION:
XS GIS Cut Line= 3
      2229787.71     13231946.84      2229587.72     13231596.85
      2228437.75     13230296.89
#Sta/Elev= 30
  4581.2  287.31  4687.5  279.98  4742.4  274.27  4756.1  274.55  4793.5  272.23
  4821.8  267.95    4831  267.07  4836.7  268.26  4933.2  259.94  4987.6  256.97
  4995.1  252.05  4997.8  251.55  5001.1  252.05  5012.3  254.32  5019.8  257.69
    5147  260.34  5218.1  263.24  5409.6  265.85  5508.3  266.48  5883.9  264.83
  5947.5  265.63  6252.7  279.43  6351.5  282.32  6408.4   286.4  6429.3  286.43
  6486.2  289.69  6500.4  291.72  6578.2  295.15  6635.1     300  6719.9  305.16
#Mann= 5 ,-1 , 0
  4581.2      .1       0  4687.5     .08       0  4821.8      .1       0
  4995.1     .07       0  5001.1      .1       0
Bank Sta=4987.6,5019.8
XS Rating Curve= 0 ,0
Exp/Cntr=0.3,0.1

Type RM Length L Ch R = 1 ,116034  ,859,859,859
BEGIN DESCRIPTION:
RAMIRENA CREEK 125.0
END DESCRIPTION:
XS GIS Cut Line= 3
      2230387.76     13231446.88      2230037.72     13231246.85
      2228437.68     13230246.83
#Sta/Elev= 30
    4597  283.67    4728  277.67    4772  274.12  4793.6  270.94  4872.7  266.13
  4964.9  256.54  4977.1  253.84  4992.2  252.54  4994.3  249.84    4997  249.34
  5000.3  249.84  5007.8  251.21  5023.1  257.02  5086.8  257.79  5153.5   261.7
  5233.1  264.44  5318.6  261.67  5400.5  261.66    5522  265.73  5595.1  266.47
  6002.5  263.55  6051.5  264.39  6191.2  270.46  6240.7   271.1  6256.2  271.53
  6621.3  294.31  6679.7  298.35  6742.5  301.44  6784.9  305.02    6887  309.68
#Mann= 9 ,-1 , 0
    4597      .1       0    4728     .08       0  4872.7      .1       0
  4994.3     .07       0  5000.3      .1       0  6240.7     .05       0
  6256.2      .1       0  6621.3     .05       0  6679.7      .1       0
Bank Sta=4964.9,5023.1
XS Rating Curve= 0 ,0
Exp/Cntr=0.3,0.1

Type RM Length L Ch R = 1 ,115175  ,763,763,763
BEGIN DESCRIPTION:
RAMIRENA CREEK 124.0
END DESCRIPTION:
XS GIS Cut Line= 2
      2230516.41     13230570.62      2228618.98     13229811.65
#Sta/Elev= 30
  4558.1  277.22  4690.4  278.46  4714.6  275.53  4744.2  274.11  4761.3  271.29
  4798.1  269.26  4846.5  263.52  4905.8  259.45  4922.9  256.58  4976.7  254.05
  4989.2  252.29  4995.3  247.41    4998  246.91  5001.3  247.41  5013.5  248.56
  5019.8  252.16  5030.6  255.72  5091.6  259.29  5138.3  258.43  5353.7  262.33
  5850.9  261.14  5982.8  262.74  6053.8  266.06  6276.3  281.79  6352.3  285.25
  6467.5  290.22  6527.7  294.46  6584.1  296.19  6598.1  296.98  6601.7  296.95
#Mann= 6 ,-1 , 0
  4558.1      .1       0  4995.3     .07       0  5001.3      .1       0
  6352.3     .08       0  6584.1     .05       0  6598.1     .08       0
Bank Sta=4976.7,5030.6
XS Rating Curve= 0 ,0
Exp/Cntr=0.3,0.1

Type RM Length L Ch R = 1 ,114412  ,790,790,790
BEGIN DESCRIPTION:
Mapping XS e7f1338a
END DESCRIPTION:
XS GIS Cut Line= 2
      2230857.27     13230059.31      2229044.51     13229013.49
#Sta/Elev= 30
  4198.9  268.79  4295.2   266.6  4369.8  262.76  4444.6  260.89  4728.9  260.88
  4809.3     259    4874  255.39  4970.2  254.86  4975.9  254.11  4991.7  243.84
  4994.5  242.95  4997.2  242.45  5000.5  242.95  5006.5  244.64    5019  253.14
  5034.8  255.48  5136.8  259.65  5158.4  258.37  5168.1  260.65  5179.9  261.12
  5276.1  261.88  5474.3  261.46  5629.4  259.65  5811.8   260.2  5883.9   262.6
  5989.7  269.14  6022.5  272.68  6058.9  274.47  6133.5  280.78  6291.7  288.93
#Mann= 5 ,-1 , 0
  4198.9     .05       0  4444.6      .1       0  4994.5     .07       0
  5000.5      .1       0  5989.7     .05       0
Bank Sta=4970.2,5034.8
XS Rating Curve= 0 ,0
Exp/Cntr=0.3,0.1

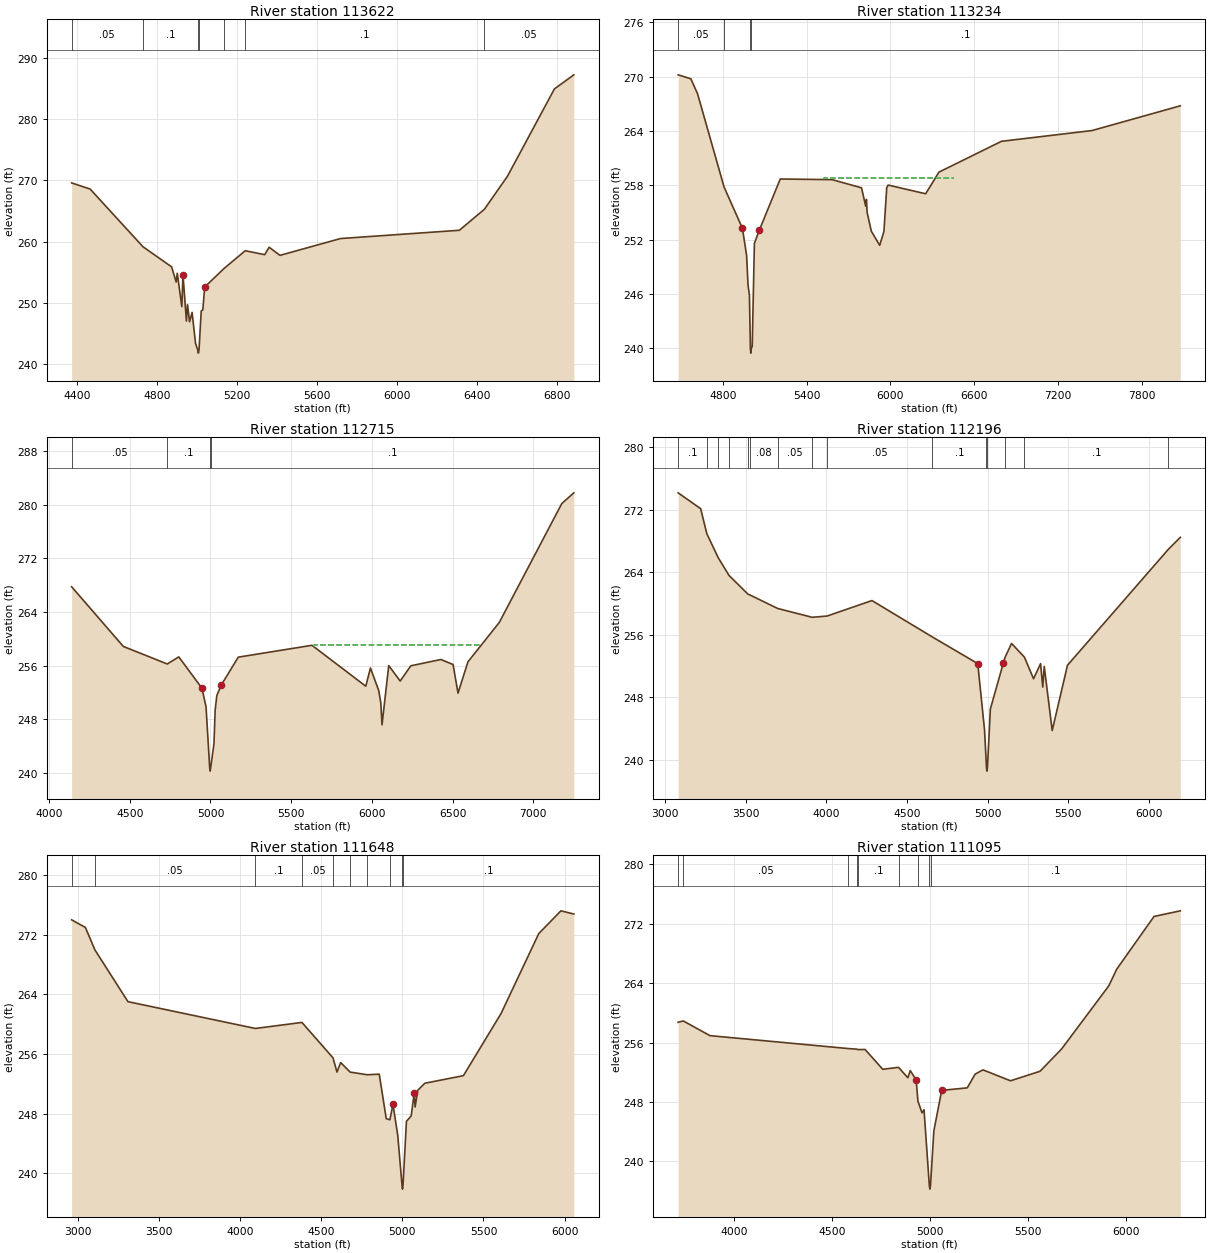
Type RM Length L Ch R = 1 ,113622  ,388,388,388
BEGIN DESCRIPTION:
Mapping XS cf324486
END DESCRIPTION:
XS GIS Cut Line= 3
      2231066.49     13229780.48      2230601.65     13228788.83
      2229270.96     13228309.16
#Sta/Elev= 30
  4372.2  269.58  4464.6  268.58  4728.6  259.15  4871.8  255.86  4894.6  253.38
  4900.1  254.81  4922.9  249.35  4928.5   254.6  4945.8     247  4951.3  249.68
  4961.5  246.88  4974.1  248.42  4991.4  243.34  5002.7  242.26  5005.5  241.76
  5008.7  242.26  5019.8  248.67  5027.8  248.83  5037.1  252.56  5133.6  255.59
  5239.9   258.5    5337  257.85  5359.1  259.07  5413.3  257.74  5716.1  260.49
  6309.8  261.84  6434.8  265.27    6550  270.66  6784.9  284.95  6881.9  287.25
#Mann= 7 ,-1 , 0
  4372.2     .05       0  4728.6      .1       0  5002.7     .07       0
  5008.7      .1       0  5133.6     .16       0  5239.9      .1       0
  6434.8     .05       0
Bank Sta=4928.5,5037.1
XS Rating Curve= 0 ,0
Exp/Cntr=0.3,0.1

Type RM Length L Ch R = 1 ,113234  ,519,519,519
BEGIN DESCRIPTION:
Mapping XS 85d0f302
END DESCRIPTION:
XS GIS Cut Line= 3
      2231190.42     13229555.83      2231043.23     13227874.69
      2230191.91     13226164.31
#Sta/Elev= 30
  4478.4   270.2  4569.7  269.76  4617.9   268.1  4807.8  257.81  4939.1  253.26
  4969.2  250.26  4979.3  246.99  4989.3  245.88  4996.4  239.98  4999.1  239.48
  5002.4  239.98  5009.4  240.22  5024.9  251.59  5059.6  253.03  5210.2   258.7
  5581.6  258.63  5792.4  257.73  5822.5   255.7  5827.7  256.45  5832.7  255.01
  5862.6  252.94  5922.9  251.38    5953  252.92  5973.1  257.74  5983.1  258.03
  6252.1  257.07  6347.3  259.46  6795.1  262.86  7444.4  264.05  8076.5  266.78
#Mann= 4 ,-1 , 0
  4478.4     .05       0  4807.8      .1       0  4996.4     .07       0
  5002.4      .1       0
#XS Ineff= 1 ,-1
 5520.81 6453.47  258.76
Permanent Ineff=
       F
Bank Sta=4939.1,5059.6
XS Rating Curve= 0 ,0
Exp/Cntr=0.3,0.1

Type RM Length L Ch R = 1 ,112715  ,519,519,519
BEGIN DESCRIPTION:
Mapping XS a0a18b65
END DESCRIPTION:
XS GIS Cut Line= 3
      2231236.94     13229648.71      2231562.27     13229331.12
      2232127.81     13226735.87
#Sta/Elev= 30
    4140  267.76  4460.1  258.85  4732.3  256.23  4803.7  257.29    4947  252.62
  4972.5  249.83  4995.2  240.73  4997.9  240.23  5001.2  240.73  5021.6  244.34
  5028.9  249.29  5039.1   251.5  5065.6  253.04  5172.2  257.25  5628.8  259.02
  5962.1  252.91  5990.9  255.63  6042.1  252.27  6055.1  250.42  6062.6  247.15
  6104.2  255.99  6175.2  253.68  6241.1  255.96  6427.2   256.9  6502.7  256.15
  6533.4  251.88  6594.8  256.55  6789.2  262.44  7176.5   280.2  7250.8  281.79
#Mann= 4 ,-1 , 0
    4140     .05       0  4732.3      .1       0  4995.2     .07       0
  5001.2      .1       0
#XS Ineff= 1 ,-1
 5641.34  6682.7  259.02
Permanent Ineff=
       F
Bank Sta=4947,5065.6
XS Rating Curve= 0 ,0
Exp/Cntr=0.3,0.1

Type RM Length L Ch R = 1 ,112196  ,548,548,548
BEGIN DESCRIPTION:
Mapping XS 5d51a1fc
END DESCRIPTION:
XS GIS Cut Line= 2
      2231066.47     13230710.07      2232786.27     13228114.89
#Sta/Elev= 30
  3081.5  274.15  3221.4  272.12  3259.2  268.93  3329.7  265.86  3397.3  263.57
  3513.5   261.2  3525.5  261.09  3698.6  259.35  3912.6  258.22  4005.1  258.38
  4283.3  260.36    4657  255.71  4939.1  252.29  4981.1  243.82  4993.2  239.03
  4995.9  238.53  4999.2  239.03  5017.2  246.48  5098.5  252.42  5108.1  253.08
  5148.7  254.87  5228.3  253.12    5285  250.35  5328.7  252.29  5342.1  249.29
  5351.2  251.93  5400.7  243.73  5495.6  252.09  6120.7  266.92  6194.8  268.45
#Mann= 15 ,-1 , 0
  3081.5      .1       0  3259.2     .08       0  3329.7     .05       0
  3397.3     .08       0  3513.5     .05       0  3525.5     .08       0
  3698.6     .05       0  3912.6      .1       0  4005.1     .05       0
    4657      .1       0  4993.2     .07       0  4999.2      .1       0
  5108.1     .16       0  5228.3      .1       0  6120.7     .08       0
#XS Ineff= 1 ,-1
 5148.77 5683.91  254.82
Permanent Ineff=
       F
Bank Sta=4939.1,5098.5
XS Rating Curve= 0 ,0
Exp/Cntr=0.3,0.1

Type RM Length L Ch R = 1 ,111648  ,553,553,553
BEGIN DESCRIPTION:
RAMIRENA CREEK 119.0
END DESCRIPTION:
XS GIS Cut Line= 3
       2231415.1     13231043.17      2232336.97     13229974.12
      2232972.23     13228416.95
#Sta/Elev= 30
  2963.4  274.02    3048     273  3106.8  269.98  3310.2  263.03  4095.1  259.43
  4381.9  260.24  4573.4  255.48  4597.8  253.57  4620.5  254.85  4678.8  253.57
  4784.2  253.21  4858.1  253.29  4901.3  247.32  4923.6  247.16  4942.7  249.23
  4972.1  245.09  4998.5  238.35  5001.3  237.85  5004.5  238.35  5025.6  246.96
    5055  247.68  5073.6  250.79    5079  248.88  5095.7  251.14  5138.9  252.07
  5376.5  253.09  5608.4  261.43  5840.9  272.18  5977.3  275.23  6056.8   274.8
#Mann= 10 ,-1 , 0
  2963.4      .1       0  3106.8     .05       0  4095.1      .1       0
  4381.9     .05       0  4573.4      .1       0  4678.8     .05       0
  4784.2     .08       0  4923.6      .1       0  4998.5     .07       0
  5004.5      .1       0
Bank Sta=4942.7,5073.6
XS Rating Curve= 0 ,0
Exp/Cntr=0.3,0.1

Type RM Length L Ch R = 1 ,111095  ,561,561,561
BEGIN DESCRIPTION:
Mapping XS ebadc261
END DESCRIPTION:
XS GIS Cut Line= 3
      2232267.28     13230694.56      2232964.47      13230136.8
       2233072.8     13228473.17
#Sta/Elev= 30
    3716  258.73    3742  258.91  3878.5  256.93  4579.7   255.2  4627.1  255.11
    4634  255.05  4668.9  255.07  4759.1   252.4  4839.8  252.66    4887  251.26
  4899.4  252.22  4929.5  250.98  4938.6   248.1  4959.5  246.53  4969.6  246.95
  4996.6  236.76  4999.4  236.26  5002.6  236.76  5019.7  244.11  5059.7  249.56
    5190   249.9  5230.1  251.75  5270.2  252.32  5410.5  250.85  5560.8  252.13
    5671  255.14  5911.5  263.64  5951.6  265.87    6142  272.98    6276  273.74
#Mann= 9 ,-1 , 0
    3716      .1       0    3742     .05       0  4579.7      .1       0
  4627.1     .05       0    4634      .1       0  4839.8     .05       0
  4938.6      .1       0  4996.6     .07       0  5002.6      .1       0
Bank Sta=4929.5,5059.7
XS Rating Curve= 0 ,0
Exp/Cntr=0.3,0.1

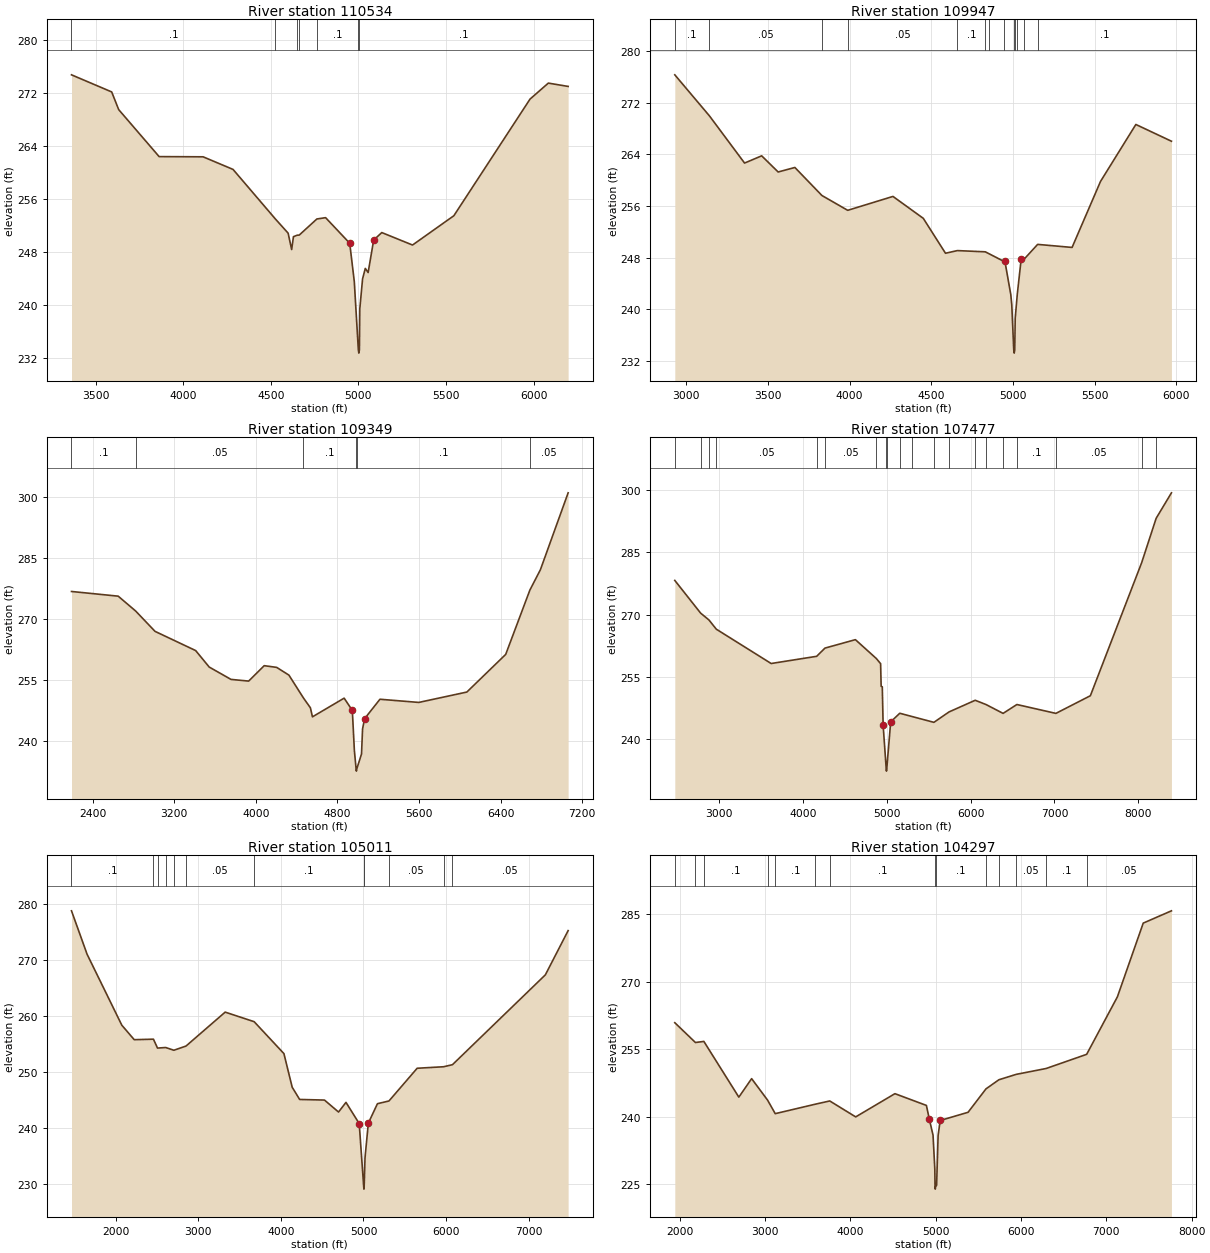
Type RM Length L Ch R = 1 ,110534  ,587,587,587
BEGIN DESCRIPTION:
RAMIRENA CREEK 118.0
END DESCRIPTION:
XS GIS Cut Line= 5
      2233719.63     13231215.41      2233643.24     13230329.85
      2233552.96     13229798.75      2233309.91     13229083.47
      2233122.42      13228458.5
#Sta/Elev= 30
  3362.2  274.74  3591.6  272.16  3631.7  269.49  3862.6   262.4  4113.5  262.37
  4284.5  260.47    4525  253.03    4599  250.85  4619.2  248.38  4629.4  250.32
  4650.5  250.54  4662.4  250.56  4763.2  252.99  4812.9  253.19  4950.7  249.33
  4976.8  243.55  4999.9  233.25  5002.7  232.75  5005.9  233.25  5008.2  239.43
  5024.1  243.96  5039.6  245.53  5055.8  244.91  5087.5  249.81  5133.7  250.94
  5309.3  249.06  5545.2  253.48  5980.2  271.08  6084.6  273.49  6197.7  272.99
#Mann= 7 ,-1 , 0
  3362.2      .1       0    4525     .05       0  4650.5      .1       0
  4662.4     .05       0  4763.2      .1       0  4999.9     .07       0
  5005.9      .1       0
Bank Sta=4950.7,5087.5
XS Rating Curve= 0 ,0
Exp/Cntr=0.3,0.1

Type RM Length L Ch R = 1 ,109947  ,598,598,598
BEGIN DESCRIPTION:
RAMIRENA CREEK 117.0
END DESCRIPTION:
XS GIS Cut Line= 3
      2233966.16     13231173.72      2234174.49     13229611.25
       2233382.8     13228382.04
#Sta/Elev= 30
  2930.9  276.29  3142.8  269.94  3357.7  262.64  3462.4  263.76  3563.3  261.26
  3665.4  261.96  3831.1  257.62  3988.8  255.33  4265.6  257.48  4451.1  254.09
    4587  248.69  4659.5   249.1  4830.6  248.91  4852.9  248.62  4944.5  247.43
  4950.1   247.5  4986.5  242.29  4992.4  240.75  5004.6  233.74  5007.3  233.24
  5010.6  233.74  5013.5  238.64  5026.2  242.34  5049.8  247.74  5064.3  247.67
  5150.7  250.06  5361.4  249.59  5535.4   259.8  5751.6  268.61  5969.3  266.02
#Mann= 13 ,-1 , 0
  2930.9      .1       0  3142.8     .05       0  3831.1      .1       0
  3988.8     .05       0  4659.5      .1       0  4830.6     .12       0
  4852.9      .1       0  4944.5     .12       0  5004.6     .07       0
  5010.6     .12       0  5026.2      .1       0  5064.3     .12       0
  5150.7      .1       0
Bank Sta=4950.1,5049.8
XS Rating Curve= 0 ,0
Exp/Cntr=0.3,0.1

Type RM Length L Ch R = 1 ,109349  ,1872,1872,1872
BEGIN DESCRIPTION:
RAMIRENA CREEK 116.0
END DESCRIPTION:
XS GIS Cut Line= 3
      2234125.42     13231722.63      2234507.37     13229760.84
      2234281.67     13226896.25
#Sta/Elev= 30
  2191.3  276.74  2649.3  275.59    2821  271.93  3010.8  266.94  3409.5  262.22
  3542.4  258.17  3755.9  255.14  3929.1  254.72  4081.9  258.51    4204  258.09
  4324.3  256.19  4466.9  250.57    4535  248.16    4555  245.94    4866  250.53
  4946.3   247.5  4966.3   237.7  4983.4   233.1  4986.1   232.6  4989.4   233.1
  5036.5  236.82  5046.6  242.97  5066.6  245.48  5217.1  250.26  5598.3  249.48
  6069.7  252.03  6450.9  261.28  6687.9  277.07  6791.2  282.08  7063.4  300.98
#Mann= 6 ,-1 , 0
  2191.3      .1       0    2821     .05       0  4466.9      .1       0
  4983.4     .07       0  4989.4      .1       0  6687.9     .05       0
Bank Sta=4946.3,5066.6
XS Rating Curve= 0 ,0
Exp/Cntr=0.3,0.1

Type RM Length L Ch R = 1 ,107477  ,2466,2466,2466
BEGIN DESCRIPTION:
RAMIRENA CREEK 114.0
END DESCRIPTION:
XS GIS Cut Line= 3
      2235310.05     13232557.09      2235441.52     13229688.61
      2234557.06     13226772.27
#Sta/Elev= 30
  2475.2  278.19  2783.3  270.33  2882.1  268.69  2969.7  266.48  3623.6  258.23
    4166  259.96  4264.8  261.93  4627.7  263.96  4876.9  259.43    4928  258.19
  4934.5  252.75    4948  252.64    4958  243.47  4995.1  232.88  4997.8  232.38
  5001.1  232.88  5048.1  244.21  5156.5  246.28  5303.6  245.49  5563.3   244.1
  5743.4   246.6  6055.4   249.4    6185  248.37  6387.8  246.25  6552.1  248.38
  7017.2  246.25    7428  250.49  8038.9  282.43    8212  293.11  8394.2  299.23
#Mann= 20 ,-1 , 0
  2475.2      .1       0  2783.3     .05       0  2882.1      .1       0
  2969.7     .05       0    4166     .08       0  4264.8     .05       0
  4876.9      .1       0  4995.1     .07       0  5001.1      .1       0
  5156.5     .05       0  5303.6      .1       0  5563.3     .05       0
  5743.4      .1       0  6055.4     .05       0    6185      .1       0
  6387.8     .05       0  6552.1      .1       0  7017.2     .05       0
  8038.9      .1       0    8212     .05       0
Bank Sta=4958,5048.1
XS Rating Curve= 0 ,0
Exp/Cntr=0.3,0.1

Type RM Length L Ch R = 1 ,105011  ,714,714,714
BEGIN DESCRIPTION:
RAMIRENA CREEK 113.0
END DESCRIPTION:
XS GIS Cut Line= 4
      2236409.06     13232135.54      2236333.11     13230030.51
      2236213.75     13227903.77      2235433.37     13226310.51
#Sta/Elev= 30
  1466.4  278.86  1655.2  271.09  2075.5   258.4  2225.6  255.81  2458.1   255.9
  2507.4  254.31  2606.4  254.41  2705.3  253.92  2852.1  254.67  3326.3  260.74
    3677  259.03  4037.2  253.32  4137.3  247.31  4227.5  245.12    4528  245.01
  4698.2  242.87  4788.4   244.6  4948.6   240.8  5002.5  229.58  5005.3  229.08
  5008.5  229.58  5018.7  234.68  5058.8  240.88    5169  244.36  5308.8  244.85
  5649.7   250.7  5969.6  250.97  6077.2  251.34  7201.4  267.41    7477  275.32
#Mann= 12 ,-1 , 0
  1466.4      .1       0  2458.1     .08       0  2507.4      .1       0
  2606.4     .08       0  2705.3      .1       0  2852.1     .05       0
    3677      .1       0  5002.5     .07       0  5008.5      .1       0
  5308.8     .05       0  5969.6      .1       0  6077.2     .05       0
Bank Sta=4948.6,5058.8
XS Rating Curve= 0 ,0
Exp/Cntr=0.3,0.1

Type RM Length L Ch R = 1 ,104297  ,878,878,878
BEGIN DESCRIPTION:
Mapping XS bbe0b536
END DESCRIPTION:
XS GIS Cut Line= 3
       2237090.9     13231457.55      2237055.05     13228828.06
      2236135.28     13225770.12
#Sta/Elev= 30
  1940.1   260.9  2182.1   256.5  2280.9  256.74  2690.9  244.36  2840.9  248.47
  3028.5  243.68  3117.7  240.69  3589.2   242.8    3757  243.51    4061  239.97
    4521  245.13    4890  242.52    4923  239.58  4967.9  235.91  4988.8  228.35
  4991.3  224.42    4994  223.92  4997.3  224.42  5009.7  224.77  5027.3  235.81
  5051.4  239.17  5378.4  240.99  5588.9   246.2  5739.7  248.22  5942.7  249.42
  6292.9  250.72    6769  253.87  7129.5  266.65  7432.3  283.03  7763.1  285.76
#Mann= 14 ,-1 , 0
  1940.1      .1       0  2182.1     .08       0  2280.9      .1       0
  3028.5     .05       0  3117.7      .1       0  3589.2     .16       0
    3757      .1       0  4991.3     .07       0  4997.3      .1       0
  5588.9     .05       0  5739.7      .1       0  5942.7     .05       0
  6292.9      .1       0    6769     .05       0
Bank Sta=4923,5051.4
XS Rating Curve= 0 ,0
Exp/Cntr=0.3,0.1

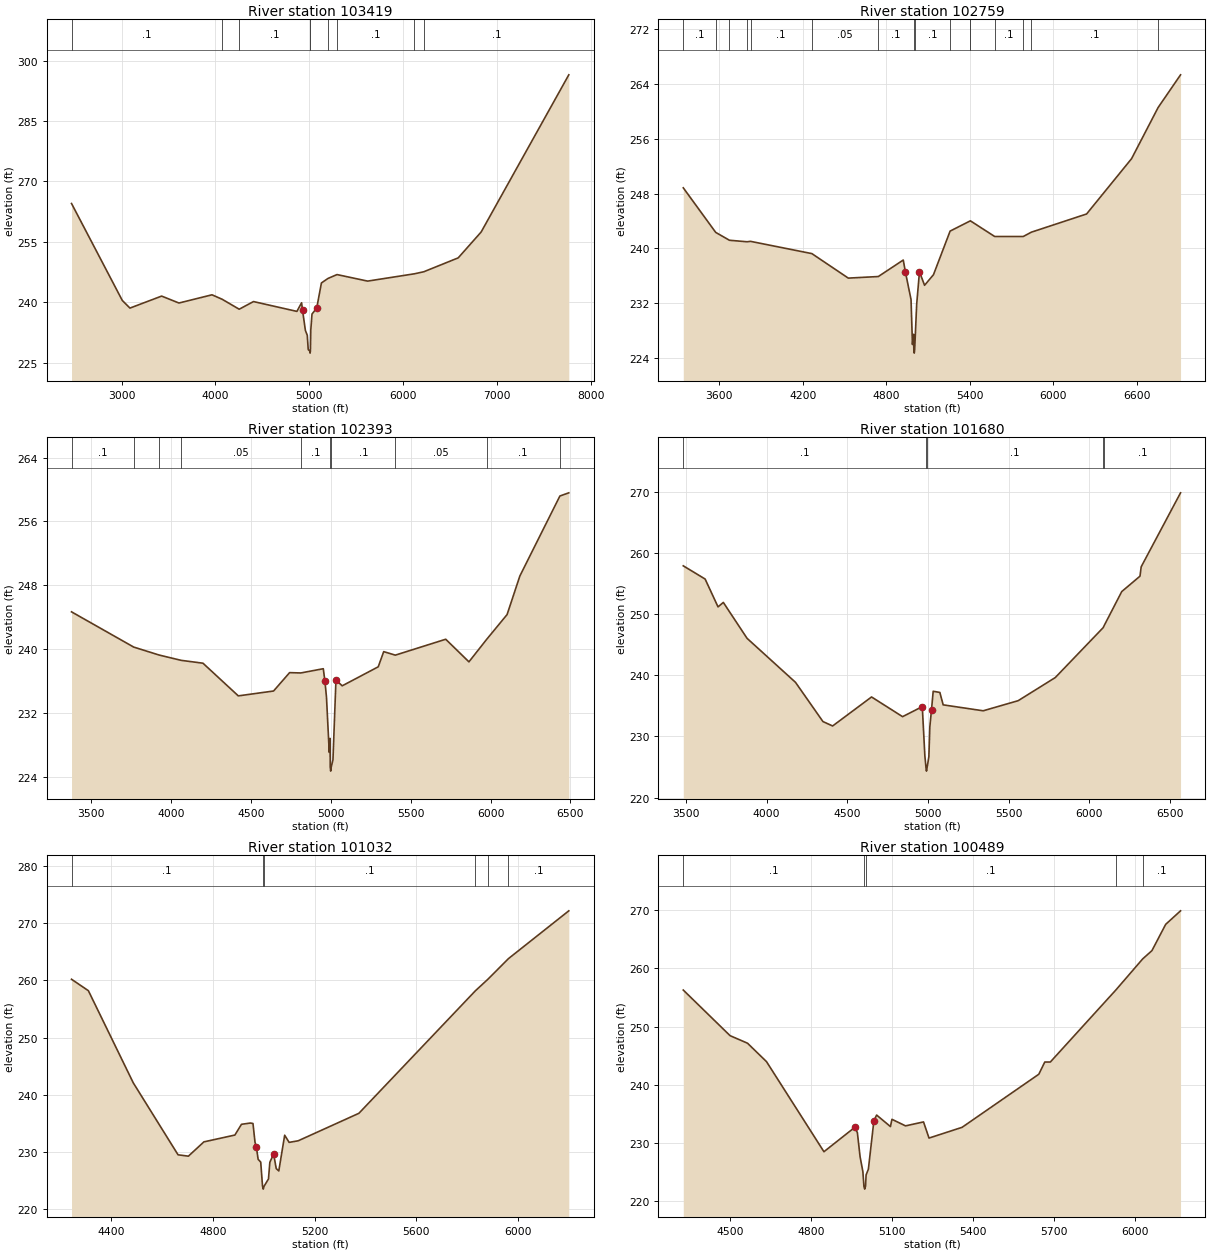
Type RM Length L Ch R = 1 ,103419  ,660,660,660
BEGIN DESCRIPTION:
RAMIRENA CREEK 112.0
END DESCRIPTION:
XS GIS Cut Line= 4
       2237891.7     13230895.81       2237640.7     13229724.47
      2237987.31     13226437.65      2238501.26     13225828.08
#Sta/Elev= 30
  2467.3  264.51  3008.3  240.44  3090.1  238.54  3427.6  241.52  3612.3   239.8
  3964.5  241.84    4073  240.73  4254.5  238.26  4406.9  240.16  4869.5  237.72
  4919.4  239.86  4929.8  237.97    4960     233  4980.1  231.79  4990.2  228.25
  5007.3  227.86    5010  227.36  5013.3  227.86  5017.4  233.06  5030.4  237.06
  5080.6  238.53  5130.9  244.78  5200.7   245.9  5296.9  246.86  5623.6  245.24
  6121.5  247.05  6221.9  247.56    6589  251.01  6833.3  257.43  7767.6  296.45
#Mann= 9 ,-1 , 0
  2467.3      .1       0    4073     .16       0  4254.5      .1       0
  5007.3     .07       0  5013.3      .1       0  5200.7     .16       0
  5296.9      .1       0  6121.5     .16       0  6221.9      .1       0
Bank Sta=4929.8,5080.6
XS Rating Curve= 0 ,0
Exp/Cntr=0.3,0.1

Type RM Length L Ch R = 1 ,102759  ,366,366,366
BEGIN DESCRIPTION:
RAMIRENA CREEK 111.0
END DESCRIPTION:
XS GIS Cut Line= 4
      2238390.04     13230203.58      2238390.04     13228720.46
      2238543.13     13227543.52      2238944.58     13226731.06
#Sta/Elev= 30
  3340.4  248.84  3573.6  242.33  3672.4  241.18  3799.4  240.96  3824.2  241.02
  4265.2  239.23  4527.1  235.65  4742.9  235.88  4922.4  238.29  4938.1  236.52
  4978.4  232.51  4988.5  225.95  4996.5  227.44  4998.5  225.19  5001.3  224.69
  5004.5  225.19  5018.8  231.77  5038.9  236.58  5075.6   234.6  5139.8  236.15
  5259.4  242.52  5403.3     244    5405  244.02  5579.9  241.73  5785.4  241.73
  5843.6  242.36  6240.9  245.02  6564.4   253.1  6755.2  260.57  6916.6  265.35
#Mann= 16 ,-1 , 0
  3340.4      .1       0  3573.6     .16       0  3672.4      .1       0
  3799.4     .16       0  3824.2      .1       0  4265.2     .05       0
  4742.9      .1       0  4998.5     .07       0  5004.5      .1       0
  5259.4     .16       0  5403.3      .1       0    5405     .16       0
  5579.9      .1       0  5785.4     .16       0  5843.6      .1       0
  6755.2     .05       0
Bank Sta=4938.1,5038.9
XS Rating Curve= 0 ,0
Exp/Cntr=0.3,0.1

Type RM Length L Ch R = 1 ,102393  ,713,713,713
BEGIN DESCRIPTION:
RAMIRENA CREEK 110.0
END DESCRIPTION:
XS GIS Cut Line= 3
      2238629.25     13230127.09      2238773.46       13228509.
      2239174.66     13227074.66
#Sta/Elev= 30
  3375.5  244.68  3764.8  240.27  3924.6  239.27  4061.7  238.61  4198.6  238.25
  4419.9  234.16  4640.7  234.77  4741.1  237.07  4811.2  237.03    4952  237.56
    4962  236.05    4972     234  4989.4  227.09  4994.4  228.84  4995.6  225.24
  4998.3  224.74  5001.6  225.24  5012.6  226.16  5031.3  236.14  5070.6  235.42
  5296.2   237.8  5330.3   239.7    5403  239.26  5718.7  241.25  5864.1  238.42
  5974.4  241.22  6102.9  244.34    6183  249.17  6433.6  259.18  6489.4  259.58
#Mann= 10 ,-1 , 0
  3375.5      .1       0  3764.8     .16       0  3924.6      .1       0
  4061.7     .05       0  4811.2      .1       0  4995.6     .07       0
  5001.6      .1       0    5403     .05       0  5974.4      .1       0
  6433.6     .05       0
Bank Sta=4962,5031.3
XS Rating Curve= 0 ,0
Exp/Cntr=0.3,0.1

Type RM Length L Ch R = 1 ,101680  ,648,648,648
BEGIN DESCRIPTION:
RAMIRENA CREEK 109.0
END DESCRIPTION:
XS GIS Cut Line= 4
      2239356.47     13230012.17      2239385.17     13228883.12
      2239643.53     13227878.42      2240235.97     13227180.86
#Sta/Elev= 30
  3483.2  257.87  3618.6  255.71  3698.6  251.16  3731.4  251.89  3878.6  246.02
  4178.7  238.83  4348.8  232.42  4408.8   231.7  4650.1  236.44  4842.4  233.22
  4964.6  234.86  4980.5  226.82  4987.8  224.82  4990.5  224.32  4993.8  224.82
  5005.3  226.68  5011.4  231.57  5021.8  234.38  5032.1  237.37  5073.4  237.18
    5094  235.15  5341.9  234.18  5558.7  235.83  5788.8  239.61  6085.4  247.76
  6092.1  248.12  6200.7  253.66  6313.8  256.18  6321.2  257.71  6565.2   269.8
#Mann= 5 ,-1 , 0
  3483.2      .1       0  4987.8     .07       0  4993.8      .1       0
  6085.4     .05       0  6092.1      .1       0
Bank Sta=4964.6,5021.8
XS Rating Curve= 0 ,0
Exp/Cntr=0.3,0.1

Type RM Length L Ch R = 1 ,101032  ,543,543,543
BEGIN DESCRIPTION:
RAMIRENA CREEK 108.0
END DESCRIPTION:
XS GIS Cut Line= 4
      2240036.67     13229273.14      2240036.67     13229028.34
      2240239.79     13227913.76       2240630.4     13227486.69
#Sta/Elev= 30
  4243.6   260.2  4309.9   258.2  4486.6  242.09  4662.7  229.52  4703.4  229.28
  4764.4  231.78  4886.3  232.97  4912.2  234.85  4947.3  235.07  4957.5  234.99
  4965.5  231.72  4970.6  230.96  4977.8  228.73    4988  228.24  4995.1  224.02
  4997.9  223.52  5001.1  224.02  5018.5   225.3  5023.9  228.22  5038.8  229.65
    5049  227.11  5059.1   226.7  5082.2  232.94  5099.8  231.69  5135.5  231.97
  5374.2  236.77  5832.5  258.18  5881.1  260.17  5962.8  263.81  6200.1  272.16
#Mann= 6 ,-1 , 0
  4243.6      .1       0  4995.1     .07       0  5001.1      .1       0
  5832.5     .05       0  5881.1     .08       0  5962.8      .1       0
Bank Sta=4970.6,5038.8
XS Rating Curve= 0 ,0
Exp/Cntr=0.3,0.1

Type RM Length L Ch R = 1 ,100489  ,689,689,689
BEGIN DESCRIPTION:
RAMIRENA CREEK 107.0
END DESCRIPTION:
XS GIS Cut Line= 4
      2240312.69      13229366.9      2240521.04      13229127.3
      2240760.62     13227960.63      2240817.91     13227632.53
#Sta/Elev= 30
  4327.4  256.28  4500.7  248.43  4565.3  247.13  4635.6  243.96  4848.3  228.45
  4961.8  232.62  4972.1  231.76  4982.3  227.55  4992.5  225.04  4996.4  222.51
  4999.2  222.01  5002.4  222.51  5004.5  224.46  5012.9  225.44  5033.3  233.78
  5043.5  234.76  5094.6  232.78  5100.2  234.03  5150.5   232.9  5217.1  233.58
  5237.5   230.8    5360  232.65  5644.1  241.79  5666.2  243.89  5686.7  243.89
  5929.4  256.29  6029.1  261.66  6063.1  263.07  6113.9  267.59    6169  269.92
#Mann= 5 ,-1 , 0
  4327.4      .1       0  4996.4     .07       0  5002.4      .1       0
  5929.4     .08       0  6029.1      .1       0
Bank Sta=4961.8,5033.3
XS Rating Curve= 0 ,0
Exp/Cntr=0.3,0.1

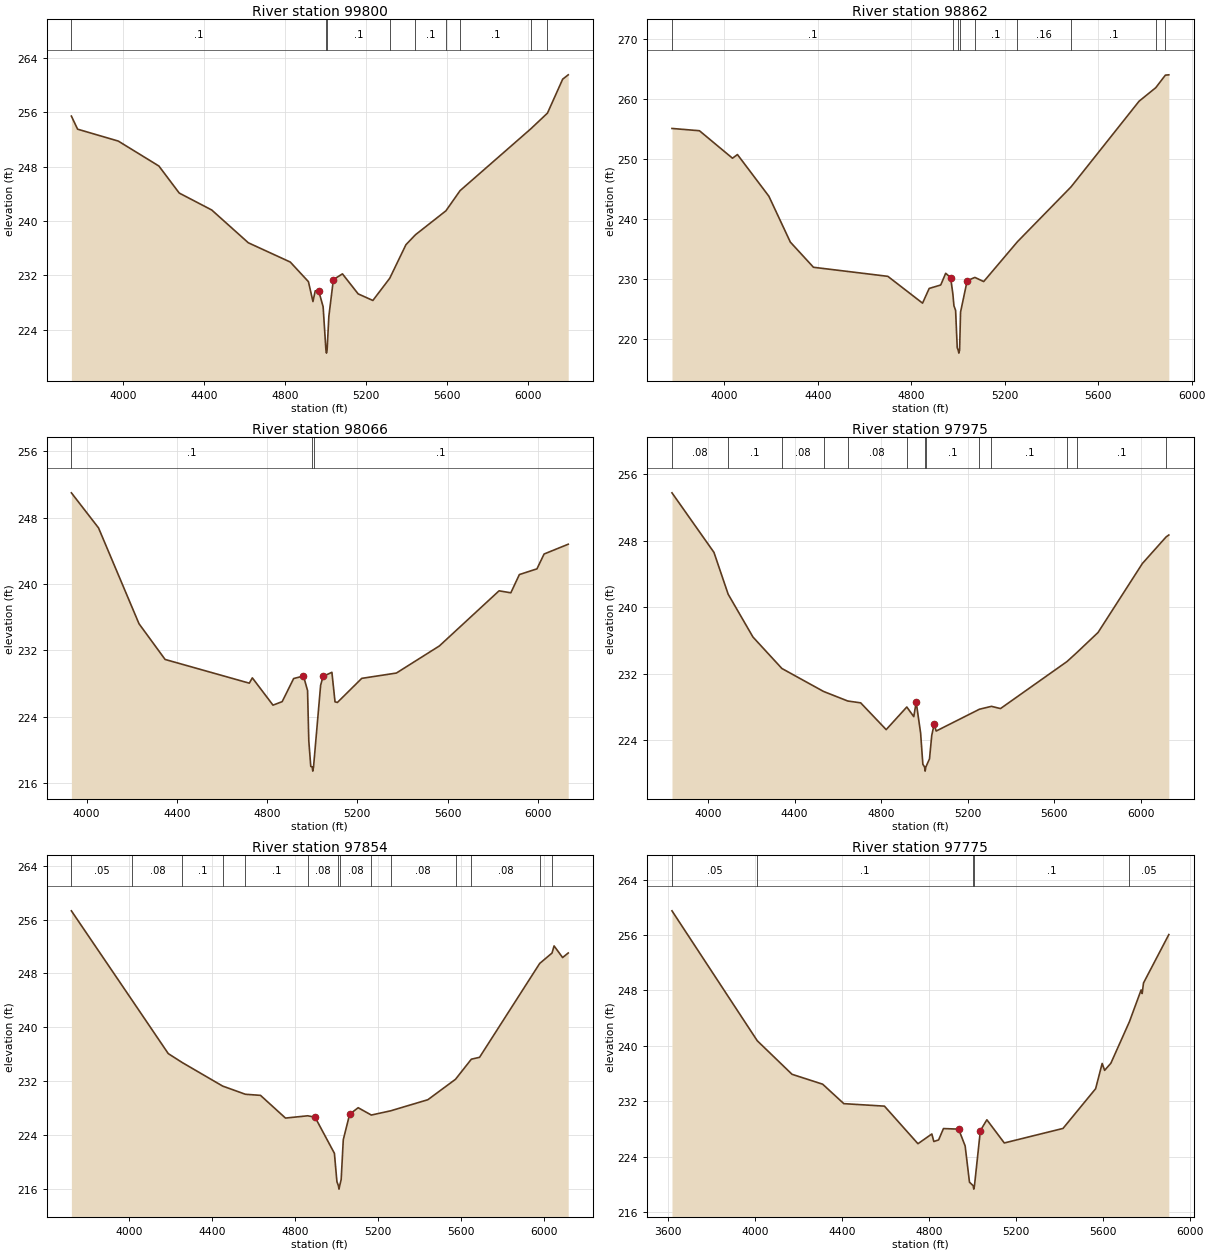
Type RM Length L Ch R = 1 ,99800   ,938,938,938
BEGIN DESCRIPTION:
RAMIRENA CREEK 106.0
END DESCRIPTION:
XS GIS Cut Line= 3
      2241011.84     13230117.46      2241088.39     13229198.89
        2241777.     13227831.22
#Sta/Elev= 30
  3744.9  255.47  3775.6  253.54  3976.3  251.79    4177  248.11  4277.3  244.13
  4437.9  241.63  4618.5   236.8  4825.7  233.96  4915.2  231.07  4937.6  228.14
  4948.8  229.72  4965.5  229.76  4987.8  227.37  5001.5  221.04  5004.3  220.54
  5007.5  221.04    5016  225.95  5038.4  231.37  5083.2  232.22  5160.7  229.27
  5233.3   228.3  5316.6  231.57  5396.7  236.52  5443.5  237.98    5594  241.51
  5663.8  244.48  6013.7  253.61  6095.4  255.91  6170.5  260.91  6197.9  261.55
#Mann= 9 ,-1 , 0
  3744.9      .1       0  5001.5     .07       0  5007.5      .1       0
  5316.6     .16       0  5443.5      .1       0    5594     .05       0
  5663.8      .1       0  6013.7     .16       0  6095.4      .1       0
Bank Sta=4965.5,5038.4
XS Rating Curve= 0 ,0
Exp/Cntr=0.3,0.1

Type RM Length L Ch R = 1 ,98862   ,796,796,796
BEGIN DESCRIPTION:
RAMIRENA CREEK 105.0
END DESCRIPTION:
XS GIS Cut Line= 3
      2241097.93     13230213.19      2242322.74     13228978.81
      2242604.16     13228713.35
#Sta/Elev= 30
  3776.5  255.13    3894  254.75  4035.4  250.17  4056.6  250.78    4191  243.84
  4282.9  236.19  4381.9  231.99  4700.1  230.48  4848.6  226.01  4876.9  228.46
  4926.4  229.04  4947.6  230.99  4968.8  230.26  4978.4  227.51  4982.9  225.57
    4990  224.81    4997  218.58  5001.1  218.18  5003.9  217.68  5007.1  218.18
  5011.2  224.53  5039.5  229.75  5072.4   230.3  5110.2  229.61  5254.6  236.25
  5483.9  245.39    5775  259.67  5846.5  261.93  5887.6  264.02  5902.3  264.07
#Mann= 9 ,-1 , 0
  3776.5      .1       0  4978.4     .16       0  5001.1     .07       0
  5007.1     .16       0  5072.4      .1       0  5254.6     .16       0
  5483.9      .1       0  5846.5     .08       0  5887.6      .1       0
Bank Sta=4968.8,5039.5
XS Rating Curve= 0 ,0
Exp/Cntr=0.3,0.1

Type RM Length L Ch R = 1 ,98066   ,91,91,91
BEGIN DESCRIPTION:
Mapping XS 207c343f
END DESCRIPTION:
XS GIS Cut Line= 4
      2241349.46     13230217.24      2242323.44     13230034.94
      2242443.24     13229982.86       2243469.3     13229644.31
#Sta/Elev= 30
  3932.8     251  4053.1  246.77  4232.5  235.21  4348.2   230.9  4721.3  228.04
  4734.8  228.68  4826.3  225.39    4867  225.81  4917.9   228.6  4961.5   228.9
  4979.5  227.15    4985  221.09  4993.8     218    5000  217.93  5002.7  217.43
    5006  217.93  5037.4  227.78  5048.3  228.86  5087.4  229.35  5101.2  225.79
  5111.7  225.71  5219.7  228.62  5373.2  229.26  5563.7  232.53  5828.3  239.18
  5880.4  238.94  5918.2  241.14  5996.2  241.83  6027.8  243.62  6134.8   244.8
#Mann= 3 ,-1 , 0
  3932.8      .1       0    5000     .07       0    5006      .1       0
Bank Sta=4961.5,5048.3
XS Rating Curve= 0 ,0
Exp/Cntr=0.3,0.1

Type RM Length L Ch R = 1 ,97975   ,121,121,121
BEGIN DESCRIPTION:
Mapping XS 6118f518
END DESCRIPTION:
XS GIS Cut Line= 3
      2241318.19     13230337.03      2242500.53     13230060.98
      2243556.81     13229821.63
#Sta/Elev= 30
  3833.3  253.77  4027.4  246.61  4093.1  241.58  4207.8  236.43  4341.5  232.65
    4534  229.89    4646  228.74  4705.7  228.52  4823.7   225.3    4919  228.02
  4951.3  226.86  4962.4  228.61  4982.9  224.88  4993.2  221.14  5001.1  220.81
  5003.9  220.31  5007.1  220.81    5024  221.79  5034.3  224.59  5045.5  225.96
  5054.8  225.13  5254.7  227.75  5310.4   228.1  5352.2  227.83    5660  233.49
  5705.1  234.56  5803.3  236.98  6008.4  245.28    6118  248.47  6130.5   248.7
#Mann= 13 ,-1 , 0
  3833.3     .08       0  4093.1      .1       0  4341.5     .08       0
    4534      .1       0    4646     .08       0    4919      .1       0
  5001.1     .07       0  5007.1      .1       0  5254.7     .08       0
  5310.4      .1       0    5660     .08       0  5705.1      .1       0
    6118     .08       0
Bank Sta=4962.4,5045.5
XS Rating Curve= 0 ,0
Exp/Cntr=0.3,0.1

Type RM Length L Ch R = 1 ,97854   ,79,79,79
BEGIN DESCRIPTION:
Mapping XS 8dbc9b00
END DESCRIPTION:
XS GIS Cut Line= 3
      2241286.97     13230430.78       2242609.9     13230144.32
      2243624.15     13229910.26
#Sta/Elev= 30
  3720.7  257.31  4014.8  243.94  4187.6  236.07  4256.1  234.72  4449.7  231.24
  4559.4  230.02  4632.1  229.86  4752.5  226.48  4859.7  226.82    4895  226.61
  4988.3  221.24  5000.4  217.02  5007.7  216.41  5010.4  215.91  5013.7  216.41
  5020.9  217.33  5031.1  223.27  5061.8  227.05  5102.8  228.02  5166.2  226.93
  5259.5  227.56  5438.7  229.21  5571.9  232.25  5648.3  235.24  5687.8  235.52
  5977.6  249.48  6037.1  251.03    6047  252.09  6088.1  250.36  6115.2  251.04
#Mann= 14 ,-1 , 0
  3720.7     .05       0  4014.8     .08       0  4256.1      .1       0
  4449.7     .08       0  4559.4      .1       0  4859.7     .08       0
  5007.7     .07       0  5013.7     .08       0  5166.2      .1       0
  5259.5     .08       0  5571.9      .1       0  5648.3     .08       0
  5977.6      .1       0  6037.1     .08       0
Bank Sta=4895,5061.8
XS Rating Curve= 0 ,0
Exp/Cntr=0.3,0.1

Type RM Length L Ch R = 1 ,97775   ,60,60,60
BEGIN DESCRIPTION:
Mapping XS d286e458
END DESCRIPTION:
XS GIS Cut Line= 3
      2241266.14     13230560.99      2242500.53     13230212.02
      2243504.24     13230154.82
#Sta/Elev= 30
  3616.6  259.51  4009.3  240.74  4169.5  235.89  4310.6  234.46    4408  231.65
  4595.1  231.29  4749.4  225.86  4813.3  227.27  4822.5  226.18  4844.5  226.41
  4866.8  228.05  4936.6  227.97  4966.7  225.54  4986.7   220.3  5003.7   219.8
  5006.5   219.3  5009.7   219.8  5036.8  227.75  5066.8  229.32    5147  225.97
  5417.4  228.07  5567.6  233.81  5597.7  237.46    5609  236.46  5637.8  237.49
  5723.2  243.49    5777  248.07    5782  247.56    5788  249.08  5904.7  256.08
#Mann= 5 ,-1 , 0
  3616.6     .05       0  4009.3      .1       0  5003.7     .07       0
  5009.7      .1       0  5723.2     .05       0
Bank Sta=4936.6,5036.8
XS Rating Curve= 0 ,0
Exp/Cntr=0.3,0.1