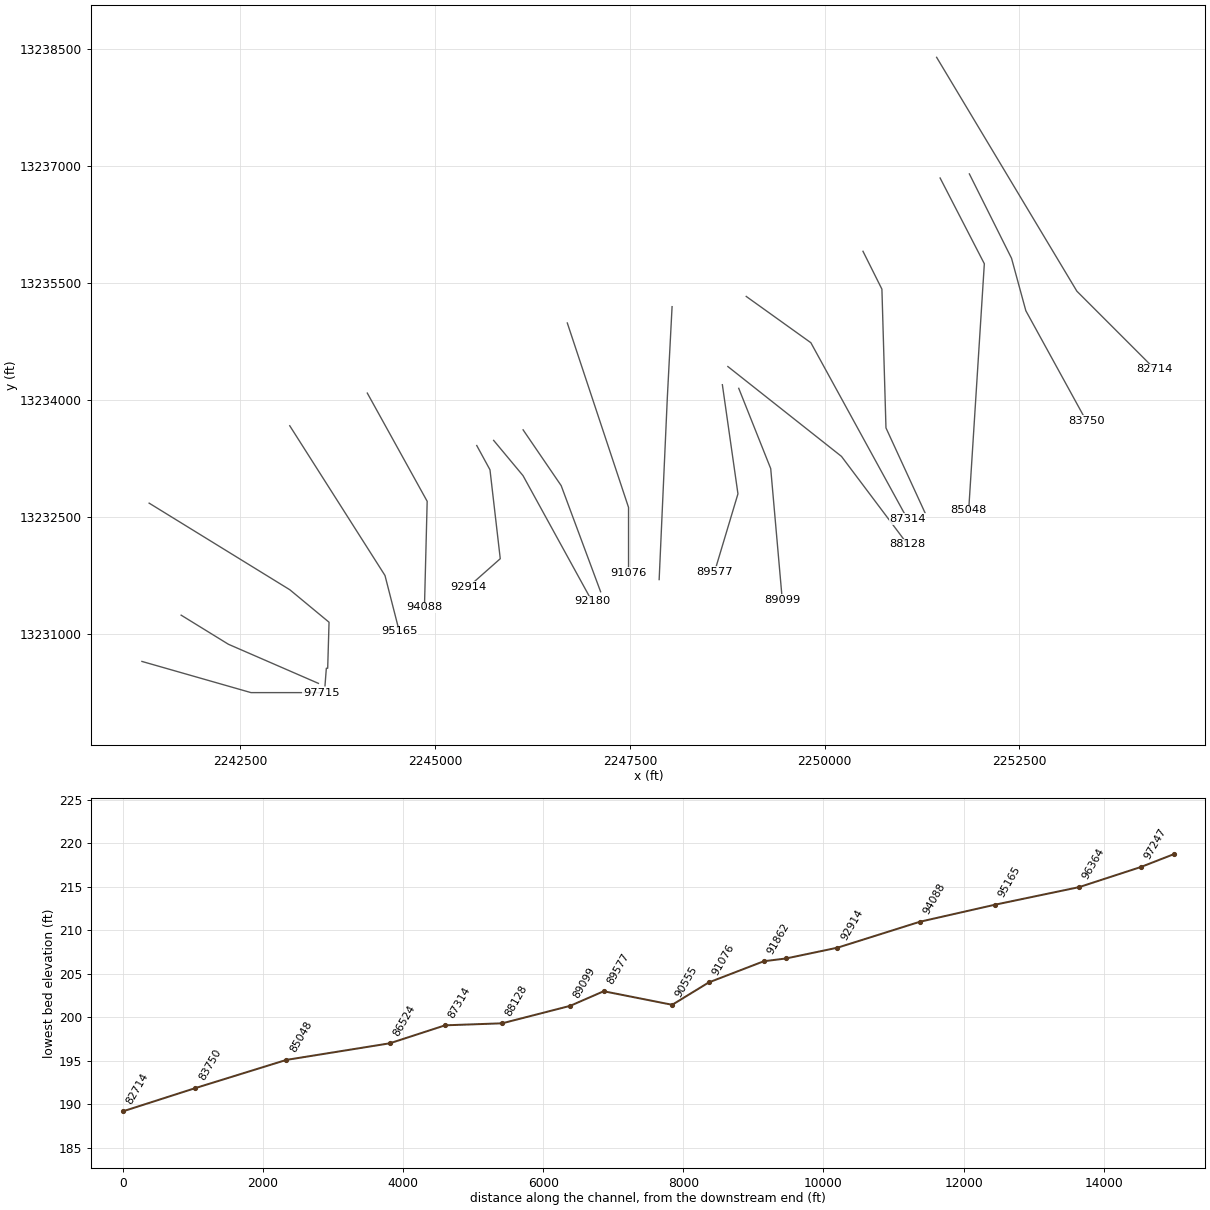
HEC-RAS study RAMIRENA CREEK.prj: RAMIRENA CREEK Base Level Engineering

--- RAMIRENA CREEK.g01 (geometry) --- (continued)

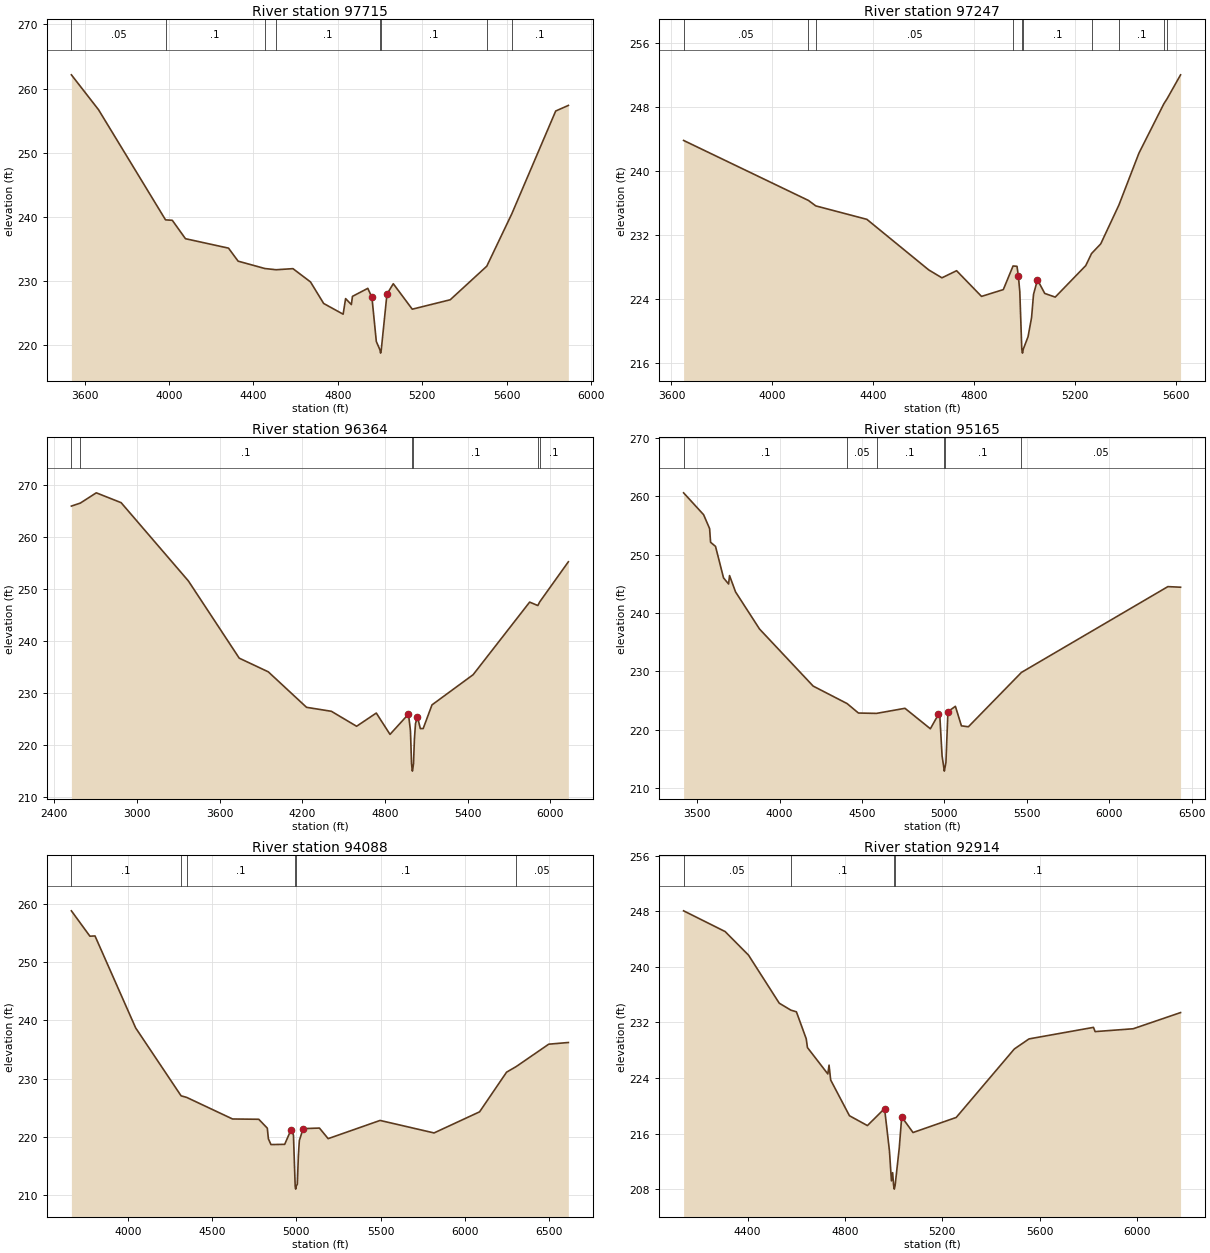
Type RM Length L Ch R = 1 ,97715   ,468,468,468
BEGIN DESCRIPTION:
RAMIRENA CREEK 103.0
END DESCRIPTION:
XS GIS Cut Line= 3
      2241237.72     13230646.86      2242637.72     13230246.85
      2243537.69     13230246.85
#Sta/Elev= 30
    3537  262.15  3665.7  256.71  3983.3  239.54  4015.4  239.47  4077.8   236.6
  4281.9  235.13  4327.4   233.1  4454.3  231.95  4507.4  231.76  4587.4  231.93
  4670.6  229.86    4733   226.5  4825.3  224.83    4837  227.26  4864.3  226.33
  4869.5  227.61  4942.3  228.86  4961.8  227.45  4982.6  220.57    5000  219.26
  5002.8  218.76    5006  219.26    5033  227.95    5063  229.58    5153  225.61
    5333  227.08  5506.2  232.31  5624.6  240.46    5833  256.51    5893  257.38
#Mann= 8 ,-1 , 0
    3537     .05       0  3983.3      .1       0  4454.3     .16       0
  4507.4      .1       0    5000     .07       0    5006      .1       0
  5506.2     .05       0  5624.6      .1       0
Bank Sta=4961.8,5033
XS Rating Curve= 0 ,0
Exp/Cntr=0.3,0.1

Type RM Length L Ch R = 1 ,97247   ,883,883,883
BEGIN DESCRIPTION:
RAMIRENA CREEK 102.0
END DESCRIPTION:
XS GIS Cut Line= 3
      2241741.04     13231240.42      2242347.71     13230867.09
      2243502.73     13230365.41
#Sta/Elev= 30
  3648.2  243.87  4143.6  236.37  4172.6  235.69  4375.3  234.01  4620.7  227.69
  4673.1   226.7  4731.2  227.59  4830.1  224.38  4916.6  225.23  4955.2  228.18
  4970.9  228.14  4976.3  226.93    4982  224.97  4989.9  217.79  4992.6  217.29
  4995.9  217.79  5014.7  219.34  5028.7  221.73  5036.5  224.64  5052.1  226.45
    5081  224.75  5122.5  224.29  5243.7  228.23  5266.7  229.74    5303  230.94
  5375.1  235.79  5454.6  242.28    5554  248.48  5565.6  249.04  5619.8  252.07
#Mann= 10 ,-1 , 0
  3648.2     .05       0  4143.6      .1       0  4172.6     .05       0
  4955.2      .1       0  4989.9     .07       0  4995.9      .1       0
  5266.7     .05       0  5375.1      .1       0    5554     .05       0
  5565.6      .1       0
Bank Sta=4976.3,5052.1
XS Rating Curve= 0 ,0
Exp/Cntr=0.3,0.1

Type RM Length L Ch R = 1 ,96364   ,1199,1199,1199
BEGIN DESCRIPTION:
Mapping XS 3755a9a2
END DESCRIPTION:
XS GIS Cut Line= 6
      2241330.27     13232677.51      2243135.84     13231566.39
      2243639.31     13231149.73      2243621.95     13230559.45
      2243604.59     13230559.45      2243587.23      13230333.8
#Sta/Elev= 30
  2523.8   265.9  2588.8  266.48  2704.6  268.45  2884.8  266.56  3373.1  251.52
  3742.2  236.68  3953.3  234.05    4231  227.23  4411.2  226.47  4594.3  223.59
  4737.2  226.13  4836.9  222.03    4971  225.93  4985.3  222.73  4993.2  216.42
  4996.7  215.47  4999.4  214.97  5002.7  215.47  5007.5  216.42    5014  221.15
  5021.8  224.07  5035.7  225.45    5057  223.14  5077.8  223.16  5141.6   227.7
  5440.3   233.5  5850.5  247.45    5910  246.79  5923.3  247.48  6131.6   255.2
#Mann= 6 ,-1 , 0
  2523.8     .05       0  2588.8      .1       0  4996.7     .07       0
  5002.7      .1       0    5910     .05       0  5923.3      .1       0
Bank Sta=4971,5035.7
XS Rating Curve= 0 ,0
Exp/Cntr=0.3,0.1

Type RM Length L Ch R = 1 ,95165   ,1077,1077,1077
BEGIN DESCRIPTION:
Mapping XS 8102f13e
END DESCRIPTION:
XS GIS Cut Line= 3
      2243134.97     13233670.31      2244357.43     13231749.31
       2244540.8      13231033.3
#Sta/Elev= 30
  3417.4  260.57  3538.8  256.83  3575.3  254.45  3581.2  252.11  3611.2   251.4
  3659.9  246.01  3690.4  244.97  3696.3  246.41  3732.7  243.62  3878.4  237.26
  4203.8   227.5  4409.7  224.51  4478.6  222.89  4588.2  222.83  4760.9   223.7
    4915   220.2  4963.8  222.64  4973.1  222.06  4986.1  215.58  4997.2  213.45
  4999.9  212.95  5003.2  213.45  5009.5  214.44  5021.7  223.13    5067  224.04
  5103.5   220.7  5145.8  220.54  5467.8  229.84  6356.5  244.52  6433.5  244.42
#Mann= 6 ,-1 , 0
  3417.4      .1       0  4409.7     .05       0  4588.2      .1       0
  4997.2     .07       0  5003.2      .1       0  5467.8     .05       0
Bank Sta=4963.8,5021.7
XS Rating Curve= 0 ,0
Exp/Cntr=0.3,0.1

Type RM Length L Ch R = 1 ,94088   ,1174,1174,1174
BEGIN DESCRIPTION:
RAMIRENA CREEK 101.0
END DESCRIPTION:
XS GIS Cut Line= 3
      2244130.41     13234089.43       2244898.8     13232701.08
      2244863.92     13231340.43
#Sta/Elev= 30
  3665.4  258.83  3775.2  254.47  3805.5  254.51  4046.6   238.7  4316.2  227.02
  4349.4  226.75  4621.4  223.04    4777  222.99  4827.5  221.46  4834.1  219.62
  4849.3  218.64  4930.6  218.68  4968.4  221.19  4982.7  220.27  4992.9  211.48
  4995.6  210.98  4998.9  211.48  5005.6  211.83  5011.9  216.79  5017.6  219.34
  5039.9  221.38  5136.7  221.48  5188.5  219.66  5496.5  222.79  5816.6  220.64
  6086.7  224.27  6246.8  231.09  6303.8  232.05  6496.8   235.9  6613.3  236.19
#Mann= 6 ,-1 , 0
  3665.4      .1       0  4316.2     .05       0  4349.4      .1       0
  4992.9     .07       0  4998.9      .1       0  6303.8     .05       0
Bank Sta=4968.4,5039.9
XS Rating Curve= 0 ,0
Exp/Cntr=0.3,0.1

Type RM Length L Ch R = 1 ,92914   ,734,734,734
BEGIN DESCRIPTION:
RAMIRENA CREEK 100.0
END DESCRIPTION:
XS GIS Cut Line= 4
       2245535.2     13233416.66      2245704.91     13233105.51
      2245836.91     13231964.66      2245432.11     13231606.93
#Sta/Elev= 30
  4136.8  248.07  4307.4  245.09  4403.7  241.69  4530.1  234.77  4577.9  233.77
  4600.6  233.53  4640.9  229.65    4646  228.38  4729.8  224.58  4734.8  225.85
  4741.5  223.71  4818.6  218.57  4892.5  217.15    4963   219.6  4983.1  213.52
  4991.2  209.19  4996.2  210.37  5000.3   208.5    5003     208  5006.3   208.5
  5023.4  213.92  5033.5   218.4    5080  216.15  5257.6  218.32  5496.5  228.18
  5556.9  229.63  5821.9  231.29  5828.6  230.68  5985.1  231.09  6179.9  233.42
#Mann= 4 ,-1 , 0
  4136.8     .05       0  4577.9      .1       0  5000.3     .07       0
  5006.3      .1       0
Bank Sta=4963,5033.5
XS Rating Curve= 0 ,0
Exp/Cntr=0.3,0.1

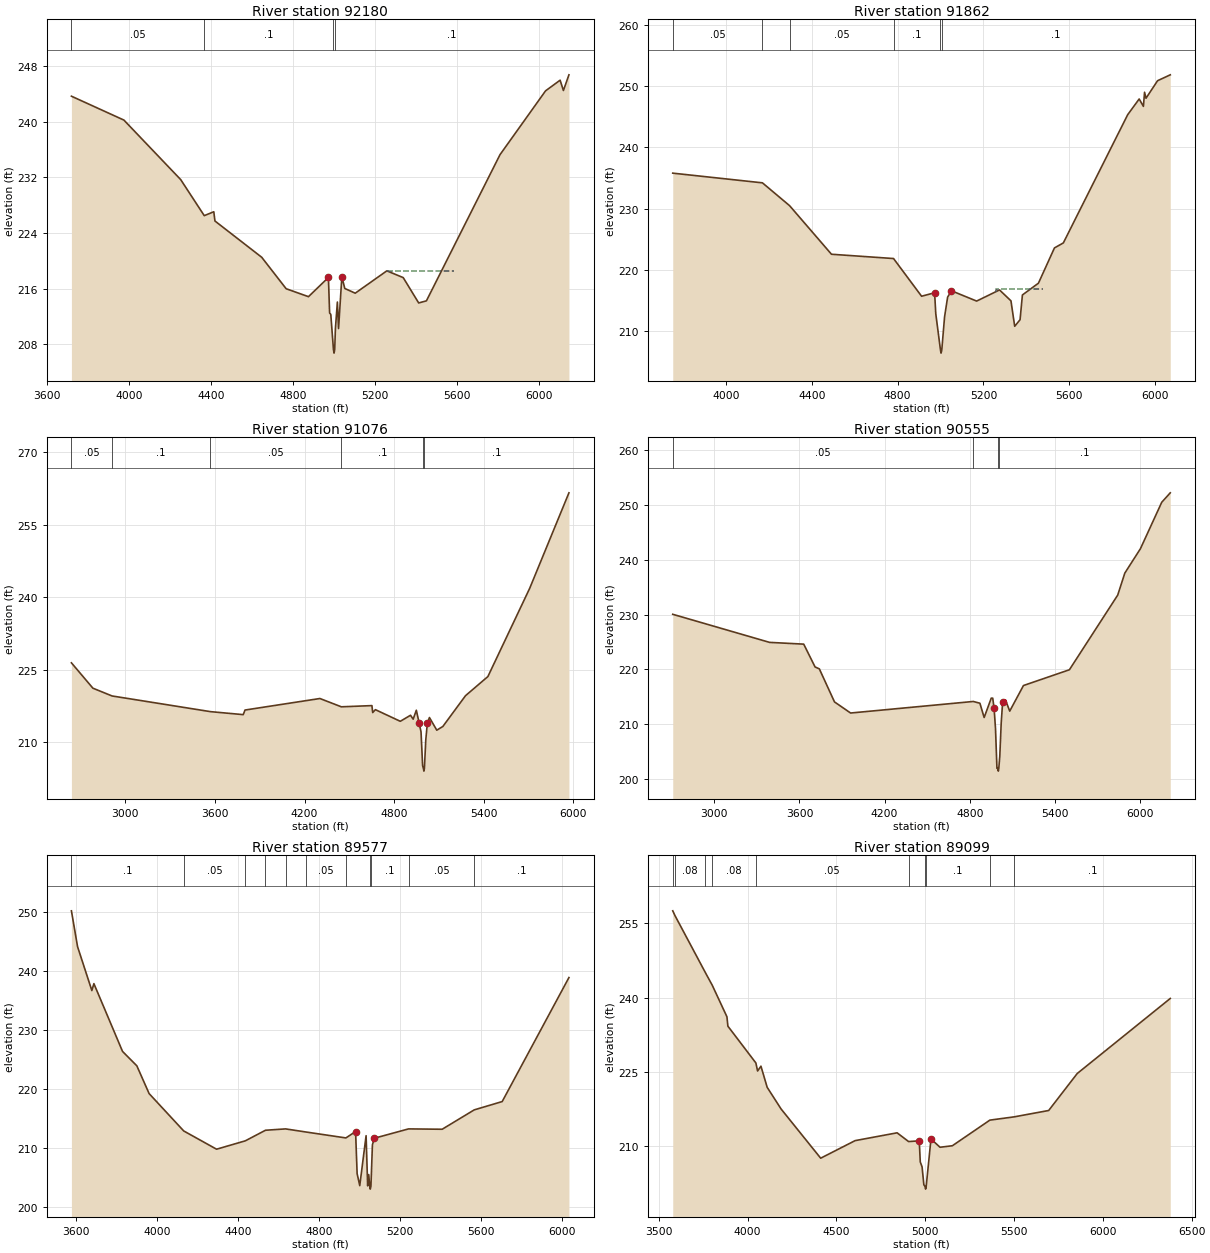
Type RM Length L Ch R = 1 ,92180   ,318,318,318
BEGIN DESCRIPTION:
RAMIRENA CREEK 99.0
END DESCRIPTION:
XS GIS Cut Line= 3
      2245752.02      13233482.7       2246129.2     13233030.09
      2247015.49      13231417.8
#Sta/Elev= 30
  3719.6  243.67  3975.8  240.24  4253.1  231.69  4368.2  226.51  4414.7  227.07
  4420.4  225.74  4648.7  220.53    4768  216.01  4876.9  214.87  4974.3  217.63
  4980.2  212.52  4985.9  212.33    4999  207.26  5001.7  206.76    5005  207.26
  5008.5  210.29  5018.1   214.1  5023.8  210.29  5039.9  217.73  5054.2  216.05
  5105.2  215.37  5259.6  218.58  5339.5  217.61    5415  213.97  5452.8  214.27
  5811.9  235.26  6034.5  244.44  6105.5  245.97  6121.6  244.49  6148.6  246.74
#Mann= 4 ,-1 , 0
  3719.6     .05       0  4368.2      .1       0    4999     .07       0
    5005      .1       0
#XS Ineff= 1 ,-1
 5258.15 5588.07  218.59
Permanent Ineff=
       F
Bank Sta=4974.3,5039.9
XS Rating Curve= 0 ,0
Exp/Cntr=0.3,0.1

Type RM Length L Ch R = 1 ,91862   ,786,786,786
BEGIN DESCRIPTION:
RAMIRENA CREEK 98.0
END DESCRIPTION:
XS GIS Cut Line= 3
      2246130.01     13233617.89      2246618.97     13232901.91
      2247125.01     13231540.85
#Sta/Elev= 30
  3751.6   235.8  4169.6  234.22  4296.1   230.5  4491.5  222.57  4780.8  221.87
  4911.5  215.72  4972.2  216.29  4977.6  212.88  4999.6  206.94  5002.3  206.44
  5005.6  206.94  5018.7  212.38  5032.9  215.58  5050.8  216.61  5168.1  214.93
  5274.8  216.75  5328.1  214.97  5345.5  210.82  5370.5  211.89  5381.5  215.93
  5456.2  217.85  5530.8   223.6  5572.3  224.42  5872.3  245.34  5925.8   247.9
  5945.5  246.69  5950.8     249  5957.6  248.02  6011.5  250.88  6070.7  251.84
#Mann= 6 ,-1 , 0
  3751.6     .05       0  4169.6      .1       0  4296.1     .05       0
  4780.8      .1       0  4999.6     .07       0  5005.6      .1       0
#XS Ineff= 1 ,-1
 5258.54 5477.72  216.86
Permanent Ineff=
       F
Bank Sta=4972.2,5050.8
XS Rating Curve= 0 ,0
Exp/Cntr=0.3,0.1

Type RM Length L Ch R = 1 ,91076   ,521,521,521
BEGIN DESCRIPTION:
RAMIRENA CREEK 97.0
END DESCRIPTION:
XS GIS Cut Line= 3
      2246697.55     13234988.82      2247483.42     13232622.49
      2247483.42      13231784.2
#Sta/Elev= 30
    2639  226.43  2782.8  221.18  2910.9  219.57  3569.9  216.32  3789.6   215.7
  3801.5  216.65    4303  219.04  4446.6  217.32  4651.3  217.57  4656.6  216.13
  4674.7  216.73  4841.3  214.32  4909.9  215.57  4927.6  214.76  4948.7  216.61
    4968  213.94  4980.3  212.11  4990.8  205.13  4996.7   204.5  4999.4     204
  5002.7   204.5  5011.9   210.4  5022.4  213.91  5036.6   215.1  5085.7  212.48
  5126.4  213.25    5278  219.62    5428  223.59    5708  241.87  5970.7  261.64
#Mann= 6 ,-1 , 0
    2639     .05       0  2910.9      .1       0  3569.9     .05       0
  4446.6      .1       0  4996.7     .07       0  5002.7      .1       0
Bank Sta=4968,5022.4
XS Rating Curve= 0 ,0
Exp/Cntr=0.3,0.1

Type RM Length L Ch R = 1 ,90555   ,978,978,978
BEGIN DESCRIPTION:
RAMIRENA CREEK 96.0
END DESCRIPTION:
XS GIS Cut Line= 3
      2248042.25     13235198.32      2247981.13     13234028.31
      2247876.35     13231696.87
#Sta/Elev= 30
  2707.3  230.07  3389.7  224.94    3630  224.62  3710.1  220.45  3740.2   220.1
  3846.9  214.07  3960.4  212.04  4824.7  214.15  4871.4  213.83  4901.4  211.22
  4951.4  214.76  4961.8  214.75  4971.5  212.91  4981.5  209.11  4991.5  201.94
  4998.5  201.93  5001.2  201.43  5004.5  201.93  5011.5  204.13  5021.5  210.22
  5031.5     214  5051.5  214.43  5081.6  212.39  5178.3  217.06    5502  219.94
  5842.3  233.57  5892.4  237.59  6002.5  242.05  6152.7  250.53  6212.7  252.25
#Mann= 4 ,-1 , 0
  2707.3     .05       0  4824.7      .1       0  4998.5     .07       0
  5004.5      .1       0
Bank Sta=4971.5,5031.5
XS Rating Curve= 0 ,0
Exp/Cntr=0.3,0.1

Type RM Length L Ch R = 1 ,89577   ,478,478,478
BEGIN DESCRIPTION:
RAMIRENA CREEK 95.0
END DESCRIPTION:
XS GIS Cut Line= 3
      2248687.72     13234196.88      2248887.72     13232796.85
      2248587.71     13231796.83
#Sta/Elev= 30
  3576.1  250.12  3606.4  244.06  3677.1  236.62  3687.2  237.79  3828.7  226.31
  3899.4  223.87    3960  219.17  4131.1  212.84  4293.3  209.75  4435.5  211.17
  4534.9  212.96  4634.3  213.19  4733.7  212.67  4932.4  211.66  4980.2  212.74
  4987.8  205.62  5000.8  203.58  5032.1  212.04  5039.9  203.54  5045.1  205.46
    5050  203.49  5052.7  202.99    5056  203.49  5063.4  210.51    5073  211.61
  5241.9  213.19    5408  213.13  5566.4  216.41  5704.6  217.82  6034.4  238.82
#Mann= 11 ,-1 , 0
  3576.1      .1       0  4131.1     .05       0  4435.5      .1       0
  4534.9     .05       0  4634.3      .1       0  4733.7     .05       0
  4932.4      .1       0    5050     .07       0    5056      .1       0
  5241.9     .05       0  5566.4      .1       0
Bank Sta=4980.2,5073
XS Rating Curve= 0 ,0
Exp/Cntr=0.3,0.1

Type RM Length L Ch R = 1 ,89099   ,971,971,971
BEGIN DESCRIPTION:
RAMIRENA CREEK 94.0
END DESCRIPTION:
XS GIS Cut Line= 3
      2248897.98     13234150.55      2249308.37      13233120.2
       2249456.8     13231434.99
#Sta/Elev= 30
  3578.8  257.55    3591  256.61    3760  245.23  3801.2  242.51  3883.8  236.14
  3889.2  234.24  4046.7  226.81  4056.4  225.18  4075.3  226.16  4110.3  221.89
  4188.6  217.51  4411.6  207.56  4605.4  211.11  4841.8  212.69  4906.6  210.92
  4966.4  211.07  4972.3  206.79  4982.4  205.81  4992.4   202.2  4999.4  201.81
  5002.2  201.31  5005.4  201.81  5032.5  211.44  5083.6  209.77    5153  210.08
  5363.9  215.25  5501.7  215.92  5695.1   217.2  5855.7  224.67  6379.6  239.84
#Mann= 10 ,-1 , 0
  3578.8     .05       0    3591     .08       0    3760     .05       0
  3801.2     .08       0  4046.7     .05       0  4906.6      .1       0
  4999.4     .07       0  5005.4      .1       0  5363.9     .05       0
  5501.7      .1       0
Bank Sta=4966.4,5032.5
XS Rating Curve= 0 ,0
Exp/Cntr=0.3,0.1

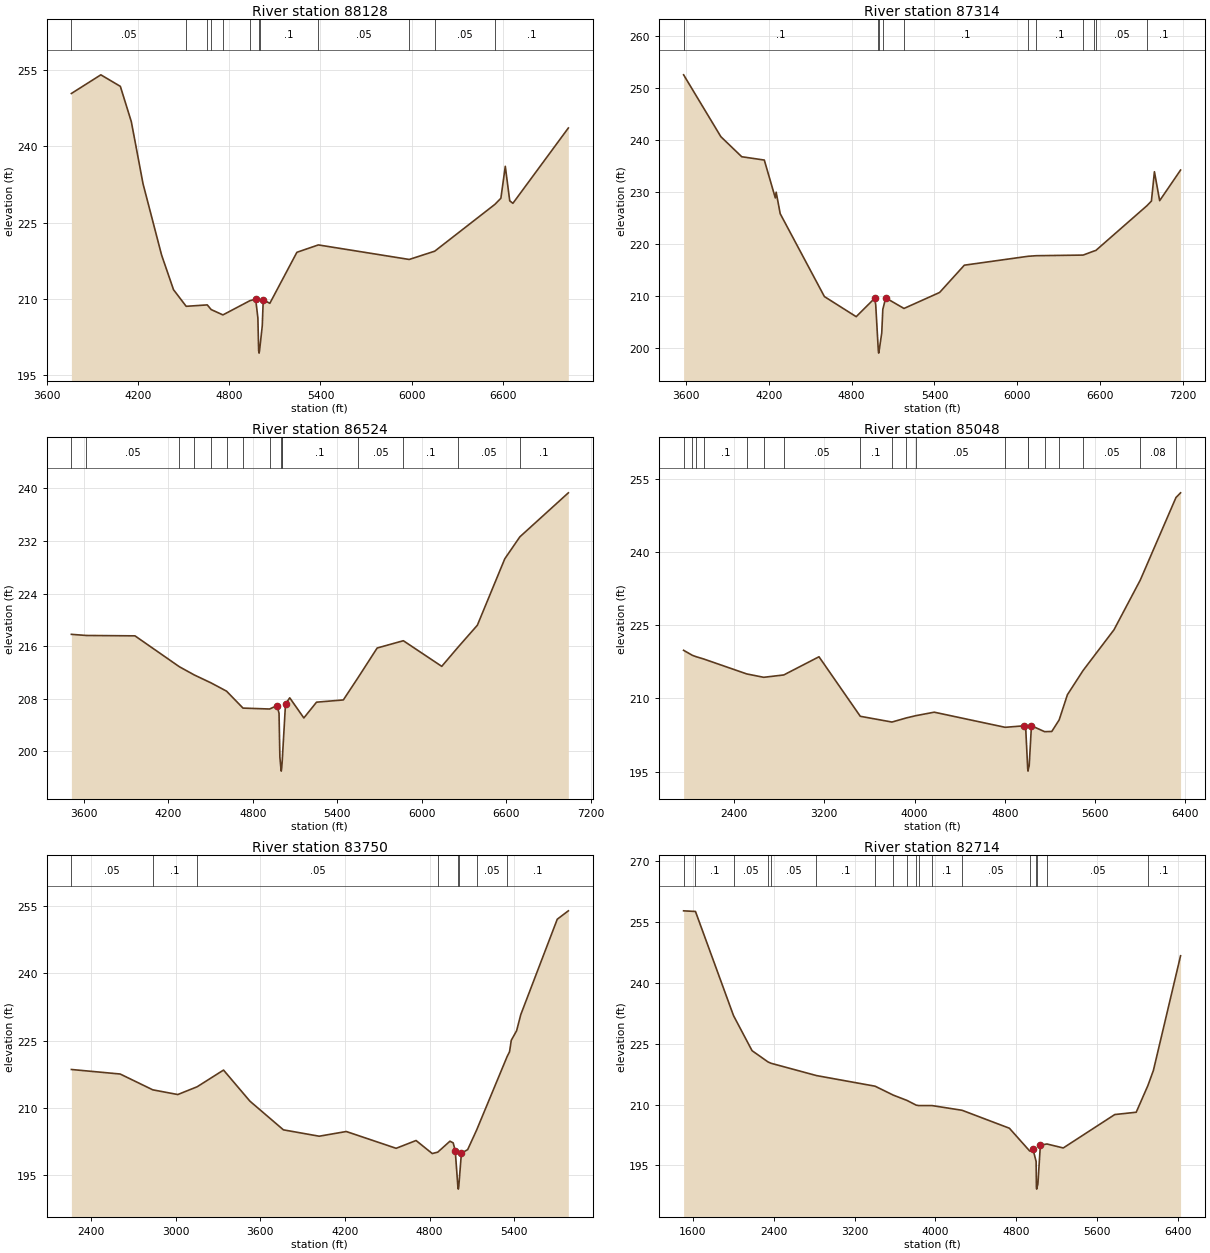
Type RM Length L Ch R = 1 ,88128   ,814,814,814
BEGIN DESCRIPTION:
RAMIRENA CREEK 93.0
END DESCRIPTION:
XS GIS Cut Line= 3
      2248758.26     13234429.97      2250216.47     13233277.38
      2251062.77     13232151.88
#Sta/Elev= 30
  3762.6  250.39  3956.3  254.06  4084.5  251.79  4156.7  244.83  4233.6  232.62
  4355.4  218.62    4434  211.78  4517.3  208.51  4655.8  208.79  4681.5  207.87
  4758.8  206.82  4936.8  209.63  4974.1   209.9  4988.6  206.22  4993.6   199.8
  4996.4   199.3  4999.6   199.8  5017.4  204.68  5023.8   209.8  5067.1   209.1
    5245  219.14  5386.1  220.59  5983.3  217.73  6151.1  219.36  6546.2  228.56
  6585.9  229.77    6615  236.06  6644.2  229.27    6665  228.78  7029.5   243.6
#Mann= 12 ,-1 , 0
  3762.6     .05       0  4517.3      .1       0  4655.8     .05       0
  4681.5      .1       0  4758.8     .05       0  4936.8      .1       0
  4993.6     .07       0  4999.6      .1       0  5386.1     .05       0
  5983.3      .1       0  6151.1     .05       0  6546.2      .1       0
Bank Sta=4974.1,5023.8
XS Rating Curve= 0 ,0
Exp/Cntr=0.3,0.1

Type RM Length L Ch R = 1 ,87314   ,790,790,790
BEGIN DESCRIPTION:
RAMIRENA CREEK 92.0
END DESCRIPTION:
XS GIS Cut Line= 3
      2248994.03     13235329.34      2249823.54     13234735.59
       2251063.1     13232474.71
#Sta/Elev= 30
  3583.6  252.52  3853.4  240.64  4004.5  236.79  4167.9  236.15  4247.7  228.88
  4253.8  229.98  4283.3  225.84  4603.2  209.93  4833.4  206.07  4967.2  209.61
  4974.7  208.36  4993.5  199.57  4996.2  199.07  4999.5  199.57  5018.3  202.93
  5026.1  207.48    5047  209.68  5179.5  207.65  5437.3  210.72  5616.4  215.96
  6077.9  217.67  6136.7  217.78  6476.3   217.9  6552.3  218.65  6568.7  218.79
    6938  227.37    6971  228.27  6992.8  233.91  7030.7  228.35  7182.1  234.23
#Mann= 11 ,-1 , 0
  3583.6      .1       0  4993.5     .07       0  4999.5      .1       0
  5026.1     .12       0  5179.5      .1       0  6077.9     .05       0
  6136.7      .1       0  6476.3     .05       0  6552.3      .1       0
  6568.7     .05       0    6938      .1       0
Bank Sta=4967.2,5047
XS Rating Curve= 0 ,0
Exp/Cntr=0.3,0.1

Type RM Length L Ch R = 1 ,86524   ,1476,1476,1476
BEGIN DESCRIPTION:
RAMIRENA CREEK 90.0
END DESCRIPTION:
XS GIS Cut Line= 4
      2250492.48     13235908.47      2250735.55     13235422.34
      2250787.63     13233642.83      2251290.45     13232550.49
#Sta/Elev= 30
  3512.9  217.81  3618.1  217.64  3964.1  217.58  4279.2  212.88  4385.1  211.63
  4504.3  210.42  4613.6  209.17  4730.7  206.59  4919.8  206.45  4972.3  206.98
  4986.3   205.8  4992.3  199.12  4999.3   197.5  5002.1     197  5005.3   197.5
  5008.6  198.43  5032.3  207.24  5062.3  208.15  5162.4  205.09  5252.4  207.49
  5442.5  207.83  5545.7  211.18  5682.6  215.73  5868.3  216.84  6140.9  212.94
  6254.8  215.81  6393.6   219.2  6588.3  229.31    6695  232.64  7039.2  239.34
#Mann= 15 ,-1 , 0
  3512.9      .1       0  3618.1     .05       0  4279.2      .1       0
  4385.1     .05       0  4504.3      .1       0  4613.6     .05       0
  4730.7      .1       0  4919.8     .12       0  4999.3     .07       0
  5005.3     .12       0  5008.6      .1       0  5545.7     .05       0
  5868.3      .1       0  6254.8     .05       0    6695      .1       0
Bank Sta=4972.3,5032.3
XS Rating Curve= 0 ,0
Exp/Cntr=0.3,0.1

Type RM Length L Ch R = 1 ,85048   ,1298,1298,1298
BEGIN DESCRIPTION:
RAMIRENA CREEK 89.0
END DESCRIPTION:
XS GIS Cut Line= 3
      2251482.57     13236848.72      2252050.15     13235748.48
      2251849.32     13232587.57
#Sta/Elev= 30
  1952.9  219.85    2031  218.82  2063.2  218.55  2132.7  218.06  2512.8  215.01
  2662.8  214.32  2840.7   214.8  3153.1  218.53  3519.1  206.33  3799.7  205.15
  3928.5     206  4010.2  206.45  4174.5  207.17  4803.3  204.07  4966.1  204.37
  4986.2  203.55  5003.2  195.59  5005.9  195.09  5009.2  195.59  5016.2  196.15
  5036.3  204.39    5153  203.18  5216.6  203.22    5282  205.59  5355.1  210.75
  5494.2  215.72  5767.7  224.05  6001.1  234.25  6317.5  251.17  6358.2  252.13
#Mann= 19 ,-1 , 0
  1952.9     .05       0    2031      .1       0  2063.2     .05       0
  2132.7      .1       0  2512.8     .05       0  2662.8      .1       0
  2840.7     .05       0  3519.1      .1       0  3799.7     .05       0
  3928.5      .1       0  4010.2     .05       0  4803.3      .1       0
  5003.2     .07       0  5009.2      .1       0    5153     .05       0
    5282      .1       0  5494.2     .05       0  6001.1     .08       0
  6317.5      .1       0
Bank Sta=4966.1,5036.3
XS Rating Curve= 0 ,0
Exp/Cntr=0.3,0.1

Type RM Length L Ch R = 1 ,83750   ,1036,1036,1036
BEGIN DESCRIPTION:
RAMIRENA CREEK 88.0
END DESCRIPTION:
XS GIS Cut Line= 4
      2251858.07     13236901.04      2252399.43     13235818.33
      2252582.79     13235145.98      2253359.79     13233731.67
#Sta/Elev= 30
  2261.6  218.55  2607.3  217.54  2838.3  214.01  3015.4  212.96    3153   214.7
  3339.6  218.42  3526.6  211.48  3763.9  205.08  4017.3  203.66  4209.2  204.71
  4562.6  200.96  4703.7   202.7  4818.4  199.79  4857.3   200.1  4943.9  202.55
  4966.7  202.17  4981.3  200.43  5000.1  192.35  5002.9  191.85  5006.1  192.35
  5024.9  199.86  5069.4  200.67    5133  205.05  5349.5  221.48    5366   222.5
  5378.3  225.07  5416.2  227.21  5445.9  230.82  5704.2  252.09  5782.7  253.96
#Mann= 8 ,-1 , 0
  2261.6     .05       0  2838.3      .1       0    3153     .05       0
  4857.3      .1       0  5000.1     .07       0  5006.1      .1       0
    5133     .05       0  5349.5      .1       0
Bank Sta=4981.3,5024.9
XS Rating Curve= 0 ,0
Exp/Cntr=0.3,0.1

Type RM Length L Ch R = 1 ,82714   ,793,793,793
BEGIN DESCRIPTION:
RAMIRENA CREEK 87.0
END DESCRIPTION:
XS GIS Cut Line= 3
      2251437.74     13238396.83      2253237.72     13235396.85
      2254237.76     13234396.82
#Sta/Elev= 30
  1510.6  257.72  1627.9  257.56  2003.9  231.92    2187  223.28  2345.6  220.49
  2376.1  220.16  2824.1  217.14  3403.9  214.52  3584.7  212.31  3718.8  211.02
  3810.3  209.85  3837.1  209.75  3966.4  209.75  4263.7  208.59  4731.2  204.17
  4931.9  198.56  4964.4  199.01  4995.5  195.97  4998.4  189.67  5001.1  189.17
  5004.4  189.67  5012.7  190.33  5037.4     200  5102.5  200.29  5263.7  199.31
  5772.8  207.54  5984.9  208.11  6100.6  214.69  6154.7   218.4  6423.4  246.65
#Mann= 18 ,-1 , 0
  1510.6     .05       0  1627.9      .1       0  2003.9     .05       0
  2345.6      .1       0  2376.1     .05       0  2824.1      .1       0
  3403.9     .05       0  3584.7      .1       0  3718.8     .05       0
  3810.3      .1       0  3837.1     .05       0  3966.4      .1       0
  4263.7     .05       0  4931.9      .1       0  4998.4     .07       0
  5004.4      .1       0  5102.5     .05       0  6100.6      .1       0
Bank Sta=4964.4,5037.4
XS Rating Curve= 0 ,0
Exp/Cntr=0.3,0.1