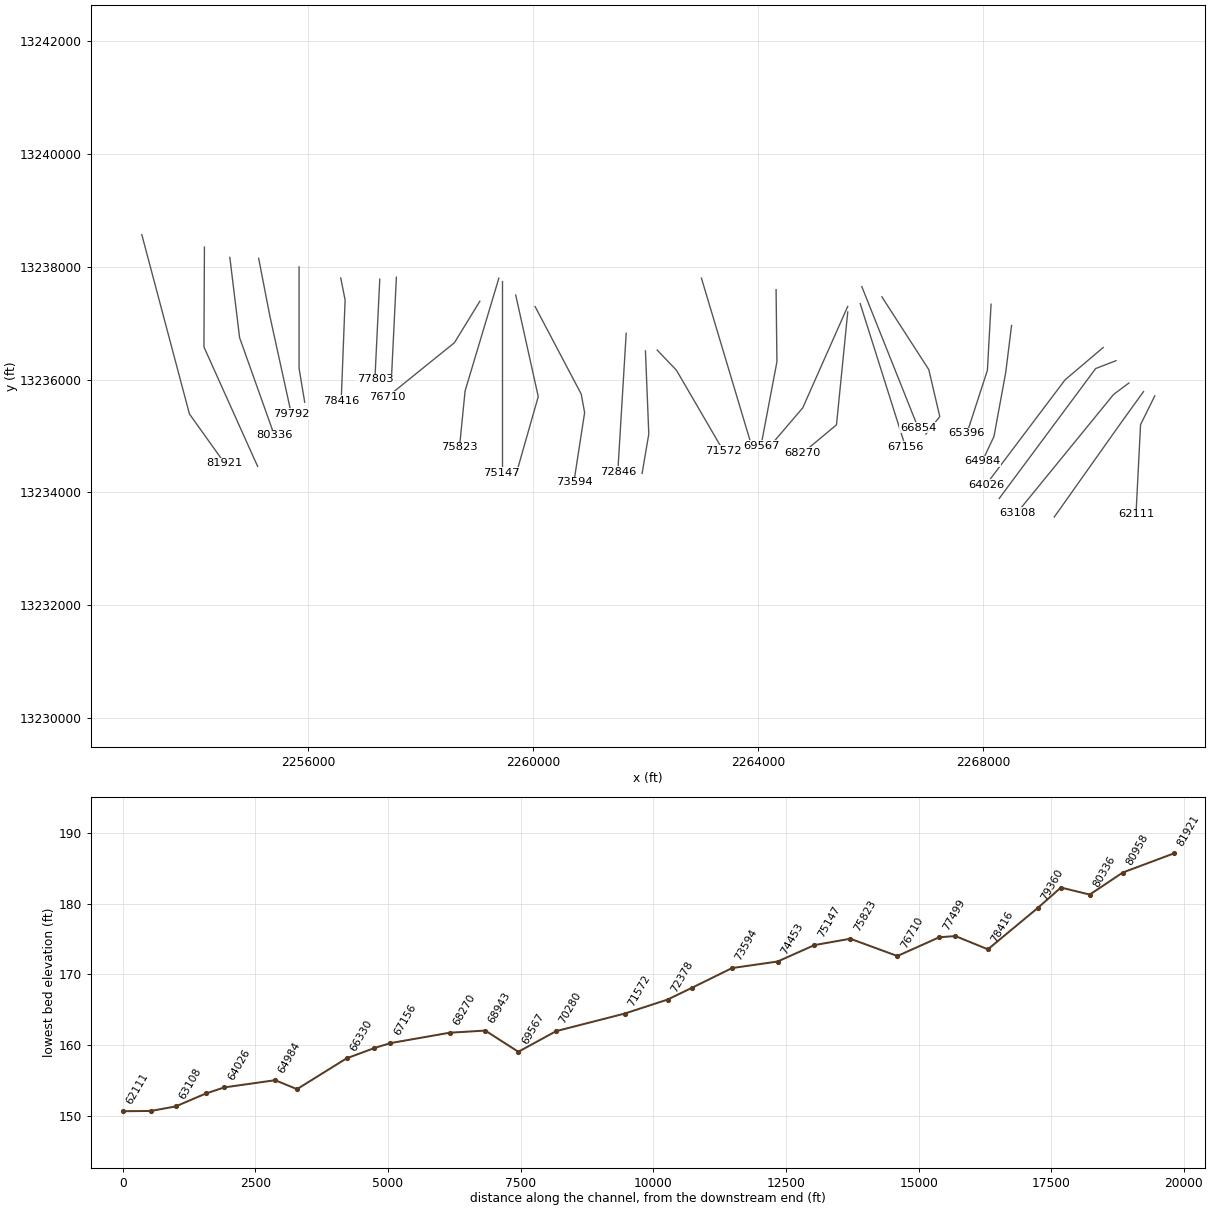
HEC-RAS study RAMIRENA CREEK.prj: RAMIRENA CREEK Base Level Engineering

--- RAMIRENA CREEK.g01 (geometry) --- (continued)

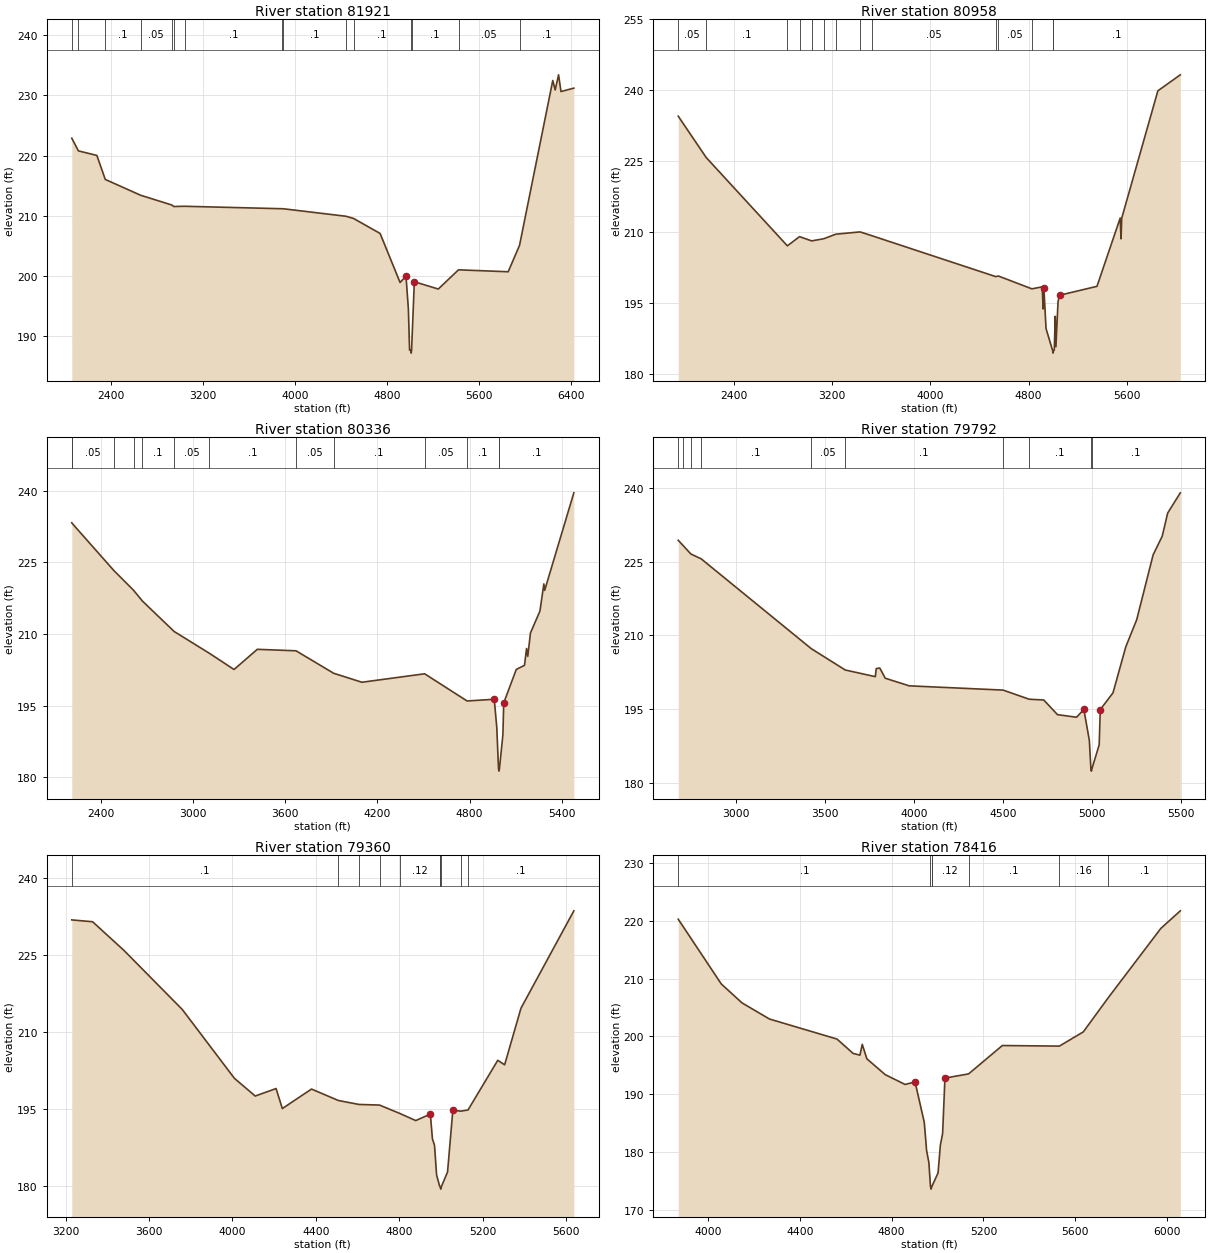
Type RM Length L Ch R = 1 ,81921   ,963,963,963
BEGIN DESCRIPTION:
Mapping XS e345499e
END DESCRIPTION:
XS GIS Cut Line= 3
      2253042.99     13238567.91      2253889.33     13235388.68
      2254517.95     13234510.79
#Sta/Elev= 30
  2055.2  222.88  2113.1  220.77  2273.6  220.02  2346.7  216.03  2654.8   213.4
  2926.1  211.78  2943.8  211.53  3036.8  211.57  3887.9  211.16  3889.7  211.17
  4442.3  209.91  4507.3  209.55    4739  207.05  4912.4  198.91  4964.2  199.95
  4984.9  194.49  4995.2  187.68  5006.6  187.67  5009.3  187.17  5012.6  187.67
  5036.6  199.03  5245.2  197.82  5421.1  201.01  5853.5  200.69  5952.3  205.08
  6241.6  232.47  6262.5  230.89    6292  233.41  6312.9  230.63  6424.9   231.2
#Mann= 15 ,-1 , 0
  2055.2      .1       0  2113.1     .05       0  2346.7      .1       0
  2654.8     .05       0  2926.1      .1       0  2943.8     .05       0
  3036.8      .1       0  3887.9     .05       0  3889.7      .1       0
  4442.3     .05       0  4507.3      .1       0  5006.6     .07       0
  5012.6      .1       0  5421.1     .05       0  5952.3      .1       0
Bank Sta=4964.2,5036.6
XS Rating Curve= 0 ,0
Exp/Cntr=0.3,0.1

Type RM Length L Ch R = 1 ,80958   ,622,622,622
BEGIN DESCRIPTION:
RAMIRENA CREEK 85.0
END DESCRIPTION:
XS GIS Cut Line= 4
      2254155.69      13238347.7      2254147.01     13236576.85
      2255015.06     13234649.77      2255101.16     13234460.36
#Sta/Elev= 30
  1944.3  234.56  2171.8  225.83    2834  207.14  2932.8  209.09  3031.6  208.19
  3130.4  208.64  3229.2  209.61  3426.9  210.09  3525.7  209.26  4533.4  200.63
  4553.2  200.77  4827.1  198.05  4910.7  198.47  4919.1   193.8  4924.6  198.29
  4942.3  189.65  4996.5  184.96  4999.3  184.46  5002.5  184.96  5009.4  185.09
  5017.2  192.24  5022.7  185.81  5040.3  195.42  5053.2   196.7  5357.6  198.58
  5546.8  213.02  5553.7  208.63  5559.2  212.98  5853.9  239.92  6036.8   243.3
#Mann= 14 ,-1 , 0
  1944.3     .05       0  2171.8      .1       0    2834     .05       0
  2932.8      .1       0  3031.6     .05       0  3130.4      .1       0
  3229.2     .05       0  3426.9      .1       0  3525.7     .05       0
  4533.4      .1       0  4553.2     .05       0  4827.1      .1       0
  4996.5     .07       0  5002.5      .1       0
Bank Sta=4924.6,5053.2
XS Rating Curve= 0 ,0
Exp/Cntr=0.3,0.1

Type RM Length L Ch R = 1 ,80336   ,544,544,544
BEGIN DESCRIPTION:
RAMIRENA CREEK 84.0
END DESCRIPTION:
XS GIS Cut Line= 3
      2254607.07     13238165.43      2254780.69     13236741.79
      2255397.01     13235014.34
#Sta/Elev= 30
  2210.9  233.31  2213.1  233.19  2486.5  223.25  2613.1  219.18  2670.3  216.94
  2876.7  210.57  3105.6  206.01  3267.2   202.6  3418.7  206.82  3670.8  206.51
  3915.7  201.81  4099.6  199.93  4507.9   201.7  4784.3  196.01  4961.1  196.37
  4977.5  190.52  4988.9  181.83  4991.6  181.33  4994.9  181.83  5017.4  188.96
  5022.7   195.6  5104.5  202.61    5158  203.47  5171.4  206.99  5179.2  205.36
  5196.9  210.25  5258.5  214.82    5284  220.51  5289.3  219.16  5479.2  239.57
#Mann= 13 ,-1 , 0
  2210.9      .1       0  2213.1     .05       0  2486.5      .1       0
  2613.1     .05       0  2670.3      .1       0  2876.7     .05       0
  3105.6      .1       0  3670.8     .05       0  3915.7      .1       0
  4507.9     .05       0  4784.3      .1       0  4988.9     .07       0
  4994.9      .1       0
Bank Sta=4961.1,5022.7
XS Rating Curve= 0 ,0
Exp/Cntr=0.3,0.1

Type RM Length L Ch R = 1 ,79792   ,432,432,432
BEGIN DESCRIPTION:
RAMIRENA CREEK 83.0
END DESCRIPTION:
XS GIS Cut Line= 3
      2255119.24     13238147.99      2255318.88     13237123.73
      2255700.83     13235387.58
#Sta/Elev= 30
  2676.1   229.4  2703.3  228.33  2747.2   226.6  2805.2  225.61  3423.6   207.3
  3614.4  202.95  3783.5  201.59  3788.6  203.23  3808.6  203.35  3839.3  201.27
  3973.9  199.72  4501.6  198.85  4648.3  196.99  4730.1  196.83  4807.4  193.84
  4914.4  193.32  4955.4   194.9  4986.1  188.61  4994.8  182.83  4997.5  182.33
  5000.8  182.83  5041.5  187.71  5047.5  194.87  5119.2   198.3  5190.9  207.67
  5252.3   213.2  5344.5  226.42  5395.7  230.23  5426.4  234.95  5497.3  239.07
#Mann= 10 ,-1 , 0
  2676.1     .05       0  2703.3      .1       0  2747.2     .05       0
  2805.2      .1       0  3423.6     .05       0  3614.4      .1       0
  4501.6     .12       0  4648.3      .1       0  4994.8     .07       0
  5000.8      .1       0
Bank Sta=4955.4,5047.5
XS Rating Curve= 0 ,0
Exp/Cntr=0.3,0.1

Type RM Length L Ch R = 1 ,79360   ,944,944,944
BEGIN DESCRIPTION:
RAMIRENA CREEK 82.0
END DESCRIPTION:
XS GIS Cut Line= 3
      2255837.72     13237996.87      2255837.72     13236196.85
      2255937.72     13235596.85
#Sta/Elev= 30
  3229.1  231.92  3329.1  231.56  3479.1  225.99  3759.1  214.47  4009.1  201.06
  4109.1   197.6  4209.1  199.06  4239.1  195.16  4379.1  198.96  4507.8  196.73
  4606.6  195.96  4705.3  195.84  4804.1  194.18  4879.1  192.82  4949.1  194.08
  4959.1  189.26  4969.1  187.99  4979.1  182.22  4993.3  180.09  4996.1  179.96
  4998.9  179.46  5002.1  179.96  5031.6   182.8    5057  194.86  5094.8  194.65
  5129.8  194.88  5272.4  204.56  5305.4  203.69  5383.9  214.72  5637.4  233.69
#Mann= 10 ,-1 , 0
  3229.1      .1       0  4507.8     .16       0  4606.6      .1       0
  4705.3     .16       0  4804.1     .12       0  4993.3      .1       0
  4996.1     .07       0  5002.1      .1       0  5094.8     .12       0
  5129.8      .1       0
Bank Sta=4949.1,5057
XS Rating Curve= 0 ,0
Exp/Cntr=0.3,0.1

Type RM Length L Ch R = 1 ,78416   ,613,613,613
BEGIN DESCRIPTION:
RAMIRENA CREEK 81.0
END DESCRIPTION:
XS GIS Cut Line= 3
      2256577.57     13237800.76      2256655.69     13237410.19
      2256586.24     13235621.95
#Sta/Elev= 30
  3870.1   220.3  4057.7  209.09  4147.8  205.82  4267.6  203.02    4562  199.55
    4632  197.07    4662  196.76    4672  198.64  4692.1  196.13  4772.1  193.39
  4858.7  191.69  4902.2  192.12  4942.3  185.13  4952.3  180.29  4962.3  178.18
  4969.3  174.07    4972  173.57  4975.3  174.07  4976.2   174.1  5002.3  176.37
  5012.3  181.15  5022.3  183.22  5032.3  192.79  5135.4  193.52  5282.5  198.43
  5531.1  198.33  5635.5   200.8  5744.6  206.74    5973   218.7    6058  221.75
#Mann= 7 ,-1 , 0
  3870.1      .1       0  4969.3     .07       0  4975.3      .1       0
  4976.2     .12       0  5135.4      .1       0  5531.1     .16       0
  5744.6      .1       0
Bank Sta=4902.2,5032.3
XS Rating Curve= 0 ,0
Exp/Cntr=0.3,0.1

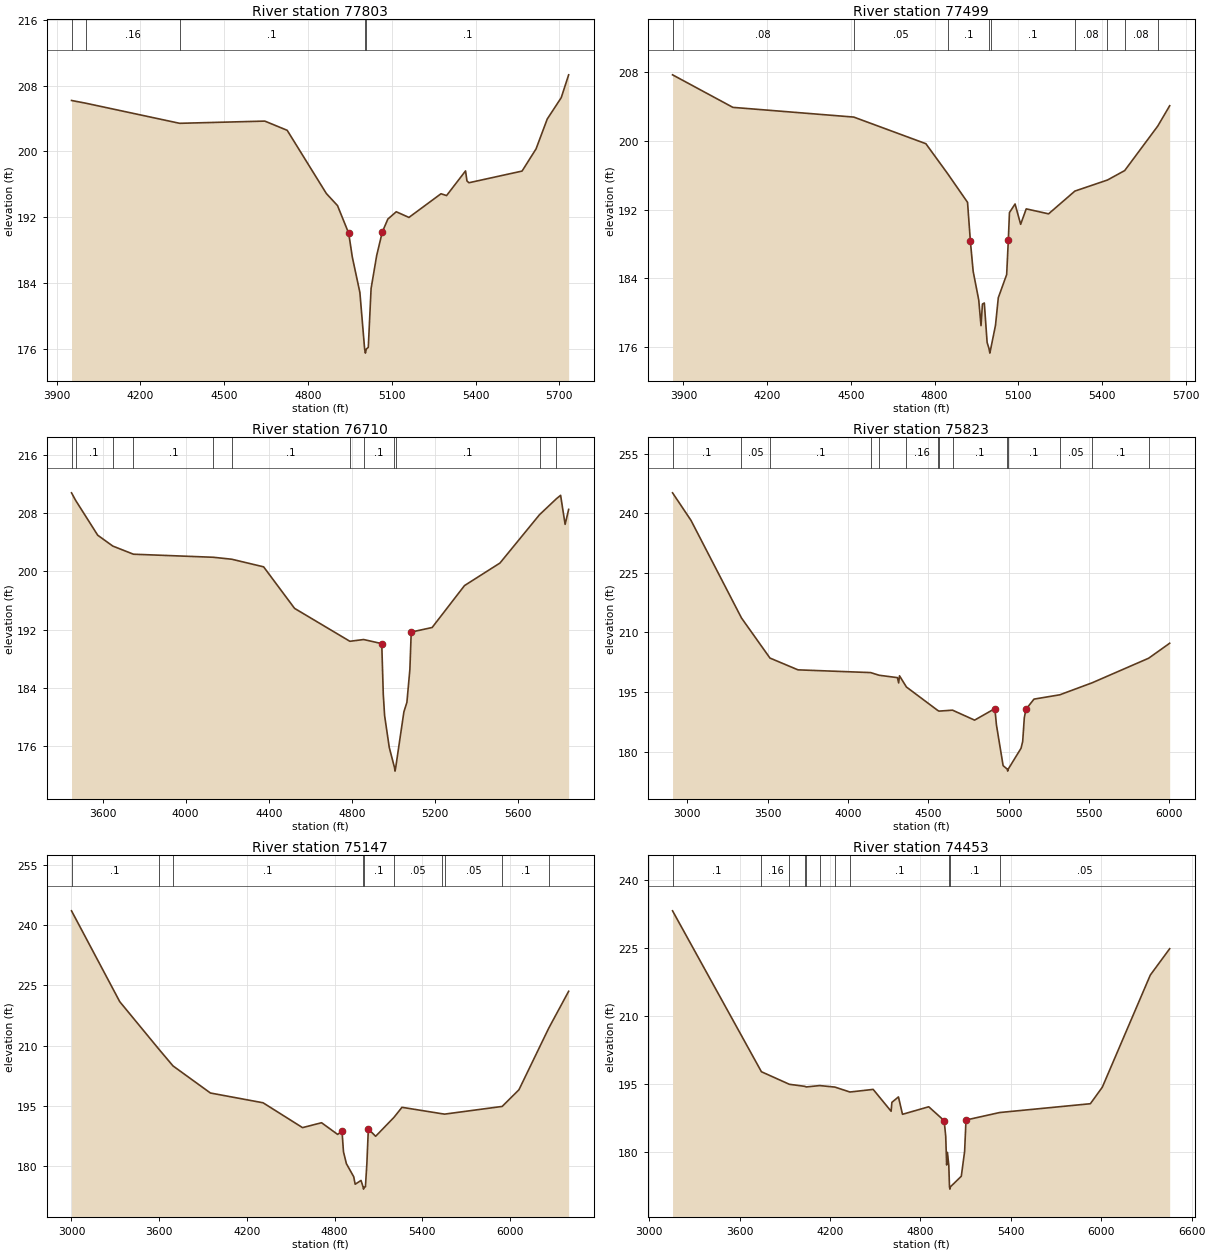
Type RM Length L Ch R = 1 ,77803   ,304,304,304
BEGIN DESCRIPTION:
RAMIRENA CREEK 80.0
END DESCRIPTION:
XS GIS Cut Line= 2
       2257271.6     13237778.15      2257184.87     13236000.26
#Sta/Elev= 30
  3953.5  206.19  4004.2  205.86  4340.7  203.41  4645.6  203.68  4725.7  202.56
  4865.9  194.87  4905.9   193.4    4946  190.03  4958.9  187.13    4986  182.83
    5003  175.95  5005.8  175.45    5009  175.95  5016.1  176.15  5026.1  183.31
  5046.1  187.32  5066.1  190.17  5086.1  191.76  5116.2  192.65  5161.6  191.96
  5276.4  194.84  5296.4  194.62  5364.3  197.62  5369.4   196.4  5376.5  196.18
  5566.7   197.6  5616.8   200.3  5656.8  203.93  5706.9  206.53  5733.5  209.31
#Mann= 5 ,-1 , 0
  3953.5      .1       0  4004.2     .16       0  4340.7      .1       0
    5003     .07       0    5009      .1       0
Bank Sta=4946,5066.1
XS Rating Curve= 0 ,0
Exp/Cntr=0.3,0.1

Type RM Length L Ch R = 1 ,77499   ,789,789,789
BEGIN DESCRIPTION:
RAMIRENA CREEK 79.0
END DESCRIPTION:
XS GIS Cut Line= 2
      2257566.74     13237812.85      2257479.93     13236033.36
#Sta/Elev= 30
  3861.1  207.69  4077.4   203.9  4510.5  202.77  4768.9  199.67    4847  196.18
  4918.3  192.84  4928.4  188.32  4938.4  184.81  4958.4  181.47  4966.6  178.48
  4971.6  180.99  4978.4  181.12  4988.4  176.53  4995.4  175.78  4998.2  175.28
  5001.4  175.78  5018.5  178.53  5028.5  181.73  5058.5  184.43 5064.45  188.46
  5068.5  191.65  5088.6  192.65  5108.6  190.28  5128.6  192.08  5208.7   191.5
  5302.9  194.15  5419.7  195.44  5481.5  196.54  5600.1  201.73  5642.7  204.09
#Mann= 9 ,-1 , 0
  3861.1     .08       0  4510.5     .05       0    4847      .1       0
  4995.4     .07       0  5001.4      .1       0  5302.9     .08       0
  5419.7     .05       0  5481.5     .08       0  5600.1     .05       0
Bank Sta=4928.4,5064.45
XS Rating Curve= 0 ,0
Exp/Cntr=0.3,0.1

Type RM Length L Ch R = 1 ,76710   ,887,887,887
BEGIN DESCRIPTION:
RAMIRENA CREEK 78.0
END DESCRIPTION:
XS GIS Cut Line= 3
      2259049.86     13237387.49      2258598.61      13236652.9
      2257407.56     13235692.72
#Sta/Elev= 30
  3450.8  210.75  3470.3  209.73  3576.9  204.94  3649.7  203.45  3748.8  202.34
  4133.5  201.92    4222  201.65  4375.1  200.61  4523.9  194.92  4790.1  190.41
  4856.3  190.65  4943.5  190.09  4950.9  183.12  4957.3  180.21  4979.7  175.86
  5004.7  173.12  5007.4  172.62  5010.7  173.12  5050.1  180.75  5064.5  182.04
  5078.9  186.58  5085.3  191.67    5186   192.3  5341.6  198.04  5512.3  201.13
  5702.8  207.76  5784.3  209.95  5804.1  210.41  5825.8  206.43  5842.8  208.48
#Mann= 12 ,-1 , 0
  3450.8     .05       0  3470.3      .1       0  3649.7     .16       0
  3748.8      .1       0  4133.5     .16       0    4222      .1       0
  4790.1     .16       0  4856.3      .1       0  5004.7     .07       0
  5010.7      .1       0  5702.8     .05       0  5784.3      .1       0
Bank Sta=4943.5,5085.3
XS Rating Curve= 0 ,0
Exp/Cntr=0.3,0.1

Type RM Length L Ch R = 1 ,75823   ,676,676,676
BEGIN DESCRIPTION:
RAMIRENA CREEK 77.0
END DESCRIPTION:
XS GIS Cut Line= 3
      2259387.71     13237796.84      2258787.72     13235796.85
      2258687.72     13234796.88
#Sta/Elev= 30
  2908.9  245.14  3023.7   238.2  3337.8  213.63  3514.9  203.54  3689.3  200.57
  4141.4  199.88  4194.2  199.21  4307.9  198.61  4315.7  197.27  4320.9  199.07
    4364  196.25  4558.3  190.37  4566.8  190.18  4650.8  190.42  4788.1  187.91
  4914.3  190.81  4923.9  186.74  4965.6  176.45  4991.3  175.57  4994.1  175.07
  4997.3  175.57  5077.3  180.84  5087.4  182.56  5097.4  188.48  5107.5  190.63
  5157.7   193.2  5318.5  194.29  5519.5  197.31  5871.2   203.5  6001.9  207.27
#Mann= 14 ,-1 , 0
  2908.9      .1       0  3337.8     .05       0  3514.9      .1       0
  4141.4     .16       0  4194.2      .1       0    4364     .16       0
  4558.3      .1       0  4566.8     .16       0  4650.8      .1       0
  4991.3     .07       0  4997.3      .1       0  5318.5     .05       0
  5519.5      .1       0  5871.2     .05       0
Bank Sta=4914.3,5107.5
XS Rating Curve= 0 ,0
Exp/Cntr=0.3,0.1

Type RM Length L Ch R = 1 ,75147   ,694,694,694
BEGIN DESCRIPTION:
RAMIRENA CREEK 76.0
END DESCRIPTION:
XS GIS Cut Line= 3
      2259437.72     13237746.89      2259437.72     13235746.85
      2259437.72     13234346.89
#Sta/Elev= 30
  3000.3  243.63  3330.3  220.95  3598.2  209.08  3694.4  204.92  3950.3  198.16
  4310.3  195.72  4580.3  189.52  4710.3  190.74  4820.3  187.83  4850.3  188.62
  4860.3  183.48  4880.3  180.52  4930.3  177.26  4940.3  175.39  4980.3  176.34
  4994.8  174.67  4997.6  174.17  5000.8  174.67  5010.3  174.74  5020.3  180.55
  5030.3  189.17  5080.3  187.36  5206.5  192.12  5260.3  194.59  5531.3     193
  5551.8  192.89  5945.6  194.81  6060.3  198.97  6264.1  214.34  6400.3  223.55
#Mann= 10 ,-1 , 0
  3000.3      .1       0  3598.2     .05       0  3694.4      .1       0
  4994.8     .07       0  5000.8      .1       0  5206.5     .05       0
  5531.3      .1       0  5551.8     .05       0  5945.6      .1       0
  6264.1     .05       0
Bank Sta=4850.3,5030.3
XS Rating Curve= 0 ,0
Exp/Cntr=0.3,0.1

Type RM Length L Ch R = 1 ,74453   ,859,859,859
BEGIN DESCRIPTION:
RAMIRENA CREEK 75.0
END DESCRIPTION:
XS GIS Cut Line= 3
      2259687.72     13237496.85      2260087.72     13235696.85
      2259687.73     13234296.88
#Sta/Elev= 30
  3154.2  233.17  3744.1  197.71  3929.8  194.94  4030.3   194.5  4042.7  194.36
  4130.8  194.66  4231.4  194.33  4331.9  193.24  4485.9  193.82    4605     189
  4610.1  190.96  4653.7  192.16  4680.5  188.33  4854.7  189.99  4957.1  186.93
  4967.4  183.52  4973.8  177.16  4978.9  179.93  4987.9  177.07  4992.5  172.34
  4995.3  171.84  4998.5  172.34  5070.9  174.68    5093  180.18  5102.1  187.07
  5325.3  188.72  5927.6  190.66  6006.9   194.3  6325.4  219.01  6454.1  224.82
#Mann= 11 ,-1 , 0
  3154.2      .1       0  3744.1     .16       0  3929.8     .05       0
  4030.3      .1       0  4042.7     .05       0  4130.8      .1       0
  4231.4     .16       0  4331.9      .1       0  4992.5     .07       0
  4998.5      .1       0  5325.3     .05       0
Bank Sta=4957.1,5102.1
XS Rating Curve= 0 ,0
Exp/Cntr=0.3,0.1

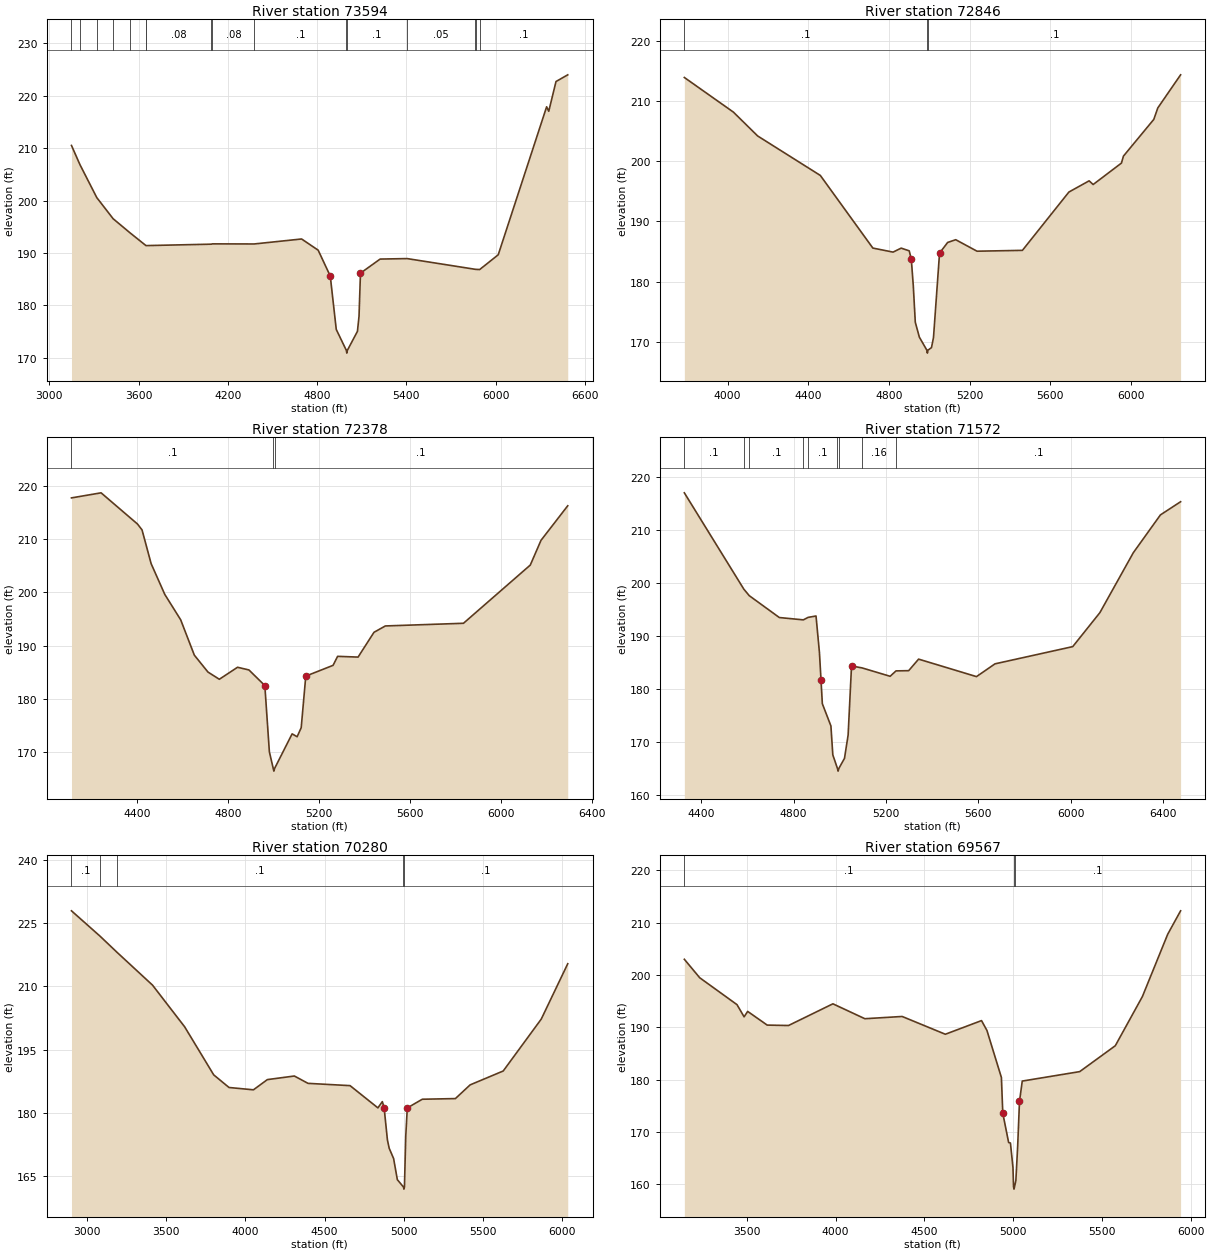
Type RM Length L Ch R = 1 ,73594   ,748,748,748
BEGIN DESCRIPTION:
RAMIRENA CREEK 74.0
END DESCRIPTION:
XS GIS Cut Line= 4
      2260031.93     13237293.05      2260851.15     13235742.36
      2260911.92      13235412.5      2260721.11     13234180.89
#Sta/Elev= 30
    3149  210.52  3206.1  206.85  3319.2  200.57  3428.8  196.55  3539.2  193.93
  3649.2  191.43    3653  191.42  4089.1  191.69  4096.7  191.75  4376.9  191.73
  4695.9  192.68  4807.2  190.54  4888.4  185.61  4928.7  175.43  4996.9  171.41
  4999.7  170.91  5002.9  171.41  5071.1  175.07  5081.7  177.95  5091.4  186.16
  5223.6  188.85  5405.3  188.94  5862.3   186.9  5866.2  186.89  5892.6  186.85
  6017.4  189.67  6342.6  217.89    6357  217.04  6405.6  222.71  6484.5  223.99
#Mann= 16 ,-1 , 0
    3149      .1       0  3206.1     .08       0  3319.2      .1       0
  3428.8     .08       0  3539.2     .05       0  3649.2      .1       0
    3653     .08       0  4089.1      .1       0  4096.7     .08       0
  4376.9      .1       0  4996.9     .07       0  5002.9      .1       0
  5405.3     .05       0  5862.3      .1       0  5866.2     .05       0
  5892.6      .1       0
Bank Sta=4888.4,5091.4
XS Rating Curve= 0 ,0
Exp/Cntr=0.3,0.1

Type RM Length L Ch R = 1 ,72846   ,468,468,468
BEGIN DESCRIPTION:
RAMIRENA CREEK 73.0
END DESCRIPTION:
XS GIS Cut Line= 2
       2261650.5     13236819.59      2261501.68     13234364.19
#Sta/Elev= 30
  3785.7   213.9  4028.9  208.15  4149.1  204.19  4459.7  197.64  4720.1  185.58
  4820.3  184.91  4860.4  185.57  4900.5  185.12  4910.8   183.7  4920.5  179.37
  4930.5  173.27  4950.6   170.8  4987.6  168.64  4990.4  168.14  4993.6  168.64
  5010.7  169.05  5020.7  170.73  5050.7  184.74  5090.8  186.51  5130.9  186.97
  5236.4  185.06  5461.5   185.2  5691.9  194.88  5792.1  196.74  5812.1  196.13
  5952.4  199.69  5962.4  200.85  6112.7  206.94  6132.7  208.85  6245.6  214.34
#Mann= 3 ,-1 , 0
  3785.7      .1       0  4987.6     .07       0  4993.6      .1       0
Bank Sta=4910.8,5050.7
XS Rating Curve= 0 ,0
Exp/Cntr=0.3,0.1

Type RM Length L Ch R = 1 ,72378   ,806,806,806
BEGIN DESCRIPTION:
RAMIRENA CREEK 72.0
END DESCRIPTION:
XS GIS Cut Line= 3
      2261992.75     13236507.07      2262052.28     13235033.83
      2261933.23     13234334.43
#Sta/Elev= 30
  4111.1  217.69  4241.4  218.64  4401.6  212.79  4421.6  211.69  4461.6  205.36
  4521.7  199.59  4591.7  194.82  4651.8  188.19  4711.8  185.02  4761.8  183.67
  4841.9  185.92    4892  185.42    4962  182.49    4982  170.06    4999  166.94
  5001.8  166.44    5005  166.94  5082.1  173.43  5104.1  172.89  5122.1  174.59
  5142.2  184.26  5262.3  186.28  5282.3  187.97  5372.3  187.83  5442.4  192.48
  5492.4  193.67  5836.1  194.17  6130.2  205.09  6177.4  209.73    6295  216.21
#Mann= 3 ,-1 , 0
  4111.1      .1       0    4999     .07       0    5005      .1       0
Bank Sta=4962,5142.2
XS Rating Curve= 0 ,0
Exp/Cntr=0.3,0.1

Type RM Length L Ch R = 1 ,71572   ,1292,1292,1292
BEGIN DESCRIPTION:
RAMIRENA CREEK 71.0
END DESCRIPTION:
XS GIS Cut Line= 3
       2262201.1     13236521.92      2262543.35     13236164.78
      2263376.68     13234736.22
#Sta/Elev= 30
    4327  216.99  4584.7   198.8    4608  197.58  4738.3  193.45  4842.2  193.01
  4862.8  193.48  4897.1  193.74  4911.9  186.85  4918.6  181.74  4924.4  177.19
  4961.6  172.99  4969.8  167.53  4989.9  164.96  4992.7  164.46  4995.9  164.96
  5020.4  166.88  5036.1  171.29  5050.8  184.31  5095.9  183.95    5218  182.36
  5243.5  183.38  5298.2  183.42  5341.2   185.6  5591.8   182.3    5672  184.71
  6008.5  187.96    6126  194.37  6270.7  205.68  6388.1  212.82  6475.5  215.31
#Mann= 9 ,-1 , 0
    4327      .1       0  4584.7     .16       0    4608      .1       0
  4842.2     .16       0  4862.8      .1       0  4989.9     .07       0
  4995.9      .1       0  5095.9     .16       0  5243.5      .1       0
Bank Sta=4918.6,5050.8
XS Rating Curve= 0 ,0
Exp/Cntr=0.3,0.1

Type RM Length L Ch R = 1 ,70280   ,713,713,713
BEGIN DESCRIPTION:
RAMIRENA CREEK 70.0
END DESCRIPTION:
XS GIS Cut Line= 3
      2262987.73     13237796.83      2263587.72     13235796.85
      2263887.73     13234796.82
#Sta/Elev= 30
  2902.9  227.91  3081.9  221.95  3187.3  218.19  3414.5   210.3  3617.2  200.43
  3800.7  189.04  3897.3  186.05  4051.3   185.5  4139.2  187.92  4309.7  188.77
  4395.8  187.03  4661.2  186.49  4836.9  181.22  4864.8   182.7  4876.1  181.28
    4897  173.61  4908.3  171.64  4936.1   169.2  4959.6  164.21  4998.4  162.47
  5001.1  161.97  5004.4  162.47  5012.7  174.51  5022.3  181.21  5117.1  183.27
  5325.9  183.42    5419  186.67  5627.8  189.96  5867.9  202.26    6035  215.37
#Mann= 5 ,-1 , 0
  2902.9      .1       0  3081.9     .05       0  3187.3      .1       0
  4998.4     .07       0  5004.4      .1       0
Bank Sta=4876.1,5022.3
XS Rating Curve= 0 ,0
Exp/Cntr=0.3,0.1

Type RM Length L Ch R = 1 ,69567   ,624,624,624
BEGIN DESCRIPTION:
RAMIRENA CREEK 69.0
END DESCRIPTION:
XS GIS Cut Line= 3
      2264314.18     13237593.39      2264329.07     13236313.59
      2264046.33      13234825.5
#Sta/Elev= 30
    3148  203.01  3234.5  199.48  3444.6  194.33  3484.6     192  3504.6  193.04
  3614.6  190.42  3734.6  190.34  3984.6  194.49  4164.6  191.64  4374.6  192.07
  4617.7  188.67  4821.5  191.28  4852.1  189.39  4933.5  180.39  4941.3  173.56
  4974.2  167.96  4984.4  167.86  4998.6  163.16  5001.8  159.54  5004.5  159.04
  5007.8  159.54  5014.9  160.68  5025.1  167.22  5035.3  175.81  5050.9  179.71
  5374.5  181.52  5574.8  186.47  5727.5  195.88    5870   207.8  5942.6  212.28
#Mann= 3 ,-1 , 0
    3148      .1       0  5001.8     .07       0  5007.8      .1       0
Bank Sta=4941.3,5035.3
XS Rating Curve= 0 ,0
Exp/Cntr=0.3,0.1

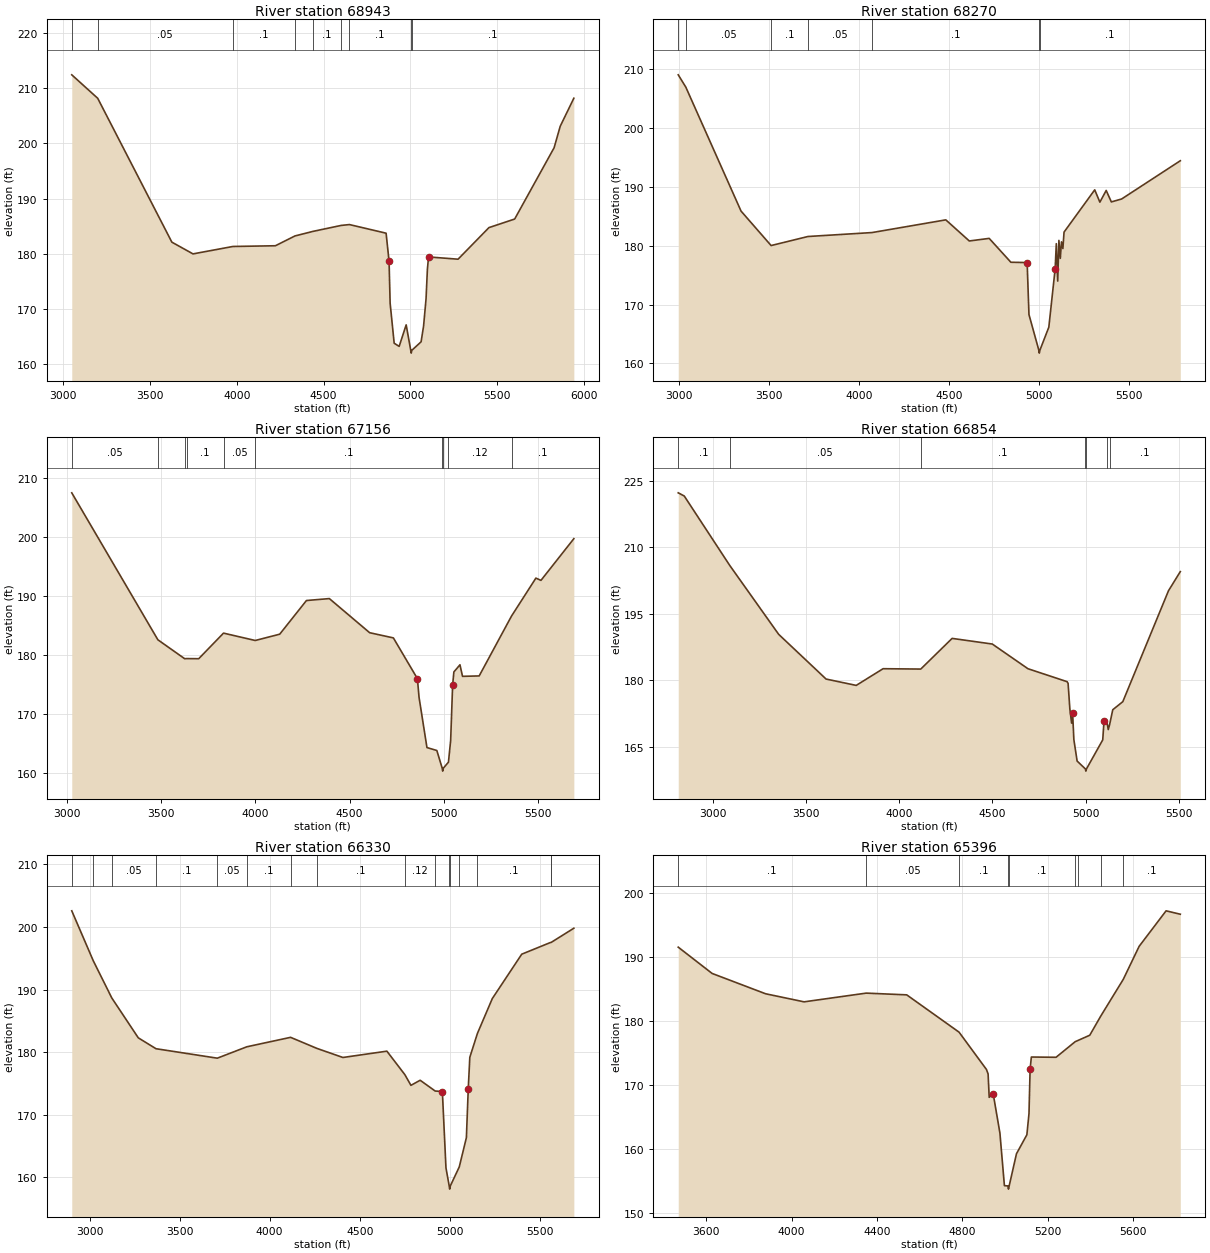
Type RM Length L Ch R = 1 ,68943   ,673,673,673
BEGIN DESCRIPTION:
RAMIRENA CREEK 68.0
END DESCRIPTION:
XS GIS Cut Line= 3
      2265587.71     13237296.83      2264787.72     13235496.85
      2264187.72     13234796.86
#Sta/Elev= 30
  3049.2  212.36  3198.6  208.12  3625.7  182.11  3747.5  179.99  3977.3  181.33
  4222.1  181.46  4334.4  183.23  4438.7  184.06  4601.6  185.14  4648.4  185.29
  4859.6  183.73  4876.7  178.65  4882.8  171.08  4906.1  163.84  4934.8  163.27
  4975.2  167.16  5001.6  162.55  5004.3  162.05  5007.6  162.55  5061.2   164.1
  5075.5  166.95  5089.7  171.89  5097.4  177.18    5104  179.44  5274.1  179.03
  5451.9  184.74  5600.1  186.29  5827.3  199.18  5862.4  203.06  5940.9  208.13
#Mann= 9 ,-1 , 0
  3049.2      .1       0  3198.6     .05       0  3977.3      .1       0
  4334.4     .16       0  4438.7      .1       0  4601.6     .16       0
  4648.4      .1       0  5001.6     .07       0  5007.6      .1       0
Bank Sta=4876.7,5104
XS Rating Curve= 0 ,0
Exp/Cntr=0.3,0.1

Type RM Length L Ch R = 1 ,68270   ,1114,1114,1114
BEGIN DESCRIPTION:
RAMIRENA CREEK 67.0
END DESCRIPTION:
XS GIS Cut Line= 3
      2265587.72     13237196.85      2265387.72     13235196.85
      2264787.71     13234696.85
#Sta/Elev= 30
  2994.7  209.06  3036.8  206.97  3343.9  185.89    3511  180.03  3715.7  181.57
  4072.2  182.24  4482.1   184.4  4612.7  180.81  4723.3  181.25  4843.9  177.19
  4934.3  177.14  4944.4   168.3  4999.2  162.24  5001.9  161.74  5005.2  162.24
  5054.8  166.15  5089.9  176.05  5096.4  180.35  5104.2  173.99  5110.8  180.91
  5118.6  177.85  5125.1  180.66  5132.9  179.52  5139.4  182.32  5309.9   189.5
  5338.6  187.41  5373.7   189.4  5402.3  187.45  5459.6  187.95  5785.7  194.45
#Mann= 7 ,-1 , 0
  2994.7      .1       0  3036.8     .05       0    3511      .1       0
  3715.7     .05       0  4072.2      .1       0  4999.2     .07       0
  5005.2      .1       0
Bank Sta=4934.3,5089.9
XS Rating Curve= 0 ,0
Exp/Cntr=0.3,0.1

Type RM Length L Ch R = 1 ,67156   ,302,302,302
BEGIN DESCRIPTION:
RAMIRENA CREEK 66.0
END DESCRIPTION:
XS GIS Cut Line= 2
      2265809.23     13237344.95      2266614.79     13234803.26
#Sta/Elev= 30
  3024.4  207.48  3481.7  182.55    3624  179.34  3635.2  179.36  3698.5  179.34
  3830.3  183.68  3998.7  182.43  4128.7   183.5  4270.7  189.21  4392.2  189.54
  4606.4  183.75  4732.3  182.87  4859.9  175.96  4868.7  172.78  4910.6  164.27
  4963.1  163.77  4991.6  160.77  4994.3  160.27  4997.6  160.77  5024.8  161.79
  5036.5  165.48    5047  174.89  5053.6  177.09  5085.9  178.31  5099.5  176.35
    5188  176.42  5359.7  186.57  5489.1  193.01  5516.1  192.63  5690.7   199.7
#Mann= 10 ,-1 , 0
  3024.4     .05       0  3481.7      .1       0    3624     .05       0
  3635.2      .1       0  3830.3     .05       0  3998.7      .1       0
  4991.6     .07       0  4997.6      .1       0  5024.8     .12       0
  5359.7      .1       0
Bank Sta=4859.9,5047
XS Rating Curve= 0 ,0
Exp/Cntr=0.3,0.1

Type RM Length L Ch R = 1 ,66854   ,524,524,524
BEGIN DESCRIPTION:
RAMIRENA CREEK 65.0
END DESCRIPTION:
XS GIS Cut Line= 3
      2265837.73     13237646.84      2266637.72     13235646.85
      2266837.73     13235146.82
#Sta/Elev= 30
  2814.9  222.26  2847.2  221.54  3090.9  205.92  3353.4  190.39  3607.8  180.31
  3769.4  178.88  3913.5  182.64  4115.6  182.56  4283.7  189.47  4499.1   188.2
  4690.3  182.64  4900.3  179.72  4905.7  179.34  4915.1  173.59  4924.5  170.38
  4929.9  172.74  4936.6  166.69  4954.1  161.84  4998.3  160.07    5001  159.57
  5004.3  160.07  5091.5  166.61  5098.2  170.79  5112.3  171.11  5121.1  168.93
  5128.1     170  5145.3   173.4  5199.2  175.22  5444.2  200.21  5507.5  204.51
#Mann= 7 ,-1 , 0
  2814.9      .1       0  3090.9     .05       0  4115.6      .1       0
  4998.3     .07       0  5004.3      .1       0  5112.3     .12       0
  5128.1      .1       0
Bank Sta=4929.9,5098.2
XS Rating Curve= 0 ,0
Exp/Cntr=0.3,0.1

Type RM Length L Ch R = 1 ,66330   ,934,934,934
BEGIN DESCRIPTION:
RAMIRENA CREEK 64.0
END DESCRIPTION:
XS GIS Cut Line= 4
      2266194.33     13237465.52      2267027.69     13236176.42
        2267223.     13235343.09       2266976.1     13235031.22
#Sta/Elev= 30
  2900.8  202.59  3020.4   194.6  3123.2  188.66  3270.3  182.29  3368.7  180.55
  3709.1  179.04  3873.3  180.86  4116.2  182.37  4262.6   180.6  4406.9  179.15
  4651.1  180.16  4750.8  176.41  4784.6   174.7  4835.9  175.51  4919.3  173.79
  4959.2  173.71  4979.2  161.51  4997.3  158.61    5000  158.11  5003.3  158.61
  5053.1  161.66  5092.7  166.34    5103  174.14  5111.7  179.18  5153.9  182.99
  5236.5  188.56  5400.1  195.66  5559.9  197.53  5563.5  197.54  5689.5  199.81
#Mann= 16 ,-1 , 0
  2900.8     .05       0  3020.4      .1       0  3123.2     .05       0
  3368.7      .1       0  3709.1     .05       0  3873.3      .1       0
  4116.2     .16       0  4262.6      .1       0  4750.8     .12       0
  4919.3      .1       0  4997.3     .07       0  5003.3      .1       0
  5053.1     .12       0  5153.9      .1       0  5559.9     .16       0
  5563.5      .1       0
Bank Sta=4959.2,5103
XS Rating Curve= 0 ,0
Exp/Cntr=0.3,0.1

Type RM Length L Ch R = 1 ,65396   ,412,412,412
BEGIN DESCRIPTION:
RAMIRENA CREEK 63.0
END DESCRIPTION:
XS GIS Cut Line= 3
      2268134.46     13237335.31      2268069.35      13236163.4
      2267704.76     13235043.57
#Sta/Elev= 30
  3469.4  191.49  3628.1  187.39  3878.5  184.22  4058.8  182.96  4349.7  184.32
  4539.5  184.05  4784.6  178.23  4912.9  172.41  4920.6  171.71  4925.8  168.06
  4944.5  168.61    4976  162.48    4997  154.28  5013.3  154.24  5016.1  153.74
  5019.3  154.24  5053.5  159.26  5102.2  162.22  5112.1  165.51  5117.4  172.49
  5123.2  174.35  5238.9  174.31  5328.3  176.74  5343.9  176.97  5396.7  177.75
  5448.8  180.77  5553.7  186.47    5628  191.62  5754.2  197.16  5820.8  196.63
#Mann= 9 ,-1 , 0
  3469.4      .1       0  4349.7     .05       0  4784.6      .1       0
  5013.3     .07       0  5019.3      .1       0  5328.3     .12       0
  5343.9      .1       0  5448.8     .16       0  5553.7      .1       0
Bank Sta=4944.5,5117.4
XS Rating Curve= 0 ,0
Exp/Cntr=0.3,0.1

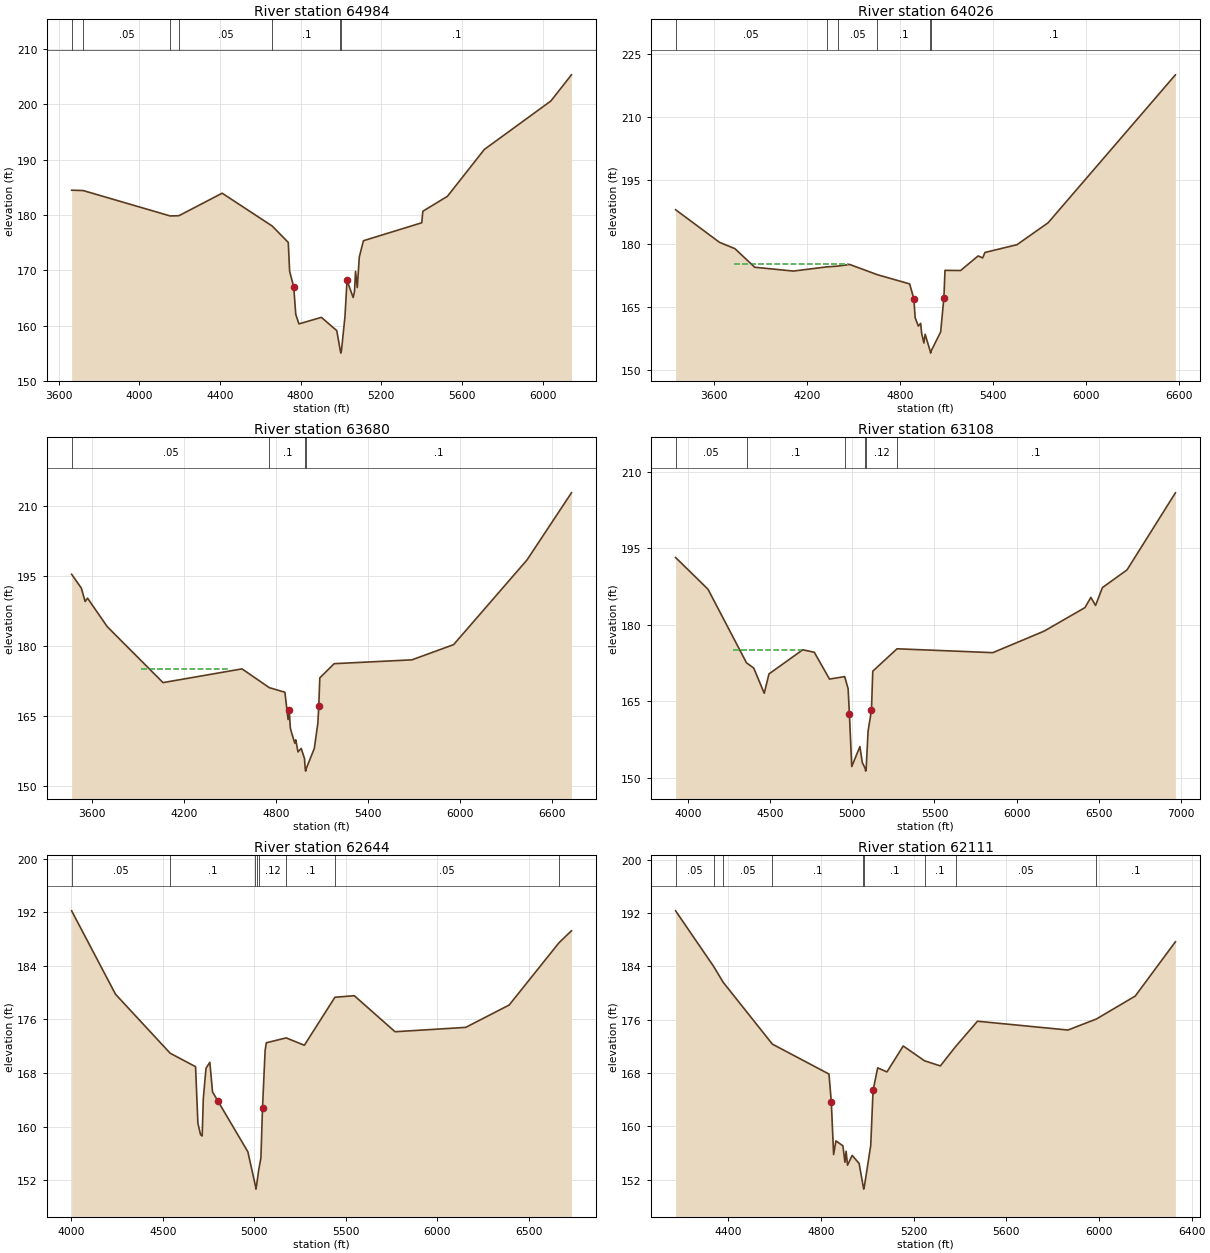
Type RM Length L Ch R = 1 ,64984   ,958,958,958
BEGIN DESCRIPTION:
Mapping XS a932ea74
END DESCRIPTION:
XS GIS Cut Line= 4
      2268499.04     13236957.71      2268394.87     13236124.34
      2268186.54     13234991.53      2267978.91     13234550.31
#Sta/Elev= 30
  3664.3  184.48  3721.3  184.42  4153.3  179.82  4196.7  179.87  4410.9  183.94
  4659.5  177.99  4738.9  175.03  4745.6  169.81    4766  166.95  4776.1  162.01
  4791.9   160.3  4903.1  161.48  4979.5  159.08  4996.8  155.51  4999.6  155.01
  5002.8  155.51  5020.1  161.61  5030.3  168.16  5060.8  165.07  5067.4  166.14
  5072.5   169.8  5081.2  166.87  5091.3  172.41  5111.7  175.34    5401  178.59
  5406.5  180.67  5528.5  183.38  5711.4  191.85  6041.6  200.62  6143.6  205.35
#Mann= 7 ,-1 , 0
  3664.3      .1       0  3721.3     .05       0  4153.3      .1       0
  4196.7     .05       0  4659.5      .1       0  4996.8     .07       0
  5002.8      .1       0
Bank Sta=4766,5030.3
XS Rating Curve= 0 ,0
Exp/Cntr=0.3,0.1

Type RM Length L Ch R = 1 ,64026   ,346,346,346
BEGIN DESCRIPTION:
RAMIRENA CREEK 62.0
END DESCRIPTION:
XS GIS Cut Line= 3
      2270126.63     13236567.04      2269449.56     13235994.13
       2268043.3     13234132.13
#Sta/Elev= 30
    3354  188.05  3637.4  180.29  3736.3   178.8  3863.7  174.39  4112.3  173.48
    4327  174.47  4397.3  174.65  4475.6  175.05  4653.7  172.62    4862  170.43
  4889.2  166.87  4897.4  162.39  4918.2  160.41  4932.8  161.07  4939.3  158.72
  4953.6  156.39  4961.9  158.47  4994.3  154.49  4997.1  153.99  5000.3  154.49
  5061.8  159.03  5082.7  167.19  5089.7  173.65  5189.9  173.61  5303.3  177.08
  5332.4   176.6    5347   177.9  5553.3  179.74  5753.8  184.94  6574.3  220.09
#Mann= 6 ,-1 , 0
    3354     .05       0    4327      .1       0  4397.3     .05       0
  4653.7      .1       0  4994.3     .07       0  5000.3      .1       0
#XS Ineff= 1 ,-1
 3727.78 4462.98  175.09
Permanent Ineff=
       F
Bank Sta=4889.2,5082.7
XS Rating Curve= 0 ,0
Exp/Cntr=0.3,0.1

Type RM Length L Ch R = 1 ,63680   ,572,572,572
BEGIN DESCRIPTION:
RAMIRENA CREEK 61.0
END DESCRIPTION:
XS GIS Cut Line= 3
      2270354.54     13236333.39      2269993.45     13236194.51
      2268279.25     13233890.41
#Sta/Elev= 30
  3469.5  195.43  3532.6  192.46  3557.3  189.58  3573.2  190.29  3701.9  184.16
  4065.3  172.15  4580.3   175.1    4758  171.07  4859.8  170.08  4880.6  164.22
    4888  166.25  4895.2  162.43  4901.5   161.6  4924.5  159.13  4930.7  159.86
  4945.3  157.26  4966.1  158.01  4987.7  155.82  4992.4  153.63  4995.1  153.13
  4998.4  153.63  5051.6     158  5074.6  163.39  5080.9  167.16  5087.4  173.16
    5181  176.22  5687.8  177.04  5959.9  180.31  6438.7  198.52  6728.2  212.93
#Mann= 4 ,-1 , 0
  3469.5     .05       0    4758      .1       0  4992.4     .07       0
  4998.4      .1       0
#XS Ineff= 1 ,-1
  3924.1  4493.9  175.06
Permanent Ineff=
       F
Bank Sta=4888,5080.9
XS Rating Curve= 0 ,0
Exp/Cntr=0.3,0.1

Type RM Length L Ch R = 1 ,63108   ,464,464,464
BEGIN DESCRIPTION:
RAMIRENA CREEK 60.0
END DESCRIPTION:
XS GIS Cut Line= 3
      2270583.69     13235937.54      2270312.89     13235736.18
      2268598.82     13233640.43
#Sta/Elev= 30
    3923  193.23  4120.2  187.01    4355  172.55  4399.1  171.52    4463  166.58
  4491.7  170.37  4697.7  175.12    4768  174.62  4860.6  169.36  4953.1  169.85
    4974  167.46  4981.9  162.46    4996  152.19  5045.8  156.11  5060.2  153.01
    5078  151.79  5080.8  151.29    5084  151.79  5095.4  159.11  5116.2  163.24
  5124.1  170.91    5272  175.31  5855.6  174.55  6168.5  178.78    6417   183.4
  6452.8   185.4  6481.5  183.82  6523.1  187.32  6673.2   190.8  6967.9  205.93
#Mann= 6 ,-1 , 0
    3923     .05       0    4355      .1       0  4953.1     .12       0
    5078     .07       0    5084     .12       0    5272      .1       0
#XS Ineff= 1 ,-1
 4273.95 4696.91  175.13
Permanent Ineff=
       F
Bank Sta=4981.9,5116.2
XS Rating Curve= 0 ,0
Exp/Cntr=0.3,0.1

Type RM Length L Ch R = 1 ,62644   ,533,533,533
BEGIN DESCRIPTION:
Mapping XS 722846a2
END DESCRIPTION:
XS GIS Cut Line= 3
      2270843.56     13235785.71      2270457.74     13235252.23
      2269257.61     13233561.56
#Sta/Elev= 30
  4002.4  192.22  4242.2  179.76  4540.9  170.95  4679.6  168.94  4692.4   160.5
  4707.1  158.77  4715.8  158.59  4721.9  164.16  4736.7   168.7  4757.6  169.59
  4772.4  165.17  4801.9   163.8  4965.5  156.23  5006.8  151.15  5009.5  150.65
  5012.8  151.15  5024.6  153.49  5036.8  155.31  5045.5  162.76  5059.8  171.38
  5066.4  172.51    5175  173.24  5274.2  172.14  5441.4  179.31  5547.4  179.54
    5770  174.16  6156.3  174.81  6393.7  178.15  6666.3  187.46  6734.1  189.24
#Mann= 8 ,-1 , 0
  4002.4     .05       0  4540.9      .1       0  5006.8     .07       0
  5012.8      .1       0  5024.6     .12       0    5175      .1       0
  5441.4     .05       0  6666.3      .1       0
#XS Ineff= 1 ,-1
 4539.68 4757.07  169.56
Permanent Ineff=
       F
Bank Sta=4801.9,5045.5
XS Rating Curve= 0 ,0
Exp/Cntr=0.3,0.1

Type RM Length L Ch R = 1 ,62111   ,359,359,359
BEGIN DESCRIPTION:
RAMIRENA CREEK 59.0
END DESCRIPTION:
XS GIS Cut Line= 3
      2271043.63     13235709.51      2270791.17     13235199.83
       2270710.2     13233613.67
#Sta/Elev= 30
  4172.9  192.33  4337.5  183.97  4377.7  181.64  4590.4  172.35  4834.8  167.86
  4844.8  163.71  4854.8  155.79  4864.8  157.84  4894.8  157.11  4903.7  154.64
  4908.7   156.3  4914.9   154.2  4934.9  155.67  4964.9  154.46    4982  151.11
  4984.7  150.61    4988  151.11    5015  157.16    5025   165.4    5045  168.79
  5085.1  168.18  5155.2  172.07  5247.2  169.85  5315.4  169.08  5381.3  171.98
  5475.6  175.78  5866.1  174.46  5988.7  176.11  6156.5  179.55  6329.9  187.69
#Mann= 9 ,-1 , 0
  4172.9     .05       0  4337.5      .1       0  4377.7     .05       0
  4590.4      .1       0    4982     .07       0    4988      .1       0
  5247.2      .1       0  5381.3     .05       0  5988.7      .1       0
Bank Sta=4844.8,5025
XS Rating Curve= 0 ,0
Exp/Cntr=0.3,0.1