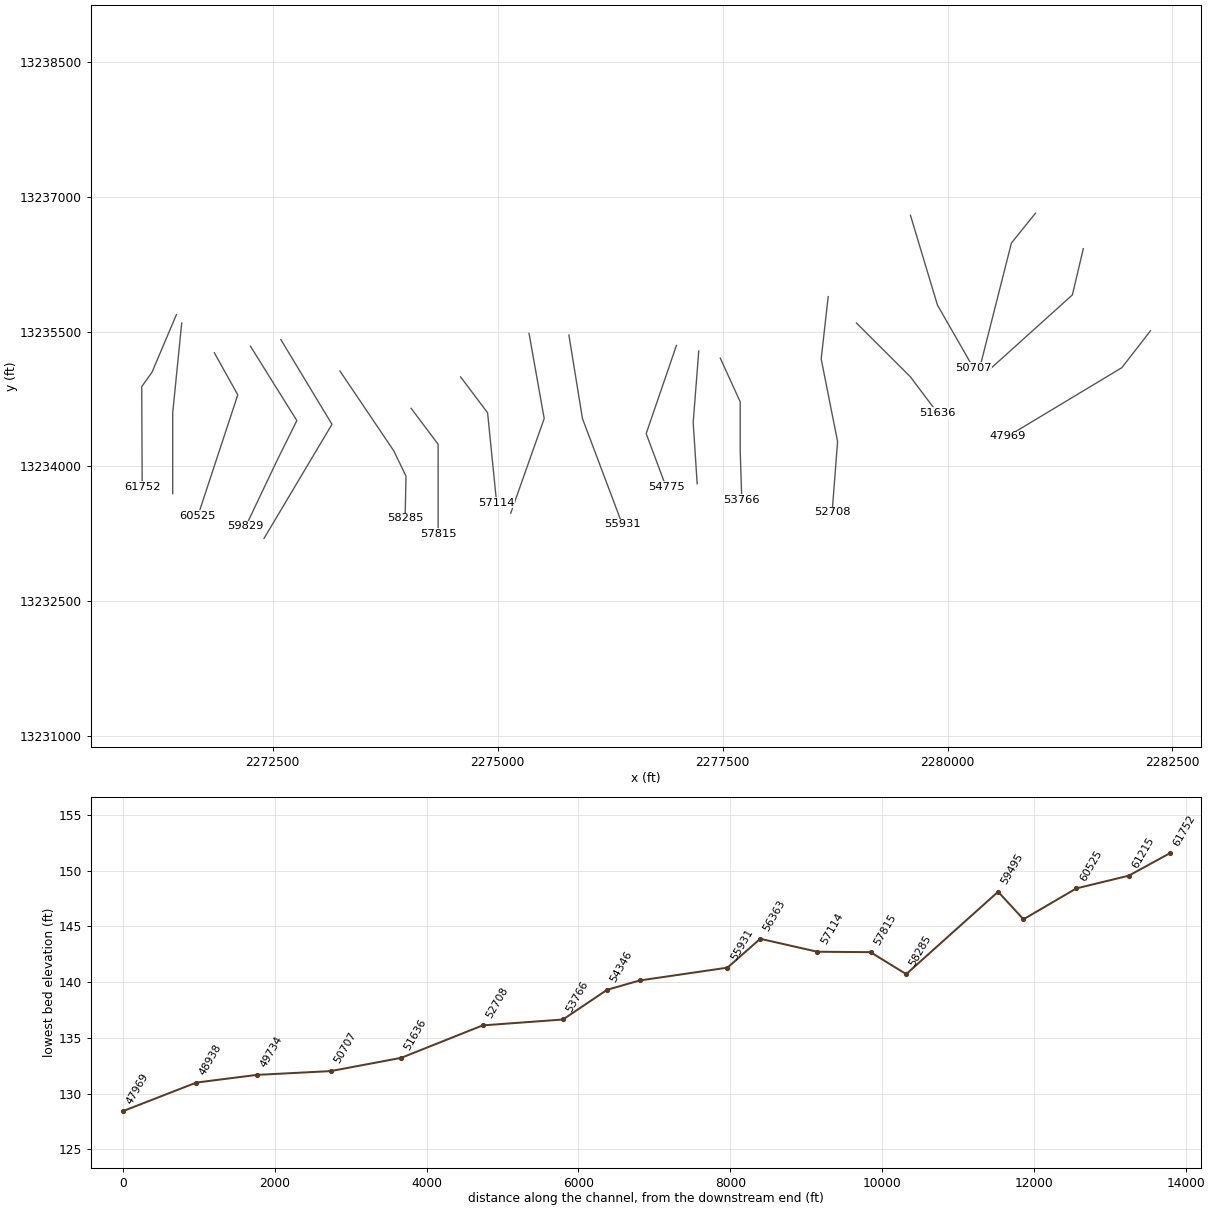
HEC-RAS study RAMIRENA CREEK.prj: RAMIRENA CREEK Base Level Engineering

--- RAMIRENA CREEK.g01 (geometry) --- (continued)

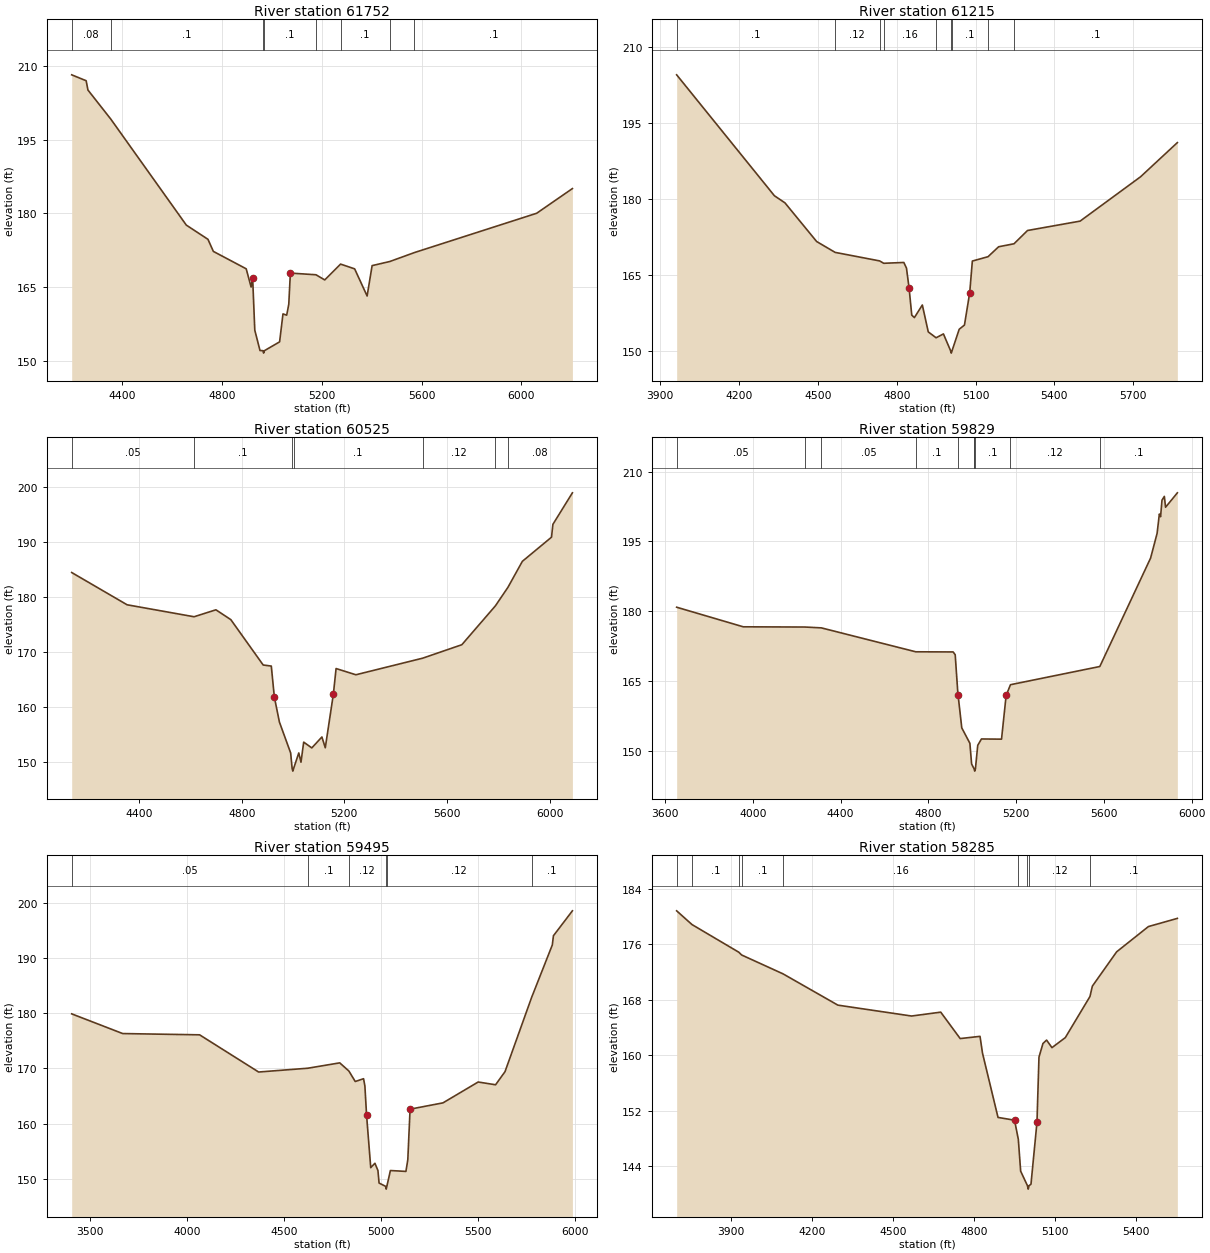
Type RM Length L Ch R = 1 ,61752   ,537,537,537
BEGIN DESCRIPTION:
Mapping XS cb431f6e
END DESCRIPTION:
XS GIS Cut Line= 4
      2271428.71     13235690.25       2271157.9     13235049.67
      2271043.31     13234888.21      2271048.52     13233773.58
#Sta/Elev= 30
    4197  208.16    4255  206.96  4262.1  205.07    4354  199.14  4656.7  177.59
  4743.5   174.7  4765.2  172.24  4896.9   168.7  4916.5  164.99  4922.6  166.93
  4931.3  156.22  4952.2  152.08    4964  152.05  4966.7  151.55    4970  152.05
  5030.8  153.84  5044.4  159.53  5059.2  159.27  5067.6  161.48    5074  167.83
  5176.6  167.49  5211.8  166.44  5275.4  169.66  5331.8  168.69  5381.8  163.17
  5401.8  169.35    5473  170.19  5571.8  172.01  6061.8     180  6205.1  185.02
#Mann= 8 ,-1 , 0
    4197     .08       0    4354      .1       0    4964     .07       0
    4970      .1       0  5176.6     .12       0  5275.4      .1       0
    5473     .08       0  5571.8      .1       0
Bank Sta=4922.6,5074
XS Rating Curve= 0 ,0
Exp/Cntr=0.3,0.1

Type RM Length L Ch R = 1 ,61215   ,690,690,690
BEGIN DESCRIPTION:
RAMIRENA CREEK 57.0
END DESCRIPTION:
XS GIS Cut Line= 3
      2271487.72     13235596.89      2271387.72     13234596.85
      2271387.72     13233696.88
#Sta/Elev= 30
  3962.8  204.47  4334.7  180.61  4374.9   179.2  4495.5  171.57  4565.8  169.43
  4734.9  167.75  4750.6  167.28  4827.1  167.44  4837.2  166.32  4847.2  162.36
  4857.3  157.05  4867.3  156.56  4897.5  159.05  4920.1  153.74  4949.8  152.58
  4977.8  153.34  5004.8  150.05  5007.6  149.55  5010.8  150.05  5037.8  154.26
  5057.8  155.09  5077.8  161.48  5087.8  167.72  5147.5  168.58  5187.8  170.54
  5246.3  171.13  5297.8  173.75  5497.8   175.6  5727.8  184.35  5867.8  191.09
#Mann= 9 ,-1 , 0
  3962.8      .1       0  4565.8     .12       0  4734.9      .1       0
  4750.6     .16       0  4949.8      .1       0  5004.8     .07       0
  5010.8      .1       0  5147.5     .08       0  5246.3      .1       0
Bank Sta=4847.2,5077.8
XS Rating Curve= 0 ,0
Exp/Cntr=0.3,0.1

Type RM Length L Ch R = 1 ,60525   ,696,696,696
BEGIN DESCRIPTION:
RAMIRENA CREEK 56.0
END DESCRIPTION:
XS GIS Cut Line= 3
      2271850.49     13235265.54      2272110.89     13234796.83
      2271668.25     13233451.57
#Sta/Elev= 30
  4136.9  184.42  4352.9  178.57    4614   176.4  4699.3  177.66  4757.3  175.88
  4883.6  167.65  4915.2  167.46  4927.1  161.84  4946.8  157.32  4990.7   151.7
  4996.4  148.91  4999.2  148.41  5002.4  148.91  5022.4  151.71    5031  150.03
  5041.5  153.67  5073.1  152.62  5112.5   154.6  5125.7  152.65  5157.3  162.39
  5167.8  167.01    5245  165.88  5505.6  168.89  5658.2  171.33  5789.1  178.38
    5838  181.74  5894.2  186.45  6007.9  190.83  6013.2  193.15  6089.3  198.87
#Mann= 7 ,-1 , 0
  4136.9     .05       0    4614      .1       0  4996.4     .07       0
  5002.4      .1       0  5505.6     .12       0  5789.1      .1       0
    5838     .08       0
Bank Sta=4927.1,5157.3
XS Rating Curve= 0 ,0
Exp/Cntr=0.3,0.1

Type RM Length L Ch R = 1 ,59829   ,334,334,334
BEGIN DESCRIPTION:
RAMIRENA CREEK 55.0
END DESCRIPTION:
XS GIS Cut Line= 4
      2272251.67     13235338.69      2272767.27     13234510.61
      2272543.31     13234057.48      2272199.54     13233333.49
#Sta/Elev= 30
  3652.5  180.86  3956.1  176.65  4238.4   176.6  4312.2  176.42  4742.5  171.28
  4912.8  171.25  4922.2  170.65  4934.1  162.51  4935.3     162  4952.2  154.93
  4989.1  151.63    4997  147.18  5007.8  146.18  5008.4  146.14  5011.2  145.64
  5014.4  146.14    5025  151.19  5041.9  152.55  5133.4  152.51  5154.4   161.9
  5174.2  164.21  5581.4  168.12  5812.9  191.42  5842.6  196.74  5852.8  200.88
  5858.4   200.3  5864.8  203.85  5875.6  204.68  5881.1  202.34  5934.9  205.44
#Mann= 10 ,-1 , 0
  3652.5     .05       0  4238.4      .1       0  4312.2     .05       0
  4742.5      .1       0  4934.1     .12       0  5007.8      .1       0
  5008.4     .07       0  5014.4      .1       0  5174.2     .12       0
  5581.4      .1       0
Bank Sta=4935.3,5154.4
XS Rating Curve= 0 ,0
Exp/Cntr=0.3,0.1

Type RM Length L Ch R = 1 ,59495   ,1210,1210,1210
BEGIN DESCRIPTION:
RAMIRENA CREEK 54.0
END DESCRIPTION:
XS GIS Cut Line= 3
       2272590.2     13235411.64       2273157.9     13234468.94
       2272402.7     13233198.14
#Sta/Elev= 30
  3406.5  179.87  3669.1   176.3  4065.2  176.07  4369.3  169.33  4622.7  170.02
  4786.9  170.99  4834.1  169.51  4866.8  167.61  4909.6  168.12  4916.5  166.79
  4925.2  161.49  4946.6     152  4968.1   152.8  4983.7  151.48  4989.5  149.21
  5023.5  148.61  5026.3  148.11  5029.5  148.61  5047.9  151.48  5127.8  151.32
  5137.5  153.44  5149.2   162.6  5318.7  163.74  5499.9  167.52  5589.5  167.02
  5638.2   169.4  5775.3  182.86  5881.7  192.35  5887.6  194.03  5985.2  198.54
#Mann= 6 ,-1 , 0
  3406.5     .05       0  4622.7      .1       0  4834.1     .12       0
  5023.5     .07       0  5029.5     .12       0  5775.3      .1       0
Bank Sta=4925.2,5149.2
XS Rating Curve= 0 ,0
Exp/Cntr=0.3,0.1

Type RM Length L Ch R = 1 ,58285   ,470,470,470
BEGIN DESCRIPTION:
RAMIRENA CREEK 53.0
END DESCRIPTION:
XS GIS Cut Line= 4
      2273246.43      13235062.7       2273845.4     13234172.07
      2273980.81     13233890.82       2273970.4     13233422.09
#Sta/Elev= 30
  3699.9  180.85  3756.7  178.87  3930.1  174.88  3940.7  174.48  4093.9  171.76
    4297  167.25  4569.9  165.68  4677.9  166.24  4749.9  162.43  4823.4  162.75
  4832.6  160.32    4890  151.06  4951.2  150.66  4965.2  147.91  4973.9  143.31
    4999  141.22  5001.8  140.72    5005  141.22  5012.1  141.43  5034.3  150.36
  5041.7  159.76  5056.5  161.72  5069.9  162.21  5089.8  161.12  5139.3  162.57
  5230.6   168.5  5239.4  169.99  5329.4  174.94    5447  178.58  5554.2  179.76
#Mann= 9 ,-1 , 0
  3699.9     .05       0  3756.7      .1       0  3930.1     .05       0
  3940.7      .1       0  4093.9     .16       0  4965.2     .12       0
    4999     .07       0    5005     .12       0  5230.6      .1       0
Bank Sta=4951.2,5034.3
XS Rating Curve= 0 ,0
Exp/Cntr=0.3,0.1

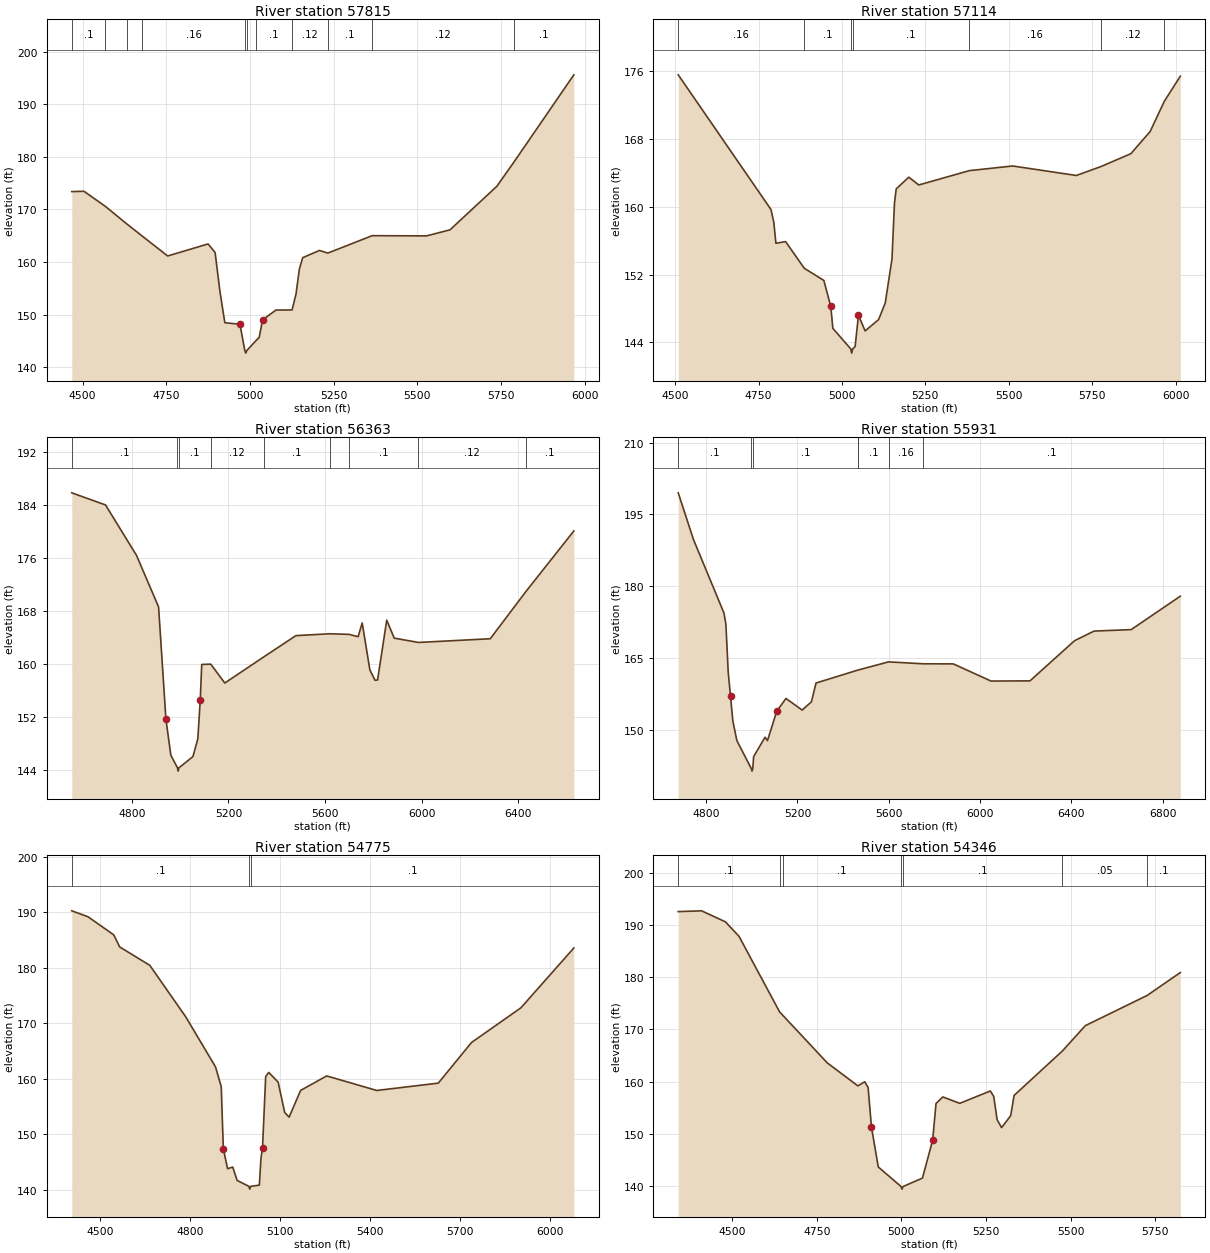
Type RM Length L Ch R = 1 ,57815   ,701,701,701
BEGIN DESCRIPTION:
RAMIRENA CREEK 52.0
END DESCRIPTION:
XS GIS Cut Line= 3
      2274037.69     13234646.89      2274337.72     13234246.85
      2274337.72      13233246.9
#Sta/Elev= 30
  4467.9   173.4  4504.4  173.46  4568.3  170.59    4633  167.22  4679.1  164.91
  4754.4  161.16  4875.2  163.45  4896.1  161.83  4910.7  154.36  4925.2  148.48
  4970.4  148.17  4984.9  143.19  4987.7  142.69  4990.9  143.19  5019.1  145.12
  5027.9  145.68  5037.9  149.01  5077.9  150.88  5126.1   150.9  5137.9  153.94
  5147.9  158.67  5157.9  160.84  5207.9  162.21    5233  161.71  5365.4  165.02
  5527.9  164.98  5597.9  166.13  5737.9  174.41  5790.1  179.12  5967.9   195.6
#Mann= 11 ,-1 , 0
  4467.9      .1       0  4568.3     .16       0    4633      .1       0
  4679.1     .16       0  4984.9     .07       0  4990.9     .16       0
  5019.1      .1       0  5126.1     .12       0    5233      .1       0
  5365.4     .12       0  5790.1      .1       0
Bank Sta=4970.4,5037.9
XS Rating Curve= 0 ,0
Exp/Cntr=0.3,0.1

Type RM Length L Ch R = 1 ,57114   ,751,751,751
BEGIN DESCRIPTION:
RAMIRENA CREEK 51.0
END DESCRIPTION:
XS GIS Cut Line= 3
      2274587.72     13234996.86      2274887.72     13234596.85
      2274987.72     13233596.85
#Sta/Elev= 30
  4509.4  175.55  4787.5  159.66  4795.9  158.16  4802.1  155.69  4831.3  155.88
  4887.2  152.74  4945.9   151.3  4966.7  148.24  4972.9  145.65  5026.5  143.23
  5029.3  142.73  5032.5  143.23  5039.6   143.5  5049.6  147.18  5069.7  145.35
  5109.9  146.68    5130  148.65  5150.1  153.83  5157.6   160.4  5162.7  162.09
  5200.4  163.48  5230.5  162.56  5381.8  164.25  5511.9   164.8  5702.8  163.68
  5776.4  164.73  5866.2  166.25  5923.9  168.86  5966.5  172.43  6014.4  175.39
#Mann= 7 ,-1 , 0
  4509.4     .16       0  4887.2      .1       0  5026.5     .07       0
  5032.5      .1       0  5381.8     .16       0  5776.4     .12       0
  5966.5      .1       0
Bank Sta=4966.7,5049.6
XS Rating Curve= 0 ,0
Exp/Cntr=0.3,0.1

Type RM Length L Ch R = 1 ,56363   ,432,432,432
BEGIN DESCRIPTION:
RAMIRENA CREEK 50.0
END DESCRIPTION:
XS GIS Cut Line= 3
      2275348.49     13235480.71      2275516.75     13234533.15
      2275145.25     13233480.56
#Sta/Elev= 30
  4551.6  185.87  4691.4  184.04  4819.6  176.44    4911  168.66  4941.5  151.69
  4961.8  146.29  4989.2  144.39    4992  143.89  4995.2  144.39  5053.2  146.08
  5073.5  148.78  5083.6  154.64  5089.6  159.98    5127  160.03  5185.2  157.18
    5346  161.11  5479.7  164.33    5620  164.61  5699.7  164.52  5737.2  164.17
    5754  166.24  5785.8  159.15    5807   157.6  5817.6  157.63  5855.6  166.66
  5886.6  163.95  5986.9   163.3  6284.2  163.86  6431.5  170.97  6630.2  180.12
#Mann= 9 ,-1 , 0
  4551.6      .1       0  4989.2     .07       0  4995.2      .1       0
    5127     .12       0    5346      .1       0    5620     .16       0
  5699.7      .1       0  5986.9     .12       0  6431.5      .1       0
Bank Sta=4941.5,5083.6
XS Rating Curve= 0 ,0
Exp/Cntr=0.3,0.1

Type RM Length L Ch R = 1 ,55931   ,1156,1156,1156
BEGIN DESCRIPTION:
RAMIRENA CREEK 49.0
END DESCRIPTION:
XS GIS Cut Line= 3
      2275791.27     13235463.02      2275941.82     13234533.15
      2276384.62     13233355.31
#Sta/Elev= 30
  4677.7  199.51  4744.5  189.74    4878  174.38  4886.5  172.09  4896.7  162.02
  4906.8  156.97  4916.9  151.82  4934.6  147.69  4998.3   141.8  5001.1   141.3
  5004.3   141.8  5008.1  144.32  5057.9  148.38  5068.9  147.68  5109.4  153.83
  5149.9   156.5  5220.8  154.07  5261.4   155.8  5281.6  159.73  5465.4  162.44
    5466  162.45  5599.6  164.15  5751.7  163.75  5883.1  163.73  6048.4  160.14
  6219.2  160.18  6414.8  168.59  6500.1  170.59  6662.7   170.9    6878  177.89
#Mann= 7 ,-1 , 0
  4677.7      .1       0  4998.3     .07       0  5004.3      .1       0
  5465.4     .16       0    5466      .1       0  5599.6     .16       0
  5751.7      .1       0
Bank Sta=4906.8,5109.4
XS Rating Curve= 0 ,0
Exp/Cntr=0.3,0.1

Type RM Length L Ch R = 1 ,54775   ,429,429,429
BEGIN DESCRIPTION:
RAMIRENA CREEK 48.0
END DESCRIPTION:
XS GIS Cut Line= 3
      2276986.78     13235347.85      2276650.28     13234364.89
      2276871.62      13233771.7
#Sta/Elev= 30
  4406.1  190.25    4460  189.19    4546  185.92  4565.7  183.75  4665.9  180.44
  4785.8  171.16  4884.9  162.15  4903.9  158.59  4910.9  147.39  4925.1  143.83
  4942.2  144.12  4956.8  141.72  4996.1  140.65  4998.8  140.15  5002.1  140.65
  5030.8  140.87  5036.1  145.66  5041.4   147.6  5051.9  160.41  5062.1  161.16
  5093.4  159.41  5115.3  153.94    5130  153.11  5168.2  157.92  5255.1  160.53
  5421.8  157.91  5626.7  159.23  5737.3  166.54  5901.9  172.79  6078.2  183.56
#Mann= 3 ,-1 , 0
  4406.1      .1       0  4996.1     .07       0  5002.1      .1       0
Bank Sta=4910.9,5041.4
XS Rating Curve= 0 ,0
Exp/Cntr=0.3,0.1

Type RM Length L Ch R = 1 ,54346   ,580,580,580
BEGIN DESCRIPTION:
RAMIRENA CREEK 47.0
END DESCRIPTION:
XS GIS Cut Line= 3
      2277234.75     13235285.85      2277172.76     13234488.87
      2277217.04       13233807.
#Sta/Elev= 30
  4341.1  192.66  4410.3  192.81  4480.5  190.69  4520.6  187.91  4640.3   173.4
  4650.1  172.71  4781.4  163.57  4871.7  159.16  4891.8  159.95  4901.8  158.85
  4911.8  151.18  4931.9  143.57  4999.1  139.81  5001.8  139.31  5005.1  139.81
  5062.3  141.43  5092.4  148.69  5102.4  155.77  5122.5  157.03  5172.6   155.8
  5262.8  158.18  5272.8  157.14  5282.8  152.66    5296  151.13  5322.9  153.43
  5332.9  157.32    5475  165.83  5543.4  170.74  5725.5  176.53  5823.8  180.94
#Mann= 7 ,-1 , 0
  4341.1      .1       0  4640.3     .05       0  4650.1      .1       0
  4999.1     .07       0  5005.1      .1       0    5475     .05       0
  5725.5      .1       0
Bank Sta=4911.8,5092.4
XS Rating Curve= 0 ,0
Exp/Cntr=0.3,0.1

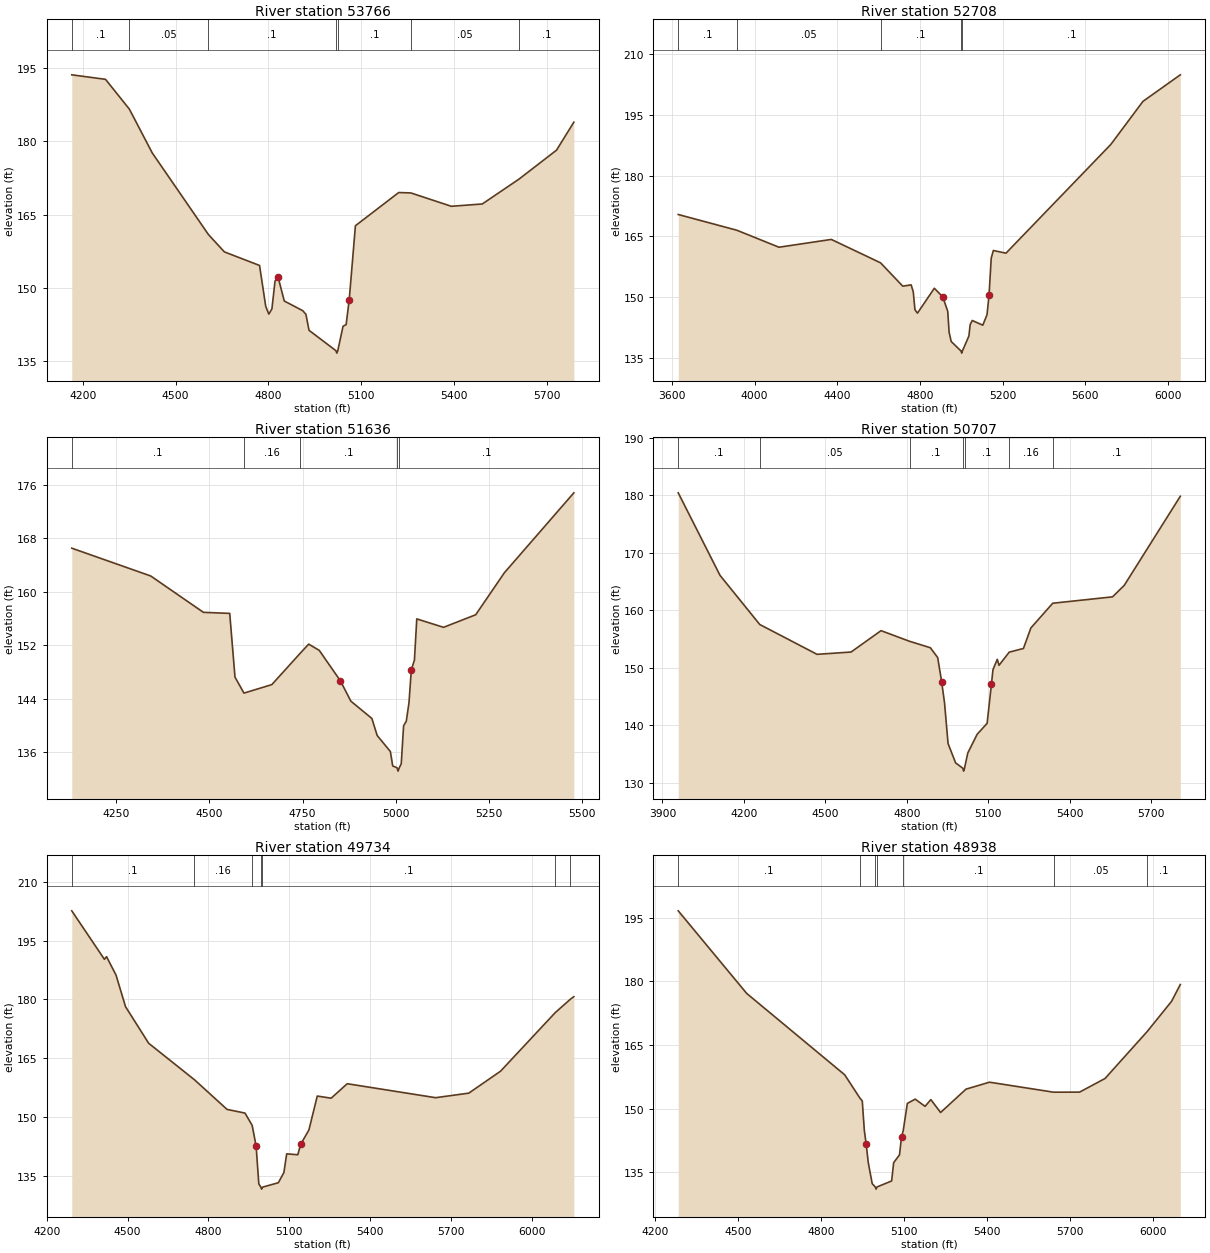
Type RM Length L Ch R = 1 ,53766   ,1058,1058,1058
BEGIN DESCRIPTION:
RAMIRENA CREEK 46.0
END DESCRIPTION:
XS GIS Cut Line= 4
      2277473.87     13235206.14      2277695.25     13234719.12
      2277695.25     13234178.92      2277712.92     13233630.88
#Sta/Elev= 30
  4164.3  193.58  4273.4  192.66  4350.6  186.56  4424.5  177.61  4606.3   160.9
  4657.8  157.36  4771.5  154.58  4791.5  146.21  4801.5  144.63  4811.5  145.69
  4821.5  151.37  4831.5  152.17  4851.5  147.31  4911.5  145.32  4921.5  144.57
  4931.5  141.32  5018.5  137.15  5021.3  136.65  5024.5  137.15  5041.5  142.14
  5051.5  142.48  5061.5  147.59  5081.5  162.71  5221.5   169.5  5260.7  169.42
  5391.6  166.69  5491.7  167.16  5610.1  172.23  5731.8  178.17  5787.8  183.89
#Mann= 7 ,-1 , 0
  4164.3      .1       0  4350.6     .05       0  4606.3      .1       0
  5018.5     .07       0  5024.5      .1       0  5260.7     .05       0
  5610.1      .1       0
Bank Sta=4831.5,5061.5
XS Rating Curve= 0 ,0
Exp/Cntr=0.3,0.1

Type RM Length L Ch R = 1 ,52708   ,1072,1072,1072
BEGIN DESCRIPTION:
RAMIRENA CREEK 45.0
END DESCRIPTION:
XS GIS Cut Line= 4
      2278673.52     13235891.22       2278595.4     13235196.81
      2278777.69     13234276.67      2278716.92     13233486.72
#Sta/Elev= 30
  3630.3  170.39  3913.9   166.5  4117.7   162.3  4370.9  164.23  4609.3  158.44
  4716.4  152.68  4757.2  152.99  4767.4  151.27  4775.5  146.85  4787.8     146
  4869.3  152.16  4910.1  150.03  4934.2  146.45  4940.7  141.33  4950.9     139
  4998.9  136.62  5001.6  136.12  5004.9  136.62  5036.6  140.35  5042.7  143.17
  5052.8  144.19  5103.8  143.03  5124.2  145.61    5134  150.42  5144.6  159.59
  5154.8  161.49    5216  160.83  5723.2  187.71  5878.7  198.36  6059.4  204.92
#Mann= 5 ,-1 , 0
  3630.3      .1       0  3913.9     .05       0  4609.3      .1       0
  4998.9     .07       0  5004.9      .1       0
Bank Sta=4910.1,5134
XS Rating Curve= 0 ,0
Exp/Cntr=0.3,0.1

Type RM Length L Ch R = 1 ,51636   ,929,929,929
BEGIN DESCRIPTION:
RAMIRENA CREEK 44.0
END DESCRIPTION:
XS GIS Cut Line= 3
       2278987.7     13235596.87      2279587.72     13234996.85
      2279887.75     13234596.82
#Sta/Elev= 30
  4130.2  166.53  4342.4  162.37  4483.8  156.94  4554.5  156.78  4568.6  147.26
  4592.7  144.87  4667.6  146.14  4743.6  150.81  4766.6  152.19  4794.9  151.26
  4851.5  146.73  4879.8  143.67  4936.3  141.08  4950.5  138.54    4986  136.14
  4992.3  133.98  5003.9  133.71  5006.6  133.21  5009.9  133.71  5015.2  134.31
  5021.5  139.98  5028.8  140.68    5036  143.46  5042.3  148.37  5050.6  149.79
  5056.9  155.96  5128.8   154.7  5215.2  156.58  5292.3  162.86  5478.8   174.8
#Mann= 5 ,-1 , 0
  4130.2      .1       0  4592.7     .16       0  4743.6      .1       0
  5003.9     .07       0  5009.9      .1       0
Bank Sta=4851.5,5042.3
XS Rating Curve= 0 ,0
Exp/Cntr=0.3,0.1

Type RM Length L Ch R = 1 ,50707   ,973,973,973
BEGIN DESCRIPTION:
RAMIRENA CREEK 43.0
END DESCRIPTION:
XS GIS Cut Line= 3
      2279587.72     13236796.86      2279887.72     13235796.85
      2280287.74     13235096.82
#Sta/Elev= 30
    3958  180.44    4112  166.08  4258.5  157.53  4469.6  152.34  4594.9  152.74
  4705.4  156.46  4810.4  154.61  4887.2  153.49  4914.2  151.77    4929   147.5
  4939.4  143.88  4952.4  136.82  4980.3  133.45    5007  132.52  5009.7  132.02
    5013  132.52  5025.1  135.17  5059.6  138.43  5096.3  140.33  5112.2  147.12
  5117.9  149.67  5133.8  151.48  5140.2  150.43  5177.8  152.72  5230.2  153.36
  5257.6  156.93  5338.2  161.23  5558.5  162.34  5601.7  164.34  5808.3  179.84
#Mann= 7 ,-1 , 0
    3958      .1       0  4258.5     .05       0  4810.4      .1       0
    5007     .07       0    5013      .1       0  5177.8     .16       0
  5338.2      .1       0
Bank Sta=4929,5112.2
XS Rating Curve= 0 ,0
Exp/Cntr=0.3,0.1

Type RM Length L Ch R = 1 ,49734   ,796,796,796
BEGIN DESCRIPTION:
RAMIRENA CREEK 42.0
END DESCRIPTION:
XS GIS Cut Line= 3
      2280976.49     13236818.91      2280710.19     13236488.93
      2280357.08     13235093.86
#Sta/Elev= 30
    4293  202.57  4414.1  190.22  4422.1  190.89  4457.3  186.19  4492.5  178.16
  4578.3  168.84  4748.3  159.54  4869.2  151.99  4935.8  151.05  4962.5  147.91
  4977.1  142.66  4987.1  133.01  4994.7  132.18  4997.4  131.68  5000.7  132.18
  5059.6  133.31  5080.2  135.91  5090.5  140.66  5131.8  140.44  5142.1  143.05
    5173  146.75    5204  155.39  5255.6  154.84  5315.2  158.53  5643.2  154.97
  5766.3  156.13  5884.1  161.72  6087.2  176.65  6143.5  180.07  6156.1   180.7
#Mann= 7 ,-1 , 0
    4293      .1       0  4748.3     .16       0  4962.5      .1       0
  4994.7     .07       0  5000.7      .1       0  6087.2     .05       0
  6143.5      .1       0
Bank Sta=4977.1,5142.1
XS Rating Curve= 0 ,0
Exp/Cntr=0.3,0.1

Type RM Length L Ch R = 1 ,48938   ,969,969,969
BEGIN DESCRIPTION:
RAMIRENA CREEK 41.0
END DESCRIPTION:
XS GIS Cut Line= 3
      2281509.04     13236425.29      2281387.47     13235910.06
      2280432.49     13235047.69
#Sta/Elev= 30
  4283.4  196.65  4531.1  177.16  4885.6  157.96  4940.2   152.5  4949.1  151.79
  4956.6  144.81  4963.3  141.58  4970.8  137.25    4985  132.29  4996.2  131.49
    4999  130.99  5002.2  131.49  5055.3  132.92  5062.7  137.24  5083.7  139.06
  5091.1  143.31  5097.3  144.81  5112.1  151.21  5140.5  152.22  5176.2  150.52
  5197.2  152.11  5232.4  149.07  5324.4  154.58  5409.5  156.22    5641  153.86
  5735.3  153.88  5827.2  157.09  5979.3  168.14  6067.8  175.29  6099.5  179.27
#Mann= 7 ,-1 , 0
  4283.4      .1       0  4940.2     .05       0  4996.2    .035       0
  5002.2     .05       0  5097.3      .1       0    5641     .05       0
  5979.3      .1       0
Bank Sta=4963.3,5091.1
XS Rating Curve= 0 ,0
Exp/Cntr=0.3,0.1

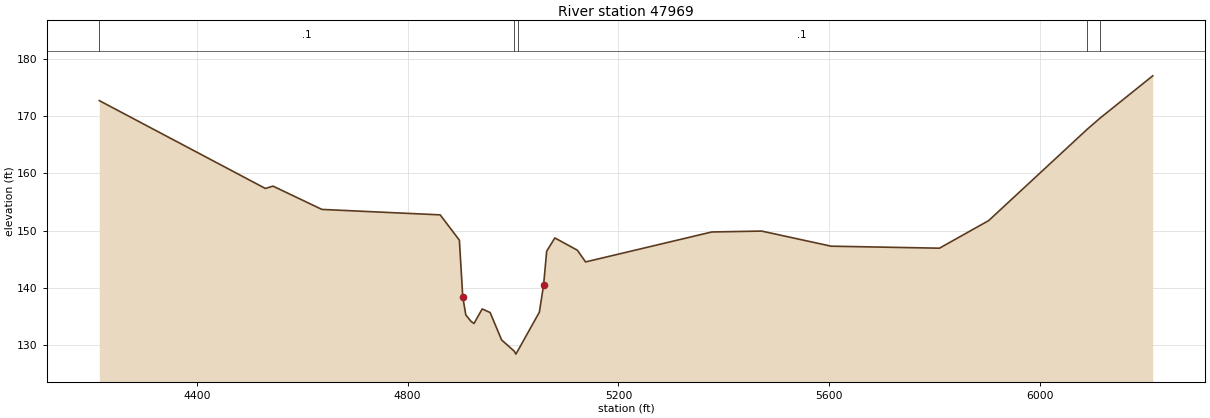
Type RM Length L Ch R = 1 ,47969   ,978,978,978
BEGIN DESCRIPTION:
RAMIRENA CREEK 40.0
END DESCRIPTION:
XS GIS Cut Line= 3
      2282255.76     13235510.64      2281937.39     13235099.65
      2280671.19     13234336.46
#Sta/Elev= 30
  4215.2  172.69  4530.2  157.35  4544.6  157.76  4637.4  153.69  4861.8  152.74
  4898.2  148.32  4904.6  138.43  4910.4  135.27  4920.1  134.16  4925.9  133.77
  4941.5  136.31  4956.5  135.69  4978.3   130.9  5002.5  128.92  5005.3  128.42
  5008.5  128.92  5049.9  135.74    5058  140.52  5063.8  146.39  5079.3  148.71
    5122  146.57  5137.6  144.52  5376.9  149.75  5471.5  149.91  5603.5  147.27
  5808.9  146.92  5902.3  151.74  6088.6  167.64  6113.5  169.63  6213.5  177.02
#Mann= 5 ,-1 , 0
  4215.2      .1       0  5002.5     .07       0  5008.5      .1       0
  6088.6     .05       0  6113.5      .1       0
Bank Sta=4904.6,5058
XS Rating Curve= 0 ,0
Exp/Cntr=0.3,0.1