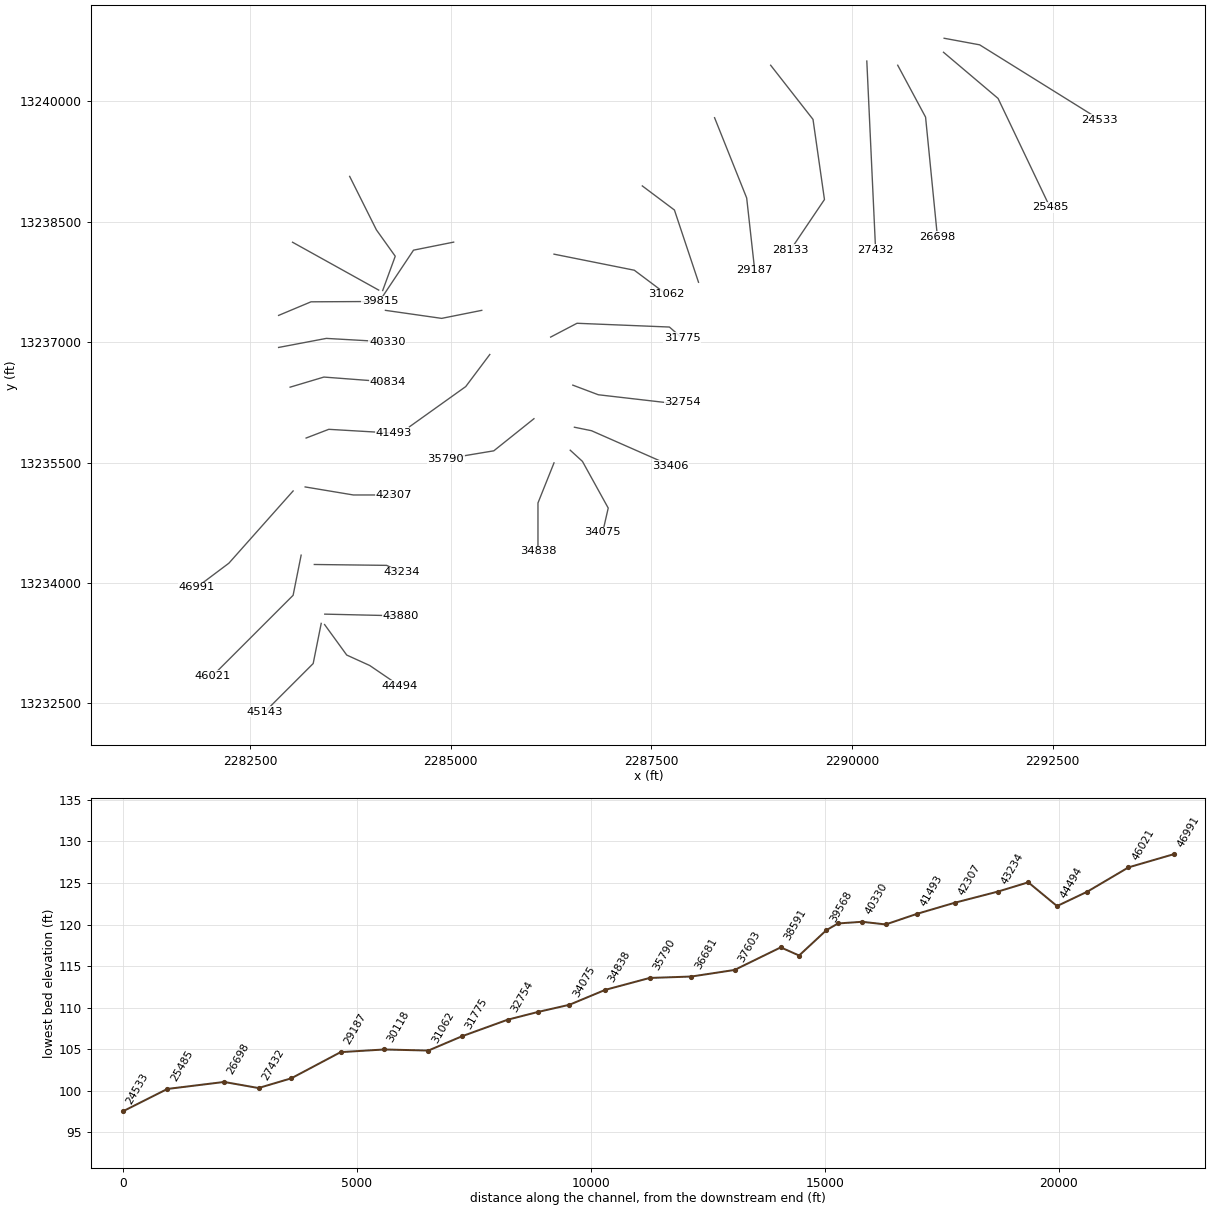
HEC-RAS study RAMIRENA CREEK.prj: RAMIRENA CREEK Base Level Engineering

--- RAMIRENA CREEK.g01 (geometry) --- (continued)

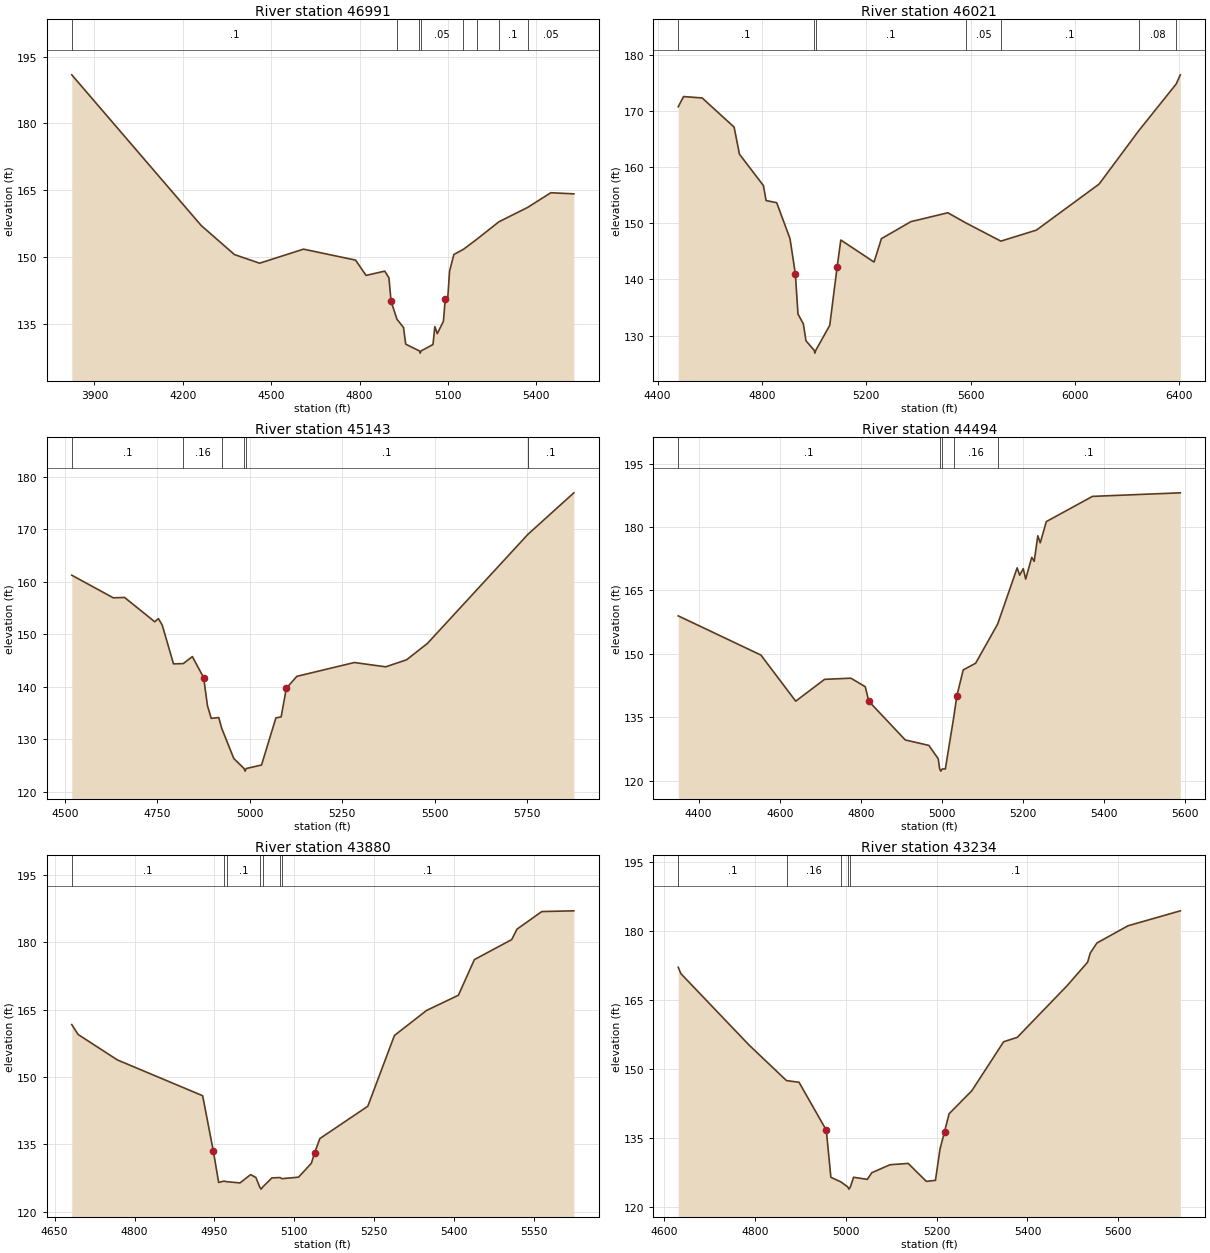
Type RM Length L Ch R = 1 ,46991   ,970,970,970
BEGIN DESCRIPTION:
RAMIRENA CREEK 39.0
END DESCRIPTION:
XS GIS Cut Line= 3
      2283037.71     13235146.85      2282237.72     13234246.85
      2281837.76     13233946.88
#Sta/Elev= 30
  3823.2  190.92  4262.6   157.1  4375.5  150.58  4460.8  148.65  4609.7   151.8
  4786.5  149.34  4822.1  145.91  4885.6  146.87  4899.8  145.35  4906.9   140.1
    4927  136.07  4949.2  134.22  4956.7  130.48    5003  128.97  5005.8  128.47
    5009  128.97  5049.2   130.4  5055.5  134.42  5063.8  132.84  5084.6  135.61
  5090.9  140.62  5099.2  140.73  5105.5  146.87  5120.1   150.6  5152.7  151.77
  5198.9  154.07  5272.7  157.93  5370.3  161.16  5449.2  164.46  5527.3  164.21
#Mann= 8 ,-1 , 0
  3823.2      .1       0    4927     .05       0    5003    .035       0
    5009     .05       0  5152.7      .1       0  5198.9     .16       0
  5272.7      .1       0  5370.3     .05       0
Bank Sta=4906.9,5090.9
XS Rating Curve= 0 ,0
Exp/Cntr=0.3,0.1

Type RM Length L Ch R = 1 ,46021   ,878,878,878
BEGIN DESCRIPTION:
RAMIRENA CREEK 38.0
END DESCRIPTION:
XS GIS Cut Line= 3
      2283137.73      13234346.9      2283037.72     13233846.85
       2282037.7     13232846.83
#Sta/Elev= 30
  4479.2  170.74  4499.6  172.56    4571  172.31  4693.4  167.12  4713.8   162.3
  4805.6  156.72  4815.8  154.05  4856.6  153.66  4907.6  147.26    4928  141.02
  4938.2  133.83  4958.6   132.1  4968.8  129.08  5000.3  127.38    5003  126.88
  5006.3  127.38  5059.9  131.83  5088.1   142.2  5102.3  147.02  5229.6   143.1
  5257.9  147.26    5371  150.29  5512.4  151.87  5581.8  150.06  5715.7  146.82
  5851.8  148.78  6092.2  156.98  6243.5  166.44  6387.5  174.79  6403.4  176.43
#Mann= 7 ,-1 , 0
  4479.2      .1       0  5000.3     .07       0  5006.3      .1       0
  5581.8     .05       0  5715.7      .1       0  6243.5     .08       0
  6387.5      .1       0
Bank Sta=4928,5088.1
XS Rating Curve= 0 ,0
Exp/Cntr=0.3,0.1

Type RM Length L Ch R = 1 ,45143   ,649,649,649
BEGIN DESCRIPTION:
RAMIRENA CREEK 37.0
END DESCRIPTION:
XS GIS Cut Line= 3
      2283387.72     13233496.85      2283287.72     13232996.85
      2282687.74     13232396.87
#Sta/Elev= 30
  4518.4  161.23  4630.6  156.93  4661.2     157  4742.8  152.38  4752.9  152.97
  4763.1  151.75  4793.7  144.36  4820.2  144.42  4844.7  145.75  4875.3  141.73
  4885.5  136.42  4895.7     134  4916.1  134.15  4924.2  132.09  4956.9  126.35
  4984.5  124.46  4987.3  123.96  4990.5  124.46  5031.8  125.12  5070.7  134.09
  5084.9  134.28    5099  139.73  5127.3  141.99  5282.9  144.62  5367.7   143.8
  5424.3  145.14  5480.8  148.26  5751.7  168.94  5752.8  169.02  5876.8   176.9
#Mann= 7 ,-1 , 0
  4518.4      .1       0  4820.2     .16       0  4924.2      .1       0
  4984.5     .07       0  4990.5      .1       0  5751.7     .05       0
  5752.8      .1       0
Bank Sta=4875.3,5099
XS Rating Curve= 0 ,0
Exp/Cntr=0.3,0.1

Type RM Length L Ch R = 1 ,44494   ,614,614,614
BEGIN DESCRIPTION:
Mapping XS abf543f6
END DESCRIPTION:
XS GIS Cut Line= 4
       2283429.7     13233482.43      2283705.73     13233102.25
      2283992.18     13232972.04       2284367.2     13232716.82
#Sta/Elev= 30
  4349.8  158.97  4553.7  149.69  4639.5  138.78  4710.6  143.94  4775.6  144.22
  4811.1  142.19  4819.6  138.77  4909.7   129.6  4967.8  128.31  4990.9  125.15
  4994.6  122.72  4997.3  122.22  5000.6  122.72  5008.5  122.74    5029  134.86
    5037  140.07  5052.5  146.17  5083.2  147.76  5137.5  157.04  5185.6  170.33
  5191.7  168.59  5200.6  170.14  5206.6  167.67  5221.5  172.82  5227.6  171.87
  5236.5  177.93  5242.5  176.26  5257.5  181.28  5371.3  187.25  5587.9  188.09
#Mann= 5 ,-1 , 0
  4349.8      .1       0  4994.6     .07       0  5000.6      .1       0
    5029     .16       0  5137.5      .1       0
Bank Sta=4819.6,5037
XS Rating Curve= 0 ,0
Exp/Cntr=0.3,0.1

Type RM Length L Ch R = 1 ,43880   ,646,646,646
BEGIN DESCRIPTION:
RAMIRENA CREEK 36.0
END DESCRIPTION:
XS GIS Cut Line= 2
      2283432.13     13233612.17      2284374.38     13233590.51
#Sta/Elev= 30
  4682.1  161.65  4694.2  159.44  4767.7   153.8  4927.8  145.84  4947.8  133.57
  4957.8  126.57  4967.5  126.86  4974.2  126.72  4997.8  126.46  5017.8   128.3
  5027.8  127.66  5034.8  125.58  5037.5  125.08  5040.8  125.58  5057.8  127.58
  5073.1  127.65  5076.5   127.4  5107.8  127.74  5131.9  130.83  5137.8  133.09
  5147.8  136.32  5237.8   143.5  5287.8  159.23  5347.9  164.78  5407.9  168.18
  5437.9   176.1  5507.9  180.54  5517.9  182.87  5564.5  186.78  5624.6  186.94
#Mann= 7 ,-1 , 0
  4682.1      .1       0  4967.5     .16       0  4974.2      .1       0
  5034.8     .07       0  5040.8      .1       0  5073.1     .16       0
  5076.5      .1       0
Bank Sta=4947.8,5137.8
XS Rating Curve= 0 ,0
Exp/Cntr=0.3,0.1

Type RM Length L Ch R = 1 ,43234   ,927,927,927
BEGIN DESCRIPTION:
RAMIRENA CREEK 35.0
END DESCRIPTION:
XS GIS Cut Line= 3
       2283301.9     13234230.66      2284202.52     13234219.81
      2284387.03     13234132.98
#Sta/Elev= 30
  4631.6   172.2  4637.4  170.83  4787.4   155.3  4869.8  147.57  4897.4   147.2
  4957.4  136.78  4967.4  126.55  4989.9  125.51  5004.4  124.47  5007.2  123.97
  5010.4  124.47  5017.4  126.55  5047.5  126.09  5057.5  127.54  5097.5  129.27
  5137.5  129.56  5177.5  125.65  5197.5  125.88  5207.5  132.68  5217.5  136.47
  5227.5  140.35  5277.5  145.36  5347.5  156.01  5377.5  156.97  5487.5  168.24
  5532.3  173.32    5538  175.29  5552.8  177.49  5621.2  181.23  5736.2  184.48
#Mann= 5 ,-1 , 0
  4631.6      .1       0  4869.8     .16       0  4989.9      .1       0
  5004.4     .07       0  5010.4      .1       0
Bank Sta=4957.4,5217.5
XS Rating Curve= 0 ,0
Exp/Cntr=0.3,0.1

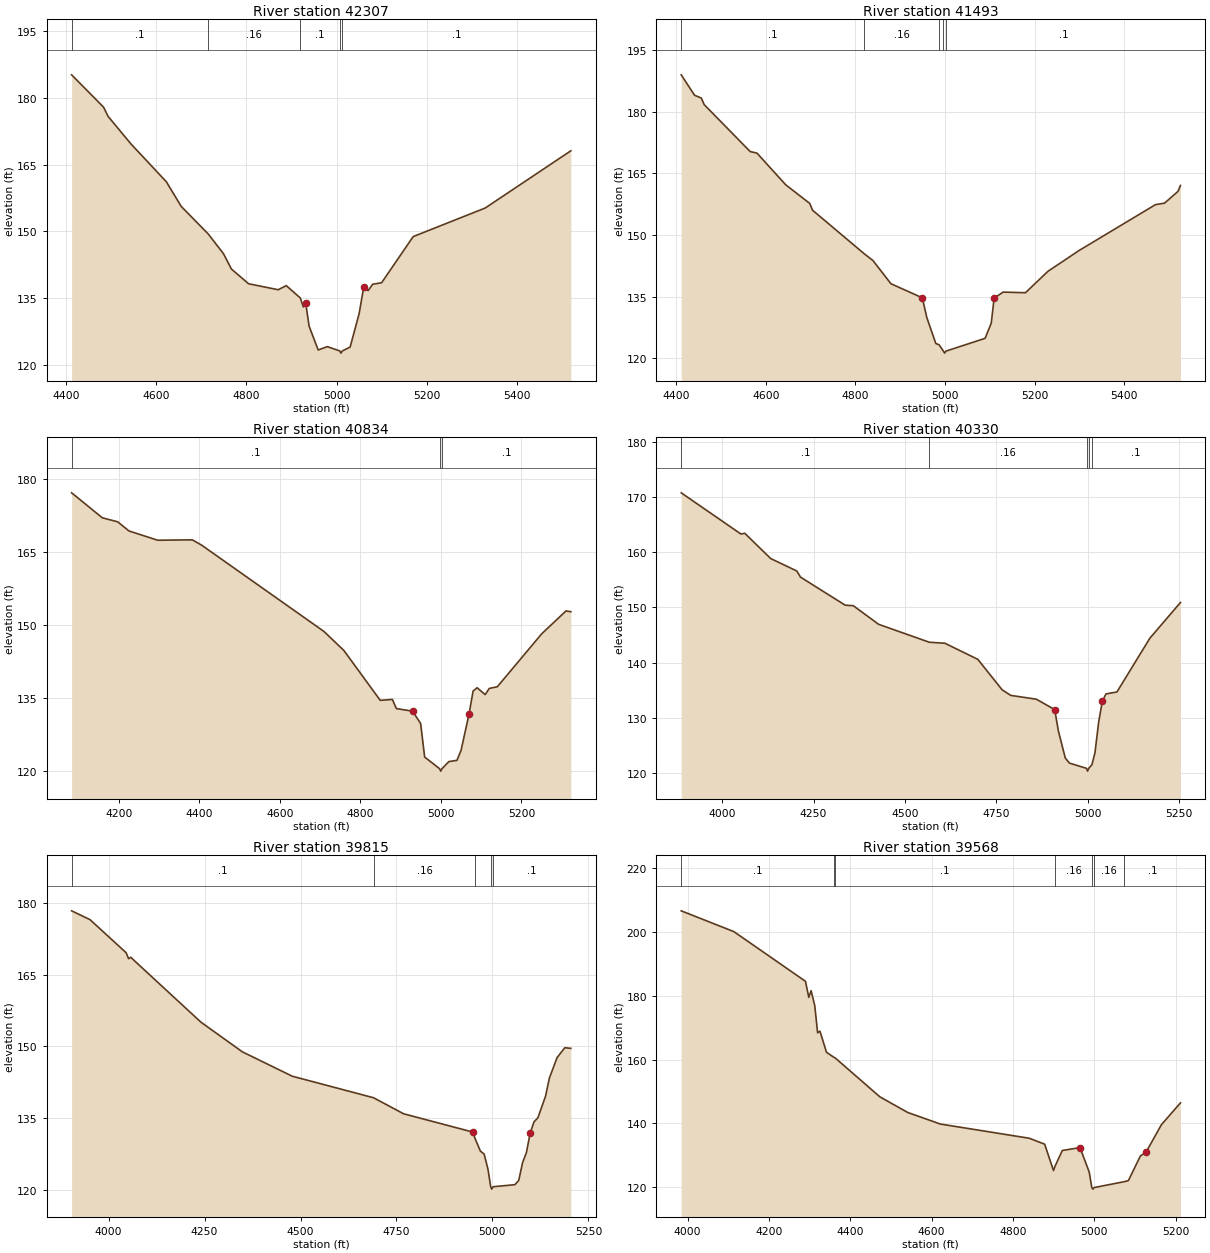
Type RM Length L Ch R = 1 ,42307   ,814,814,814
BEGIN DESCRIPTION:
RAMIRENA CREEK 34.0
END DESCRIPTION:
XS GIS Cut Line= 3
      2283187.73     13235196.85      2283787.72     13235096.85
      2284287.75     13235096.85
#Sta/Elev= 30
  4411.9  185.19  4482.9  177.91    4493  175.83  4543.7  169.65  4622.3  161.13
  4655.2  155.61    4715  149.43    4749  144.98  4766.7  141.52  4804.7  138.22
  4870.6  136.87  4888.4   137.8  4919.6  135.02  4926.4     133  4931.5  133.94
  4939.1  128.69  4959.3  123.33  4979.6  124.08    5007  123.12  5009.8  122.62
    5013  123.12  5030.2  123.98  5050.2   131.5  5060.2  137.38  5070.2  136.68
  5080.2   138.1  5100.2  138.46  5170.2  148.82  5330.2  155.25  5520.2  168.11
#Mann= 5 ,-1 , 0
  4411.9      .1       0    4715     .16       0  4919.6      .1       0
    5007     .07       0    5013      .1       0
Bank Sta=4931.5,5060.2
XS Rating Curve= 0 ,0
Exp/Cntr=0.3,0.1

Type RM Length L Ch R = 1 ,41493   ,659,659,659
BEGIN DESCRIPTION:
RAMIRENA CREEK 33.0
END DESCRIPTION:
XS GIS Cut Line= 3
      2283199.87     13235806.16      2283482.03     13235914.69
      2284293.22     13235866.97
#Sta/Elev= 30
  4410.9  188.95  4440.7  183.98  4455.7  183.31  4462.2   181.7    4565  170.28
    4580  169.92  4644.3   162.2  4697.9  157.68  4704.3  156.01  4819.2  145.47
  4839.1  143.79  4879.2  138.15  4949.3  134.72  4959.3  129.95  4979.4  123.62
  4986.9  123.28  4996.4  121.77  4999.1  121.27  5002.4  121.77  5089.5  124.87
  5103.3  128.56  5109.6   134.6  5129.6  136.11  5179.7  135.96  5229.8  141.16
  5299.9  146.26  5470.2  157.39  5490.2  157.74  5520.3   160.6  5525.8  162.04
#Mann= 5 ,-1 , 0
  4410.9      .1       0  4819.2     .16       0  4986.9      .1       0
  4996.4     .07       0  5002.4      .1       0
Bank Sta=4949.3,5109.6
XS Rating Curve= 0 ,0
Exp/Cntr=0.3,0.1

Type RM Length L Ch R = 1 ,40834   ,504,504,504
BEGIN DESCRIPTION:
Mapping XS d566d330
END DESCRIPTION:
XS GIS Cut Line= 3
       2283000.3     13236439.87      2283421.27     13236565.73
      2284219.88     13236504.97
#Sta/Elev= 30
  4082.6  177.12  4158.8     172  4197.1  171.17    4225   169.3  4296.4  167.39
  4382.6  167.47  4406.2  166.35  4709.4  148.68  4759.1  144.76  4849.4  134.53
  4879.5  134.72  4889.5  132.84  4929.6  132.32  4949.7  129.79  4959.7   122.9
  4996.8  120.51  4999.6  120.01  5002.8  120.51  5019.9  121.97  5039.9  122.22
    5050  124.23    5070  131.72    5080  136.44  5090.1  137.12  5110.1  135.71
  5120.2  136.98  5140.2  137.32  5250.5  148.19  5310.7  152.87  5322.9  152.73
#Mann= 3 ,-1 , 0
  4082.6      .1       0  4996.8     .07       0  5002.8      .1       0
Bank Sta=4929.6,5070
XS Rating Curve= 0 ,0
Exp/Cntr=0.3,0.1

Type RM Length L Ch R = 1 ,40330   ,515,515,515
BEGIN DESCRIPTION:
Mapping XS 14f3a109
END DESCRIPTION:
XS GIS Cut Line= 3
      2282857.08     13236934.66      2283451.65      13237047.5
      2284211.23      13237004.1
#Sta/Elev= 30
  3887.8  170.75  4051.3  163.28  4061.5  163.43  4132.7  158.84    4204  156.59
  4214.2  155.48  4336.3   150.4  4358.6   150.3  4427.9  146.93  4566.6  143.68
  4609.2   143.5  4699.4  140.58  4765.9  135.06  4789.5  134.05  4859.6  133.36
  4909.7  131.48  4919.7  127.64  4938.6  122.72  4949.8  121.79  4996.9  120.83
  4999.6  120.33  5002.9  120.83  5011.5  121.48  5019.9  123.66  5029.9  129.16
  5039.9  132.96    5050  134.32    5080  134.67  5170.2  144.42  5253.8  150.88
#Mann= 5 ,-1 , 0
  3887.8      .1       0  4566.6     .16       0  4996.9     .07       0
  5002.9     .16       0  5011.5      .1       0
Bank Sta=4909.7,5039.9
XS Rating Curve= 0 ,0
Exp/Cntr=0.3,0.1

Type RM Length L Ch R = 1 ,39815   ,247,247,247
BEGIN DESCRIPTION:
Mapping XS b35ca7f7
END DESCRIPTION:
XS GIS Cut Line= 3
      2282856.99     13237333.94      2283260.68     13237503.23
      2284123.52     13237507.56
#Sta/Elev= 30
  3903.7  178.37  3951.7  176.52  4045.5  169.62  4052.2  168.35  4057.6  168.65
  4240.6  155.07  4348.5  148.86  4478.5  143.76  4690.4  139.25  4768.5   135.9
  4948.5  132.08  4955.3  130.62  4968.5  128.11  4978.5  127.45  4988.5  124.25
  4995.5  120.63  4998.2  120.13  5001.5  120.63  5058.5  121.06  5068.5  121.95
  5078.5  125.66  5088.5  127.77  5098.5  131.92  5108.5  134.22  5118.5  135.07
  5138.5  139.61  5148.5   143.4  5168.5  147.66  5188.5  149.72  5204.3  149.59
#Mann= 5 ,-1 , 0
  3903.7      .1       0  4690.4     .16       0  4955.3      .1       0
  4995.5     .07       0  5001.5      .1       0
Bank Sta=4948.5,5098.5
XS Rating Curve= 0 ,0
Exp/Cntr=0.3,0.1

Type RM Length L Ch R = 1 ,39568   ,585,585,585
BEGIN DESCRIPTION:
Mapping XS 51995a6a
END DESCRIPTION:
XS GIS Cut Line= 2
      2283030.67      13238245.4      2284103.79     13237649.23
#Sta/Elev= 30
  3984.5  206.69    4114  200.16    4290  184.57  4298.2  179.52  4303.9  181.63
  4312.9  176.89  4319.9   168.4  4325.6  168.93  4341.7  162.29  4359.7  160.73
  4363.1  160.51    4473   148.3  4541.7  143.38  4621.7  139.76  4840.4   135.3
  4878.2  133.44  4899.9  125.17  4904.3  126.68  4921.6  131.46  4965.1  132.36
  4987.8  124.67  4994.1  119.83  4996.9  119.33  5000.1  119.83  5074.1  121.67
  5084.1  122.01  5113.6  129.74  5127.6  130.95  5165.3  139.56  5212.1  146.41
#Mann= 7 ,-1 , 0
  3984.5      .1       0  4359.7     .16       0  4363.1      .1       0
  4904.3     .16       0  4994.1     .07       0  5000.1     .16       0
  5074.1      .1       0
Bank Sta=4965.1,5127.6
XS Rating Curve= 0 ,0
Exp/Cntr=0.3,0.1

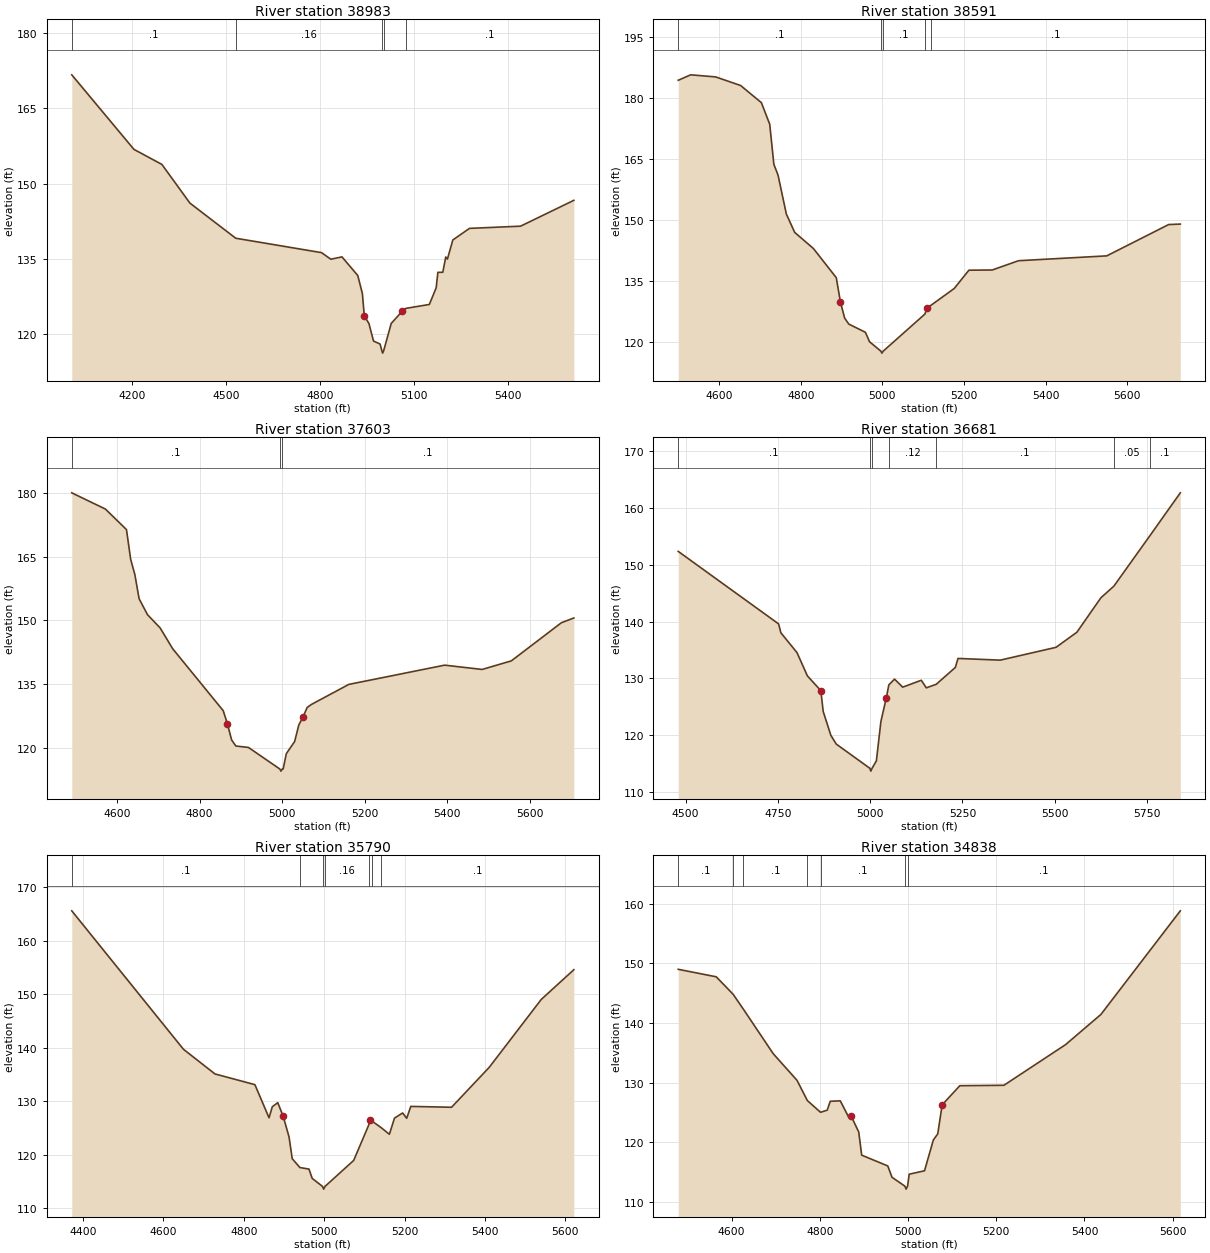
Type RM Length L Ch R = 1 ,38983   ,392,392,392
BEGIN DESCRIPTION:
Mapping XS 422b39b9
END DESCRIPTION:
XS GIS Cut Line= 4
      2283742.18     13239065.79      2284075.52     13238399.12
      2284309.89       13238071.      2284153.63     13237643.88
#Sta/Elev= 30
    4007  171.64  4205.5  156.81  4294.9  153.81  4384.3  146.12  4530.6  139.13
  4804.8  136.26  4834.3  134.95  4869.9  135.42  4920.3  131.72  4935.1  128.12
  4941.2  123.69    4956  122.16  4970.7  118.67  4991.6  118.08  4997.2  116.77
  4999.9  116.27  5003.2  116.77  5027.2  122.18  5062.9  124.64  5074.4  125.18
  5148.9  125.95  5170.7  129.26  5176.2  132.34  5191.9  132.36  5201.4   135.4
  5206.7  134.98  5223.9  138.78  5277.1  141.09  5440.3  141.53  5610.4  146.67
#Mann= 5 ,-1 , 0
    4007      .1       0  4530.6     .16       0  4997.2     .07       0
  5003.2     .16       0  5074.4      .1       0
Bank Sta=4941.2,5062.9
XS Rating Curve= 0 ,0
Exp/Cntr=0.3,0.1

Type RM Length L Ch R = 1 ,38591   ,988,988,988
BEGIN DESCRIPTION:
RAMIRENA CREEK 32.0
END DESCRIPTION:
XS GIS Cut Line= 3
      2285037.67     13238246.85      2284537.72     13238146.85
       2284137.7     13237546.82
#Sta/Elev= 30
  4499.5  184.27    4530  185.61  4591.2   185.1  4652.4  182.99  4703.4  178.77
  4723.8  173.48    4734  163.62  4744.2  160.98  4764.6  151.41    4785  146.91
  4830.9  142.95    4887  135.78  4897.2  129.81  4907.4  125.88  4917.6  124.39
  4958.4  122.37  4968.6  120.04  4996.2  117.75  4998.9  117.25  5002.2  117.75
  5104.3  126.84    5110  128.45  5119.1  128.99  5176.1  133.12  5212.2  137.62
  5269.3  137.67  5333.9  139.95  5550.2  141.14  5701.9  148.83  5730.5  148.95
#Mann= 5 ,-1 , 0
  4499.5      .1       0  4996.2     .07       0  5002.2      .1       0
  5104.3     .16       0  5119.1      .1       0
Bank Sta=4897.2,5110
XS Rating Curve= 0 ,0
Exp/Cntr=0.3,0.1

Type RM Length L Ch R = 1 ,37603   ,922,922,922
BEGIN DESCRIPTION:
RAMIRENA CREEK 31.0
END DESCRIPTION:
XS GIS Cut Line= 3
      2285387.71     13237396.85      2284887.72     13237296.85
      2284187.72     13237396.85
#Sta/Elev= 30
  4490.2     180  4571.8  176.18  4622.8  171.35    4633  164.35  4643.2  160.74
  4653.4  155.09  4673.8  151.33  4704.4  148.22  4734.9  143.31  4857.3  128.75
  4867.5  125.65  4877.7  121.86  4887.9  120.44  4918.5   120.1  4994.5  115.03
  4997.3  114.53  5000.5  115.03  5002.6  115.03  5010.2  118.63  5030.4  121.49
  5040.5  125.38  5050.6  127.23  5060.7  129.49  5070.8   130.2  5161.7  134.93
  5394.1  139.46    5485  138.45  5555.7  140.47  5676.9  149.43  5707.2  150.56
#Mann= 3 ,-1 , 0
  4490.2      .1       0  4994.5     .07       0  5000.5      .1       0
Bank Sta=4867.5,5050.6
XS Rating Curve= 0 ,0
Exp/Cntr=0.3,0.1

Type RM Length L Ch R = 1 ,36681   ,891,891,891
BEGIN DESCRIPTION:
RAMIRENA CREEK 30.0
END DESCRIPTION:
XS GIS Cut Line= 3
      2285487.69     13236846.82      2285187.72     13236446.85
      2284487.71     13235946.85
#Sta/Elev= 30
  4479.9  152.31  4751.7  139.59    4758  138.02  4801.7  134.54  4829.9  130.45
  4866.3  127.87  4872.6  124.22  4893.4  120.02    4908  118.49    4999  114.24
  5001.7  113.74    5005  114.24  5016.7  115.54    5029  122.46  5043.8  126.66
  5050.4  128.87  5065.9  129.89    5088  128.48  5138.4  129.69  5151.9  128.36
  5178.8  128.98  5230.6  131.94  5237.9  133.52  5352.2  133.22  5503.4  135.47
  5559.9  138.12    5625  144.17  5660.1  146.21  5756.7  154.97  5840.1  162.59
#Mann= 7 ,-1 , 0
  4479.9      .1       0    4999     .07       0    5005      .1       0
  5050.4     .12       0  5178.8      .1       0  5660.1     .05       0
  5756.7      .1       0
Bank Sta=4866.3,5043.8
XS Rating Curve= 0 ,0
Exp/Cntr=0.3,0.1

Type RM Length L Ch R = 1 ,35790   ,952,952,952
BEGIN DESCRIPTION:
RAMIRENA CREEK 29.0
END DESCRIPTION:
XS GIS Cut Line= 3
      2286037.73     13236046.86      2285537.72     13235646.85
      2284937.72     13235546.85
#Sta/Elev= 30
  4372.4  165.62  4650.1  139.73  4728.6  135.11  4827.8  133.11    4863  126.91
  4871.1  128.98  4884.7  129.74  4898.3  127.17  4912.7  123.34  4920.7  119.26
  4939.7  117.61  4962.3  117.32  4970.3  115.58  4996.1  114.07  4998.9  113.57
  5002.1  114.07  5073.5  118.94  5110.6   125.5  5114.1  126.43    5120  126.24
  5141.8  125.07  5162.3  123.83  5174.9  126.84  5195.2  127.82  5205.3  126.82
  5215.5  129.04  5316.9  128.88  5410.6  136.35  5539.9  149.04    5621  154.61
#Mann= 7 ,-1 , 0
  4372.4      .1       0  4939.7     .16       0  4996.1     .07       0
  5002.1     .16       0  5110.6      .1       0    5120     .16       0
  5141.8      .1       0
Bank Sta=4898.3,5114.1
XS Rating Curve= 0 ,0
Exp/Cntr=0.3,0.1

Type RM Length L Ch R = 1 ,34838   ,763,763,763
BEGIN DESCRIPTION:
RAMIRENA CREEK 28.0
END DESCRIPTION:
XS GIS Cut Line= 3
      2286287.72     13235496.86      2286087.72     13234996.85
      2286087.72     13234396.88
#Sta/Elev= 30
  4478.8  149.01    4565  147.75  4603.3  144.82  4626.4  142.33  4694.2  134.85
  4748.1  130.39  4771.6  126.99  4801.5  125.02  4816.7  125.38  4823.5  126.87
  4846.3  126.94  4865.2  124.22  4870.6  124.44  4888.1  121.71  4894.8  117.83
    4954  116.02  4963.5  114.12  4992.8  112.63  4995.5  112.13  4998.8  112.63
  5002.5  114.63  5037.3  115.21  5057.3  120.38  5067.3   121.4  5077.3  126.27
  5117.3  129.48  5217.3  129.55  5357.3  136.38  5437.3  141.44  5617.3  158.82
#Mann= 7 ,-1 , 0
  4478.8      .1       0  4603.3     .16       0  4626.4      .1       0
  4771.6     .16       0  4801.5      .1       0  4992.8     .07       0
  4998.8      .1       0
Bank Sta=4870.6,5077.3
XS Rating Curve= 0 ,0
Exp/Cntr=0.3,0.1

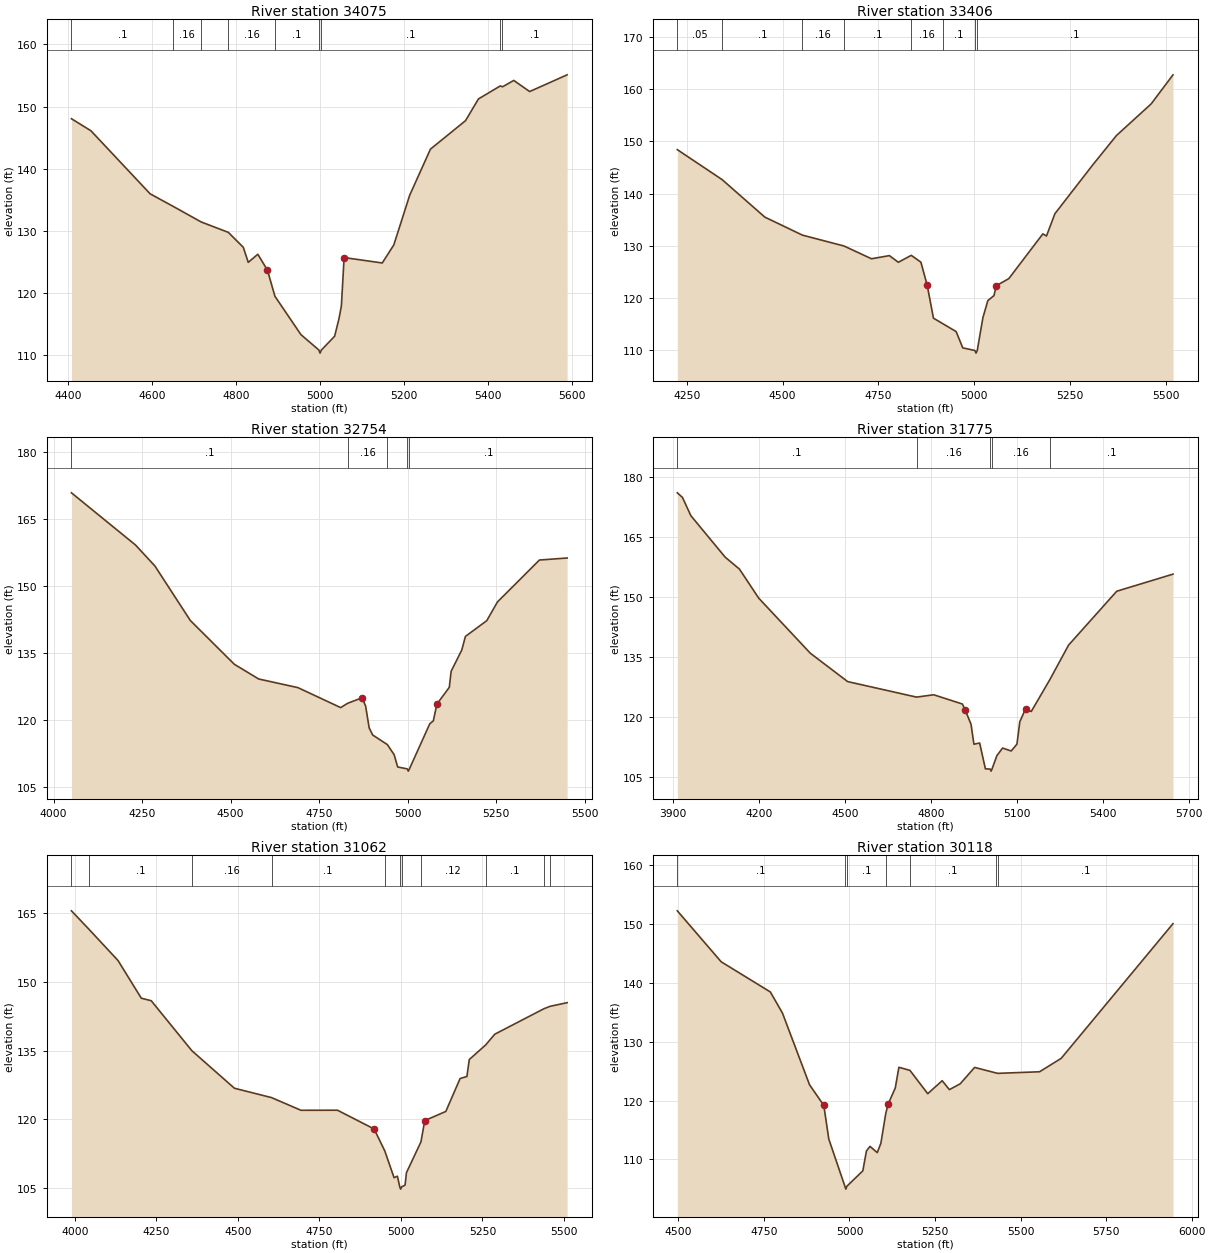
Type RM Length L Ch R = 1 ,34075   ,669,669,669
BEGIN DESCRIPTION:
RAMIRENA CREEK 27.0
END DESCRIPTION:
XS GIS Cut Line= 4
      2286489.86     13235654.26      2286641.76     13235515.38
      2286962.94     13234933.78      2286893.71      13234630.9
#Sta/Elev= 30
  4407.9  148.04  4454.2  146.11  4595.4  135.96  4650.3  133.94  4716.8  131.44
  4781.7  129.76  4817.3  127.36  4829.1  124.94  4851.9  126.24  4874.8  123.69
  4892.7  119.48  4954.7  113.31  4997.4  110.84  5000.2  110.34  5003.4  110.84
  5034.9  113.06  5045.3  115.89    5051  117.94  5057.5  125.71  5148.4  124.84
  5175.9  127.74  5213.7  135.73  5263.2  143.15  5346.8  147.73  5377.5  151.22
  5429.7  153.32  5434.8  153.17  5461.7   154.2  5499.5  152.41  5588.8   155.1
#Mann= 9 ,-1 , 0
  4407.9      .1       0  4650.3     .16       0  4716.8      .1       0
  4781.7     .16       0  4892.7      .1       0  4997.4     .07       0
  5003.4      .1       0  5429.7     .08       0  5434.8      .1       0
Bank Sta=4874.8,5057.5
XS Rating Curve= 0 ,0
Exp/Cntr=0.3,0.1

Type RM Length L Ch R = 1 ,33406   ,652,652,652
BEGIN DESCRIPTION:
Mapping XS cfc0bc34
END DESCRIPTION:
XS GIS Cut Line= 3
      2286541.93     13235940.73       2286754.6     13235897.33
      2287739.88     13235463.29
#Sta/Elev= 30
  4225.4   148.4  4342.3  142.67  4453.7   135.5  4551.9  132.05  4660.4  129.97
  4732.2  127.53  4778.8  128.13  4802.2  126.86    4836  128.18  4861.1  126.88
  4877.6  122.46  4893.9  116.17  4919.7  115.05  4953.1   113.6  4970.4  110.49
  5002.2  109.98  5004.9  109.48  5008.2  109.98    5023  116.27  5035.9  119.54
  5051.8  120.47  5057.8  122.37  5090.6  123.73  5179.4  132.29  5188.9  131.88
  5210.8  136.14  5309.1  145.43  5371.5   151.1  5462.1  157.15  5519.1  162.71
#Mann= 8 ,-1 , 0
  4225.4     .05       0  4342.3      .1       0  4551.9     .16       0
  4660.4      .1       0    4836     .16       0  4919.7      .1       0
  5002.2     .07       0  5008.2      .1       0
Bank Sta=4877.6,5057.8
XS Rating Curve= 0 ,0
Exp/Cntr=0.3,0.1

Type RM Length L Ch R = 1 ,32754   ,979,979,979
BEGIN DESCRIPTION:
RAMIRENA CREEK 26.0
END DESCRIPTION:
XS GIS Cut Line= 4
      2286521.96     13236465.03      2286839.67     13236345.24
      2287787.59     13236235.87      2287891.78     13236256.71
#Sta/Elev= 30
  4050.7  170.79  4231.5  159.13  4286.5  154.42  4386.5  142.23  4510.6  132.45
  4579.5  129.15  4690.3  127.22  4811.1  122.75  4830.8  123.71  4871.5  124.95
  4881.5  123.12  4891.6  118.21  4901.7  116.61  4942.9  114.48  4962.1  112.22
  4972.1  109.47  4999.3  109.04  5002.1  108.54  5005.3  109.04  5062.7  119.12
  5072.8  119.79  5082.9  123.53  5117.9  127.28  5123.1  130.87  5153.3  135.66
  5163.4  138.67  5223.8   142.2    5254  146.39  5372.5  155.76  5450.7  156.21
#Mann= 5 ,-1 , 0
  4050.7      .1       0  4830.8     .16       0  4942.9      .1       0
  4999.3     .07       0  5005.3      .1       0
Bank Sta=4871.5,5082.9
XS Rating Curve= 0 ,0
Exp/Cntr=0.3,0.1

Type RM Length L Ch R = 1 ,31775   ,713,713,713
BEGIN DESCRIPTION:
RAMIRENA CREEK 25.0
END DESCRIPTION:
XS GIS Cut Line= 4
       2286245.9     13237063.98      2286574.05     13237235.87
      2287725.09     13237188.99      2287881.34     13237053.58
#Sta/Elev= 30
  3914.4  176.02  3932.4  174.87  3961.6  170.32  4081.2  159.97    4131  156.99
  4198.7   149.7  4378.5  135.97  4508.7  128.89  4748.8  125.02  4808.9   125.6
    4909  123.29    4919  121.75  4939.1  118.22  4949.1  113.26  4969.1  113.56
  4989.1  107.12  5006.1  107.04  5008.9  106.54  5012.1  107.04  5029.1  110.39
  5049.1   112.3  5079.2  111.57  5099.2  113.28  5109.2  118.87  5129.2  122.08
  5149.2  121.43  5214.1   129.4  5279.3     138  5447.3  151.45  5643.6  155.72
#Mann= 5 ,-1 , 0
  3914.4      .1       0  4748.8     .16       0  5006.1     .07       0
  5012.1     .16       0  5214.1      .1       0
Bank Sta=4919,5129.2
XS Rating Curve= 0 ,0
Exp/Cntr=0.3,0.1

Type RM Length L Ch R = 1 ,31062   ,944,944,944
BEGIN DESCRIPTION:
RAMIRENA CREEK 24.0
END DESCRIPTION:
XS GIS Cut Line= 3
      2286287.73     13238096.85      2287287.72     13237896.85
      2287687.73     13237596.85
#Sta/Elev= 30
  3989.7  165.43    4044  161.37  4132.5  154.61  4203.8  146.41  4234.4  145.85
  4358.9  134.97  4489.4   126.8  4603.1  124.76  4693.4     122  4805.5  122.01
  4917.7  117.93  4950.3  113.17  4978.9  107.32  4989.1  107.65  4996.3  105.33
    4999  104.83  5002.3  105.33  5012.6   105.7  5016.8   108.4  5061.3  115.12
    5073  119.75  5137.6  121.75  5181.4  128.92  5202.2  129.35  5209.5  133.05
  5259.5  136.21  5287.6  138.56    5438   144.1  5457.4  144.64  5509.5  145.43
#Mann= 11 ,-1 , 0
  3989.7     .16       0    4044      .1       0  4358.9     .16       0
  4603.1      .1       0  4950.3     .16       0  4996.3     .07       0
  5002.3     .16       0  5061.3     .12       0  5259.5      .1       0
    5438     .12       0  5457.4      .1       0
Bank Sta=4917.7,5073
XS Rating Curve= 0 ,0
Exp/Cntr=0.3,0.1

Type RM Length L Ch R = 1 ,30118   ,931,931,931
BEGIN DESCRIPTION:
RAMIRENA CREEK 23.0
END DESCRIPTION:
XS GIS Cut Line= 3
      2287387.72     13238946.85      2287787.72     13238646.85
      2288087.73     13237746.84
#Sta/Elev= 30
  4496.8  152.29  4624.9  143.63  4768.7  138.49  4804.1   134.9  4883.3   122.7
  4924.9  119.21  4939.5  113.48  4986.5  105.46  4989.3  104.96  4992.5  105.46
    5039  108.07  5049.5  111.45    5060  112.23  5081.1  111.17  5091.7  112.75
  5105.9  117.79  5112.7  119.39  5133.8  122.16  5144.4  125.68  5176.6  125.16
  5228.7  121.19  5270.9   123.4  5291.9  121.88  5323.6  122.87  5365.7  125.66
  5429.4   124.7  5433.7  124.65  5555.5  124.92  5618.7   127.2  5945.5  150.11
#Mann= 7 ,-1 , 0
  4496.8      .1       0  4986.5     .07       0  4992.5      .1       0
  5105.9     .16       0  5176.6      .1       0  5429.4     .16       0
  5433.7      .1       0
Bank Sta=4924.9,5112.7
XS Rating Curve= 0 ,0
Exp/Cntr=0.3,0.1

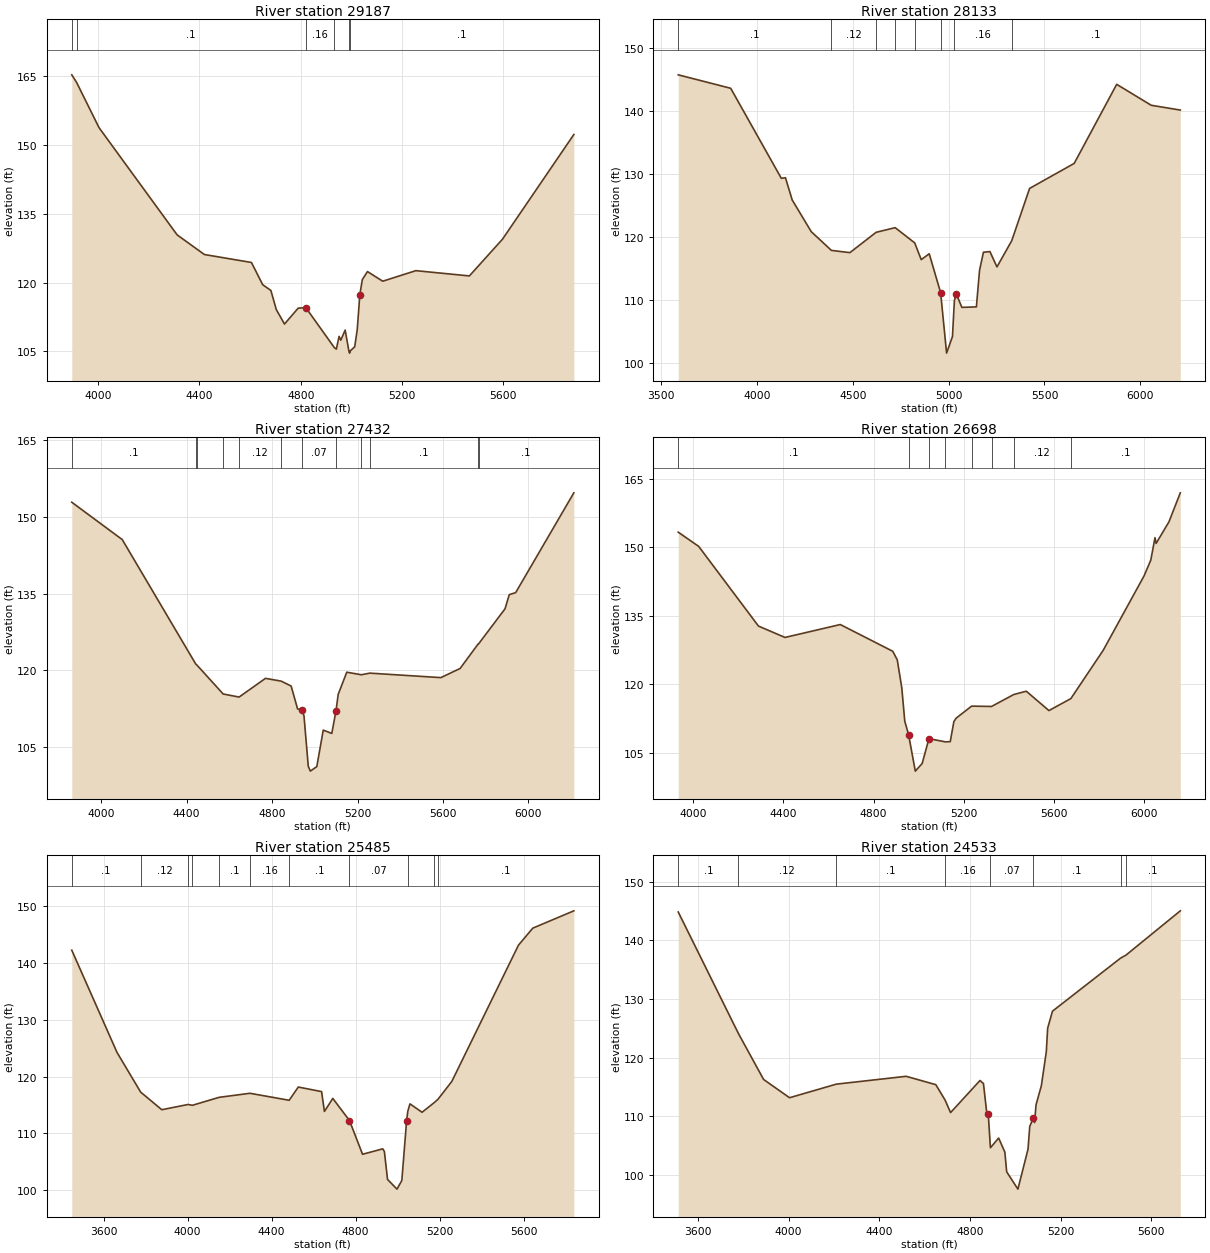
Type RM Length L Ch R = 1 ,29187   ,1054,1054,1054
BEGIN DESCRIPTION:
RAMIRENA CREEK 22.0
END DESCRIPTION:
XS GIS Cut Line= 3
      2288287.73     13239796.82      2288687.72     13238796.85
      2288787.72     13237896.89
#Sta/Elev= 30
  3895.7  165.21  3914.4   163.6  4003.4  153.71  4311.7  130.38  4419.4   126.1
  4605.2  124.37  4649.6  119.53  4681.9  118.28  4703.4  114.11  4735.7  110.97
  4789.6  114.42  4819.7  114.55  4932.1  105.87  4940.4  105.51  4951.2  108.29
  4957.9  107.45  4975.2  109.66  4989.8  105.14  4992.6  104.64  4995.8  105.14
  5012.9  106.02    5023  109.79  5033.1  117.34  5043.1  120.66  5063.3  122.39
  5123.6  120.29  5254.4  122.59  5465.7  121.44  5596.5  129.44  5878.2  152.22
#Mann= 6 ,-1 , 0
  3895.7     .05       0  3914.4      .1       0  4819.7     .16       0
  4932.1      .1       0  4989.8     .07       0  4995.8      .1       0
Bank Sta=4819.7,5033.1
XS Rating Curve= 0 ,0
Exp/Cntr=0.3,0.1

Type RM Length L Ch R = 1 ,28133   ,701,701,701
BEGIN DESCRIPTION:
RAMIRENA CREEK 21.0
END DESCRIPTION:
XS GIS Cut Line= 4
      2288986.38     13240450.64      2289513.99     13239775.68
      2289656.58     13238777.55      2289234.15     13238151.02
#Sta/Elev= 30
  3588.4  145.72  3862.3  143.58  4126.3  129.28  4148.1  129.36  4183.3  125.83
  4282.8  120.79  4387.7  117.82  4484.3  117.46  4621.2  120.69  4720.6  121.43
  4822.7  119.01  4856.7  116.35  4898.5  117.28    4958   111.1  4989.1  101.49
  5019.7  104.12  5029.8  109.82  5039.9  110.89  5068.8  108.76  5144.6  108.84
  5161.1  114.65  5181.3  117.52  5215.3  117.63    5252  115.19  5329.2  119.36
  5422.4  127.67  5655.1  131.64    5877  144.21  6057.2  140.88    6209  140.12
#Mann= 8 ,-1 , 0
  3588.4      .1       0  4387.7     .12       0  4621.2      .1       0
  4720.6     .16       0  4822.7      .1       0    4958     .07       0
  5029.8     .16       0  5329.2      .1       0
Bank Sta=4958,5039.9
XS Rating Curve= 0 ,0
Exp/Cntr=0.3,0.1

Type RM Length L Ch R = 1 ,27432   ,734,734,734
BEGIN DESCRIPTION:
RAMIRENA CREEK 20.0
END DESCRIPTION:
XS GIS Cut Line= 2
      2290184.16     13240502.85      2290293.48     13238154.89
#Sta/Elev= 30
  3862.3  152.89  4098.6  145.59  4442.4  121.28  4448.1  121.06  4571.1   115.4
  4645.6   114.8  4769.3  118.46  4843.1  117.91  4889.4  116.95  4919.4  112.49
  4939.5  112.26  4949.5  111.12  4969.5  101.27  4979.3  100.32  5009.5  101.21
  5039.6  108.34  5079.6  107.69  5099.6  112.17  5109.6  115.33  5149.7  119.66
  5218.1  119.16  5257.7  119.48  5590.2   118.6  5680.3  120.39  5765.4  125.21
  5766.9   125.2  5890.5  132.05  5910.5  134.82  5940.5  135.22  6212.8  154.73
#Mann= 12 ,-1 , 0
  3862.3      .1       0  4442.4     .16       0  4448.1     .12       0
  4571.1      .1       0  4645.6     .12       0  4843.1      .1       0
  4939.5     .07       0  5099.6      .1       0  5218.1     .16       0
  5257.7      .1       0  5765.4     .12       0  5766.9      .1       0
Bank Sta=4939.5,5099.6
XS Rating Curve= 0 ,0
Exp/Cntr=0.3,0.1

Type RM Length L Ch R = 1 ,26698   ,1213,1213,1213
BEGIN DESCRIPTION:
RAMIRENA CREEK 19.0
END DESCRIPTION:
XS GIS Cut Line= 3
      2290569.13     13240450.64      2290916.12     13239804.19
      2291063.46     13238316.56
#Sta/Elev= 30
    3933   153.3  4023.8  150.19  4289.1  132.77    4407  130.28  4652.3   133.1
  4885.1  127.26  4905.2  125.38  4925.3  119.27  4938.5  111.98  4955.4  109.04
  4985.3  101.05  5015.7  102.71  5045.9  108.15  5118.7  107.45  5140.4  107.49
  5156.4  111.86  5166.5  112.63  5235.2  115.26  5323.8  115.19  5422.8  117.81
    5478  118.52  5578.5  114.29  5675.8  116.91  5819.6  127.49  6000.5  143.72
  6030.7   147.2  6049.2   152.1  6054.2  150.84  6111.1  155.55  6161.6   161.9
#Mann= 8 ,-1 , 0
    3933      .1       0  4955.4     .07       0  5045.9      .1       0
  5118.7     .16       0  5235.2      .1       0  5323.8     .16       0
  5422.8     .12       0  5675.8      .1       0
Bank Sta=4955.4,5045.9
XS Rating Curve= 0 ,0
Exp/Cntr=0.3,0.1

Type RM Length L Ch R = 1 ,25485   ,952,952,952
BEGIN DESCRIPTION:
RAMIRENA CREEK 18.0
END DESCRIPTION:
XS GIS Cut Line= 3
      2291139.52      13240612.2      2291819.19     13240037.09
      2292465.61     13238682.46
#Sta/Elev= 30
  3448.3  142.25  3663.8  124.26  3776.4  117.28    3877  114.18  4002.4   115.1
    4023  114.96  4150.2  116.36  4297.1  117.07  4483.7  115.84  4527.2  118.17
  4638.1  117.37  4651.7  113.88  4691.5  116.17    4771  112.28  4833.2  106.34
  4929.5   107.3  4937.2  106.83  4952.2  101.92  4997.3  100.21  5020.3  101.73
    5043  112.19  5048.5  113.87  5059.1  115.21  5116.6  113.73  5172.3  115.36
  5192.2     116  5258.6  119.17  5575.9  143.13    5644  146.12  5839.6  149.17
#Mann= 11 ,-1 , 0
  3448.3      .1       0  3776.4     .12       0  4002.4      .1       0
    4023     .16       0  4150.2      .1       0  4297.1     .16       0
  4483.7      .1       0    4771     .07       0  5048.5      .1       0
  5172.3     .12       0  5192.2      .1       0
Bank Sta=4771,5043
XS Rating Curve= 0 ,0
Exp/Cntr=0.3,0.1

Type RM Length L Ch R = 1 ,24533   ,667,667,667
BEGIN DESCRIPTION:
RAMIRENA CREEK 17.0
END DESCRIPTION:
XS GIS Cut Line= 3
      2291147.28      13240786.8       2291589.6     13240704.89
        2293088.     13239771.45
#Sta/Elev= 30
  3513.4  144.87    3779   124.1  3890.1  116.25  4004.5  113.13  4210.8  115.45
    4519  116.79    4650  115.36  4690.9  112.72    4715  110.59  4844.7  116.07
  4860.1  115.56  4875.4  110.28  4881.3  110.34  4890.8  104.58  4927.1  106.24
  4954.5  103.83  4962.5  100.47  5012.1   97.51  5056.7  104.34  5064.3  108.23
  5079.6  109.61  5085.5  108.89  5092.1  111.92  5115.6  115.19  5137.4     121
  5143.3     125  5164.6  127.92  5464.8  136.98  5488.5  137.49  5728.6  145.07
#Mann= 8 ,-1 , 0
  3513.4      .1       0    3779     .12       0  4210.8      .1       0
  4690.9     .16       0  4890.8     .07       0  5079.6      .1       0
  5464.8     .16       0  5488.5      .1       0
Bank Sta=4881.3,5079.6
XS Rating Curve= 0 ,0
Exp/Cntr=0.3,0.1