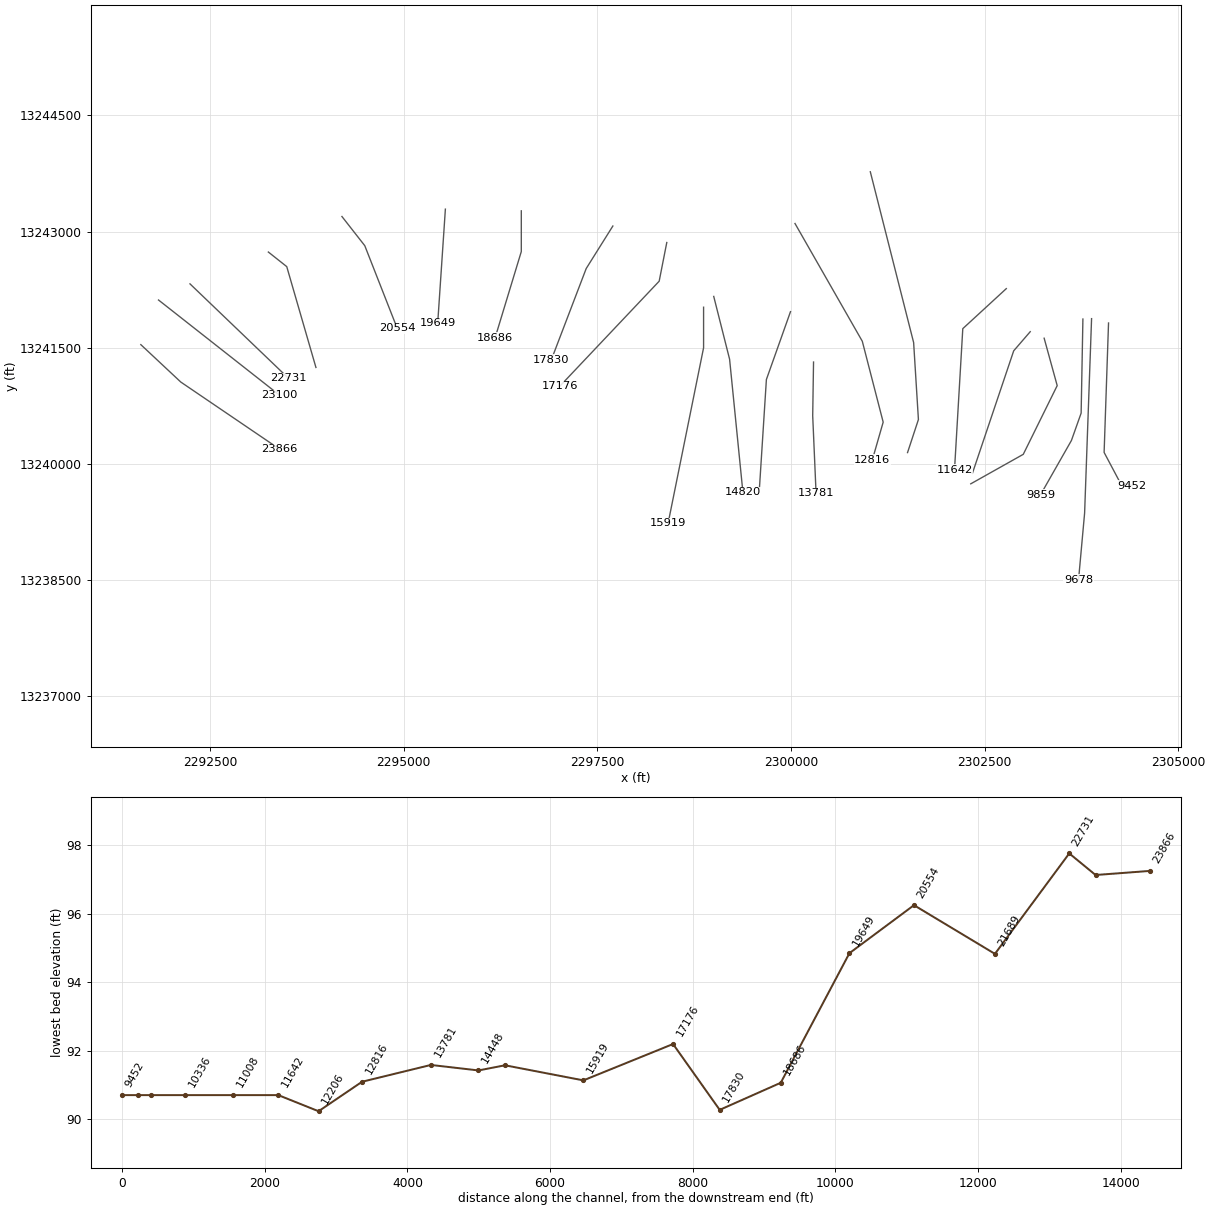
HEC-RAS study RAMIRENA CREEK.prj: RAMIRENA CREEK Base Level Engineering

--- RAMIRENA CREEK.g01 (geometry) --- (continued)

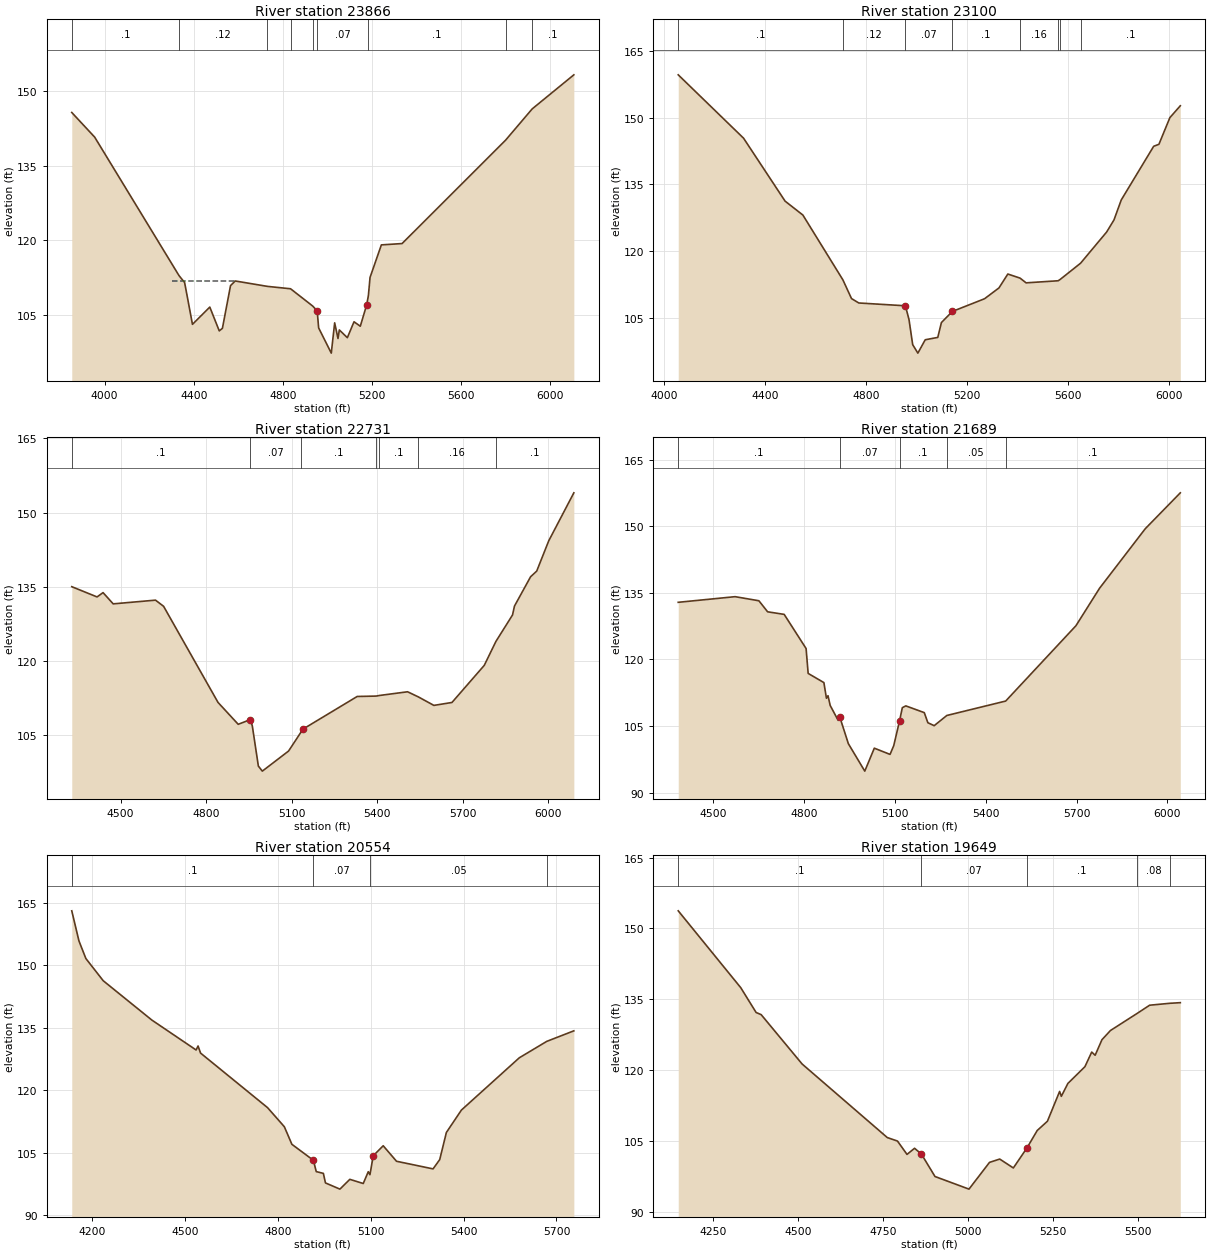
Type RM Length L Ch R = 1 ,23866   ,766,766,766
BEGIN DESCRIPTION:
Mapping XS 7238af6f
END DESCRIPTION:
XS GIS Cut Line= 3
      2291605.97     13241540.42      2292122.04     13241057.12
      2293399.91     13240188.82
#Sta/Elev= 30
  3853.1  145.74  3955.8  140.78  4334.3  112.86  4359.3  111.47  4394.5  103.05
  4472.2  106.53  4514.7  101.73  4528.8  102.25  4565.2  110.85  4586.2  111.79
  4730.5   110.7  4834.4  110.22  4933.7  106.74  4953.9  105.78  4960.4  102.34
  5017.1   97.25  5032.3  103.35  5047.2   100.2  5053.3  101.92  5089.2  100.36
  5119.1  103.57  5147.3  102.67    5176     107  5183.6  108.86    5191  112.51
  5241.8  119.06  5334.7  119.33  5798.9  140.16  5918.4  146.47  6105.1  153.33
#Mann= 9 ,-1 , 0
  3853.1      .1       0  4334.3     .12       0  4730.5     .16       0
  4834.4     .12       0  4933.7     .16       0  4953.9     .07       0
  5183.6      .1       0  5798.9     .16       0  5918.4      .1       0
#XS Ineff= 1 ,-1
 4302.39 4586.91  111.82
Permanent Ineff=
       F
Bank Sta=4953.9,5176
XS Rating Curve= 0 ,0
Exp/Cntr=0.3,0.1

Type RM Length L Ch R = 1 ,23100   ,369,369,369
BEGIN DESCRIPTION:
Mapping XS 9fb0bf8a
END DESCRIPTION:
XS GIS Cut Line= 2
      2291834.43      13242116.8      2293396.91     13240887.65
#Sta/Elev= 30
  4055.8  159.62  4314.5  145.39  4478.9  131.26  4549.4  128.13  4707.8  113.58
  4741.9  109.38  4770.8  108.39  4955.2  107.76  4969.6  104.66  4984.1   99.04
  5004.6   97.13  5033.8  100.13  5083.5  100.66  5097.9     104  5141.3  106.49
  5268.7  109.34  5325.7  111.77  5360.9  114.89  5409.4  113.97  5433.2  112.91
  5560.3  113.38    5568  113.67  5648.9  117.32  5752.2  124.33  5781.1  127.03
    5810  131.53  5938.3  143.57  5959.1  144.02  6002.5  150.01  6043.8  152.67
#Mann= 8 ,-1 , 0
  4055.8      .1       0  4707.8     .12       0  4955.2     .07       0
  5141.3      .1       0  5409.4     .16       0  5560.3      .1       0
    5568     .16       0  5648.9      .1       0
Bank Sta=4955.2,5141.3
XS Rating Curve= 0 ,0
Exp/Cntr=0.3,0.1

Type RM Length L Ch R = 1 ,22731   ,1042,1042,1042
BEGIN DESCRIPTION:
Mapping XS de6fdc89
END DESCRIPTION:
XS GIS Cut Line= 2
       2292240.7     13242325.12      2293511.54     13241106.36
#Sta/Elev= 30
  4328.5  135.02  4417.2  132.95  4438.2  133.82  4473.8  131.55  4622.2   132.3
  4650.5  131.06  4841.4  111.64  4912.2  107.22  4954.6  108.16  4961.7  106.89
  4982.9   98.78  4996.8   97.76  5088.9  101.82  5131.4  105.55  5138.6  106.22
  5329.5  112.84  5395.9  112.92  5407.4  113.04  5506.2  113.79  5543.8  112.76
  5598.4  111.04  5661.9  111.63  5775.1  119.12    5816  123.96  5874.2   129.3
  5881.1   131.1  5937.7  137.03  5959.1  138.17  6001.2  144.28  6089.3  153.98
#Mann= 7 ,-1 , 0
  4328.5      .1       0  4954.6     .07       0  5131.4      .1       0
  5395.9     .16       0  5407.4      .1       0  5543.8     .16       0
    5816      .1       0
Bank Sta=4954.6,5138.6
XS Rating Curve= 0 ,0
Exp/Cntr=0.3,0.1

Type RM Length L Ch R = 1 ,21689   ,1135,1135,1135
BEGIN DESCRIPTION:
RAMIRENA CREEK 14.0
END DESCRIPTION:
XS GIS Cut Line= 3
      2293252.46     13242736.36      2293490.01     13242547.96
      2293866.81     13241245.56
#Sta/Elev= 30
  4383.6  132.87  4571.6  134.14  4650.1  133.22    4679  130.73  4733.7  130.15
  4806.1  122.45  4812.9  116.85  4864.9  114.78  4873.3  111.25  4878.5  111.82
  4885.7  109.63  4912.1  106.26  4917.3  107.05  4945.7  101.02    5000   94.83
  5031.5     100  5083.5    98.6  5095.7  100.57  5114.8  106.13  5124.1  109.13
  5135.6  109.53  5196.6  108.01  5208.4  105.74  5229.3  105.07  5271.1  107.37
  5465.6  110.62  5697.7  127.59  5775.9  136.05  5926.7  149.44  6042.6  157.54
#Mann= 5 ,-1 , 0
  4383.6      .1       0  4917.3     .07       0  5114.8      .1       0
  5271.1     .05       0  5465.6      .1       0
Bank Sta=4917.3,5114.8
XS Rating Curve= 0 ,0
Exp/Cntr=0.3,0.1

Type RM Length L Ch R = 1 ,20554   ,905,905,905
BEGIN DESCRIPTION:
RAMIRENA CREEK 13.0
END DESCRIPTION:
XS GIS Cut Line= 3
      2294202.65      13243195.1      2294497.56     13242818.28
      2294915.32     13241753.39
#Sta/Elev= 30
  4133.7  163.06  4156.9  155.84  4179.2  151.62  4235.3  146.28  4392.6  136.83
  4535.5  129.65  4541.8  130.61  4549.9  128.91  4766.4  115.81  4820.6  111.23
    4845  107.01  4914.5  103.17  4923.7  100.46  4946.7  100.03  4953.5   97.74
  5000.2   96.25  5032.2    98.6  5075.6    97.6  5091.8  100.43  5097.2   99.71
  5107.9  104.26  5140.1  106.66  5183.1  102.94  5301.2  101.11  5322.7  103.34
  5344.2  109.85  5392.8  115.23  5579.9  127.78  5668.6  131.72  5756.1  134.25
#Mann= 4 ,-1 , 0
  4133.7      .1       0  4914.5     .07       0  5097.2     .05       0
  5668.6      .1       0
Bank Sta=4914.5,5107.9
XS Rating Curve= 0 ,0
Exp/Cntr=0.3,0.1

Type RM Length L Ch R = 1 ,19649   ,963,963,963
BEGIN DESCRIPTION:
RAMIRENA CREEK 12.0
END DESCRIPTION:
XS GIS Cut Line= 2
      2295538.11     13243290.34      2295438.93     13241816.88
#Sta/Elev= 30
  4148.1  153.73    4332  137.47  4377.2  132.22  4392.1  131.76  4512.4  121.33
    4763  105.76    4793  105.02    4821   102.2  4843.2  103.49  4863.2  102.29
  4903.3   97.52  5003.3   94.85  5063.7  100.51  5093.7  101.21  5133.8   99.33
  5173.9  103.57    5204  107.25    5234  109.21  5269.9  115.52  5274.9  114.48
  5294.2  117.21  5344.3  120.75  5364.3  123.85  5374.4  123.17  5394.4  126.46
  5419.5  128.41  5497.8  132.02  5534.7  133.76  5594.7  134.17  5624.9   134.3
#Mann= 5 ,-1 , 0
  4148.1      .1       0  4863.2     .07       0  5173.9      .1       0
  5497.8     .08       0  5594.7      .1       0
Bank Sta=4863.2,5173.9
XS Rating Curve= 0 ,0
Exp/Cntr=0.3,0.1

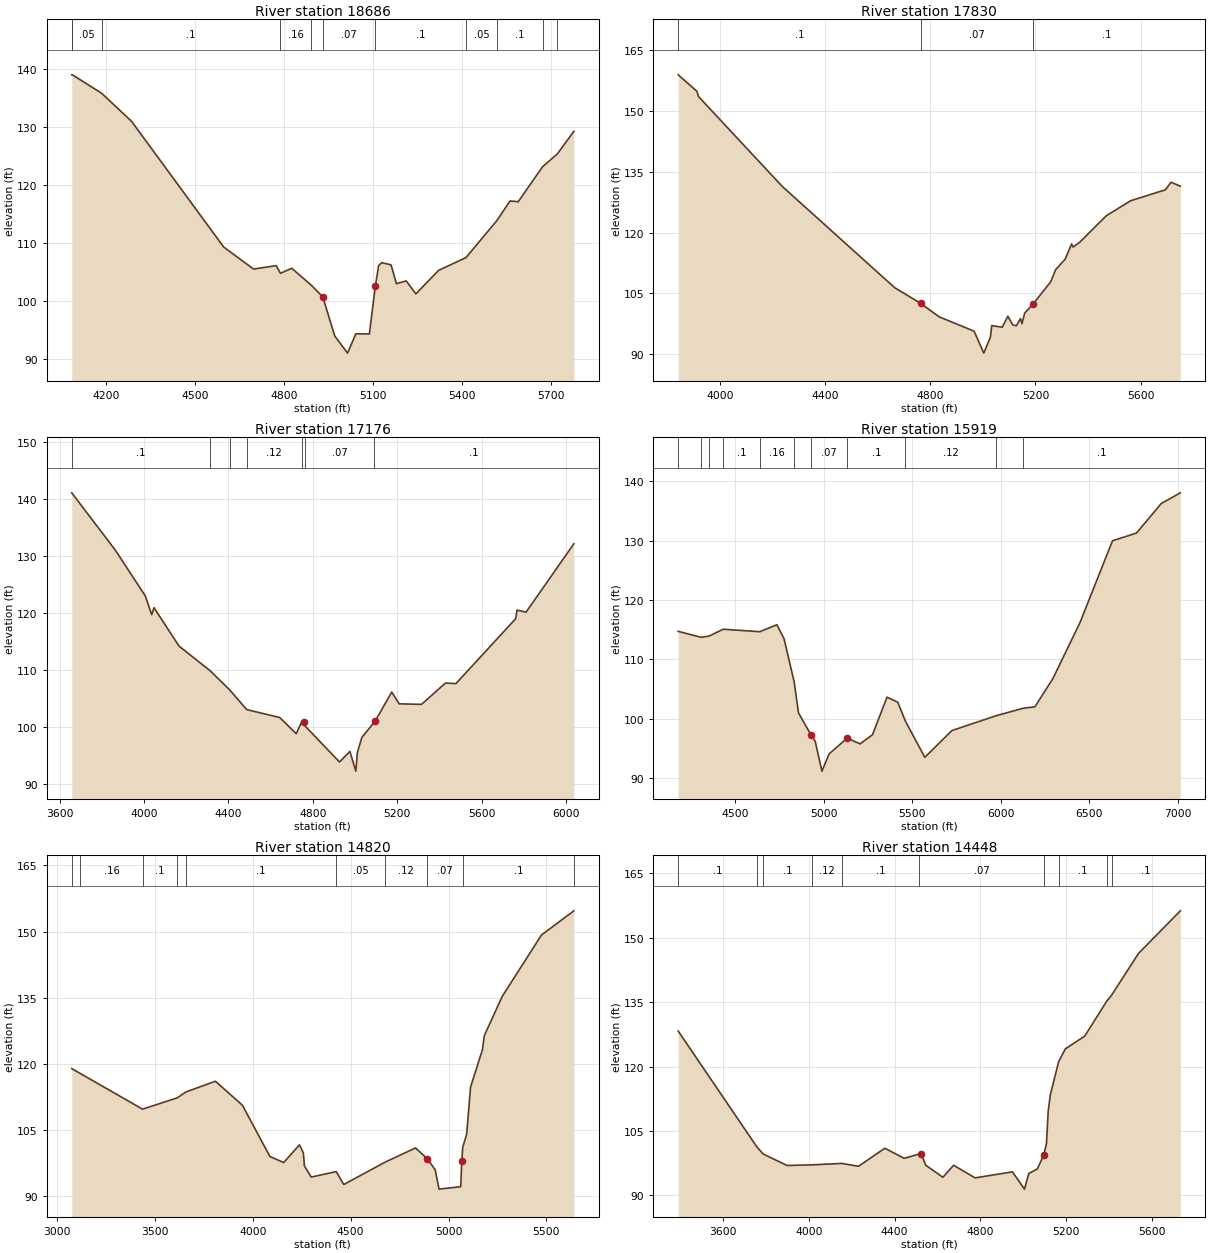
Type RM Length L Ch R = 1 ,18686   ,856,856,856
BEGIN DESCRIPTION:
RAMIRENA CREEK 11.0
END DESCRIPTION:
XS GIS Cut Line= 3
      2296518.35     13243268.46      2296518.35     13242742.46
       2296179.8     13241627.84
#Sta/Elev= 30
  4085.2  138.93  4087.3  138.93  4186.1  135.75  4286.8  130.92  4596.8  109.32
  4697.4  105.53  4773.8  106.12  4787.9   104.8  4826.1  105.66  4892.1  102.74
  4930.6  100.74  4970.9   94.01    5014   91.07  5041.9   94.39  5087.4   94.37
  5107.7  102.62  5118.7  106.14  5129.2  106.63  5160.5  106.25  5178.6  103.01
  5211.5  103.49  5244.1  101.26  5320.6   105.3    5413  107.51  5517.2  113.88
  5561.2  117.24  5588.9  117.11  5670.6  123.12  5720.5  125.33  5776.1  129.21
#Mann= 11 ,-1 , 0
  4085.2      .1       0  4087.3     .05       0  4186.1      .1       0
  4787.9     .16       0  4892.1      .1       0  4930.6     .07       0
  5107.7      .1       0    5413     .05       0  5517.2      .1       0
  5670.6     .08       0  5720.5      .1       0
Bank Sta=4930.6,5107.7
XS Rating Curve= 0 ,0
Exp/Cntr=0.3,0.1

Type RM Length L Ch R = 1 ,17830   ,654,654,654
BEGIN DESCRIPTION:
RAMIRENA CREEK 10.0
END DESCRIPTION:
XS GIS Cut Line= 3
      2297700.42     13243072.23      2297356.37     13242523.39
      2296905.86     13241343.86
#Sta/Elev= 30
  3840.8  158.94  3911.9  154.88    3918  153.58  4237.2  131.37  4664.2  106.44
  4763.2  102.56  4833.9   99.22  4966.6    95.7  5003.4   90.28  5028.4    94.2
  5033.7   97.06  5073.6   96.68    5095   99.38  5113.2    97.3  5127.1   97.02
  5143.3    98.8  5148.6   97.54  5159.2  100.17  5191.4  102.42  5258.2   107.9
    5277  110.88    5313  113.47  5337.7  117.23  5343.1  116.45  5367.8   117.6
  5469.7  124.18  5562.2  127.87  5694.5  130.58  5715.9  132.44  5751.2  131.47
#Mann= 3 , 0 , 0
  3840.8      .1       0  4763.2     .07       0  5191.4      .1       0
Bank Sta=4763.2,5191.4
XS Rating Curve= 0 ,0
Exp/Cntr=0.3,0.1

Type RM Length L Ch R = 1 ,17176   ,1257,1257,1257
BEGIN DESCRIPTION:
RAMIRENA CREEK 9.0
END DESCRIPTION:
XS GIS Cut Line= 3
      2298396.68     13242859.22      2298298.38     13242359.56
      2297013.53     13241001.05
#Sta/Elev= 30
  3657.5  141.09  3863.7  131.03  4006.4  122.95  4036.3  119.69  4047.2  120.91
  4165.6  114.17  4313.7  109.82  4405.7  106.48  4486.4  103.01    4643  101.62
    4721   98.78  4747.4  100.89  4756.3  100.77  4763.1  100.12  4926.2   93.81
  4975.5   95.66  5003.6    92.2  5010.7   95.45  5032.2   98.13  5088.8   100.7
  5095.7  101.03  5173.7  106.09  5208.9  104.02  5314.9  103.93  5428.2  107.67
    5478  107.58  5760.7  118.97  5767.6  120.49  5810.1  120.12  6036.6  132.14
#Mann= 7 ,-1 , 0
  3657.5      .1       0  4313.7     .12       0  4405.7      .1       0
  4486.4     .12       0  4747.4      .1       0  4763.1     .07       0
  5088.8      .1       0
Bank Sta=4756.3,5095.7
XS Rating Curve= 0 ,0
Exp/Cntr=0.3,0.1

Type RM Length L Ch R = 1 ,15919   ,1099,1099,1099
BEGIN DESCRIPTION:
RAMIRENA CREEK 8.0
END DESCRIPTION:
XS GIS Cut Line= 3
      2298871.78     13242023.75      2298871.78     13241499.46
      2298413.21     13239231.14
#Sta/Elev= 30
  4176.7   114.7  4306.1   113.7    4352  113.91    4431  115.06  4637.3  114.64
  4734.3  115.81  4775.1  113.43  4832.3  106.16  4856.7  100.95  4928.1    97.2
  4951.1   96.17  4989.1   91.14  5030.1   94.06  5132.1   96.71  5204.8   95.73
    5275   97.27    5357  103.61  5417.8  102.76  5461.4   99.54  5570.8   93.47
  5723.9   97.98    5975  100.49  6128.4  101.75  6193.2  101.98  6295.2  106.76
  6448.2  116.19  6631.9  129.97  6767.5  131.27  6907.3  136.24  7015.2  138.05
#Mann= 11 ,-1 , 0
  4176.7     .16       0  4306.1      .1       0    4352     .16       0
    4431      .1       0  4637.3     .16       0  4832.3      .1       0
  4928.1     .07       0  5132.1      .1       0  5461.4     .12       0
    5975     .05       0  6128.4      .1       0
Bank Sta=4928.1,5132.1
XS Rating Curve= 0 ,0
Exp/Cntr=0.3,0.1

Type RM Length L Ch R = 1 ,14820   ,372,372,372
BEGIN DESCRIPTION:
RAMIRENA CREEK 7.0
END DESCRIPTION:
XS GIS Cut Line= 3
      2299002.85     13242162.93      2299207.63     13241352.01
      2299379.65     13239631.87
#Sta/Elev= 30
  3075.1  118.92  3118.3  117.82  3436.8  109.72    3615   112.3  3657.5  113.61
  3809.1  116.05  3946.8  110.62  4087.5   98.98  4157.9   97.61  4238.3  101.63
  4258.4   99.77  4263.7   96.85  4298.6   94.31  4426.2   95.56  4464.7   92.63
  4676.9   97.72  4831.2  100.92  4891.5   98.49  4931.7   95.97  4951.5   91.58
  5062.3   92.14  5067.7   97.99  5072.8  101.14  5092.5     104  5112.6  114.74
  5173.3  123.22  5182.9   126.4  5273.8  135.26  5474.8  149.22  5640.2  154.71
#Mann= 10 ,-1 , 0
  3075.1      .1       0  3118.3     .16       0  3436.8      .1       0
    3615     .16       0  3657.5      .1       0  4426.2     .05       0
  4676.9     .12       0  4891.5     .07       0  5072.8      .1       0
  5640.2      .1       0
Bank Sta=4891.5,5067.7
XS Rating Curve= 0 ,0
Exp/Cntr=0.3,0.1

Type RM Length L Ch R = 1 ,14448   ,667,667,667
BEGIN DESCRIPTION:
RAMIRENA CREEK 6.0
END DESCRIPTION:
XS GIS Cut Line= 3
        2299994.     13241966.33      2299682.74     13241089.88
      2299592.71     13239682.13
#Sta/Elev= 30
  3391.4  128.25  3756.5  101.38  3787.2   99.62    3899   96.94  4015.7   97.09
    4154   97.42  4231.9   96.75  4354.6  100.96  4444.8    98.6  4514.9   99.61
  4524.9   99.58    4545   97.02  4625.1   94.19  4675.2   96.99  4775.4   94.05
  4949.6   95.46  5005.6   91.43  5025.9   95.07    5066   96.15  5096.1   99.49
  5108.1  102.04  5116.1  109.52  5126.1  113.38    5165  121.15  5196.3  124.13
  5286.5  127.08  5389.6  135.27  5411.4  136.59    5537  146.34  5732.1  156.28
#Mann= 10 ,-1 , 0
  3391.4      .1       0  3756.5     .12       0  3787.2      .1       0
  4015.7     .12       0    4154      .1       0  4514.9     .07       0
  5096.1     .12       0    5165      .1       0  5389.6     .05       0
  5411.4      .1       0
Bank Sta=4524.9,5096.1
XS Rating Curve= 0 ,0
Exp/Cntr=0.3,0.1

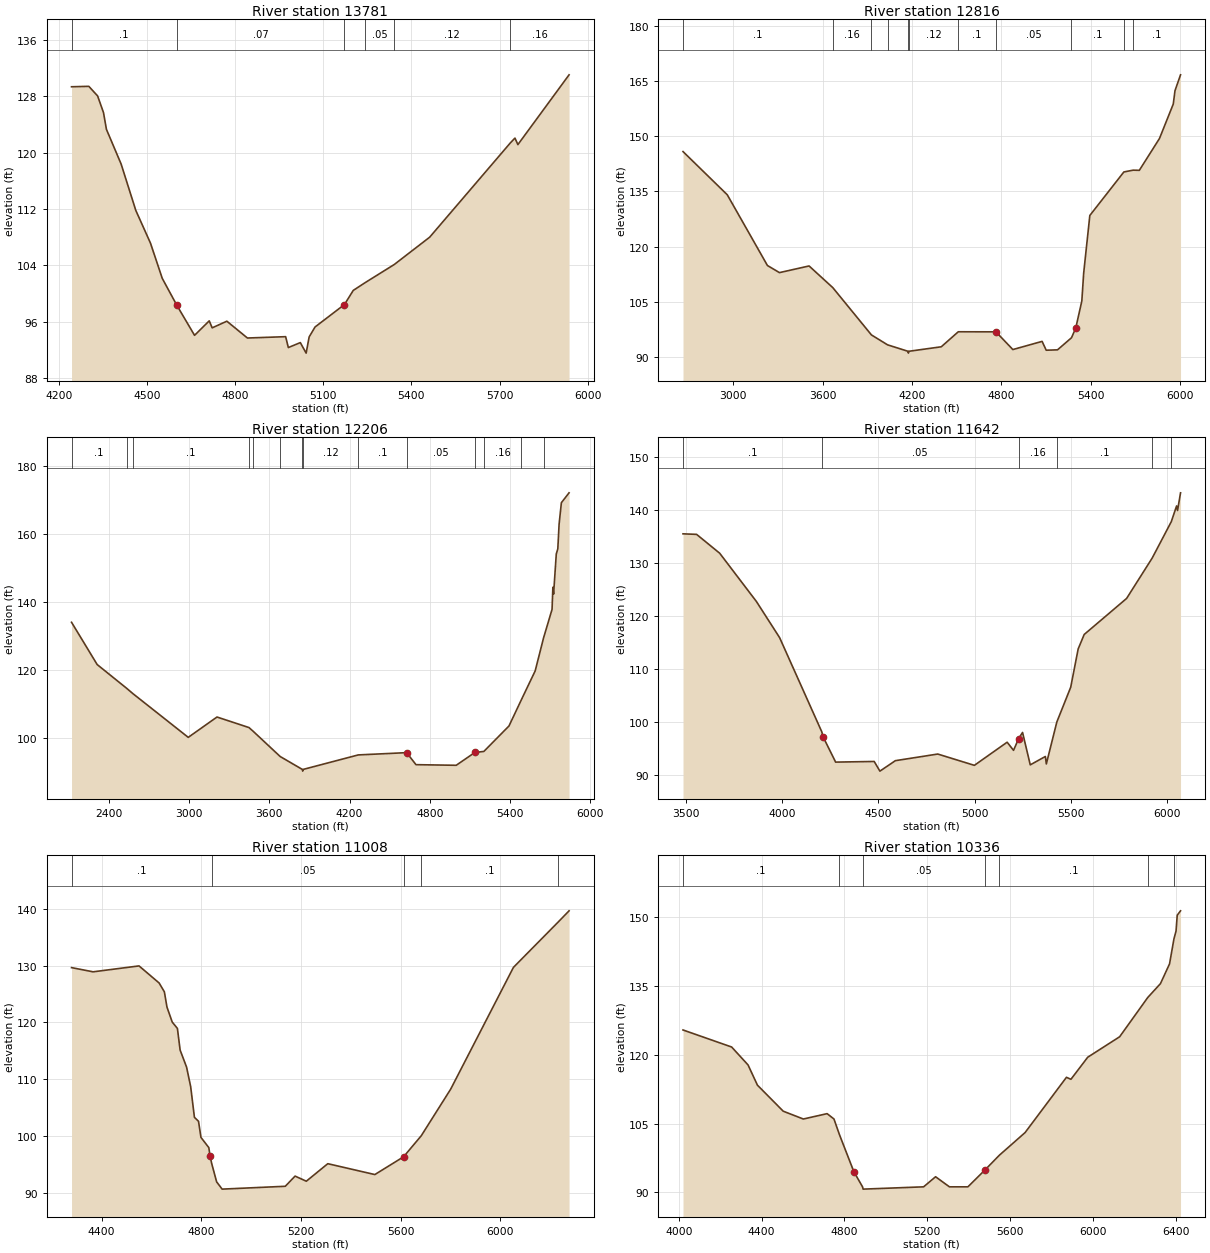
Type RM Length L Ch R = 1 ,13781   ,965,965,965
BEGIN DESCRIPTION:
Mapping XS 521ec740
END DESCRIPTION:
XS GIS Cut Line= 3
      2300291.49     13241315.61      2300280.64     13240621.15
      2300324.05     13239622.83
#Sta/Elev= 30
  4242.9  129.31  4301.7  129.37  4331.7  128.01  4351.7  125.65  4361.7  123.28
  4411.7  118.37  4461.7   111.8  4511.7  107.16  4551.7  102.18  4601.7   98.34
  4661.7   94.11  4711.7   96.16  4721.7   95.17  4771.7   96.11  4841.7   93.73
  4971.8   93.92    4981   92.38  5021.8   93.08  5041.6   91.59  5051.8   93.88
  5071.9   95.29    5172   98.47    5202  100.47  5242.8  101.58  5341.6  104.14
  5462.2  108.01  5736.6  121.35  5752.5  122.04  5762.5  121.12  5936.7     131
#Mann= 6 ,-1 , 0
  4242.9      .1       0  4601.7     .07       0    5172     .12       0
  5242.8     .05       0  5341.6     .12       0  5736.6     .16       0
Bank Sta=4601.7,5172
XS Rating Curve= 0 ,0
Exp/Cntr=0.3,0.1

Type RM Length L Ch R = 1 ,12816   ,610,610,610
BEGIN DESCRIPTION:
RAMIRENA CREEK 5.0
END DESCRIPTION:
XS GIS Cut Line= 4
      2300052.23     13243104.66      2300920.95     13241584.01
      2301190.57     13240539.22      2301050.33     13240051.19
#Sta/Elev= 30
  2663.5  145.83  2960.4   134.1    3230  114.89  3310.6  112.96  3509.3  114.77
  3668.3  108.89  3927.8   96.04    4036   93.35  4172.9    91.6  4175.7    91.1
  4178.9    91.6  4396.2   92.82  4510.5    96.9    4763   96.88  4876.6   92.07
  5072.8   94.29  5100.4   91.89  5176.1   91.99  5269.9   95.27  5298.6    97.9
  5339.3  105.26  5351.7  112.82    5393  128.48  5621.3  140.29  5682.9  140.78
  5725.2  140.74  5860.4  149.39  5952.8  158.73  5964.5  162.38  6001.6  166.67
#Mann= 11 ,-1 , 0
  2663.5      .1       0  3668.3     .16       0  3927.8      .1       0
    4036     .12       0  4172.9     .07       0  4178.9     .12       0
  4510.5      .1       0    4763     .05       0  5269.9      .1       0
  5621.3     .16       0  5682.9      .1       0
Bank Sta=4763,5298.6
XS Rating Curve= 0 ,0
Exp/Cntr=0.3,0.1

Type RM Length L Ch R = 1 ,12206   ,564,564,564
BEGIN DESCRIPTION:
RAMIRENA CREEK 4.0
END DESCRIPTION:
XS GIS Cut Line= 4
      2301024.47     13243773.01      2301583.77     13241567.16
      2301645.56     13240572.93      2301505.13     13240146.03
#Sta/Elev= 30
  2120.7  134.06  2312.3  121.62  2533.6   114.6  2580.8  113.02  2993.6  100.18
  3208.6  106.17  3447.5  103.07    3477  102.05  3681.3   94.54  3846.9   90.74
  3849.6   90.24  3852.9   90.74  4265.1   95.01  4627.1   95.68    4697   92.14
  4997.8   91.96  5138.1   95.75  5204.4   96.03  5392.5  103.53  5483.6  111.12
  5588.4  119.74  5651.1  129.45  5714.7  137.87  5720.8  144.37  5726.1  142.35
  5746.3  154.17  5757.8   155.7  5767.3   162.9  5784.4  169.26  5841.9  172.17
#Mann= 14 ,-1 , 0
  2120.7      .1       0  2533.6     .16       0  2580.8      .1       0
  3447.5     .12       0    3477      .1       0  3681.3     .12       0
  3846.9     .07       0  3852.9     .12       0  4265.1      .1       0
  4627.1     .05       0  5138.1     .12       0  5204.4     .16       0
  5483.6     .05       0  5651.1      .1       0
Bank Sta=4627.1,5138.1
XS Rating Curve= 0 ,0
Exp/Cntr=0.3,0.1

Type RM Length L Ch R = 1 ,11642   ,634,634,634
BEGIN DESCRIPTION:
Mapping XS 94a14cb2
END DESCRIPTION:
XS GIS Cut Line= 3
      2302780.26     13242263.72      2302218.51     13241746.91
      2302111.78     13239926.95
#Sta/Elev= 30
  3484.1  135.44  3554.7  135.34  3674.9  131.78    3866  122.67  3986.3  115.87
  4205.8    98.1  4212.5   97.16  4277.5   92.41  4477.9   92.53  4507.7   90.71
  4588.1   92.68  4808.4   93.93  4998.8    91.8  5169.1   96.16  5202.3   94.63
  5229.2   96.86  5249.2      98  5289.3   91.89  5367.8   93.47  5372.8   92.06
  5427.6   99.99  5499.6  106.53  5538.4  113.75  5569.7  116.47  5790.1  123.26
  5923.3  130.88  6022.4  137.73    6050   140.7    6055  139.84  6070.5  143.17
#Mann= 6 ,-1 , 0
  3484.1      .1       0  4205.8     .05       0  5229.2     .16       0
  5427.6      .1       0  5923.3     .05       0  6022.4      .1       0
Bank Sta=4212.5,5229.2
XS Rating Curve= 0 ,0
Exp/Cntr=0.3,0.1

Type RM Length L Ch R = 1 ,11008   ,672,672,672
BEGIN DESCRIPTION:
RAMIRENA CREEK 3.0
END DESCRIPTION:
XS GIS Cut Line= 3
      2303089.18      13241707.6      2302875.72     13241460.44
       2302342.4     13239877.34
#Sta/Elev= 30
    4279  129.64  4365.6   128.9  4549.9  129.94  4630.5  126.94  4651.6  125.39
  4662.1   122.7  4683.2  120.07    4704  118.95  4714.9  115.14  4740.8  112.15
  4757.1  108.75  4772.3  103.33  4788.7  102.63  4798.5    99.8    4830   98.01
  4835.2   96.51  4841.5   95.23  4861.4   91.99  4883.5   90.71    5137   91.21
  5176.3      93  5221.4    92.1  5307.6   95.18  5496.5   93.27  5611.8   96.39
  5682.8  100.09  5800.9  108.28  6052.8  129.68  6233.1  137.68  6276.1  139.62
#Mann= 5 ,-1 , 0
    4279      .1       0  4841.5     .05       0  5611.8     .12       0
  5682.8      .1       0  6233.1     .05       0
Bank Sta=4835.2,5611.8
XS Rating Curve= 0 ,0
Exp/Cntr=0.3,0.1

Type RM Length L Ch R = 1 ,10336   ,477,477,477
BEGIN DESCRIPTION:
RAMIRENA CREEK 2.0
END DESCRIPTION:
XS GIS Cut Line= 4
      2303268.93      13241623.3      2303437.43     13241011.06
       2302999.3     13240123.55      2302321.39     13239742.58
#Sta/Elev= 30
  4020.4  125.44  4255.3  121.72  4334.6   117.8  4379.7   113.4  4504.2  107.72
  4601.3  106.01  4716.3  107.18  4749.3  106.01  4775.3  102.66  4845.4   94.51
  4887.3   91.21  4890.1   90.71  5182.2   91.21    5240   93.41  5306.9   91.21
  5396.1   91.21  5479.5   94.94  5547.8    98.1  5672.4  103.06  5871.9  115.11
  5893.6  114.68  5974.6  119.49  6128.8  123.96  6264.6  132.53  6325.9  135.56
  6369.7  139.86  6390.9   145.3  6401.1  147.03  6406.8  150.48  6422.8  151.44
#Mann= 7 ,-1 , 0
  4020.4      .1       0  4775.3     .12       0  4887.3     .05       0
  5479.5     .12       0  5547.8      .1       0  6264.6     .05       0
  6390.9      .1       0
Bank Sta=4845.4,5479.5
XS Rating Curve= 0 ,0
Exp/Cntr=0.3,0.1

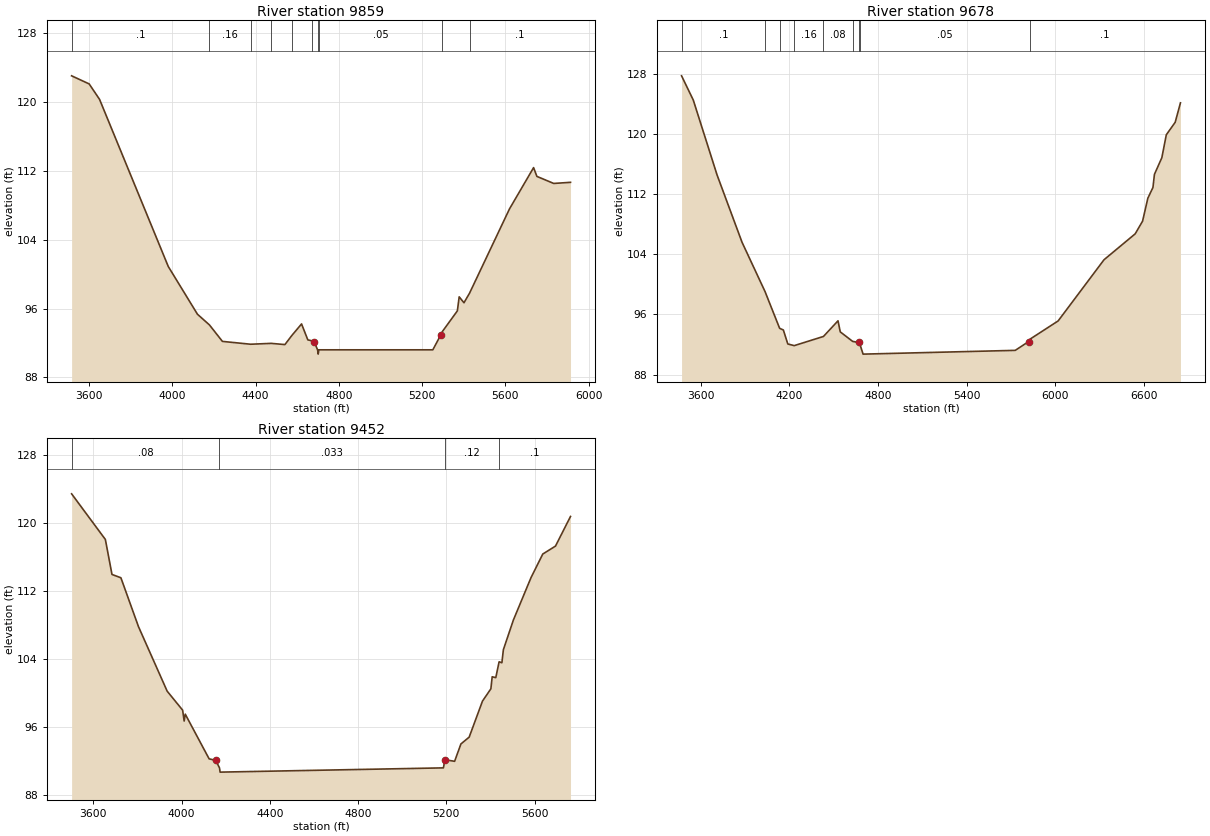
Type RM Length L Ch R = 1 ,9859    ,181,181,181
BEGIN DESCRIPTION:
Mapping XS 1144e551
END DESCRIPTION:
XS GIS Cut Line= 4
      2303769.27     13241871.16      2303746.45     13240655.86
      2303620.93     13240302.12      2303222.54      13239602.1
#Sta/Elev= 30
  3516.4  123.06  3600.7  122.12  3650.7  120.32  3980.8  100.89  4120.8   95.35
  4178.6    94.1  4240.8   92.19  4376.3   91.86  4475.1   91.96  4540.9   91.82
    4574   92.87  4620.9   94.22  4650.9   92.37  4672.9   92.24  4680.9   92.17
  4697.9   91.21  4700.7   90.71  4703.9   91.21  5251.4   91.21  5288.6    92.9
  5297.4   93.34  5369.3   95.74    5378   97.37    5401   96.68  5427.9    97.8
  5619.6  107.59  5735.4  112.39  5751.2  111.37    5832  110.55  5912.7  110.68
#Mann= 10 ,-1 , 0
  3516.4      .1       0  4178.6     .16       0  4376.3     .12       0
  4475.1     .16       0    4574     .12       0  4672.9     .05       0
  4697.9     .07       0  4703.9     .05       0  5297.4     .16       0
  5427.9      .1       0
Bank Sta=4680.9,5288.6
XS Rating Curve= 0 ,0
Exp/Cntr=0.3,0.1

Type RM Length L Ch R = 1 ,9678    ,226,226,226
BEGIN DESCRIPTION:
Mapping XS 31b6192d
END DESCRIPTION:
XS GIS Cut Line= 3
      2303881.19     13241876.06      2303791.32     13239365.24
      2303712.77     13238501.23
#Sta/Elev= 30
  3469.1  127.71  3548.4  124.49  3709.6  114.53  3878.6  105.59  4034.5   99.03
  4133.5   94.14  4158.7   93.92  4188.8   92.06  4232.4   91.84  4430.4   93.06
    4529   95.14  4544.2   93.67  4628.3    92.4  4669.1   92.26  4679.1   91.92
  4698.8   90.71  5729.7   91.21  5819.8   92.37  5829.8    92.7  6020.1   95.12
  6331.3  103.26  6542.2   106.7  6592.4  108.39  6628.1  111.44  6662.7  112.87
  6672.7  114.61    6723  116.83  6753.1  119.87  6813.3  121.53  6849.1  124.12
#Mann= 9 ,-1 , 0
  3469.1      .1       0  4034.5     .16       0  4133.5      .1       0
  4232.4     .16       0  4430.4     .08       0  4628.3     .05       0
  4669.1     .07       0  4679.1     .05       0  5829.8      .1       0
Bank Sta=4669.1,5819.8
XS Rating Curve= 0 ,0
Exp/Cntr=0.3,0.1

Type RM Length L Ch R = 1 ,9452    ,338,338,338
BEGIN DESCRIPTION:
Mapping XS b1b29180
END DESCRIPTION:
XS GIS Cut Line= 4
      2304100.18     13241819.75      2304043.13     13240148.08
      2304242.82     13239771.52      2304396.91     13239720.15
#Sta/Elev= 30
  3501.7   123.4  3654.7  118.04  3684.7  113.93  3725.1  113.54  3804.8   107.8
  3934.8  100.22  4004.9   97.99  4011.8   96.71  4016.8   97.52    4125   92.27
    4155   92.09    4172   91.21  4174.7   90.71    5187   91.21  5193.8   92.17
  5237.7   91.98  5266.3   94.02  5303.7   94.82    5364   99.05  5402.1   100.5
    5408  101.91  5424.3  101.81  5439.4  103.67    5452  103.56  5458.7  105.09
    5504  108.57  5583.9  113.55  5637.4  116.33  5694.9  117.26    5763  120.74
#Mann= 4 ,-1 , 0
  3501.7     .08       0    4172    .033       0  5193.8     .12       0
  5439.4      .1       0
Bank Sta=4155,5193.8
XS Rating Curve= 0 ,0
Exp/Cntr=0.3,0.1