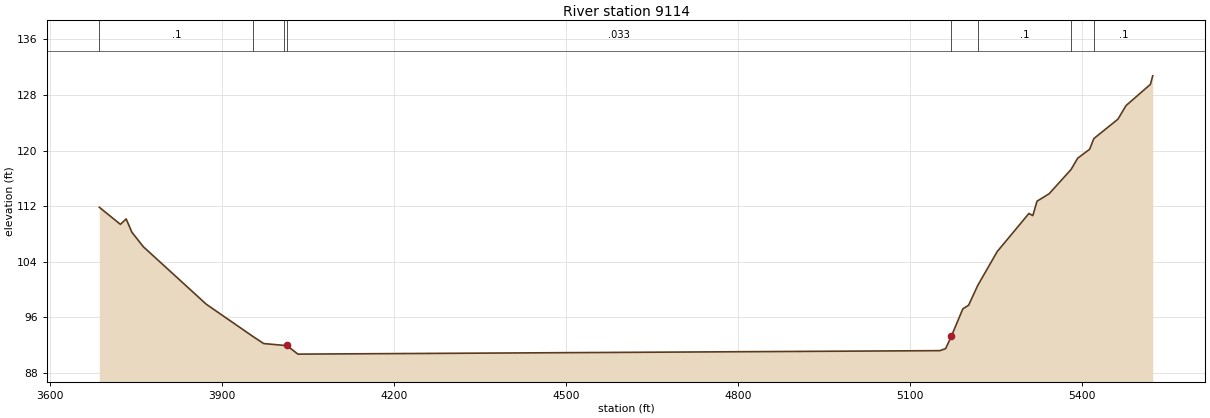
HEC-RAS study RAMIRENA CREEK.prj: RAMIRENA CREEK Base Level Engineering

--- RAMIRENA CREEK.g01 (geometry) --- (continued)

Type RM Length L Ch R = 1 ,9114    ,0,0,0
BEGIN DESCRIPTION:
RAMIRENA CREEK 1.0
END DESCRIPTION:
XS GIS Cut Line= 3
      2304410.83     13241673.67      2304379.12     13240060.08
      2304542.98     13239906.46
#Sta/Elev= 30
  3685.4  111.84  3722.2  109.38  3732.2  110.16  3742.2  108.25  3762.2  106.16
  3872.2   97.88  3954.4    93.2  3972.3   92.23  4007.5   91.97  4012.3   91.97
    4032   90.71  5152.5   91.21  5162.5   91.51  5172.5    93.3  5192.5   97.23
  5202.5   97.74  5218.4  100.58  5252.5  105.47  5307.8  110.95  5314.6  110.64
  5321.9  112.71    5343  113.78  5381.3  117.27  5392.8  118.89  5413.8  120.19
  5421.1  121.72  5463.1  124.51  5477.3  126.47  5519.8  129.52  5523.9  130.75
#Mann= 8 ,-1 , 0
  3685.4      .1       0  3954.4     .12       0  4007.5     .07       0
  4012.3    .033       0  5172.5     .05       0  5218.4      .1       0
  5381.3     .12       0  5421.1      .1       0
Bank Sta=4012.3,5172.5
XS Rating Curve= 0 ,0
Exp/Cntr=0.3,0.1

Chan Stop Cuts=-1
Use User Specified Reach Order=0
Composite Channel Slope=5