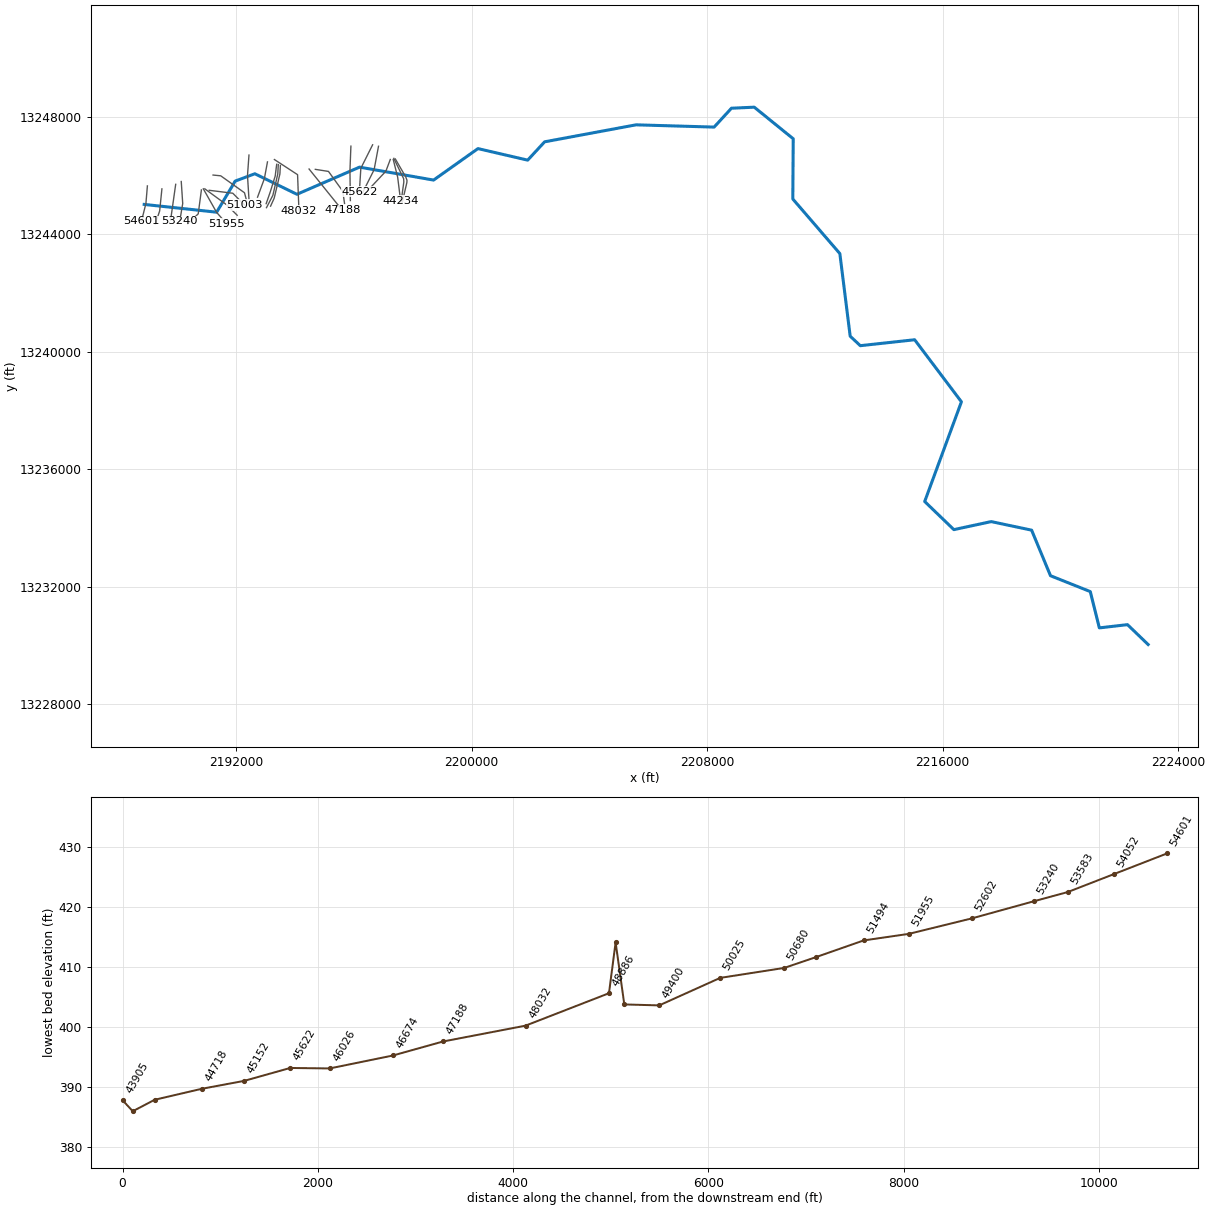
--- SALT BRANCH RAMIRENA CREEK.prj (project) ---

Proj Title=SALT BRANCH RAMIRENA CREEK Base Level Engineering
Current Plan=p01
Default Exp/Contr=0.3,0.1
English Units
Geom File=g01
Flow File=f01
Plan File=p01
Y Axis Title=Elevation
X Axis Title(PF)=Main Channel Distance
X Axis Title(XS)=Station
BEGIN DESCRIPTION:
SALT BRANCH RAMIRENA CREEK
END DESCRIPTION:
DSS Export Rating Curves= 0
DSS Export Rating Curve Sorted= 0
DSS Export Volume Flow Curves= 0
DXF OffsetX= 0
DXF OffsetY= 0
DXF ScaleX= 1
DXF ScaleY= 10

--- SALT BRANCH RAMIRENA CREEK.p01 (plan) ---

Plan Title=Multiple Run
Program Version=4.10
Short Identifier=Multiple
Geom File=g01
Flow File=f01
Subcritical Flow
K Sum by GR= 0
Std Step Tol= 0.01
Critical Tol= 0.01
Num of Std Step Trials= 20
Max Error Tol= 0.3
Flow Tol Ratio= 0.001
Split Flow NTrial= 30
Split Flow Tol= 0.02
Split Flow Ratio= 0.02
Log Output Level= 0
Friction Slope Method= 1
Unsteady Friction Slope Method= 2
Unsteady Bridges Friction Slope Method= 1
Parabolic Critical Depth
Global Vel Dist= 1 , 1 , 1
Global Log Level= 0
CheckData=True
Encroach Param=-1 ,0,0, 0
BEGIN DESCRIPTION:
Multiple Run
END DESCRIPTION:
Computation Interval=1HOUR
Output Interval=1HOUR
Run HTab= 0
Run UNet= 0
Run PostProcess= 0
Run WQNet= 0
UNET Theta= 1
UNET Theta Warmup= 1
UNET ZTol= 0.02
UNET ZSATol= 0.05
UNET MxIter= 20
UNET MaxInSteps= 0
UNET DtIC= 0
UNET DtMin= 0
UNET MaxCRTS= 20
UNET WFStab= 2
UNET SFStab= 1
UNET WFX= 1
UNET SFX= 1
UNET DSS MLevel= 4
UNET DZMax Abort= 100
UNET Convert EG Bridges= 0
UNET Use Existing IB Tables=-1
UNET Froude Reduction=False
UNET Froude Limit= 1
UNET Froude Power= 10
UNET Time Slicing=0,0, 5
UNET Junction Losses=0
Instantaneous Interval=1HOUR
Write IC File= 0
Write IC File at Sim End=0
Echo Input=False
Echo Parameters=False
Echo Output=False
Write Detailed= 0
WQ AD Non Conservative
WQ ULTIMATE=-1
WQ Max Comp Step=1HOUR
WQ Output Interval=15MIN
WQ Output Selected Increments= 0
WQ Output face flow=0
WQ Output face velocity=0
WQ Output face area=0
WQ Output face dispersion=0
WQ Output cell volume=0
WQ Output cell surface area=0
WQ Output cell continuity=0
WQ Output cumulative cell continuity=0
WQ Output face conc=0
WQ Output face dconc_dx=0
WQ Output face courant=0
WQ Output face peclet=0
WQ Output face adv mass=0
WQ Output face disp mass=0
WQ Output cell mass=0
WQ Output cell source sink temp=0
WQ Output cell source sink nsm=0
WQ Output MaxMinRange=-1
WQ Daily Max Min Mean=-1
WQ Daily Range=0
WQ Daily Time=0
WQ Create Restart=0
WQ Fixed Restart=0
WQ System Summary=0
WQ Use Fixed Temperature=0
Sorting and Armoring Iterations= 10
XS Update Threshold= 0.02
Hydraulics Update Threshold= 0.02
Energy Slope Method= 1
Volume Change Method= 0
XS Weighting Method= 0
Number of US Weighted Cross Sections= 1
Number of DS Weighted Cross Sections= 1
Upstream XS Weight=0.25
Main XS Weight=0.5
Downstream XS Weight=0.25
Number of DS XS's Weighted with US Boundary= 1
Upstream Boundary Weight= 1
Weight of XSs Associated with US Boundary= 0
Number of US XS's Weighted with DS Boundary= 1
Downstream Boundary Weight= 0.5
Weight of XSs Associated with DS Boundary= 0.5
Sediment Output Level= 4
Mass or Volume Output= 0
Output Increment Type= 1
Profile and TS Output Increment= 10
XS Output Flag= 0
XS Output Increment= 10
Disregard all LS=0
Disregard all Conn=0
Disregard all Breaches=0
Disregard all Pumps=0

--- SALT BRANCH RAMIRENA CREEK.f01 (steady flow) ---

Flow Title=Multiple
Program Version=4.10
Number of Profiles= 7
Profile Names=10-year,25-year,50-year,1pct_min,100-year,1pct_plu,500-year
River Rch & RM=SALT BRANCH RAMI,Reach-1         ,54601
     173     239     293     266     359     486     547
River Rch & RM=SALT BRANCH RAMI,Reach-1         ,54052
     224     313     387     353     477     645     735
River Rch & RM=SALT BRANCH RAMI,Reach-1         ,51003
     355     506     635     585     791    1070    1250
River Rch & RM=SALT BRANCH RAMI,Reach-1         ,46026
     536     775     982     912    1233    1668    1979
River Rch & RM=SALT BRANCH RAMI,Reach-1         ,45622
     536     775     982     912    1233    1668    1979
River Rch & RM=SALT BRANCH RAMI,Reach-1         ,40472
     605     878    1114    1037    1403    1897    2260
River Rch & RM=SALT BRANCH RAMI,Reach-1         ,35365
     702    1023    1303    1215    1644    2223    2661
River Rch & RM=SALT BRANCH RAMI,Reach-1         ,30205
     723    1053    1339    1248    1688    2283    2726
River Rch & RM=SALT BRANCH RAMI,Reach-1         ,23012
     970    1427    1826    1712    2315    3131    3781
River Rch & RM=SALT BRANCH RAMI,Reach-1         ,18288
    1045    1538    1969    1846    2497    3376    4079
River Rch & RM=SALT BRANCH RAMI,Reach-1         ,17823
    1045    1538    1969    1846    2497    3376    4079
River Rch & RM=SALT BRANCH RAMI,Reach-1         ,12078
    1241    1836    2360    2219    3001    4059    4935
River Rch & RM=SALT BRANCH RAMI,Reach-1         ,10830
    1241    1836    2360    2219    3001    4059    4935
River Rch & RM=SALT BRANCH RAMI,Reach-1         ,7970
    1247    1844    2369    2226    3011    4072    4945
Boundary for River Rch & Prof#=SALT BRANCH RAMI,Reach-1         , 1
Up Type= 0
Dn Type= 3
Dn Slope=0.0027
Boundary for River Rch & Prof#=SALT BRANCH RAMI,Reach-1         , 2
Up Type= 0
Dn Type= 3
Dn Slope=0.0027
Boundary for River Rch & Prof#=SALT BRANCH RAMI,Reach-1         , 3
Up Type= 0
Dn Type= 3
Dn Slope=0.0027
Boundary for River Rch & Prof#=SALT BRANCH RAMI,Reach-1         , 4
Up Type= 0
Dn Type= 3
Dn Slope=0.0027
Boundary for River Rch & Prof#=SALT BRANCH RAMI,Reach-1         , 5
Up Type= 0
Dn Type= 3
Dn Slope=0.0027
Boundary for River Rch & Prof#=SALT BRANCH RAMI,Reach-1         , 6
Up Type= 0
Dn Type= 3
Dn Slope=0.0027
Boundary for River Rch & Prof#=SALT BRANCH RAMI,Reach-1         , 7
Up Type= 0
Dn Type= 3
Dn Slope=0.0027
DSS Import GetInterval= 0
DSS Import GetPeak= 0
DSS Import FillOption= 0

--- SALT BRANCH RAMIRENA CREEK.g01 (geometry) ---

Geom Title=Existing Conditions
Program Version=4.10

River Reach=SALT BRANCH RAMI,Reach-1
Reach XY= 30
      2188879.98     13245016.23      2191340.83     13244751.34
      2191969.66     13245810.07      2192637.12     13246060.22
      2194067.04     13245361.26      2196193.03     13246285.87
      2198708.43     13245845.21      2200215.73     13246917.08
      2201904.31     13246523.85      2202479.83     13247147.98
      2205582.98     13247726.41      2208236.86     13247649.61
      2208825.12     13248292.32      2209599.89      13248327.5
      2210923.41      13247251.8      2210909.06     13245200.89
       2212506.8     13243341.39      2212858.15     13240527.67
      2213201.91     13240204.75      2215047.45     13240406.85
      2216636.29      13238293.3      2215388.61      13234897.7
      2216379.37     13233940.15      2217647.79     13234213.32
      2219020.34     13233921.81       2219661.2     13232370.36
      2221012.69     13231829.52      2221320.93     13230593.41
      2222276.47     13230703.86      2222977.72     13230026.86

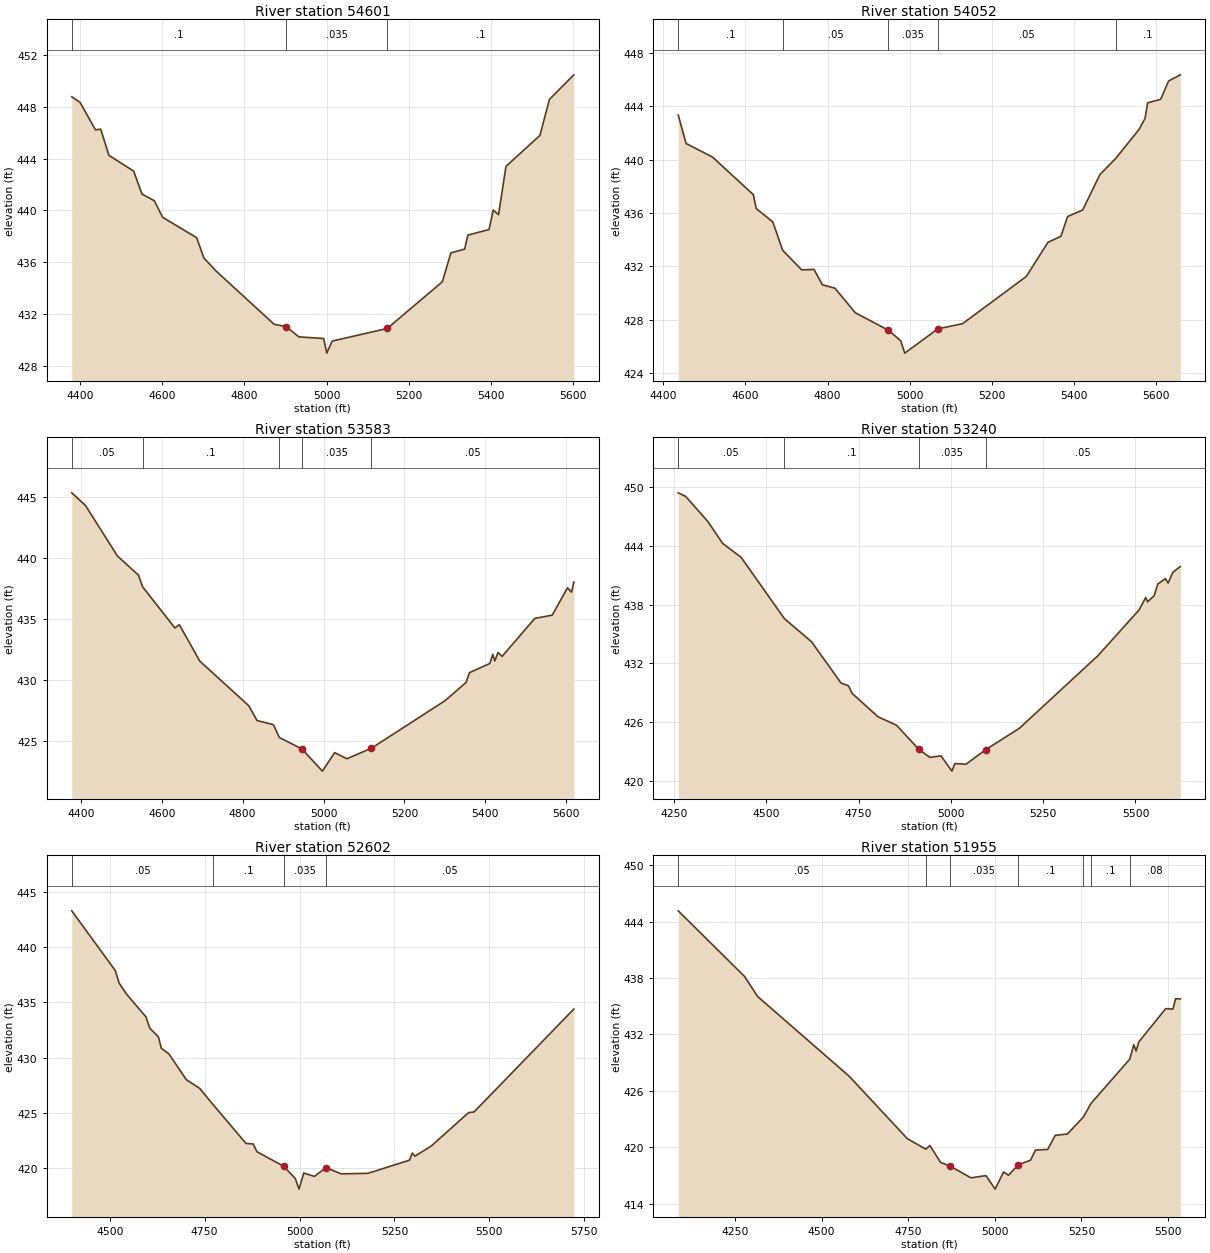
Type RM Length L Ch R = 1 ,54601   ,549,549,549
BEGIN DESCRIPTION:
SALT BRANCH RAMIRENA CREEK 69.0
END DESCRIPTION:
XS GIS Cut Line= 3
      2188987.72     13245646.87      2188937.72     13245046.85
      2188787.71     13244446.81
#Sta/Elev= 30
  4380.6  448.79  4400.7  448.36  4438.3  446.23  4450.9  446.29  4470.9  444.26
  4531.1  443.04  4551.2  441.27  4581.3  440.75  4601.4  439.47  4684.2  437.89
  4701.7  436.32  4731.8   435.3  4872.3   431.2  4902.4     431  4932.5  430.22
    4993  430.09  5000.5  428.96  5013.6  429.89  5147.6  430.87  5281.6  434.48
  5302.2  436.71  5335.7  437.01  5343.5  438.09    5395  438.52  5405.3  440.03
  5418.2  439.67  5436.2  443.41  5518.7   445.8  5541.9  448.59  5601.2  450.49
#Mann= 3 , 0 , 0
  4380.6      .1       0  4902.4    .035       0  5147.6      .1       0
Bank Sta=4902.4,5147.6
XS Rating Curve= 0 ,0
Exp/Cntr=0.3,0.1

Type RM Length L Ch R = 1 ,54052   ,469,469,469
BEGIN DESCRIPTION:
SALT BRANCH RAMIRENA CREEK 68.0
END DESCRIPTION:
XS GIS Cut Line= 3
      2189481.12     13245545.89      2189403.97      13244791.8
      2189254.73     13244351.54
#Sta/Elev= 30
  4436.4  443.34  4455.5  441.21  4519.9  440.19  4619.3  437.37  4626.4  436.32
  4666.6  435.33  4690.7   433.2    4737  431.73  4767.2  431.76  4787.3  430.61
  4818.1  430.35  4867.7  428.51  4948.1   427.2  4978.3  426.41  4988.1  425.48
  5068.7   427.3    5129  427.69  5284.1  431.23  5336.9  433.79  5368.6  434.25
  5384.8  435.73  5421.5  436.22  5463.6  438.88    5502  440.09  5558.7  442.26
  5573.3  443.08  5579.8  444.26  5611.4  444.52  5630.8   445.9  5659.3  446.36
#Mann= 5 ,-1 , 0
  4436.4      .1       0  4690.7     .05       0  4948.1    .035       0
  5068.7     .05       0    5502      .1       0
Bank Sta=4948.1,5068.7
XS Rating Curve= 0 ,0
Exp/Cntr=0.3,0.1

Type RM Length L Ch R = 1 ,53583   ,343,343,343
BEGIN DESCRIPTION:
SALT BRANCH RAMIRENA CREEK 67.0
END DESCRIPTION:
XS GIS Cut Line= 2
      2189949.03     13245700.22      2189774.89      13244471.3
#Sta/Elev= 30
  4377.6  445.38  4411.3  444.35  4490.5  440.19  4542.6  438.61  4552.7  437.66
  4632.4  434.28  4643.6  434.54  4694.1  431.55  4815.3  427.88  4835.5  426.67
  4875.9  426.33  4890.6  425.28  4946.6  424.33  4997.2  422.51  5027.4  424.03
  5057.7  423.53  5118.3  424.39  5300.1  428.29  5352.4   429.8  5360.7   430.6
  5411.2  431.36  5418.4  432.11  5423.4  431.56  5431.4  432.26  5441.5  431.94
  5522.3  435.06  5565.4  435.33  5603.1  437.57  5613.2  437.22  5618.8  438.05
#Mann= 5 ,-1 , 0
  4377.6     .05       0  4552.7      .1       0  4890.6     .05       0
  4946.6    .035       0  5118.3     .05       0
Bank Sta=4946.6,5118.3
XS Rating Curve= 0 ,0
Exp/Cntr=0.3,0.1

Type RM Length L Ch R = 1 ,53240   ,638,638,638
BEGIN DESCRIPTION:
SALT BRANCH RAMIRENA CREEK 66.0
END DESCRIPTION:
XS GIS Cut Line= 3
      2190137.72     13245796.85      2190187.72     13245046.85
      2190087.73     13244446.89
#Sta/Elev= 30
  4261.6  449.45  4281.6  449.09  4341.8  446.52  4381.9  444.28    4432  442.85
    4549  436.59  4622.4  434.23  4702.6     430  4722.6  429.72  4732.6  428.94
  4802.8  426.55  4852.9  425.68    4913  423.23  4943.1   422.4  4973.2  422.55
    5003  420.99  5010.8  421.76  5041.1   421.7  5094.4  423.18  5185.6  425.37
  5398.5   432.8    5510  437.48  5527.8  438.75  5532.8  438.31  5550.6  438.93
  5560.7  440.14    5581  440.67  5588.6  440.23  5601.3  441.33  5621.5  441.91
#Mann= 4 ,-1 , 0
  4261.6     .05       0    4549      .1       0    4913    .035       0
  5094.4     .05       0
Bank Sta=4913,5094.4
XS Rating Curve= 0 ,0
Exp/Cntr=0.3,0.1

Type RM Length L Ch R = 1 ,52602   ,647,647,647
BEGIN DESCRIPTION:
SALT BRANCH RAMIRENA CREEK 65.0
END DESCRIPTION:
XS GIS Cut Line= 3
      2190822.18     13245510.71      2190714.76     13244695.56
      2190354.58     13244348.02
#Sta/Elev= 30
  4399.9  443.28  4514.7  437.87  4524.8  436.73  4544.4  435.74  4595.4  433.69
  4605.5  432.67  4628.1  431.89  4635.8  430.86  4655.9  430.34  4701.6  428.02
  4736.6  427.24    4772  425.77  4858.9  422.25  4877.8   422.2  4887.9   421.5
  4958.5  420.18  4988.8  419.08  4998.6  418.12    5011  419.58  5039.2  419.27
  5069.5  420.07  5109.8   419.5  5180.4  419.55  5289.7  420.74  5296.9  421.38
  5303.9   421.1  5346.3     422  5445.4  425.04  5459.5  425.09  5722.6   434.4
#Mann= 4 ,-1 , 0
  4399.9     .05       0    4772      .1       0  4958.5    .035       0
  5069.5     .05       0
Bank Sta=4958.5,5069.5
XS Rating Curve= 0 ,0
Exp/Cntr=0.3,0.1

Type RM Length L Ch R = 1 ,51955   ,461,461,461
BEGIN DESCRIPTION:
SALT BRANCH RAMIRENA CREEK 64.0
END DESCRIPTION:
XS GIS Cut Line= 3
       2190887.7     13245546.89      2191337.72     13244746.85
       2191687.7     13244346.88
#Sta/Elev= 30
  4085.9  445.15  4277.5  438.16  4315.1  436.03  4579.3  427.55  4747.3   420.9
  4800.7  419.78  4812.3  420.18  4843.2  418.37  4871.6  417.97  4930.8  416.73
  4974.2  416.97  5000.7  415.53  5025.2  417.36  5039.4  417.01  5067.9  418.13
    5103  418.61  5117.2  419.69  5152.4  419.75  5174.2  421.25  5209.3   421.4
    5255  423.18  5277.7  424.66  5389.3  429.36    5401  430.91  5407.7  430.23
  5415.3  431.19  5493.1  434.74    5514  434.69  5521.6  435.79  5535.3  435.78
#Mann= 7 ,-1 , 0
  4085.9     .05       0  4800.7      .1       0  4871.6    .035       0
  5067.9      .1       0    5255     .08       0  5277.7      .1       0
  5389.3     .08       0
Bank Sta=4871.6,5067.9
XS Rating Curve= 0 ,0
Exp/Cntr=0.3,0.1

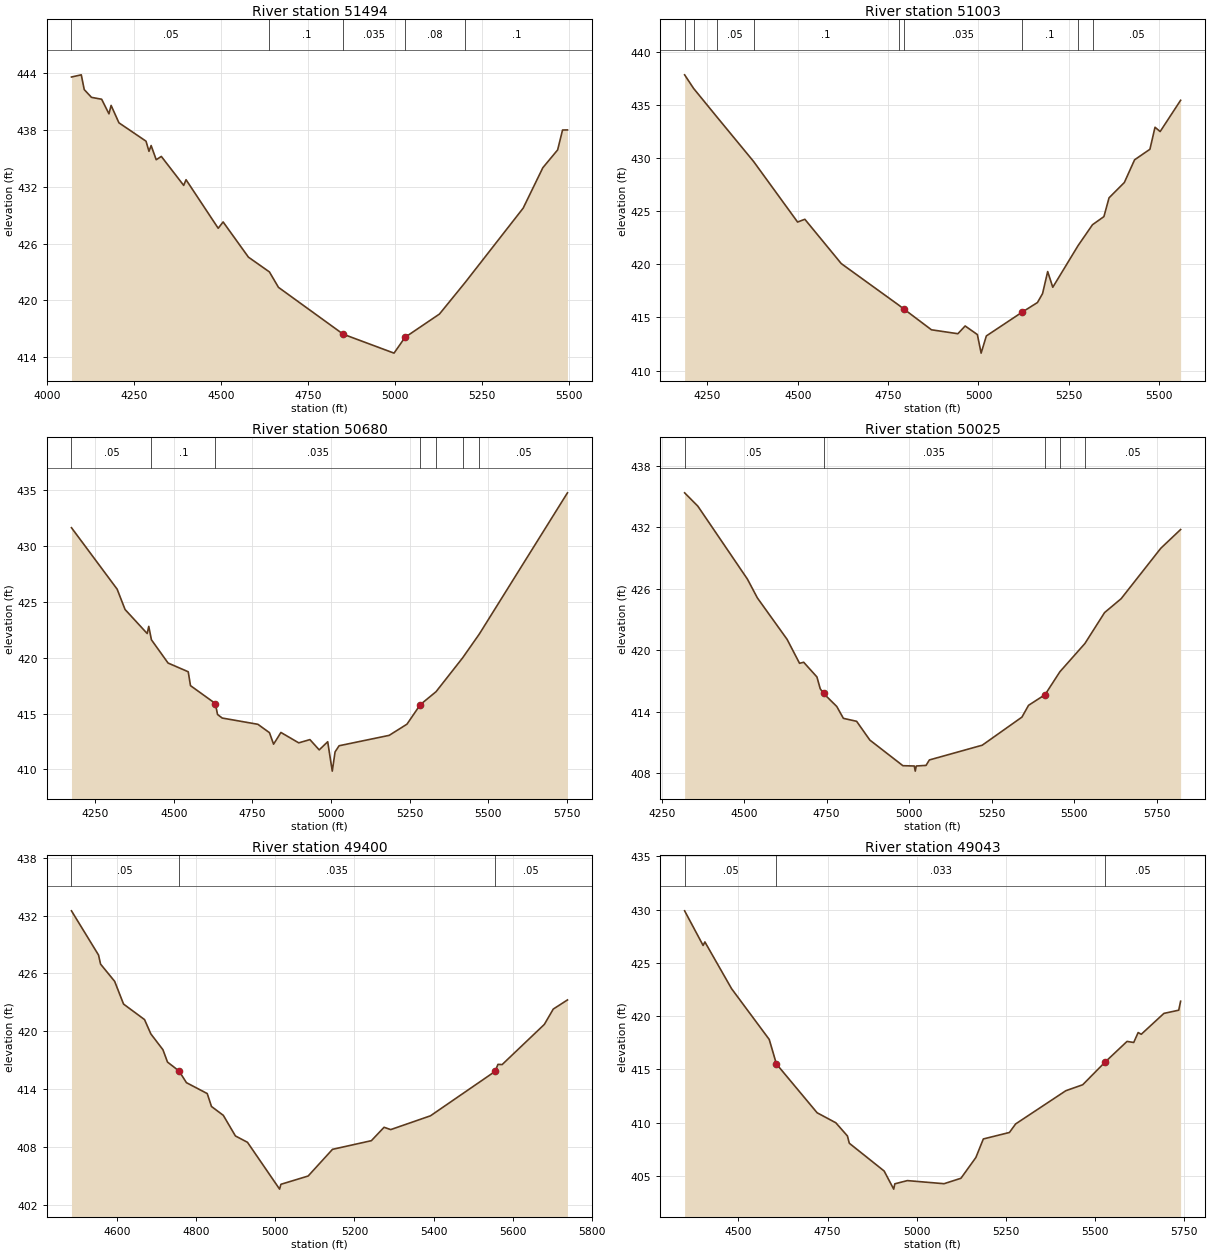
Type RM Length L Ch R = 1 ,51494   ,491,491,491
BEGIN DESCRIPTION:
SALT BRANCH RAMIRENA CREEK 63.0
END DESCRIPTION:
XS GIS Cut Line= 3
      2190937.71     13245546.86      2191687.72     13244996.85
      2192037.69     13244646.88
#Sta/Elev= 30
  4070.8  443.61    4099  443.84  4107.5  442.28  4128.3  441.46  4157.6  441.26
  4178.5  439.72  4184.7  440.61  4207.2  438.77    4285  436.83  4293.5  435.76
  4299.7  436.37  4314.3  434.87    4329  435.22  4393.2  432.16    4400  432.76
  4492.4  427.63  4506.5   428.3  4579.2  424.58  4639.5  423.02  4665.5  421.39
  4851.5  416.44  4997.5  414.44  5029.2  416.11  5128.1  418.57  5202.2  421.92
  5368.6  429.76  5425.1  434.03  5467.6  435.91  5481.7  438.01  5495.8  438.02
#Mann= 5 ,-1 , 0
  4070.8     .05       0  4639.5      .1       0  4851.5    .035       0
  5029.2     .08       0  5202.2      .1       0
Bank Sta=4851.5,5029.2
XS Rating Curve= 0 ,0
Exp/Cntr=0.3,0.1

Type RM Length L Ch R = 1 ,51003   ,323,323,323
BEGIN DESCRIPTION:
SALT BRANCH RAMIRENA CREEK 62.0
END DESCRIPTION:
XS GIS Cut Line= 3
      2191087.68     13245496.86      2191887.72     13245396.85
      2192287.76     13244996.82
#Sta/Elev= 30
  4187.2  437.88    4212   436.6    4276  433.93    4378  429.71  4499.7     424
  4519.8  424.26  4620.6  420.08  4779.4  416.17  4794.4  415.78    4870  413.84
  4943.1  413.47  4963.2   414.2    4997  413.39  5007.4  411.64  5021.8  413.26
  5120.7   415.5  5163.2  416.41  5177.3  417.25  5191.5  419.33  5205.6  417.85
  5275.8  421.79  5315.5  423.75    5347  424.51  5361.2  426.28  5403.6  427.73
  5431.9  429.87  5474.3  430.86  5488.4  432.94  5502.6  432.53  5559.2  435.48
#Mann= 9 ,-1 , 0
  4187.2     .05       0    4212      .1       0    4276     .05       0
    4378      .1       0  4779.4     .08       0  4794.4    .035       0
  5120.7      .1       0  5275.8     .08       0  5315.5     .05       0
Bank Sta=4794.4,5120.7
XS Rating Curve= 0 ,0
Exp/Cntr=0.3,0.1

Type RM Length L Ch R = 1 ,50680   ,655,655,655
BEGIN DESCRIPTION:
SALT BRANCH RAMIRENA CREEK 61.0
END DESCRIPTION:
XS GIS Cut Line= 4
      2191218.21      13246016.3      2191478.59     13245990.26
      2192285.88       13245413.      2192368.17      13245101.2
#Sta/Elev= 30
  4174.8  431.63    4320  426.13  4345.2  424.31  4415.5  422.16  4420.5   422.8
    4429   421.6  4481.9  419.52    4546  418.74  4553.1   417.5  4632.1   415.9
  4639.1  414.92  4653.9   414.6  4767.3  414.04  4804.2  413.29  4817.3  412.26
  4840.6  413.31  4897.2  412.38  4932.8  412.67  4962.3  411.75  4989.3  412.48
  5003.8  409.85  5012.7  411.57  5025.5  412.12  5184.7  413.05  5241.2  414.05
  5283.7   415.8  5333.8  416.96    5418  419.98  5471.1  422.11  5751.4  434.75
#Mann= 7 ,-1 , 0
  4174.8     .05       0    4429      .1       0  4632.1    .035       0
  5283.7      .1       0  5333.8     .05       0    5418     .08       0
  5471.1     .05       0
Bank Sta=4632.1,5283.7
XS Rating Curve= 0 ,0
Exp/Cntr=0.3,0.1

Type RM Length L Ch R = 1 ,50025   ,625,625,625
BEGIN DESCRIPTION:
SALT BRANCH RAMIRENA CREEK 60.0
END DESCRIPTION:
XS GIS Cut Line= 3
      2192437.72     13246696.81      2192387.72     13245996.85
      2192437.72     13245196.86
#Sta/Elev= 30
  4319.6  435.34  4359.7  434.04    4510  426.92  4540.1  425.09  4630.3  421.04
  4667.9  418.71  4680.5  418.81  4720.6  417.38  4730.6  416.23  4740.6  415.77
  4780.7   414.5  4800.8  413.34  4840.9  413.05    4881  411.22  4981.2  408.72
  5015.8  408.69  5018.6  408.19  5021.8  408.69  5051.4  408.75  5061.4  409.28
  5221.7  410.72    5342  413.46    5362  414.61  5412.1  415.65  5456.9  417.88
  5532.8  420.64  5592.5  423.66  5642.6  425.01  5762.8  429.93  5822.9  431.76
#Mann= 5 ,-1 , 0
  4319.6     .05       0  4740.6    .035       0  5412.1      .1       0
  5456.9     .08       0  5532.8     .05       0
Bank Sta=4740.6,5412.1
XS Rating Curve= 0 ,0
Exp/Cntr=0.3,0.1

Type RM Length L Ch R = 1 ,49400   ,357,357,357
BEGIN DESCRIPTION:
SALT BRANCH RAMIRENA CREEK 59.0
END DESCRIPTION:
XS GIS Cut Line= 3
      2193066.07     13246464.13       2192960.5     13245891.99
      2192728.93       13245262.
#Sta/Elev= 30
  4485.3  432.49  4553.7   427.9  4558.8  426.96  4594.4  425.17  4616.9  422.81
  4669.9   421.2  4685.9  419.71  4716.4  418.07  4727.9  416.79  4757.1  415.86
  4775.8  414.65  4828.3  413.52    4839  412.18  4868.9  411.26  4899.5  409.12
    4930  408.46  5011.1   403.6  5014.3   404.1  5083.2  404.96  5144.7  407.73
    5243  408.63    5275  410.02  5291.8  409.78  5392.2  411.21  5555.4  415.82
  5562.7  416.55  5573.3  416.53  5679.9   420.7  5702.4  422.29  5738.3  423.24
#Mann= 3 , 0 , 0
  4485.3     .05       0  4757.1    .035       0  5555.4     .05       0
Bank Sta=4757.1,5555.4
XS Rating Curve= 0 ,0
Exp/Cntr=0.3,0.1

Type RM Length L Ch R = 1 ,49043   ,89,89,89
BEGIN DESCRIPTION:
SALT BRANCH RAMIRENA CREEK 58.0
END DESCRIPTION:
XS GIS Cut Line= 4
      2193379.37     13246382.41      2193328.29     13245980.53
      2193161.42     13245442.46      2193022.48     13245042.58
#Sta/Elev= 30
    4349  429.89  4400.9  426.64  4405.9  426.97  4480.8  422.58  4586.5  417.81
  4606.6  415.51  4720.8  410.93  4773.3  409.99  4805.9  408.75  4811.1  408.07
  4908.9  405.46  4935.7  403.76  4938.9  404.26    4974  404.56    5077  404.27
  5124.4  404.78  5166.3  406.73  5187.2  408.47  5260.5  409.08  5277.8  409.88
  5418.7     413  5466.1  413.56  5528.3  415.67  5590.5  417.63  5609.2  417.53
  5621.6  418.46  5630.4   418.3  5693.9  420.26  5735.5  420.56  5740.8   421.4
#Mann= 3 , 0 , 0
    4349     .05       0  4606.6    .033       0  5528.3     .05       0
Bank Sta=4606.6,5528.3
XS Rating Curve= 0 ,0
Exp/Cntr=0.3,0.1

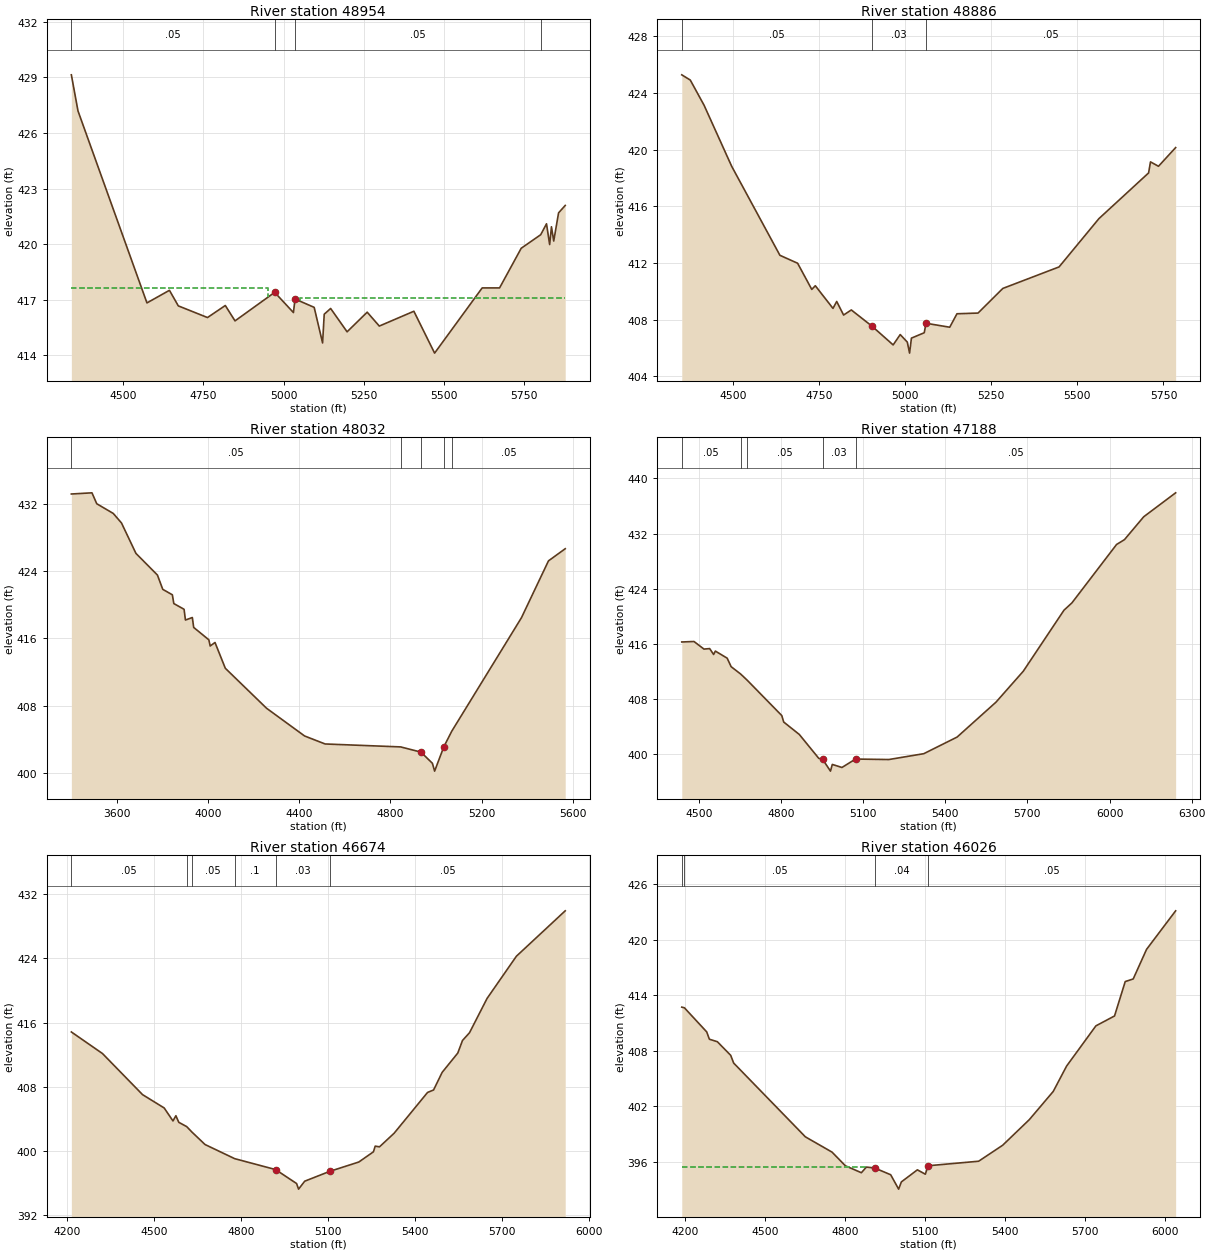
Type RM Length L Ch R = 1 ,48954   ,68,68,68
BEGIN DESCRIPTION:
Mapping XS 1ec1aad7
END DESCRIPTION:
XS GIS Cut Line= 4
      2193433.86     13246372.12      2193416.83     13246055.45
      2193249.96     13245326.68      2193032.36     13244905.08
#Sta/Elev= 30
  4338.8  429.14  4359.5  427.19  4574.4  416.83  4644.5  417.51  4672.1  416.67
  4763.1  416.04  4818.6  416.69  4848.9  415.86  4972.5   417.4  5030.9  416.31
    5036  417.04  5095.6  416.59  5121.8  414.67  5126.9  416.22  5146.9  416.53
  5198.2  415.27  5260.8  416.33  5298.6  415.58  5406.3  416.38  5470.9  414.12
  5619.2  417.64  5673.4  417.64  5740.9  419.78  5801.6  420.51  5819.7   421.1
  5829.5  419.98  5835.1  420.94  5842.2  420.17  5857.3  421.69    5878  422.09
#Mann= 4 ,-1 , 0
  4338.8     .05       0  4972.5     .03       0    5036     .05       0
  5801.6      .1       0
#XS Ineff= 2 , 0
       0 4950.75  417.65 5052.24       0  417.09
Permanent Ineff=
       T       T
Bank Sta=4972.5,5036
XS Rating Curve= 0 ,0
Exp/Cntr=0.3,0.1

Type RM Length L Ch R = 1 ,48886   ,854,854,854
BEGIN DESCRIPTION:
SALT BRANCH RAMIRENA CREEK 57.0
END DESCRIPTION:
XS GIS Cut Line= 4
      2193505.37      13246341.5      2193488.35     13246052.04
      2193294.23     13245227.92      2193172.16     13244956.65
#Sta/Elev= 30
  4351.3  425.29    4376  424.92  4416.1  423.14  4496.2  418.83  4636.3  412.54
  4687.7  411.98  4728.8  410.13  4739.1  410.39  4790.4  408.79  4801.2  409.28
  4821.2  408.32  4843.6  408.68  4903.4  407.54  4965.1  406.21  4985.6  406.94
  5006.2  406.41  5012.8  405.63  5018.2  406.69  5055.4  407.07  5060.5  407.74
  5129.4  407.46  5150.4  408.41  5211.6  408.46  5283.6   410.2  5446.9  411.72
  5562.6  415.13  5706.9  418.36  5712.4  419.14  5735.6  418.83  5785.4  420.15
#Mann= 3 , 0 , 0
  4351.3     .05       0  4903.4     .03       0  5060.5     .05       0
Bank Sta=4903.4,5060.5
XS Rating Curve= 0 ,0
Exp/Cntr=0.3,0.1

Type RM Length L Ch R = 1 ,48032   ,844,844,844
BEGIN DESCRIPTION:
Mapping XS d9a6ca15
END DESCRIPTION:
XS GIS Cut Line= 3
      2193302.06     13246544.56      2194088.51     13246028.95
      2194135.39     13244804.95
#Sta/Elev= 30
  3401.7  433.18    3492  433.32  3513.1  432.02  3585.4  430.87  3621.6  429.73
  3684.8  426.12  3779.1  423.54  3802.5  421.84  3844.6  421.19  3850.9  420.15
  3895.9  419.47  3901.9  418.19  3932.1  418.49  3938.1  417.31  4004.4  415.84
  4010.4   415.1  4031.5  415.52  4076.8  412.45  4257.5   407.7  4424.3   404.4
  4514.3  403.45  4845.4   403.1  4934.6  402.48  4984.7  401.15  4994.4  400.22
  5034.7  403.11  5069.6  404.97    5375  418.46  5493.7  425.23    5567  426.67
#Mann= 5 ,-1 , 0
  3401.7     .05       0  4845.4      .1       0  4934.6    .035       0
  5034.7      .1       0  5069.6     .05       0
Bank Sta=4934.6,5034.7
XS Rating Curve= 0 ,0
Exp/Cntr=0.3,0.1

Type RM Length L Ch R = 1 ,47188   ,514,514,514
BEGIN DESCRIPTION:
Mapping XS a1ce095a
END DESCRIPTION:
XS GIS Cut Line= 2
      2194479.16     13246221.63      2195609.34     13244815.41
#Sta/Elev= 30
  4437.4   416.3    4482  416.37  4518.5  415.27  4539.3  415.34  4553.7  414.49
  4560.1  414.98  4603.3  413.95  4617.7  412.72  4652.6  411.65  4675.9  410.78
  4802.8  405.63  4809.7   404.7  4866.9  402.89  4937.7  399.44  4952.1  399.28
  4980.6  397.58  4987.3  398.55  5022.5  398.11  5072.2  399.33  5193.7  399.26
  5321.7  400.11  5443.3  402.52  5585.3  407.58  5684.9  412.06  5833.7  420.91
  5862.5  421.96  6025.7  430.43  6054.5  431.13  6124.9  434.45  6241.5  437.92
#Mann= 5 ,-1 , 0
  4437.4     .05       0  4652.6     .08       0  4675.9     .05       0
  4952.1     .03       0  5072.2     .05       0
Bank Sta=4952.1,5072.2
XS Rating Curve= 0 ,0
Exp/Cntr=0.3,0.1

Type RM Length L Ch R = 1 ,46674   ,648,648,648
BEGIN DESCRIPTION:
Mapping XS b0e9dfef
END DESCRIPTION:
XS GIS Cut Line= 4
       2194691.7     13246210.35      2195138.47     13246139.81
      2195622.81     13245467.37      2195683.73     13245050.31
#Sta/Elev= 30
    4215  414.83  4322.3  412.14  4460.4  407.02  4534.9  405.36  4565.3  403.74
  4575.4  404.39  4585.3  403.57  4612.7  403.03  4630.5  402.36  4675.8   400.8
  4777.9  399.04  4918.8  397.68  4991.4  395.94  4998.3  395.24  5019.5  396.23
  5105.4  397.45    5206  398.62  5256.3  399.89  5262.5   400.6  5277.2  400.51
  5327.5   402.2  5442.9  407.29  5463.7   407.6  5493.2  409.79  5547.1   412.2
  5563.4  413.77  5587.5  414.73  5648.1  419.01  5749.2  424.27  5917.5  429.93
#Mann= 6 ,-1 , 0
    4215     .05       0  4612.7     .08       0  4630.5     .05       0
  4777.9      .1       0  4918.8     .03       0  5105.4     .05       0
Bank Sta=4918.8,5105.4
XS Rating Curve= 0 ,0
Exp/Cntr=0.3,0.1

Type RM Length L Ch R = 1 ,46026   ,404,404,404
BEGIN DESCRIPTION:
Mapping XS 3513bf7c
END DESCRIPTION:
XS GIS Cut Line= 3
      2195900.25     13247000.38      2195867.34     13246168.02
      2195881.44     13245147.62
#Sta/Elev= 30
  4186.1  412.71    4196  412.64  4279.7  410.04  4289.7  409.25  4319.7  408.98
  4369.8  407.51  4380.8  406.68    4650  398.72  4750.1  397.07  4800.1   395.6
  4860.1  394.85    4879  395.46  4910.2  395.36  4970.2  394.63    5000  393.08
  5010.3  393.86  5070.3  395.16  5100.3  394.69  5110.3   395.6  5300.3  396.09
  5390.3  397.81  5490.3  400.57  5580.3  403.62  5630.3  406.35  5740.3  410.69
  5810.3  411.76  5850.4  415.47  5880.4  415.75  5930.4  418.94  6039.6   423.1
#Mann= 4 ,-1 , 0
  4186.1     .08       0    4196     .05       0  4910.2     .04       0
  5110.3     .05       0
#XS Ineff= 2 , 0
         4879.07  395.47
Permanent Ineff=
       F       F
Bank Sta=4910.2,5110.3
XS Rating Curve= 0 ,0
Exp/Cntr=0.3,0.1

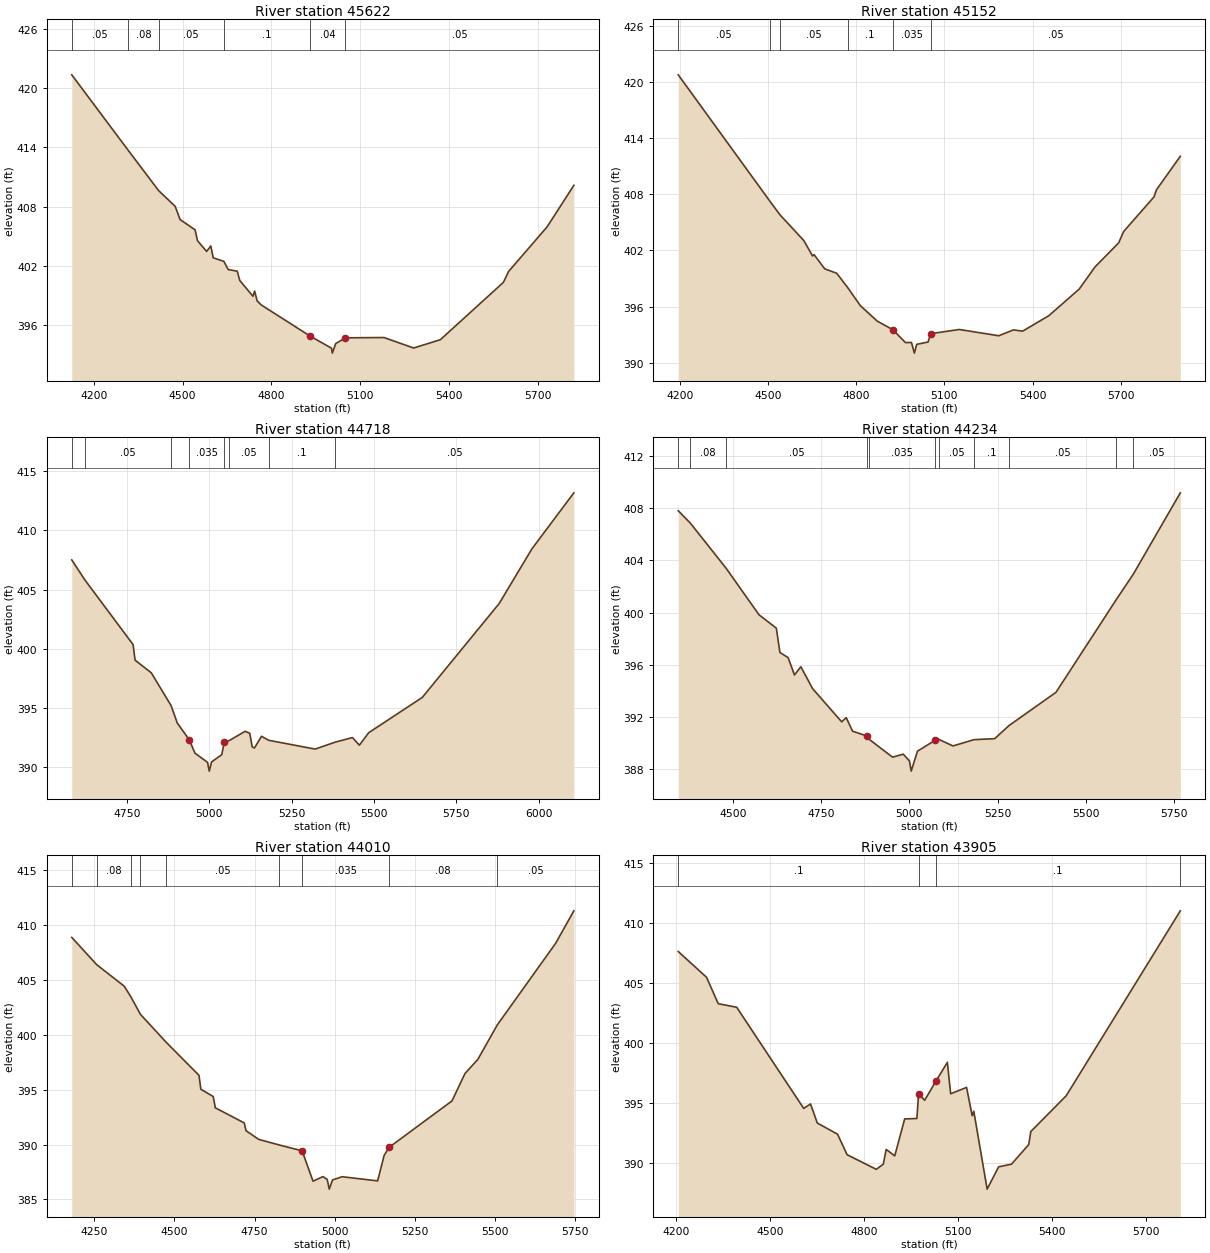
Type RM Length L Ch R = 1 ,45622   ,470,470,470
BEGIN DESCRIPTION:
SALT BRANCH RAMIRENA CREEK 56.0
END DESCRIPTION:
XS GIS Cut Line= 3
      2196637.72     13247046.85      2196237.72     13246246.85
      2196187.72     13245446.83
#Sta/Elev= 30
  4125.4  421.36  4315.6  413.73  4419.1  409.62  4474.8  408.03  4491.5  406.69
  4541.9  405.66  4550.2  404.55    4581  403.46    4595  404.02  4603.3  402.82
  4639.3  402.46  4653.7  401.63  4684.4  401.46  4692.8  400.53  4737.5  398.92
  4743.1  399.45  4751.5  398.46  4765.5  398.04  4930.4  394.89  5002.8  393.66
  5005.6  393.16    5017  394.13  5049.9  394.71  5180.1  394.74  5280.3  393.68
  5370.5  394.52  5583.4  400.33  5600.9  401.43  5731.2  405.96  5821.4  410.16
#Mann= 6 ,-1 , 0
  4125.4     .05       0  4315.6     .08       0  4419.1     .05       0
  4639.3      .1       0  4930.4     .04       0  5049.9     .05       0
Bank Sta=4930.4,5049.9
XS Rating Curve= 0 ,0
Exp/Cntr=0.3,0.1

Type RM Length L Ch R = 1 ,45152   ,434,434,434
BEGIN DESCRIPTION:
SALT BRANCH RAMIRENA CREEK 55.0
END DESCRIPTION:
XS GIS Cut Line= 3
      2196837.71     13246996.82      2196687.72     13246196.85
      2196287.73     13245396.88
#Sta/Elev= 30
  4194.3   420.8    4506  407.28  4540.1  405.83  4621.6  403.06  4651.3  401.41
  4656.3  401.56  4692.8  400.03  4733.5  399.56  4770.3  398.05    4814  396.09
  4871.7  394.43  4924.3  393.52  4967.5  392.14  4987.9  392.15  4997.8  391.01
  5005.7  391.95  5044.5   392.2  5052.9  393.09  5150.8  393.54  5284.9  392.87
  5335.2   393.5    5366  393.36  5455.4  395.02  5558.8  397.87  5611.9  400.22
    5693  402.82  5709.8  404.03  5813.2  407.74  5821.6   408.5  5902.6  412.08
#Mann= 6 ,-1 , 0
  4194.3     .05       0    4506     .08       0  4540.1     .05       0
  4770.3      .1       0  4924.3    .035       0  5052.9     .05       0
Bank Sta=4924.3,5052.9
XS Rating Curve= 0 ,0
Exp/Cntr=0.3,0.1

Type RM Length L Ch R = 1 ,44718   ,484,484,484
BEGIN DESCRIPTION:
SALT BRANCH RAMIRENA CREEK 54.0
END DESCRIPTION:
XS GIS Cut Line= 3
      2197237.72     13246546.85      2197087.72     13246146.85
      2196337.71     13245346.84
#Sta/Elev= 30
  4582.6  407.51  4622.4  405.82  4768.6  400.37  4774.8  399.05  4823.8  397.99
    4884  395.22    4903  393.74  4939.5  392.32  4956.4  391.21  4994.7  390.43
  4999.8  389.69  5007.1  390.47  5037.9  391.08  5045.2  392.12  5061.3  392.28
  5108.7  393.05  5122.9  392.88  5130.2  391.74    5137  391.64  5158.5  392.63
  5180.5  392.29  5321.2  391.55  5382.7  392.14  5434.5  392.52  5455.5  391.88
  5483.8  392.93  5646.5  395.91    5880  403.84  5979.1  408.44  6106.4  413.17
#Mann= 8 ,-1 , 0
  4582.6     .08       0  4622.4     .05       0    4884      .1       0
  4939.5    .035       0  5045.2      .1       0  5061.3     .05       0
  5180.5      .1       0  5382.7     .05       0
Bank Sta=4939.5,5045.2
XS Rating Curve= 0 ,0
Exp/Cntr=0.3,0.1

Type RM Length L Ch R = 1 ,44234   ,224,224,224
BEGIN DESCRIPTION:
SALT BRANCH RAMIRENA CREEK 53.0
END DESCRIPTION:
XS GIS Cut Line= 3
      2197337.73     13246546.82      2197487.72     13245946.85
      2197587.73     13245146.81
#Sta/Elev= 30
    4344  407.81  4378.6  406.85  4479.6  403.41  4573.3  399.83  4622.3  398.81
  4632.6  396.94  4655.8  396.55  4673.8  395.22  4691.9  395.85  4725.4  394.17
  4807.8  391.63  4820.7  391.95  4838.7  390.91    4880  390.54  4883.9  390.33
  4952.1  388.92  4982.6  389.15  5000.2  388.63    5005  387.85  5022.9  389.38
  5073.3  390.22  5083.7  390.28  5123.7  389.78  5182.9  390.26  5242.1  390.34
    5282  391.33  5415.9  393.89  5587.6  401.02  5635.2  402.94  5768.7  409.18
#Mann= 11 ,-1 , 0
    4344     .05       0  4378.6     .08       0  4479.6     .05       0
    4880     .08       0  4883.9    .035       0  5073.3     .08       0
  5083.7     .05       0  5182.9      .1       0    5282     .05       0
  5587.6     .08       0  5635.2     .05       0
Bank Sta=4880,5073.3
XS Rating Curve= 0 ,0
Exp/Cntr=0.3,0.1

Type RM Length L Ch R = 1 ,44010   ,105,105,105
BEGIN DESCRIPTION:
Mapping XS bb2b3c8d
END DESCRIPTION:
XS GIS Cut Line= 4
       2197357.6     13246584.52      2197690.94     13245893.53
      2197697.89     13245782.42      2197604.37     13245100.12
#Sta/Elev= 30
  4179.5  408.88  4257.1   406.4  4343.4  404.43  4365.2   403.4  4393.8  401.87
  4473.3  399.35  4576.6  396.31  4582.4  395.04    4621  394.38  4627.6  393.35
    4718  391.97  4723.6  391.26  4763.2  390.47  4827.6  389.96  4898.6  389.43
  4932.6  386.66  4963.4  387.08  4976.8  386.83  4983.2  385.94  4993.5  386.78
  5023.5  387.07  5134.3  386.69  5154.5  389.01  5169.7  389.74  5366.4  393.98
  5406.8  396.47  5447.2  397.77  5507.9  400.91  5689.9  408.34  5746.7   411.3
#Mann= 9 ,-1 , 0
  4179.5     .05       0  4257.1     .08       0  4365.2     .05       0
  4393.8     .08       0  4473.3     .05       0  4827.6     .08       0
  4898.6    .035       0  5169.7     .08       0  5507.9     .05       0
Bank Sta=4898.6,5169.7
XS Rating Curve= 0 ,0
Exp/Cntr=0.3,0.1

Type RM Length L Ch R = 1 ,43905   ,95,95,95
BEGIN DESCRIPTION:
Mapping XS 06d3e961
END DESCRIPTION:
XS GIS Cut Line= 5
      2197409.69     13246563.67      2197763.86     13245949.08
      2197805.53     13245837.97      2197798.58     13245751.17
      2197642.63     13245082.29
#Sta/Elev= 30
  4206.4   407.6  4296.7  405.45    4334  403.25  4392.9  402.95  4606.7  394.52
  4628.5  394.89  4650.1   393.3  4714.7  392.37  4745.2  390.66  4838.3  389.44
  4860.6  389.87  4869.9   391.1  4897.2  390.56  4928.8  393.64  4967.8  393.68
  4973.2  395.72  4992.7   395.2  5028.3  396.78  5065.1  398.36  5075.6  395.74
  5126.3  396.27  5144.3  393.91  5149.4  394.28    5192  387.79  5228.6  389.65
  5269.7  389.87  5324.8  391.51  5331.3  392.59  5444.2  395.57  5808.3  410.99
#Mann= 4 ,-1 , 0
  4206.4      .1       0  4973.2    .035       0  5028.3      .1       0
  5808.3     .05       0
#XS Ineff= 2 ,-1
 4492.43 4975.08  395.05 5068.77 5540.06   396.4
Permanent Ineff=
       T       T
Bank Sta=4973.2,5028.3
XS Rating Curve= 0 ,0
Exp/Cntr=0.3,0.1