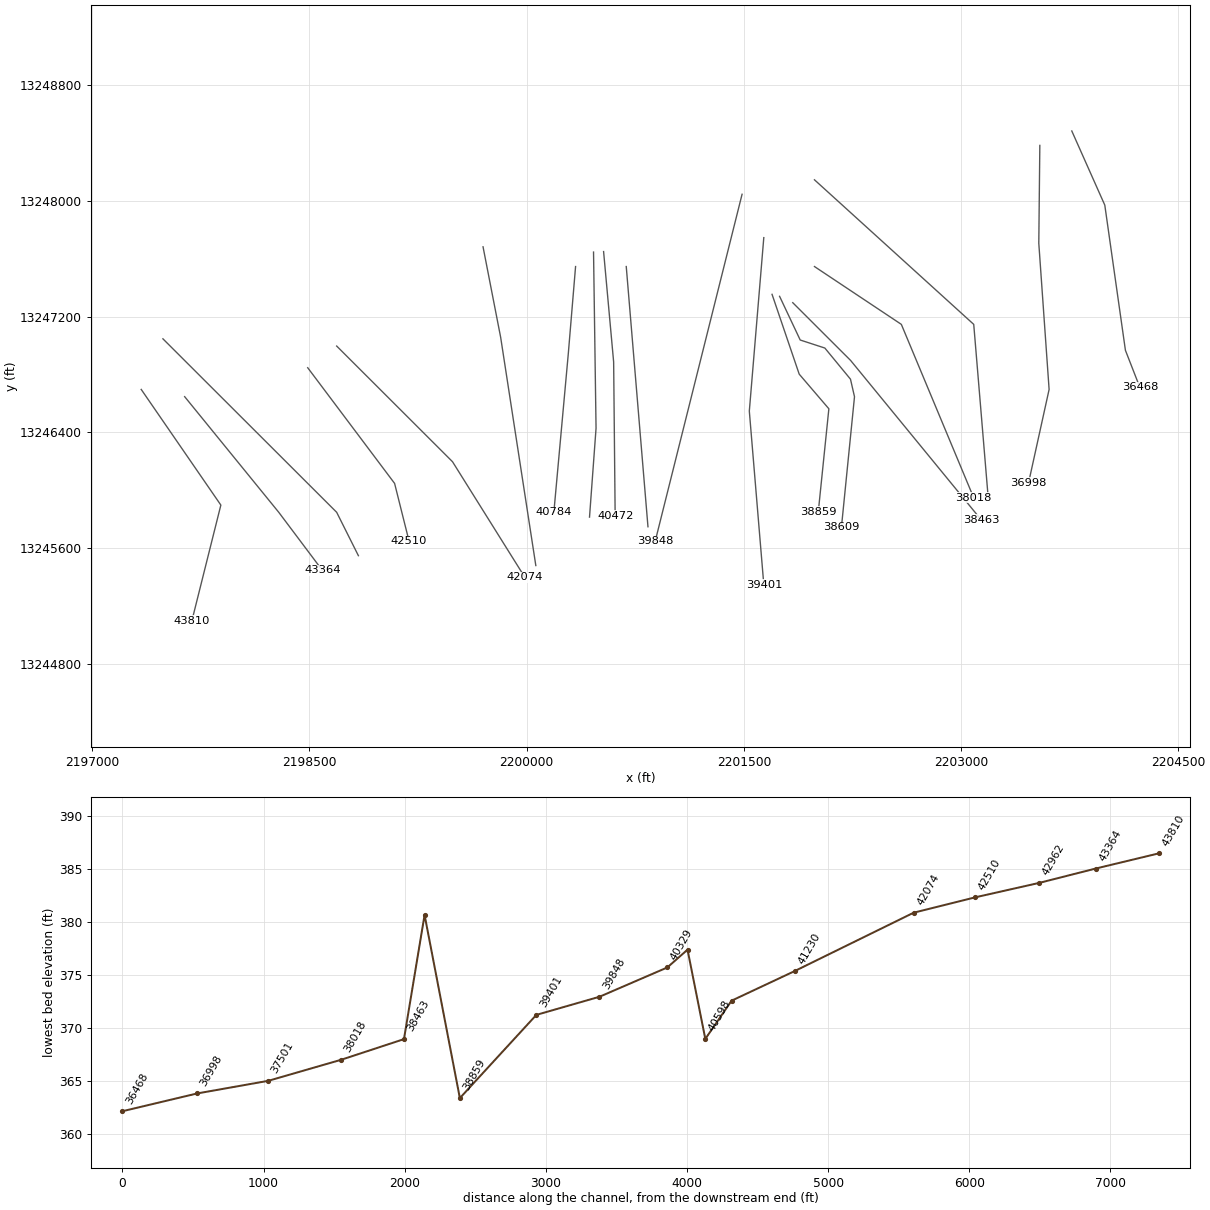
HEC-RAS study SALT BRANCH RAMIRENA CREEK.prj: SALT BRANCH RAMIRENA CREEK Base Level Engineering

--- SALT BRANCH RAMIRENA CREEK.g01 (geometry) --- (continued)

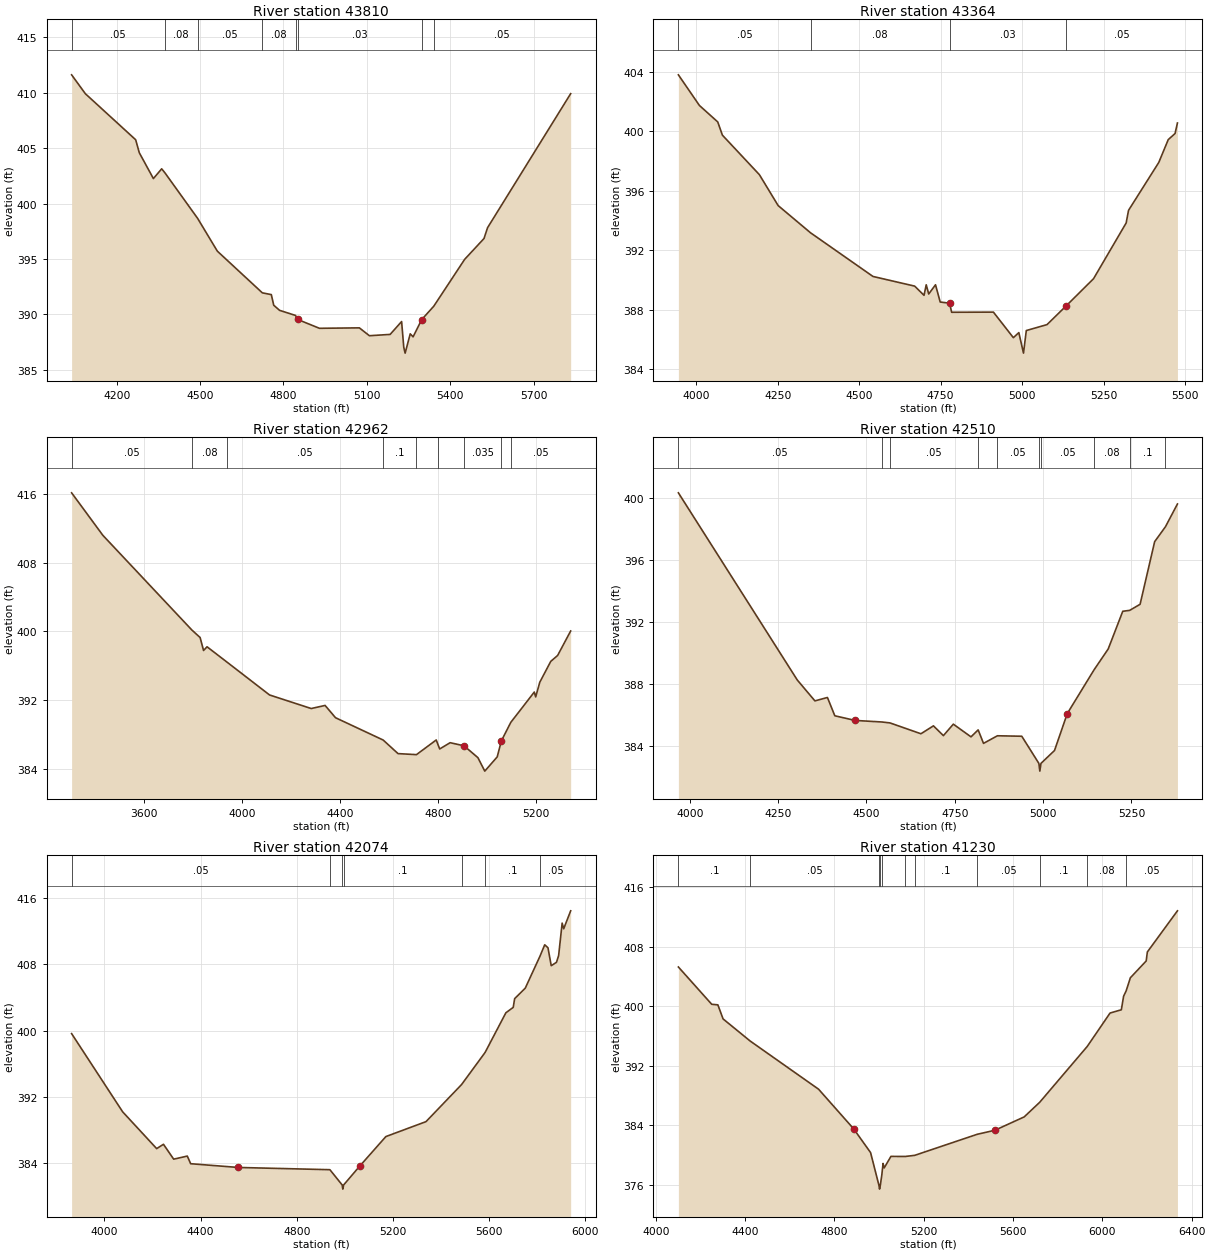
Type RM Length L Ch R = 1 ,43810   ,446,446,446
BEGIN DESCRIPTION:
SALT BRANCH RAMIRENA CREEK 52.0
END DESCRIPTION:
XS GIS Cut Line= 3
      2197337.75     13246696.82      2197887.72     13245896.85
      2197687.72     13245096.85
#Sta/Elev= 30
  4037.8  411.62  4087.1  409.92  4268.3  405.76  4281.3  404.59    4332  402.26
  4361.8  403.14  4373.7  402.77  4491.1  398.67  4562.1  395.71  4723.9  391.95
  4756.2  391.79    4765  390.83    4786  390.37  4843.4  389.91  4850.8  389.55
  4929.4  388.75    5073  388.79  5109.1  388.08  5183.8   388.2    5225  389.36
  5232.8  387.03  5237.7  386.51    5256  388.25  5266.3  387.98  5297.2  389.53
  5340.9  390.75  5451.8  394.97  5521.4  396.85  5534.3  397.83  5833.2  409.92
#Mann= 8 ,-1 , 0
  4037.8     .05       0  4373.7     .08       0  4491.1     .05       0
  4723.9     .08       0  4843.4     .05       0  4850.8     .03       0
  5297.2      .1       0  5340.9     .05       0
Bank Sta=4850.8,5297.2
XS Rating Curve= 0 ,0
Exp/Cntr=0.3,0.1

Type RM Length L Ch R = 1 ,43364   ,402,402,402
BEGIN DESCRIPTION:
SALT BRANCH RAMIRENA CREEK 51.0
END DESCRIPTION:
XS GIS Cut Line= 3
      2197637.73     13246646.85      2198287.72     13245846.85
      2198587.74     13245446.83
#Sta/Elev= 30
  3945.5  403.81  4009.9  401.75  4066.2  400.64  4080.5  399.75    4194  397.09
  4251.5  395.01  4350.8  393.18  4542.4  390.24  4670.3  389.59    4699  388.97
  4705.7  389.68  4713.4  389.06  4734.2  389.68  4748.6  388.52  4777.3  388.44
  4783.7  387.83  4911.8  387.84    4973  386.12  4989.8  386.46  5004.1  385.08
  5012.7   386.6  5076.3     387  5133.6  388.23    5219  390.09    5319  393.84
  5326.3  394.69    5419  397.91  5448.1  399.45    5469  399.86  5476.3  400.57
#Mann= 4 ,-1 , 0
  3945.5     .05       0  4350.8     .08       0  4777.3     .03       0
  5133.6     .05       0
Bank Sta=4777.3,5133.6
XS Rating Curve= 0 ,0
Exp/Cntr=0.3,0.1

Type RM Length L Ch R = 1 ,42962   ,452,452,452
BEGIN DESCRIPTION:
SALT BRANCH RAMIRENA CREEK 50.0
END DESCRIPTION:
XS GIS Cut Line= 3
      2197487.69     13247046.88      2198687.72     13245846.85
      2198837.72     13245546.86
#Sta/Elev= 30
  3307.2  416.13  3434.5  411.18  3797.1  400.15  3830.5  399.28  3844.6  397.77
  3858.8   398.2  3940.3  396.41  4113.3  392.59    4283  391.01  4339.6  391.37
    4382  389.94  4576.1  387.34  4636.6  385.76  4711.7  385.64  4792.2  387.35
    4799  386.84  4806.3   386.3  4848.7  387.03  4905.3  386.67  4961.9  385.29
  4989.9  383.72  5040.6  385.38  5057.4  387.24  5095.9   389.4  5191.6  392.93
  5197.2  392.36  5213.9  394.07  5258.6   396.5  5286.6  397.19  5339.7  400.04
#Mann= 9 ,-1 , 0
  3307.2     .05       0  3797.1     .08       0  3940.3     .05       0
  4576.1      .1       0  4711.7     .08       0    4799      .1       0
  4905.3    .035       0  5057.4     .08       0  5095.9     .05       0
Bank Sta=4905.3,5057.4
XS Rating Curve= 0 ,0
Exp/Cntr=0.3,0.1

Type RM Length L Ch R = 1 ,42510   ,436,436,436
BEGIN DESCRIPTION:
SALT BRANCH RAMIRENA CREEK 49.0
END DESCRIPTION:
XS GIS Cut Line= 3
      2198487.75     13246846.82      2199087.72     13246046.85
      2199187.73     13245646.82
#Sta/Elev= 30
  3967.9  400.31  4304.3  388.24  4354.3  386.89  4389.7  387.11  4410.6  385.93
  4467.9  385.63  4543.5  385.53  4566.6  385.47  4654.3  384.77  4689.7  385.28
  4717.9  384.65    4746  385.39    4796  384.57  4816.2  385.02  4831.4  384.15
  4870.7  384.64  4939.7  384.61    4988  382.86  4990.8  382.36    4994  382.86
  5032.3  383.69  5068.4  386.07  5144.1  388.89  5184.3  390.24  5225.5  392.67
  5245.1  392.73  5274.5  393.12  5315.7  397.16  5346.2  398.12  5380.2  399.59
#Mann= 10 ,-1 , 0
  3967.9     .05       0  4543.5      .1       0  4566.6     .05       0
  4816.2      .1       0  4870.7     .05       0    4988     .03       0
    4994     .05       0  5144.1     .08       0  5245.1      .1       0
  5346.2     .08       0
Bank Sta=4467.9,5068.4
XS Rating Curve= 0 ,0
Exp/Cntr=0.3,0.1

Type RM Length L Ch R = 1 ,42074   ,844,844,844
BEGIN DESCRIPTION:
SALT BRANCH RAMIRENA CREEK 48.0
END DESCRIPTION:
XS GIS Cut Line= 3
      2198687.69     13246996.88      2199487.72     13246196.85
      2199987.72     13245396.86
#Sta/Elev= 30
  3863.7  399.64  4075.9  390.22  4217.3  385.79  4245.6  386.31    4288  384.52
  4344.6  384.89  4358.7  383.97  4556.7  383.52  4937.5  383.25  4988.6  381.41
  4991.3  380.91  4994.6  381.41  5060.6  383.65  5170.2  387.24  5337.1  389.04
  5484.8   393.5  5582.7  397.37  5669.1  402.15  5699.7   402.8  5705.6  403.85
  5749.8  405.12  5811.3  408.99  5830.6  410.34  5844.2  409.98  5857.7  407.82
  5879.5  408.23  5888.4  409.03  5903.1  412.95  5909.6  412.27  5938.5  414.43
#Mann= 7 ,-1 , 0
  3863.7     .05       0  4937.5      .1       0  4988.6     .07       0
  4994.6      .1       0  5484.8     .08       0  5582.7      .1       0
  5811.3     .05       0
Bank Sta=4556.7,5060.6
XS Rating Curve= 0 ,0
Exp/Cntr=0.3,0.1

Type RM Length L Ch R = 1 ,41230   ,446,446,446
BEGIN DESCRIPTION:
SALT BRANCH RAMIRENA CREEK 47.0
END DESCRIPTION:
XS GIS Cut Line= 3
      2199698.59     13247683.34      2199820.11     13247058.34
      2200063.16     13245478.53
#Sta/Elev= 30
  4101.4  405.25  4250.6  400.24  4278.2  400.16  4301.6  398.27  4422.8   395.3
  4729.4  388.82  4886.5  383.49  4962.2   380.3  4999.7  375.89  5002.4  375.39
  5005.7  375.89  5012.5   377.3  5018.1  378.84  5023.1  378.24  5053.3  379.79
  5117.2  379.78  5159.7  379.93  5439.6  382.76  5518.7   383.3  5650.2   385.1
  5719.5  387.06  5932.5  394.57  6034.7  399.06  6085.3   399.5  6095.4  401.32
  6106.8  402.04  6125.7   403.8  6196.5  406.06  6201.8  407.27  6336.5   412.8
#Mann= 11 ,-1 , 0
  4101.4      .1       0  4422.8     .05       0  4999.7     .03       0
  5005.7     .05       0  5012.5      .1       0  5117.2     .05       0
  5159.7      .1       0  5439.6     .05       0  5719.5      .1       0
  5932.5     .08       0  6106.8     .05       0
Bank Sta=4886.5,5518.7
XS Rating Curve= 0 ,0
Exp/Cntr=0.3,0.1

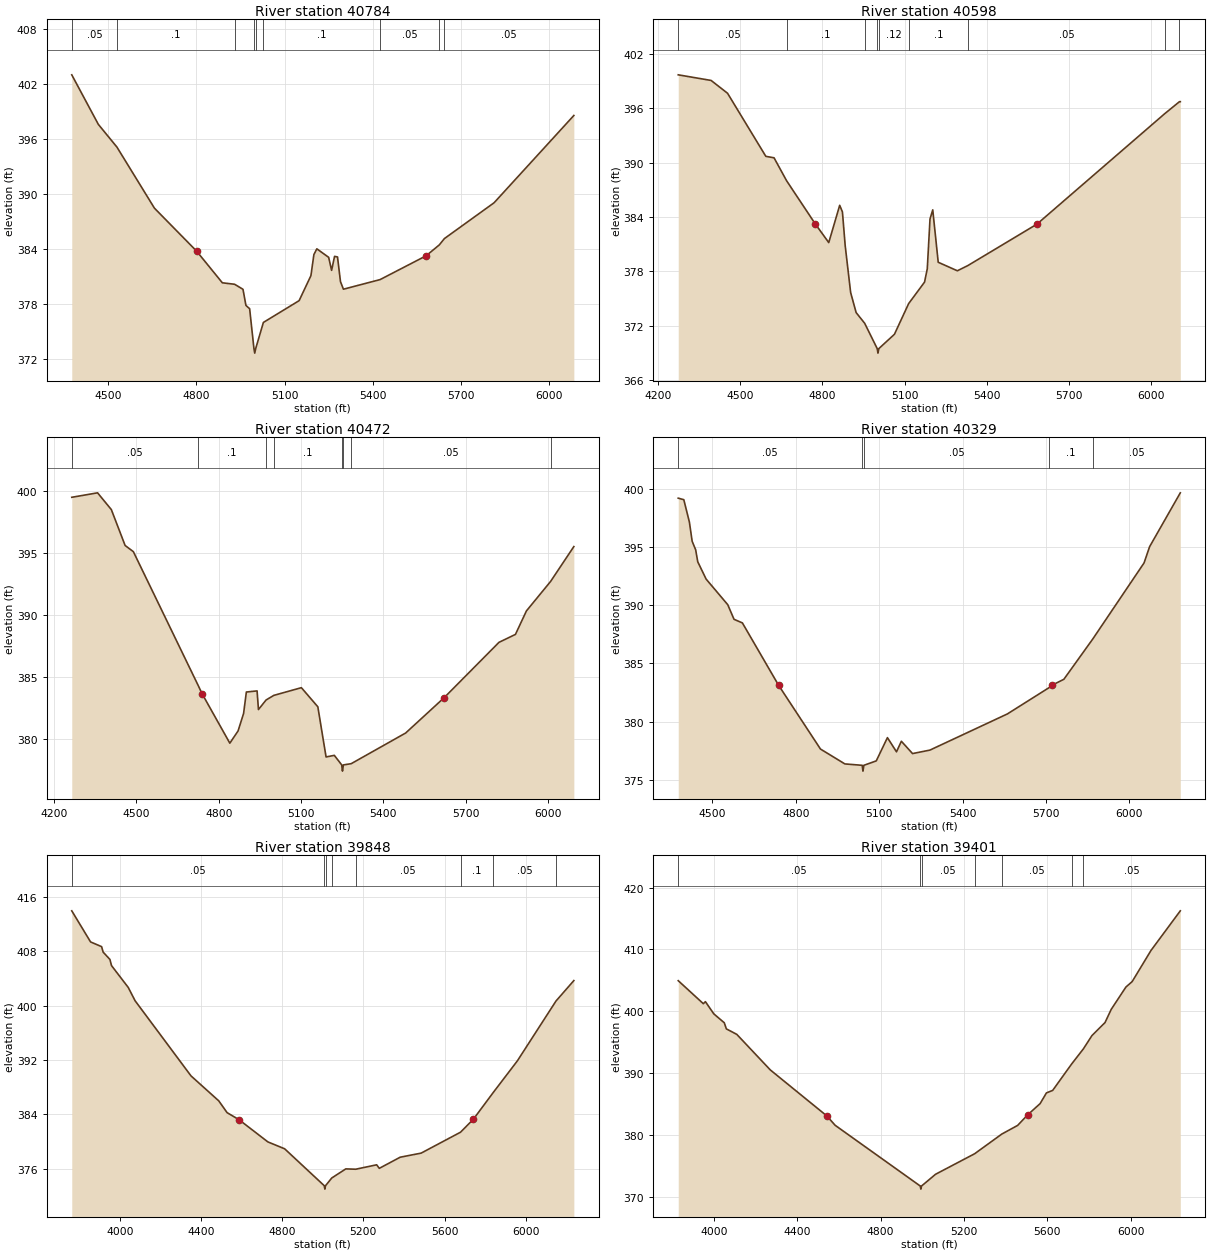
Type RM Length L Ch R = 1 ,40784   ,186,186,186
BEGIN DESCRIPTION:
SALT BRANCH RAMIRENA CREEK 46.0
END DESCRIPTION:
XS GIS Cut Line= 3
      2200337.72     13247546.85      2200287.72     13246946.85
      2200187.72     13245846.87
#Sta/Elev= 30
  4376.8  402.99  4467.1  397.58  4530.3   395.1  4657.8  388.43  4800.8  383.75
  4888.6  380.28  4930.2  380.12  4958.8  379.57  4968.8  377.81  4981.4  377.45
    4996   373.1  4998.7   372.6    5002   373.1  5028.1  375.95  5149.6  378.33
  5189.7  381.06  5199.8  383.36  5209.8  383.99    5250  383.06    5260  381.64
  5270.1  383.17  5280.1   383.1  5290.2   380.4  5300.2  379.58  5424.8  380.63
  5581.4  383.23  5626.1  384.42  5643.5  385.11  5812.3  389.02  6083.4  398.55
#Mann= 9 ,-1 , 0
  4376.8     .05       0  4530.3      .1       0  4930.2     .12       0
    4996     .07       0    5002     .12       0  5028.1      .1       0
  5424.8     .05       0  5626.1      .1       0  5643.5     .05       0
Bank Sta=4800.8,5581.4
XS Rating Curve= 0 ,0
Exp/Cntr=0.3,0.1

Type RM Length L Ch R = 1 ,40598   ,126,126,126
BEGIN DESCRIPTION:
Mapping XS a5e59eb4
END DESCRIPTION:
XS GIS Cut Line= 3
      2200461.78     13247647.04      2200479.14     13246428.25
      2200433.99     13245813.62
#Sta/Elev= 30
  4272.8  399.68    4393  399.06    4453  397.65    4593  390.69    4623  390.53
  4668.9     388    4773  383.27    4823  381.18    4863  385.29    4873  384.56
    4883  380.86    4903  375.67  4923.1  373.46  4954.3  372.28  5000.1  369.49
  5002.8  368.99  5006.1  369.49  5063.1  371.07    5115  374.45  5173.1  376.82
  5183.1  378.29  5193.1  383.78  5203.1  384.79  5223.1  379.01  5293.1  378.07
  5331.7  378.65  5583.8  383.21  6051.6  395.41    6105  396.72    6108  396.72
#Mann= 9 ,-1 , 0
  4272.8     .05       0  4668.9      .1       0  4954.3     .12       0
  5000.1     .07       0  5006.1     .12       0    5115      .1       0
  5331.7     .05       0  6051.6      .1       0    6105     .08       0
Bank Sta=4773,5583.8
XS Rating Curve= 0 ,0
Exp/Cntr=0.3,0.1

Type RM Length L Ch R = 1 ,40472   ,143,143,143
BEGIN DESCRIPTION:
Mapping XS 61c471d2
END DESCRIPTION:
XS GIS Cut Line= 3
      2200531.22     13247650.44      2200600.66     13246886.58
      2200611.08     13245824.04
#Sta/Elev= 30
  4264.6  399.47  4358.6  399.83  4408.8  398.48    4459  395.59  4489.1  395.09
  4723.7  384.39  4740.1  383.63  4840.6  379.67  4870.7  380.66  4890.8  382.07
  4900.8  383.79  4939.9  383.88  4944.9  382.38  4972.8  383.15    5001  383.52
  5101.3  384.14  5161.3   382.6  5191.3  378.56  5221.3  378.69  5248.3  377.92
  5251.1  377.42  5254.3  377.92  5282.9  378.02  5481.4  380.49  5621.4  383.33
  5821.4  387.79  5881.4  388.43  5921.4  390.32  6009.7   392.7  6094.2   395.5
#Mann= 8 ,-1 , 0
  4264.6     .05       0  4723.7      .1       0  4972.8     .12       0
    5001      .1       0  5248.3     .07       0  5254.3      .1       0
  5282.9     .05       0  6009.7      .1       0
Bank Sta=4740.1,5621.4
XS Rating Curve= 0 ,0
Exp/Cntr=0.3,0.1

Type RM Length L Ch R = 1 ,40329   ,481,481,481
BEGIN DESCRIPTION:
SALT BRANCH RAMIRENA CREEK 45.0
END DESCRIPTION:
XS GIS Cut Line= 3
      2200687.72     13247546.83      2200737.72     13246946.85
      2200837.72     13245746.87
#Sta/Elev= 30
  4376.8  399.22  4396.8  399.09  4416.9  397.17  4426.9  395.51  4439.5  394.78
    4447  393.75  4477.1  392.26  4554.9  390.06  4577.5   388.8  4607.6  388.49
    4738  383.12  4888.5  377.64  4976.3  376.36  5038.6  376.24  5041.3  375.74
  5044.6  376.24  5089.2  376.62  5129.4  378.62    5162   377.4  5179.5  378.31
  5219.7  377.25  5282.4  377.55  5560.9  380.66  5711.5  382.93  5721.4  383.13
  5764.1  383.64  5867.9   387.1  6052.6  393.65  6072.6  395.05    6183  399.68
#Mann= 5 ,-1 , 0
  4376.8     .05       0  5038.6     .03       0  5044.6     .05       0
  5711.5      .1       0  5867.9     .05       0
Bank Sta=4738,5721.4
XS Rating Curve= 0 ,0
Exp/Cntr=0.3,0.1

Type RM Length L Ch R = 1 ,39848   ,447,447,447
BEGIN DESCRIPTION:
SALT BRANCH RAMIRENA CREEK 44.0
END DESCRIPTION:
XS GIS Cut Line= 3
      2201487.71     13248046.82      2201187.72     13246846.85
      2200887.73     13245646.88
#Sta/Elev= 30
  3763.4  413.94  3856.1  409.36  3910.3  408.67    3918  407.86  3951.5  406.78
  3959.2  405.88  4041.7  402.66  4075.2  400.71  4350.9  389.64  4487.5  385.97
  4528.7  384.23    4588  383.18  4729.7  379.92  4812.2  378.91  5007.6  373.47
  5010.4  372.97  5013.6  373.47  5044.5  374.61  5113.7  375.95  5162.4   375.9
  5265.7  376.55  5278.6  376.03  5381.7  377.67  5484.8  378.27  5678.9  381.35
  5742.5  383.27  5839.2  387.16  5958.9  391.85  6149.2  400.66  6237.2  403.67
#Mann= 8 ,-1 , 0
  3763.4     .05       0  5007.6     .03       0  5013.6     .05       0
  5044.5      .1       0  5162.4     .05       0  5678.9      .1       0
  5839.2     .05       0  6149.2     .08       0
Bank Sta=4588,5742.5
XS Rating Curve= 0 ,0
Exp/Cntr=0.3,0.1

Type RM Length L Ch R = 1 ,39401   ,542,542,542
BEGIN DESCRIPTION:
SALT BRANCH RAMIRENA CREEK 43.0
END DESCRIPTION:
XS GIS Cut Line= 3
      2201637.72     13247746.85      2201537.72     13246546.85
      2201637.72     13245346.87
#Sta/Elev= 30
  3829.4  404.95  3949.8  401.23  3959.8  401.56    4000  399.59  4050.2  398.15
  4060.2  397.16  4110.4  396.27  4270.9  390.53  4541.9   383.1    4582  381.58
  4990.4  371.76  4993.2  371.26  4996.4  371.76  5063.7  373.66  5251.2  376.98
  5381.5  380.16  5457.5  381.56  5505.2  383.25  5565.4  385.09  5595.5  386.81
  5625.6  387.22  5716.1  391.47    5773  393.94  5813.7  396.07  5876.5  398.18
  5906.6  400.33  5976.8  403.92  6006.9  404.81  6097.2  409.84  6237.7  416.24
#Mann= 7 ,-1 , 0
  3829.4     .05       0  4990.4     .03       0  4996.4     .05       0
  5251.2      .1       0  5381.5     .05       0  5716.1      .1       0
    5773     .05       0
Bank Sta=4541.9,5505.2
XS Rating Curve= 0 ,0
Exp/Cntr=0.3,0.1

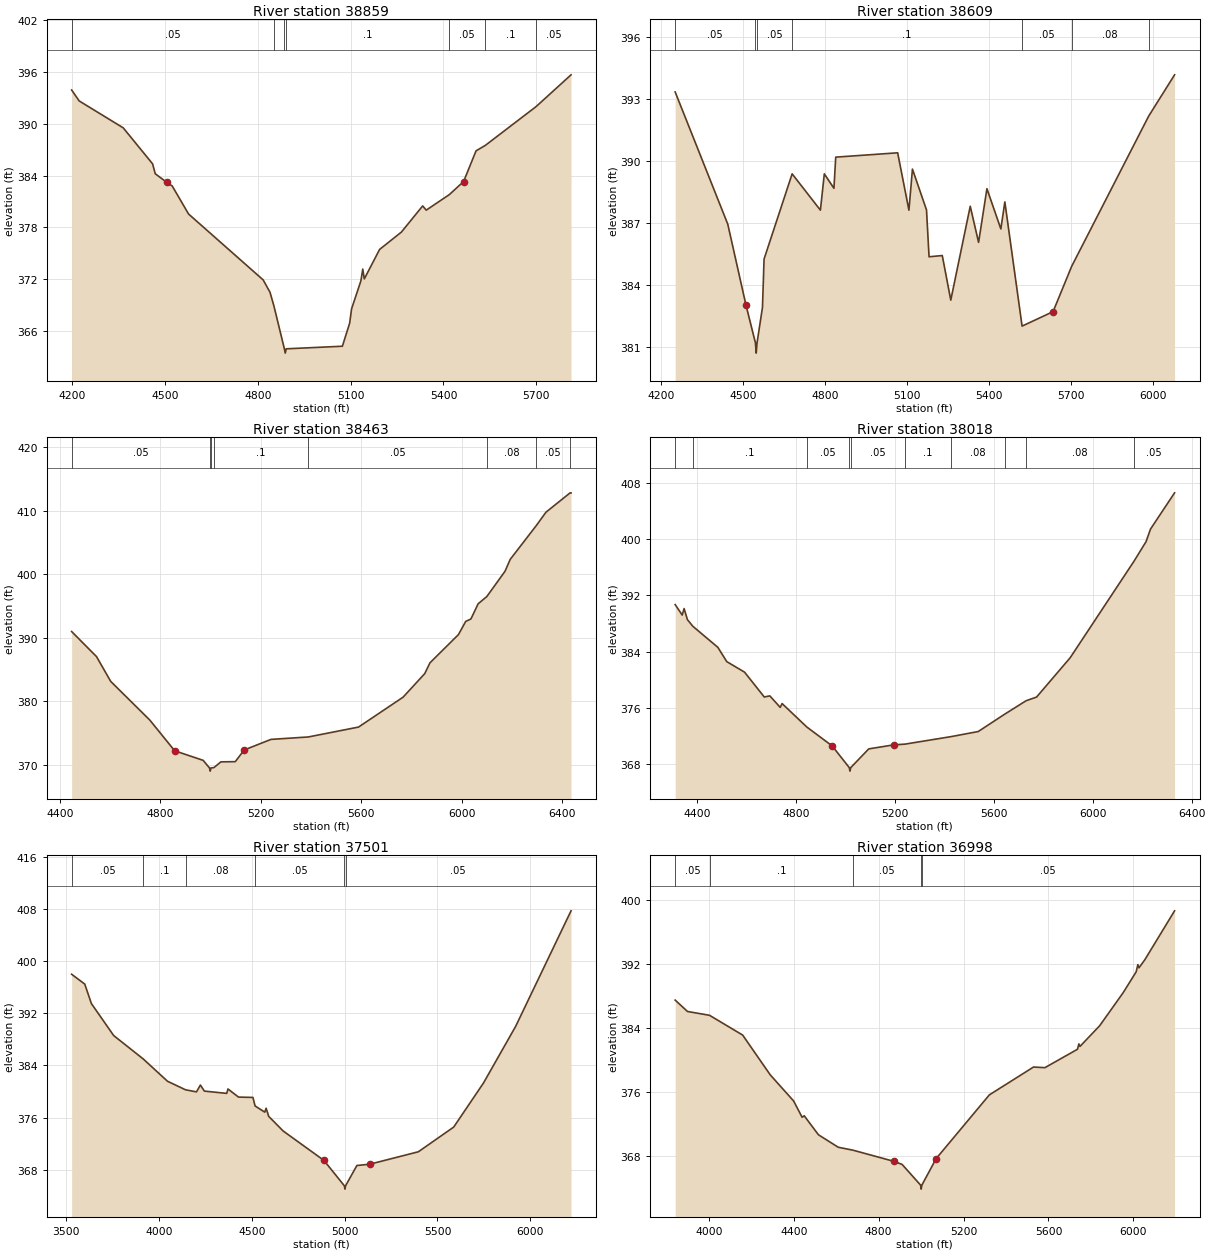
Type RM Length L Ch R = 1 ,38859   ,250,250,250
BEGIN DESCRIPTION:
SALT BRANCH RAMIRENA CREEK 42.0
END DESCRIPTION:
XS GIS Cut Line= 4
      2201694.78     13247354.59      2201882.26     13246802.56
      2202087.12     13246562.97      2202014.24     13245851.53
#Sta/Elev= 30
  4198.7  393.93  4223.1  392.66  4365.3  389.54  4460.3  385.36  4468.9  384.21
  4505.6  383.23  4523.7  382.79  4576.5  379.54  4817.6  371.89  4839.6  370.46
  4852.4  368.84    4886   363.9  4888.8   363.4    4892   363.9  5073.4   364.2
  5096.9  366.88  5103.1  368.54  5133.2  371.78  5139.2  373.15  5144.2  372.01
  5193.6  375.43  5263.9  377.44  5332.8  380.48  5344.3  379.99  5418.8  381.79
    5465  383.31  5505.2  386.87  5535.1   387.5  5699.4  392.01  5812.1  395.69
#Mann= 7 ,-1 , 0
  4198.7     .05       0  4852.4      .1       0    4886     .07       0
    4892      .1       0  5418.8     .05       0  5535.1      .1       0
  5699.4     .05       0
Bank Sta=4505.6,5465
XS Rating Curve= 0 ,0
Exp/Cntr=0.3,0.1

Type RM Length L Ch R = 1 ,38609   ,146,146,146
BEGIN DESCRIPTION:
Mapping XS 5f25c7bd
END DESCRIPTION:
XS GIS Cut Line= 6
      2201746.83     13247340.79      2201889.21     13247038.67
      2202059.35     13246983.11      2202236.43     13246767.83
      2202264.21     13246646.31      2202173.93     13245743.51
#Sta/Elev= 30
  4252.8  393.36  4445.1  386.95  4511.4  383.04  4546.1   381.2  4548.9   380.7
  4552.1   381.2  4571.9  382.92  4577.7  385.26  4680.3  389.39  4783.6  387.63
  4797.9  389.39  4833.1  388.69  4839.6   390.2    5066  390.41  5107.1  387.63
    5120  389.62  5171.4  387.64  5180.7  385.37    5229  385.43  5260.1  383.27
  5331.2  387.82  5361.7  386.07  5392.2  388.67  5443.1  386.72  5457.7  388.03
  5520.7  382.01  5633.9  382.71    5702  384.91  5983.4  392.19    6078  394.19
#Mann= 7 ,-1 , 0
  4252.8     .05       0  4546.1     .07       0  4552.1     .05       0
  4680.3      .1       0  5520.7     .05       0    5702     .08       0
  5983.4     .05       0
Bank Sta=4511.4,5633.9
XS Rating Curve= 0 ,0
Exp/Cntr=0.3,0.1

Type RM Length L Ch R = 1 ,38463   ,445,445,445
BEGIN DESCRIPTION:
SALT BRANCH RAMIRENA CREEK 41.0
END DESCRIPTION:
XS GIS Cut Line= 3
      2201837.73     13247296.85      2202237.72     13246896.85
      2203137.69     13245796.89
#Sta/Elev= 30
  4447.2  390.96  4546.2  387.01  4602.8   383.1  4758.3  377.01  4857.3  372.17
  4970.4  370.67  4995.7  369.47  4998.5  368.97  5001.7  369.47  5013.5  369.53
  5040.9  370.43  5098.3  370.46  5133.5   372.3  5240.4  373.97  5388.6  374.35
  5588.6  375.91  5765.9  380.62    5852  384.33  5872.8  386.03  5986.2  390.48
  6014.9  392.55  6035.8  392.94  6064.5  395.33  6099.2  396.48  6171.4  400.45
  6192.2  402.33  6295.8  407.65  6334.4  409.76  6430.5  412.81  6434.1  412.79
#Mann= 8 ,-1 , 0
  4447.2     .05       0  4995.7     .03       0  5001.7     .05       0
  5013.5      .1       0  5388.6     .05       0  6099.2     .08       0
  6295.8     .05       0  6430.5     .08       0
Bank Sta=4857.3,5133.5
XS Rating Curve= 0 ,0
Exp/Cntr=0.3,0.1

Type RM Length L Ch R = 1 ,38018   ,517,517,517
BEGIN DESCRIPTION:
SALT BRANCH RAMIRENA CREEK 40.0
END DESCRIPTION:
XS GIS Cut Line= 3
      2201987.72     13247546.85      2202587.72     13247146.85
      2203087.72     13245946.86
#Sta/Elev= 30
  4309.8   390.7  4338.3  389.21  4345.9  390.13  4359.4  388.56  4381.5  387.61
  4482.6  384.62  4518.6  382.59  4590.7  381.09  4670.4  377.56  4692.9  377.72
    4735  376.08  4742.5  376.63  4842.3   373.3  4945.3   370.6  5014.4  367.52
  5017.1  367.02  5020.4  367.52  5093.2  370.18  5193.4  370.75  5240.1  370.86
  5427.2  371.93  5536.3  372.65  5644.4  375.14  5730.1  377.03  5772.4  377.55
  5908.4  383.14  6166.4  396.85  6215.5  399.65  6233.4  401.43  6330.9  406.59
#Mann= 10 ,-1 , 0
  4309.8     .05       0  4381.5      .1       0  4842.3     .05       0
  5014.4     .03       0  5020.4     .05       0  5240.1      .1       0
  5427.2     .08       0  5644.4     .05       0  5730.1     .08       0
  6166.4     .05       0
Bank Sta=4945.3,5193.4
XS Rating Curve= 0 ,0
Exp/Cntr=0.3,0.1

Type RM Length L Ch R = 1 ,37501   ,503,503,503
BEGIN DESCRIPTION:
SALT BRANCH RAMIRENA CREEK 39.0
END DESCRIPTION:
XS GIS Cut Line= 3
      2201987.69     13248146.88      2203087.72     13247146.85
      2203187.72     13245946.86
#Sta/Elev= 30
  3528.8     398  3599.5  396.49  3635.3   393.5  3755.5  388.59  3914.3  385.01
  4045.4  381.58  4142.6  380.27  4201.5  379.95  4222.5     381  4244.1  380.07
  4364.4  379.72  4371.1   380.4  4427.9  379.15  4505.6   379.1  4517.3  377.79
  4569.5  376.84  4576.6  377.44  4590.7  376.19  4668.5  373.95  4888.1  369.44
  4998.6  365.53  5001.3  365.03  5004.6  365.53  5065.6  368.65  5135.9  368.86
  5396.8  370.76  5587.4  374.55    5748  381.32  5921.1     390  6219.6  407.73
#Mann= 6 ,-1 , 0
  3528.8     .05       0  3914.3      .1       0  4142.6     .08       0
  4517.3     .05       0  4998.6     .03       0  5004.6     .05       0
Bank Sta=4888.1,5135.9
XS Rating Curve= 0 ,0
Exp/Cntr=0.3,0.1

Type RM Length L Ch R = 1 ,36998   ,530,530,530
BEGIN DESCRIPTION:
SALT BRANCH RAMIRENA CREEK 38.0
END DESCRIPTION:
XS GIS Cut Line= 4
      2203544.21     13248384.81      2203537.09     13247708.12
      2203608.32     13246696.65      2203466.24     13246050.18
#Sta/Elev= 30
  3841.6  387.45  3899.6  386.03  4003.5  385.55  4159.6  383.08  4289.6  378.11
  4399.6  374.85  4439.6  372.82  4449.6     373  4516.5  370.63  4609.8  369.07
  4679.9   368.7  4870.5  367.32  4910.6  366.93  4997.8  364.34  5000.5  363.84
  5003.8  364.34    5071  367.65  5321.6  375.61  5529.7  379.09  5583.3  379.01
  5736.9  381.31  5743.4  381.98  5748.5  381.66  5841.1  384.24  5951.9  388.37
  6013.3  390.98  6021.3  391.88  6026.5  391.48  6054.3   392.5  6194.2   398.6
#Mann= 5 ,-1 , 0
  3841.6     .05       0  4003.5      .1       0  4679.9     .05       0
  4997.8     .03       0  5003.8     .05       0
Bank Sta=4870.5,5071
XS Rating Curve= 0 ,0
Exp/Cntr=0.3,0.1

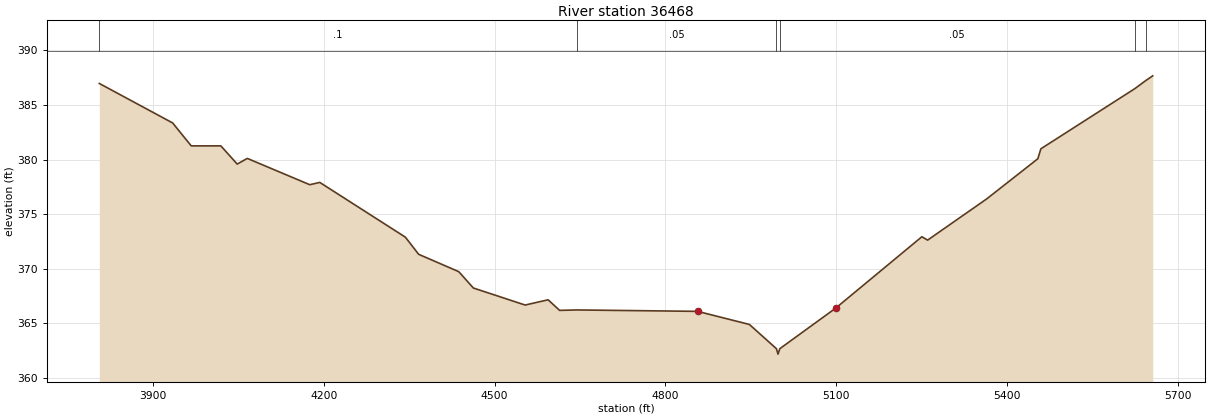
Type RM Length L Ch R = 1 ,36468   ,381,381,381
BEGIN DESCRIPTION:
SALT BRANCH RAMIRENA CREEK 37.0
END DESCRIPTION:
XS GIS Cut Line= 4
      2203765.01     13248484.57      2203992.96     13247971.67
      2204135.42     13246967.33      2204234.96     13246711.37
#Sta/Elev= 30
  3805.6  386.97  3934.4  383.35    3967  381.25    4019  381.25  4047.8  379.58
  4065.5   380.1  4175.2  377.69  4192.8   377.9  4343.2  372.88  4366.5  371.31
  4436.9  369.72  4462.6  368.22  4553.5  366.66  4593.9  367.14  4614.1  366.17
  4644.2  366.21  4856.5  366.08  4947.4  364.88  4994.9  362.66  4997.7  362.16
  5000.9  362.66  5098.9  366.37  5250.4  372.92  5260.5  372.61  5364.3  376.39
  5454.1  380.07  5459.4  380.98  5624.3  386.49  5644.6  387.27  5655.9  387.67
#Mann= 6 ,-1 , 0
  3805.6      .1       0  4644.2     .05       0  4994.9     .03       0
  5000.9     .05       0  5624.3     .08       0  5644.6      .1       0
Bank Sta=4856.5,5098.9
XS Rating Curve= 0 ,0
Exp/Cntr=0.3,0.1