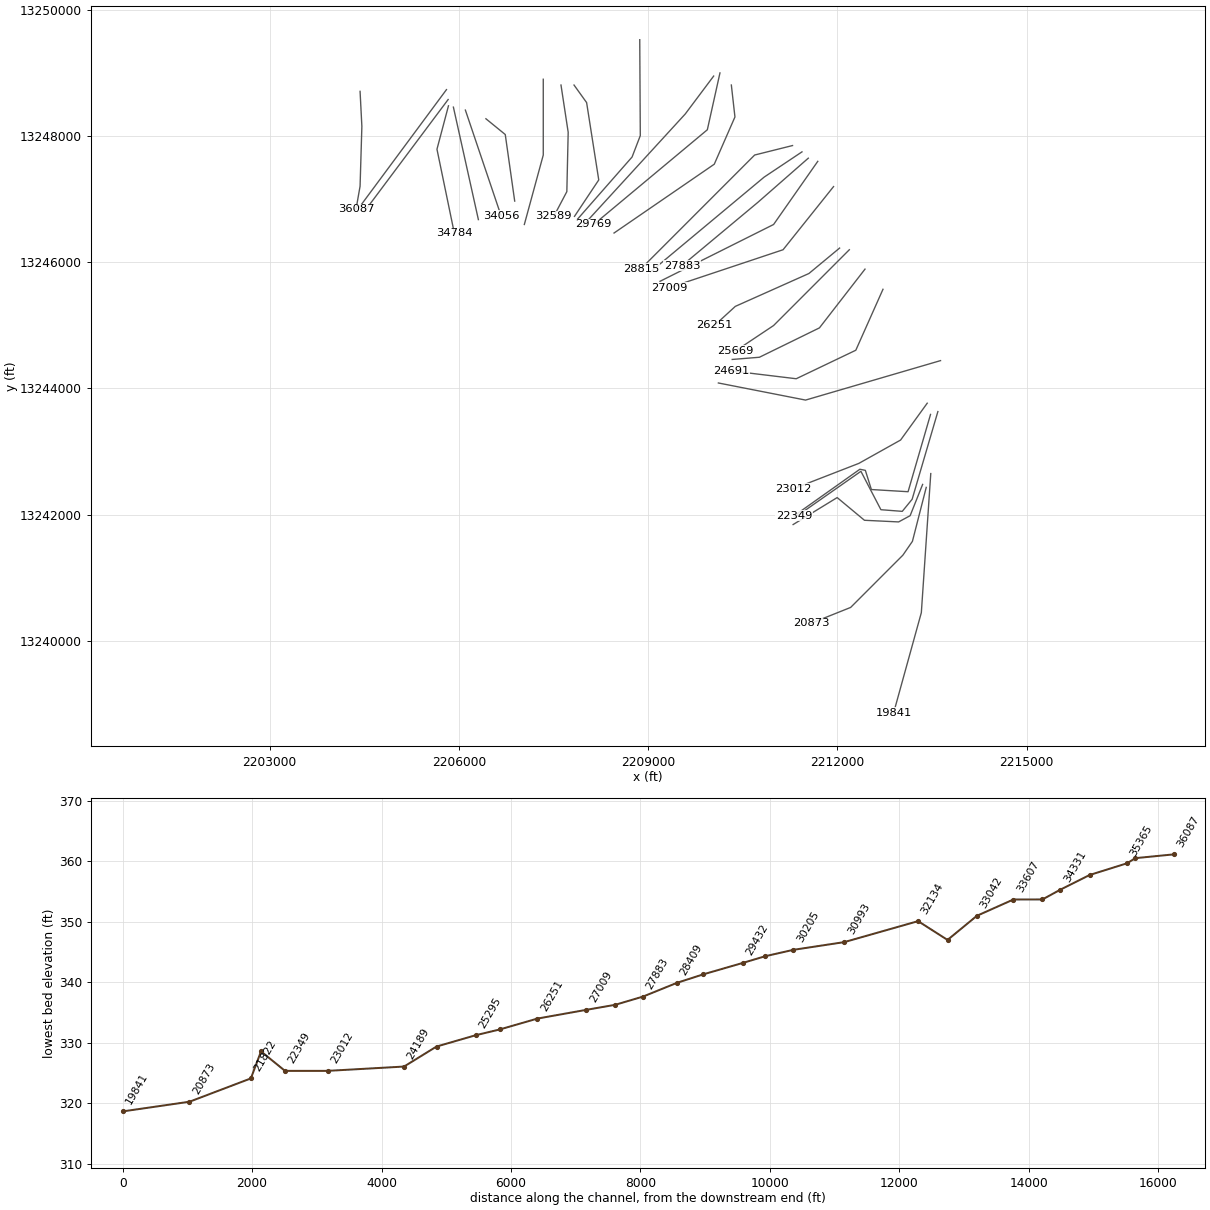
HEC-RAS study SALT BRANCH RAMIRENA CREEK.prj: SALT BRANCH RAMIRENA CREEK Base Level Engineering

--- SALT BRANCH RAMIRENA CREEK.g01 (geometry) --- (continued)

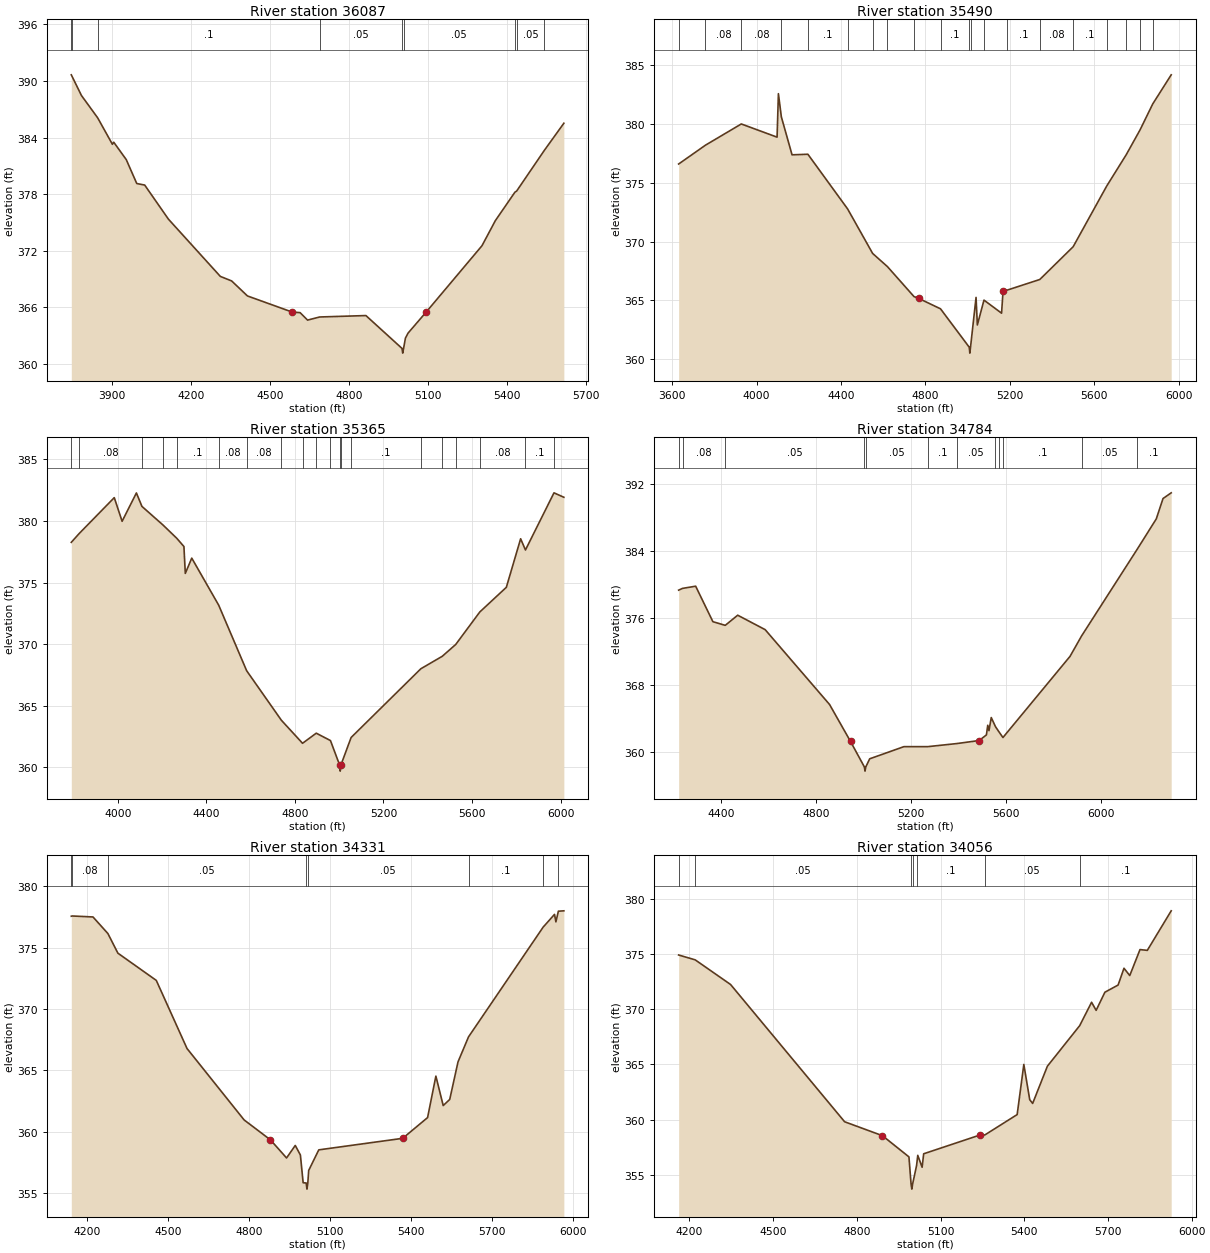
Type RM Length L Ch R = 1 ,36087   ,597,597,597
BEGIN DESCRIPTION:
SALT BRANCH RAMIRENA CREEK 36.0
END DESCRIPTION:
XS GIS Cut Line= 4
      2204434.59     13248705.36      2204463.08     13248149.75
      2204434.59     13247202.39      2204370.73     13246840.51
#Sta/Elev= 30
    3744  390.65  3745.6  390.56  3782.6  388.46  3844.3  386.09  3900.2  383.29
  3905.3  383.51  3952.8  381.67  3992.8  379.13  4022.9  378.97    4113  375.36
  4310.3  369.29  4353.3  368.81  4413.3  367.22  4583.4  365.51  4613.4  365.45
  4641.7  364.66  4687.7  364.99  4863.5  365.14  5000.6  361.66  5003.3  361.16
  5006.6  361.66  5013.6  362.75  5023.6  363.28  5093.6  365.55  5304.5  372.54
  5355.3   375.2  5429.8  378.22  5436.1  378.33  5541.8  382.66  5615.6  385.52
#Mann= 9 ,-1 , 0
    3744      .1       0  3745.6     .05       0  3844.3      .1       0
  4687.7     .05       0  5000.6     .03       0  5006.6     .05       0
  5429.8     .08       0  5436.1     .05       0  5541.8     .08       0
Bank Sta=4583.4,5093.6
XS Rating Curve= 0 ,0
Exp/Cntr=0.3,0.1

Type RM Length L Ch R = 1 ,35490   ,125,125,125
BEGIN DESCRIPTION:
SALT BRANCH RAMIRENA CREEK 35.0
END DESCRIPTION:
XS GIS Cut Line= 2
      2205803.75      13248732.6      2204413.49     13246856.34
#Sta/Elev= 30
  3630.1  376.58  3757.4  378.18  3927.2  379.98  4096.8  378.86  4103.1  382.55
  4117.1  380.58  4167.8  377.36  4242.8  377.41  4431.2  372.77  4549.9  368.99
  4620.1  367.87  4745.9  365.33  4768.8  365.17  4871.7  364.29  5007.9  361.03
  5010.6  360.53  5013.9  361.03  5040.1  365.26  5046.3  362.92  5077.7  365.03
  5161.1  363.92  5168.1   365.8  5186.4  365.87  5342.3  366.78  5500.5  369.56
  5659.2   374.7  5752.1  377.37  5817.7  379.48  5877.8  381.68  5965.3  384.15
#Mann= 20 ,-1 , 0
  3630.1     .08       0  3757.4     .08       0  3927.2     .08       0
  4117.1      .1       0  4242.8      .1       0  4431.2     .08       0
  4549.9     .08       0  4620.1      .1       0  4745.9      .1       0
  4871.7      .1       0  5007.9     .07       0  5013.9      .1       0
  5077.7     .08       0  5186.4      .1       0  5342.3     .08       0
  5500.5      .1       0  5659.2     .08       0  5752.1      .1       0
  5817.7     .08       0  5877.8      .1       0
Bank Sta=4768.8,5168.1
XS Rating Curve= 0 ,0
Exp/Cntr=0.3,0.1

Type RM Length L Ch R = 1 ,35365   ,581,581,581
BEGIN DESCRIPTION:
SALT BRANCH RAMIRENA CREEK 34.0
END DESCRIPTION:
XS GIS Cut Line= 2
      2205830.22     13248575.75      2204496.86      13246793.9
#Sta/Elev= 30
  3789.5  378.26  3824.3  378.96  3983.7  381.89  4019.1  379.97  4083.7  382.27
  4108.6  381.18  4203.1  379.68  4266.1  378.59  4298.4  377.92  4304.6  375.74
  4333.8  376.98  4455.5  373.16  4581.8  367.84  4738.7  363.82  4834.3  361.95
  4896.3  362.77  4960.5  362.17  5001.8  360.19  5004.6  359.69  5007.8  360.19
  5053.8  362.42  5368.9     368  5465.5  369.01  5526.4  369.97  5635.3  372.61
  5755.1  374.61  5819.7  378.55  5841.5  377.64  5970.4  382.28    6015  381.92
#Mann= 20 ,-1 , 0
  3789.5     .08       0  3824.3     .08       0  4108.6      .1       0
  4203.1     .08       0  4266.1      .1       0  4455.5     .08       0
  4581.8     .08       0  4738.7      .1       0  4834.3     .05       0
  4896.3      .1       0  4960.5     .05       0  5001.8     .04       0
  5007.8     .05       0  5053.8      .1       0  5368.9      .1       0
  5465.5     .08       0  5526.4      .1       0  5635.3     .08       0
  5841.5      .1       0  5970.4     .08       0
Bank Sta=5001.8,5007.8
XS Rating Curve= 0 ,0
Exp/Cntr=0.3,0.1

Type RM Length L Ch R = 1 ,34784   ,453,453,453
BEGIN DESCRIPTION:
SALT BRANCH RAMIRENA CREEK 33.0
END DESCRIPTION:
XS GIS Cut Line= 3
      2205835.38     13248476.15       2205653.1     13247788.67
      2205929.13     13246455.38
#Sta/Elev= 30
  4220.9  379.33  4237.2  379.54  4292.6   379.8    4365  375.57    4417  375.13
  4469.5  376.34  4584.9  374.62    4856  365.69  4944.2  361.28  5002.5  358.24
  5005.2  357.74  5008.5  358.24  5024.9  359.21  5168.9  360.66  5269.2  360.66
  5392.2  361.03  5485.4  361.39  5516.1  362.06  5521.7  363.21  5526.8  362.57
  5536.5  364.13  5554.1  363.05  5567.6  362.48  5585.7  361.75  5867.9  371.43
  5917.1  373.89    6150  384.18  6230.9  387.83  6259.3  390.26  6293.7  390.94
#Mann= 12 ,-1 , 0
  4220.9     .05       0  4237.2     .08       0    4417     .05       0
  5002.5     .03       0  5008.5     .05       0  5269.2      .1       0
  5392.2     .05       0  5554.1      .1       0  5567.6     .05       0
  5585.7      .1       0  5917.1     .05       0    6150      .1       0
Bank Sta=4944.2,5485.4
XS Rating Curve= 0 ,0
Exp/Cntr=0.3,0.1

Type RM Length L Ch R = 1 ,34331   ,275,275,275
BEGIN DESCRIPTION:
SALT BRANCH RAMIRENA CREEK 32.0
END DESCRIPTION:
XS GIS Cut Line= 2
      2205913.51     13248455.32      2206309.35     13246674.07
#Sta/Elev= 30
  4141.7  377.55  4144.9  377.57  4222.1  377.49  4277.3  376.14  4314.3  374.54
  4456.6  372.32  4570.4  366.77  4781.9  360.95  4879.2  359.33  4939.2  357.85
  4971.4  358.87  4990.4  358.09  5000.6  355.83  5011.9  355.81  5014.7  355.31
  5017.9  355.81  5021.1  356.83  5058.5  358.51  5369.4  359.45  5461.6  361.14
  5492.3  364.52  5519.5  362.12  5543.6  362.62  5574.3  365.68  5613.3  367.72
    5890  376.67  5931.8   377.7  5936.9  377.09  5946.1  377.96  5966.4  377.99
#Mann= 8 ,-1 , 0
  4141.7     .05       0  4144.9     .08       0  4277.3     .05       0
  5011.9     .03       0  5017.9     .05       0  5613.3      .1       0
    5890     .05       0  5946.1      .1       0
Bank Sta=4879.2,5369.4
XS Rating Curve= 0 ,0
Exp/Cntr=0.3,0.1

Type RM Length L Ch R = 1 ,34056   ,449,449,449
BEGIN DESCRIPTION:
SALT BRANCH RAMIRENA CREEK 31.0
END DESCRIPTION:
XS GIS Cut Line= 2
      2206103.29     13248408.64      2206668.73     13246736.56
#Sta/Elev= 30
  4161.6   374.9    4221  374.46  4347.7  372.23  4756.4   359.8  4891.9  358.54
  4986.9  356.62  4994.4   354.2  4997.2   353.7  5000.4   354.2  5014.3  355.84
  5018.5  356.76  5034.1  355.68  5039.7   356.9  5240.2  358.59  5259.1  358.61
  5374.7  360.45  5398.6  364.99  5419.7   361.8  5430.2  361.46    5483  364.83
  5598.7   368.5  5641.4  370.62  5657.7  369.89  5689.1  371.53  5736.4  372.18
  5757.5   373.7  5778.2  373.04  5814.9  375.39  5841.1  375.32  5926.7   378.9
#Mann= 7 ,-1 , 0
  4161.6     .08       0    4221     .05       0  4994.4     .03       0
  5000.4     .05       0  5014.3      .1       0  5259.1     .05       0
  5598.7      .1       0
Bank Sta=4891.9,5240.2
XS Rating Curve= 0 ,0
Exp/Cntr=0.3,0.1

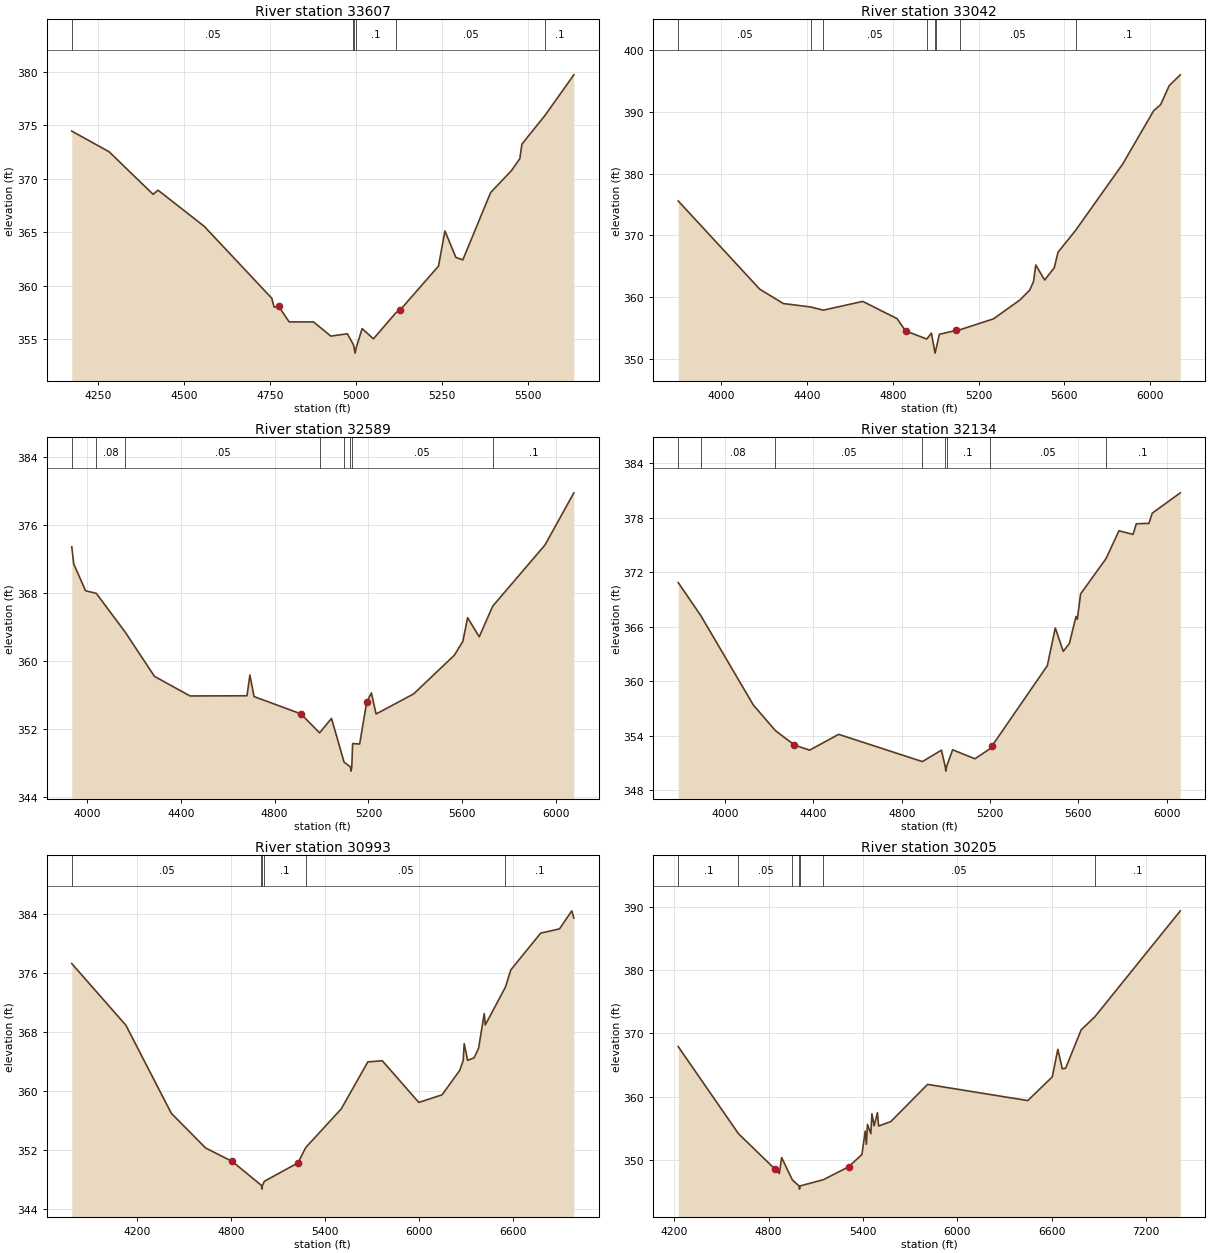
Type RM Length L Ch R = 1 ,33607   ,565,565,565
BEGIN DESCRIPTION:
SALT BRANCH RAMIRENA CREEK 30.0
END DESCRIPTION:
XS GIS Cut Line= 3
        2206429.     13248270.87      2206735.32     13248021.53
       2206884.9     13246967.36
#Sta/Elev= 30
  4174.3  374.44  4282.9  372.51  4410.8  368.53  4425.1  368.92  4559.5  365.54
  4755.8  358.82  4762.6  357.99    4776  358.05  4806.3  356.61    4877  356.61
  4927.5  355.28  4975.4   355.5  4993.2  354.48  4995.2  354.19    4998  353.69
  5001.2  354.19  5018.4  355.98  5051.4  355.03  5117.1  357.48  5129.5  357.74
  5240.6  361.83  5259.2  365.11  5291.1  362.63  5311.3  362.41  5392.1   368.7
  5452.7  370.75    5477  371.87    5483  373.22  5550.2  375.91    5634   379.7
#Mann= 6 ,-1 , 0
  4174.3     .05       0  4993.2      .1       0  4995.2     .07       0
  5001.2      .1       0  5117.1     .05       0  5550.2      .1       0
Bank Sta=4776,5129.5
XS Rating Curve= 0 ,0
Exp/Cntr=0.3,0.1

Type RM Length L Ch R = 1 ,33042   ,453,453,453
BEGIN DESCRIPTION:
SALT BRANCH RAMIRENA CREEK 29.0
END DESCRIPTION:
XS GIS Cut Line= 3
      2207337.72     13248896.83      2207337.72     13247696.85
      2207037.71     13246596.81
#Sta/Elev= 30
  3799.9  375.57  4179.9  361.32  4289.9     359  4416.5  358.45  4476.1  357.93
  4659.9  359.35  4819.9  356.56  4859.9  354.57  4958.5  353.27  4979.9  354.22
  4994.4  351.49  4997.1  350.99  5000.4  351.49  5017.2  354.04  5096.6  354.66
  5112.5  354.76  5269.4  356.53  5393.8  359.61  5438.7   361.2  5455.9  362.55
  5466.3  365.23  5507.8   362.8  5552.7  364.79    5570  367.28  5652.6  370.85
  5870.6  381.49  6015.7  390.14  6048.5  391.14  6088.2   394.2  6140.1  395.95
#Mann= 8 ,-1 , 0
  3799.9     .05       0  4416.5      .1       0  4476.1     .05       0
  4958.5      .1       0  4994.4     .07       0  5000.4      .1       0
  5112.5     .05       0  5652.6      .1       0
Bank Sta=4859.9,5096.6
XS Rating Curve= 0 ,0
Exp/Cntr=0.3,0.1

Type RM Length L Ch R = 1 ,32589   ,455,455,455
BEGIN DESCRIPTION:
SALT BRANCH RAMIRENA CREEK 28.0
END DESCRIPTION:
XS GIS Cut Line= 4
      2207618.57     13248805.09      2207732.54     13248057.15
      2207711.18     13247116.91      2207504.63     13246725.18
#Sta/Elev= 30
  3935.6  373.38  3943.9  371.38  3994.5  368.21    4040  367.91  4164.1  363.32
  4287.9  358.15  4439.6  355.84  4682.4  355.86  4694.8   358.3  4712.5  355.77
  4912.5  353.73  4991.8   351.5  5042.6   353.2  5096.2  348.06  5123.1   347.5
  5125.8     347  5129.1   347.5  5132.6  350.24  5162.6  350.19  5192.6  355.11
  5212.6   356.2  5232.6  353.72  5392.6  356.08  5566.2  360.63  5602.7  362.28
  5622.7  365.05  5672.3   362.8  5729.7   366.4  5952.9  373.61  6075.5  379.73
#Mann= 8 ,-1 , 0
  3935.6     .05       0    4040     .08       0  4164.1     .05       0
  4991.8      .1       0  5096.2     .05       0  5123.1     .07       0
  5129.1     .05       0  5729.7      .1       0
Bank Sta=4912.5,5192.6
XS Rating Curve= 0 ,0
Exp/Cntr=0.3,0.1

Type RM Length L Ch R = 1 ,32134   ,1141,1141,1141
BEGIN DESCRIPTION:
SALT BRANCH RAMIRENA CREEK 27.0
END DESCRIPTION:
XS GIS Cut Line= 4
      2207825.16     13248805.05      2208024.59     13248527.27
      2208216.91     13247302.11      2207832.51     13246725.52
#Sta/Elev= 30
  3787.2  370.87  3889.7  367.23  4127.6  357.39  4227.2  354.58  4313.7  352.98
  4382.6  352.42  4514.2  354.16  4893.6  351.16  4979.9  352.42  4997.1  350.61
  4999.9  350.11  5003.1  350.61  5030.5  352.46  5131.7  351.47  5198.3  352.55
  5210.5  352.93  5459.8  361.73  5495.8  365.88  5531.9   363.3  5559.5  364.16
  5589.6  367.14  5595.6  366.83  5610.6  369.63  5725.8  373.52  5784.3  376.58
    5848  376.18    5863  377.35  5920.1   377.4  5935.1  378.52  6062.3  380.76
#Mann= 8 ,-1 , 0
  3787.2     .05       0  3889.7     .08       0  4227.2     .05       0
  4893.6      .1       0  4997.1     .07       0  5003.1      .1       0
  5198.3     .05       0  5725.8      .1       0
Bank Sta=4313.7,5210.5
XS Rating Curve= 0 ,0
Exp/Cntr=0.3,0.1

Type RM Length L Ch R = 1 ,30993   ,788,788,788
BEGIN DESCRIPTION:
Mapping XS 8732a4e4
END DESCRIPTION:
XS GIS Cut Line= 4
      2208866.64     13249523.07      2208875.32     13248003.95
      2208745.11      13247665.4      2207868.36     13246667.12
#Sta/Elev= 30
  3781.6  377.25  4127.8  368.88  4417.8  356.94  4637.8  352.22  4807.8   350.4
  4994.8  347.14  4997.6  346.64  5000.8  347.14  5012.8   347.7  5227.8   350.2
    5278  352.29  5504.8  357.53  5674.8  363.91  5767.3  364.06  6000.7  358.41
  6149.7  359.44  6262.6  362.76  6284.4  364.09  6291.1  366.38  6312.9  364.12
  6354.6  364.46  6383.1  365.78  6419.1  370.46  6425.8  368.92  6554.9  374.07
    6589  376.39  6779.7  381.38  6900.3  381.96    6979  384.41  6992.1  383.43
#Mann= 6 ,-1 , 0
  3781.6     .05       0  4994.8     .03       0  5000.8     .05       0
  5012.8      .1       0    5278     .05       0  6554.9      .1       0
Bank Sta=4807.8,5227.8
XS Rating Curve= 0 ,0
Exp/Cntr=0.3,0.1

Type RM Length L Ch R = 1 ,30205   ,436,436,436
BEGIN DESCRIPTION:
SALT BRANCH RAMIRENA CREEK 26.0
END DESCRIPTION:
XS GIS Cut Line= 3
      2210037.72     13248946.85      2209587.72     13248346.85
      2207937.73     13246546.87
#Sta/Elev= 30
  4225.5  367.91  4608.4  354.13    4839  348.57  4868.2  347.83  4882.8  350.35
  4951.2  346.81  4993.8  345.86  4996.5  345.36  4999.8  345.86  5148.7  346.86
  5308.2  348.88  5393.3  350.85  5414.2  354.55  5421.6  352.46  5428.4   355.6
    5450  354.13  5456.8  357.28    5471  355.38  5491.9  357.46  5499.3  355.34
    5577  356.05  5810.7  361.93  6447.7  359.37  6603.4  363.12  6638.8  367.49
  6667.2  364.39  6688.2  364.49  6787.4  370.58  6872.8  372.59  7417.3  389.39
#Mann= 7 ,-1 , 0
  4225.5      .1       0  4608.4     .05       0  4951.2      .1       0
  4993.8     .07       0  4999.8      .1       0  5148.7     .05       0
  6872.8      .1       0
Bank Sta=4839,5308.2
XS Rating Curve= 0 ,0
Exp/Cntr=0.3,0.1

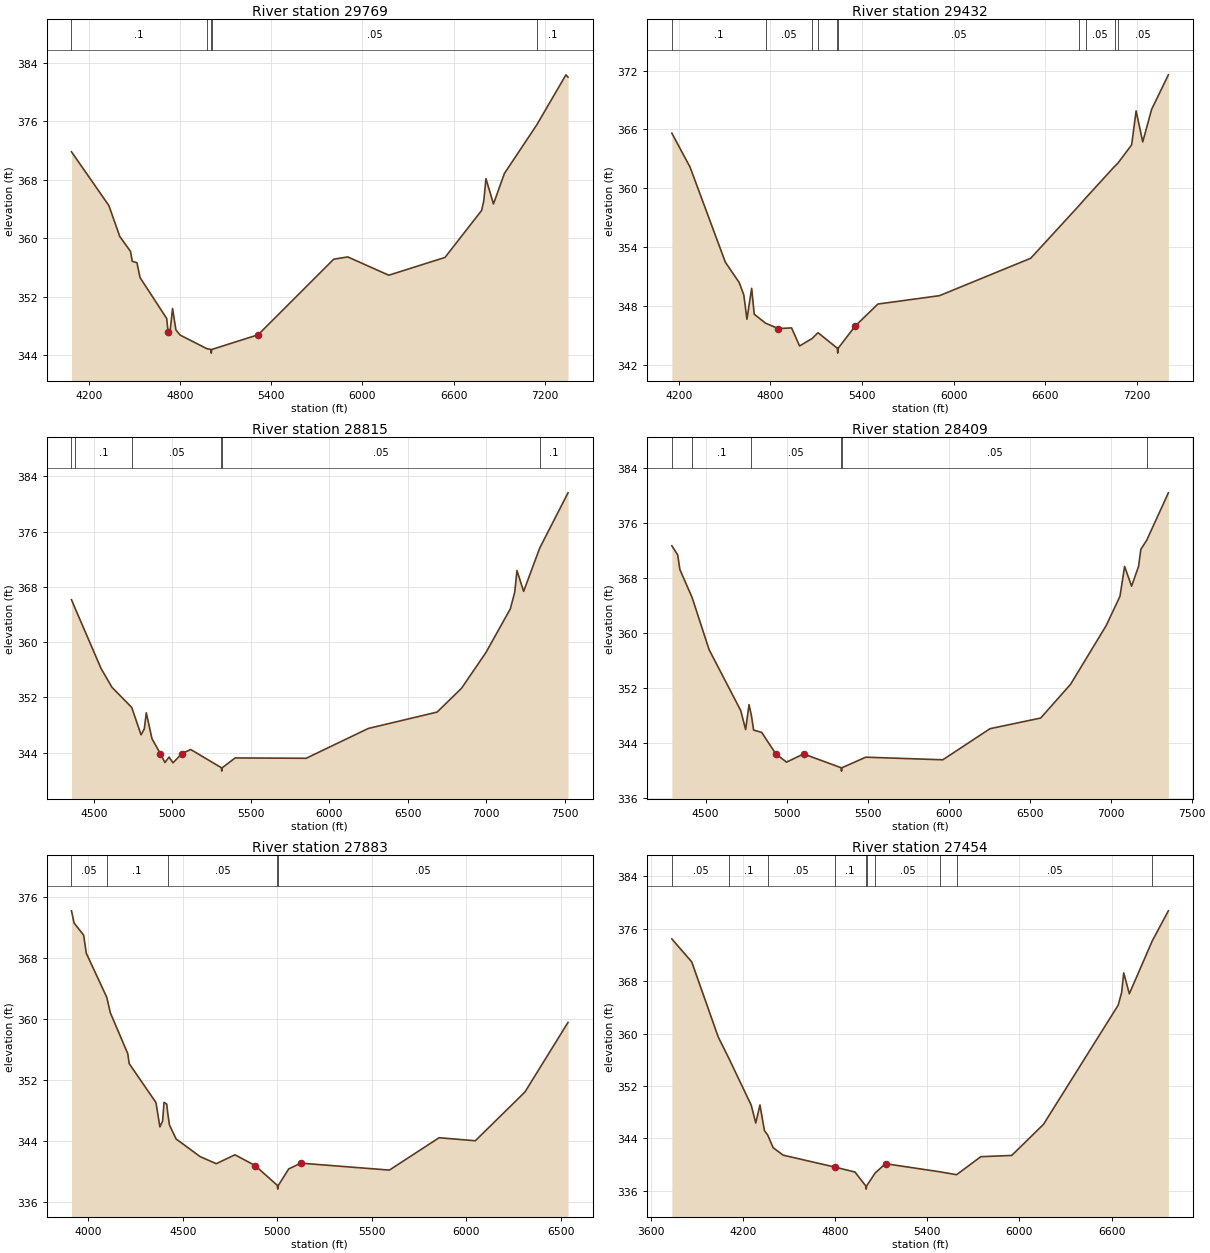
Type RM Length L Ch R = 1 ,29769   ,337,337,337
BEGIN DESCRIPTION:
SALT BRANCH RAMIRENA CREEK 25.0
END DESCRIPTION:
XS GIS Cut Line= 3
      2210137.73      13248996.9      2209937.72     13248096.85
       2208137.7     13246596.84
#Sta/Elev= 30
  4086.5  371.82  4332.4  364.47  4404.1  360.24  4474.5  358.21  4486.1  356.85
  4516.8  356.66  4537.3  354.63  4712.7  349.03  4721.7  347.24  4731.9  346.72
  4751.1   350.4  4772.9  347.49  4799.8  346.78  4977.5   344.9  5002.9   344.8
  5005.7   344.3  5008.9   344.8  5313.7  346.81    5811  357.14  5903.4  357.45
  6172.9  354.95  6542.6  357.38  6783.4   363.8  6797.7  365.11    6812  368.15
  6861.5  364.69  6933.1  368.85  7147.3  375.54  7337.9  382.34  7351.6  382.02
#Mann= 5 ,-1 , 0
  4086.5      .1       0  4977.5     .05       0  5002.9     .03       0
  5008.9     .05       0  7147.3      .1       0
Bank Sta=4721.7,5313.7
XS Rating Curve= 0 ,0
Exp/Cntr=0.3,0.1

Type RM Length L Ch R = 1 ,29432   ,617,617,617
BEGIN DESCRIPTION:
SALT BRANCH RAMIRENA CREEK 24.0
END DESCRIPTION:
XS GIS Cut Line= 4
       2210318.2     13248805.09      2210375.18     13248299.33
      2210047.53     13247551.42       2208459.3     13246461.74
#Sta/Elev= 30
  4155.3  365.62  4274.3  362.17  4505.7  352.48  4596.3  350.41  4626.5  349.15
    4647  346.67  4677.9  349.82  4694.8  347.18  4768.9  346.27  4852.6  345.72
  4939.5  345.79  4991.7  343.95  5073.2   344.7  5112.7   345.3  5238.9  343.72
  5241.6  343.22  5244.9  343.72  5354.8  345.96  5504.8  348.22  5907.7  349.07
  6505.3  352.88  6820.4  358.22  6866.4  359.03  7054.4  362.23  7075.7  362.55
  7166.3  364.43  7195.6  367.89    7239  364.73  7297.1  368.04  7406.9  371.56
#Mann= 10 ,-1 , 0
  4155.3      .1       0  4768.9     .05       0  5073.2      .1       0
  5112.7     .05       0  5238.9     .03       0  5244.9     .05       0
  6820.4      .1       0  6866.4     .05       0  7054.4      .1       0
  7075.7     .05       0
Bank Sta=4852.6,5354.8
XS Rating Curve= 0 ,0
Exp/Cntr=0.3,0.1

Type RM Length L Ch R = 1 ,28815   ,406,406,406
BEGIN DESCRIPTION:
SALT BRANCH RAMIRENA CREEK 23.0
END DESCRIPTION:
XS GIS Cut Line= 3
      2211287.76     13247846.87      2210687.72     13247696.85
      2208887.72     13245896.85
#Sta/Elev= 30
  4357.6  366.14  4380.9  364.88  4545.8  356.19  4615.3  353.46  4741.4  350.54
  4800.9  346.57  4821.5  347.42  4834.4  349.76  4870.5  346.01  4924.6  343.81
  4952.9  342.56  4979.6  343.35  5004.4  342.51    5061  343.85  5117.5  344.44
  5312.5  341.81  5315.3  341.31  5318.5  341.81  5400.4  343.22  5852.9  343.17
  6248.9  347.49  6687.3  349.86  6842.9  353.31  6998.4  358.48    7154  364.81
  7182.3  367.24  7196.4  370.36  7238.9  367.35  7341.8  373.64  7521.7  381.62
#Mann= 6 ,-1 , 0
  4357.6     .05       0  4380.9      .1       0  4741.4     .05       0
  5312.5     .03       0  5318.5     .05       0  7341.8      .1       0
Bank Sta=4924.6,5061
XS Rating Curve= 0 ,0
Exp/Cntr=0.3,0.1

Type RM Length L Ch R = 1 ,28409   ,526,526,526
BEGIN DESCRIPTION:
SALT BRANCH RAMIRENA CREEK 22.0
END DESCRIPTION:
XS GIS Cut Line= 3
      2211437.69     13247746.83      2210837.72     13247346.85
      2209037.76     13245846.89
#Sta/Elev= 30
  4292.2  372.72  4328.2   371.4  4341.7  369.27  4417.5  365.17    4522   357.6
  4717.3  348.73  4747.4  345.96  4768.4  349.59  4783.2     348  4796.9  345.89
  4846.5  345.55  4933.7  342.43  4999.8  341.22    5105  342.41  5336.4  340.41
  5339.1  339.91  5342.4  340.41    5489  341.94  5964.2  341.56  6255.8  346.09
  6568.2  347.64    6753  352.56    6973  361.12  7057.6  365.37  7086.2  369.72
  7129.2  366.84  7172.2  369.71  7186.5  372.21  7222.6  373.53  7356.3  380.43
#Mann= 6 ,-1 , 0
  4292.2     .05       0  4417.5      .1       0  4783.2     .05       0
  5336.4     .03       0  5342.4     .05       0  7222.6      .1       0
Bank Sta=4933.7,5105
XS Rating Curve= 0 ,0
Exp/Cntr=0.3,0.1

Type RM Length L Ch R = 1 ,27883   ,429,429,429
BEGIN DESCRIPTION:
SALT BRANCH RAMIRENA CREEK 21.0
END DESCRIPTION:
XS GIS Cut Line= 3
      2211537.72     13247646.85      2210737.72     13246946.85
      2209537.69     13245946.83
#Sta/Elev= 30
  3911.8  374.17  3925.6  372.57  3975.9  370.98  3990.1   368.6  4098.3  362.82
  4117.3  360.78  4209.3  355.42  4216.9  354.11  4358.4     349  4379.2   345.8
  4393.5  346.58  4401.1  349.02  4415.3  348.79  4420.6  347.64  4429.5  346.07
  4464.7  344.22  4591.8   341.9  4677.3  340.97    4776  342.14  4882.3  340.73
  4999.8  338.13  5002.5  337.63  5005.8  338.13  5060.1  340.28  5123.9  341.04
  5592.5  340.13  5855.4  344.38  6046.8  343.98  6309.1  350.38  6536.9  359.52
#Mann= 5 ,-1 , 0
  3911.8     .05       0  4098.3      .1       0  4420.6     .05       0
  4999.8     .03       0  5005.8     .05       0
Bank Sta=4882.3,5123.9
XS Rating Curve= 0 ,0
Exp/Cntr=0.3,0.1

Type RM Length L Ch R = 1 ,27454   ,445,445,445
BEGIN DESCRIPTION:
SALT BRANCH RAMIRENA CREEK 20.0
END DESCRIPTION:
XS GIS Cut Line= 3
      2211687.73     13247596.87      2210987.72     13246596.85
      2209187.75     13245696.87
#Sta/Elev= 30
  3736.4  374.44  3865.9  370.94  4038.5  359.48  4108.4  356.19    4253  349.09
  4282.7  346.36  4310.1  349.11  4339.3  345.19  4360.6  344.52    4396  342.59
  4461.4  341.45  4796.8  339.64  4798.4  339.63  4928.7  338.88  4998.8  336.77
  5001.5  336.27  5004.8  336.77  5060.7  338.74  5127.6  340.15  5479.6  338.92
  5590.5  338.47  5748.1  341.22  5949.3  341.41  6156.2  346.15  6642.5  364.33
  6664.9  366.24  6678.8  369.26  6715.2  366.08  6865.8   374.2  6969.5  378.73
#Mann= 10 ,-1 , 0
  3736.4     .05       0  4108.4      .1       0  4360.6     .05       0
  4796.8      .1       0  4998.8     .07       0  5004.8      .1       0
  5060.7     .05       0  5479.6      .1       0  5590.5     .05       0
  6865.8      .1       0
Bank Sta=4798.4,5127.6
XS Rating Curve= 0 ,0
Exp/Cntr=0.3,0.1

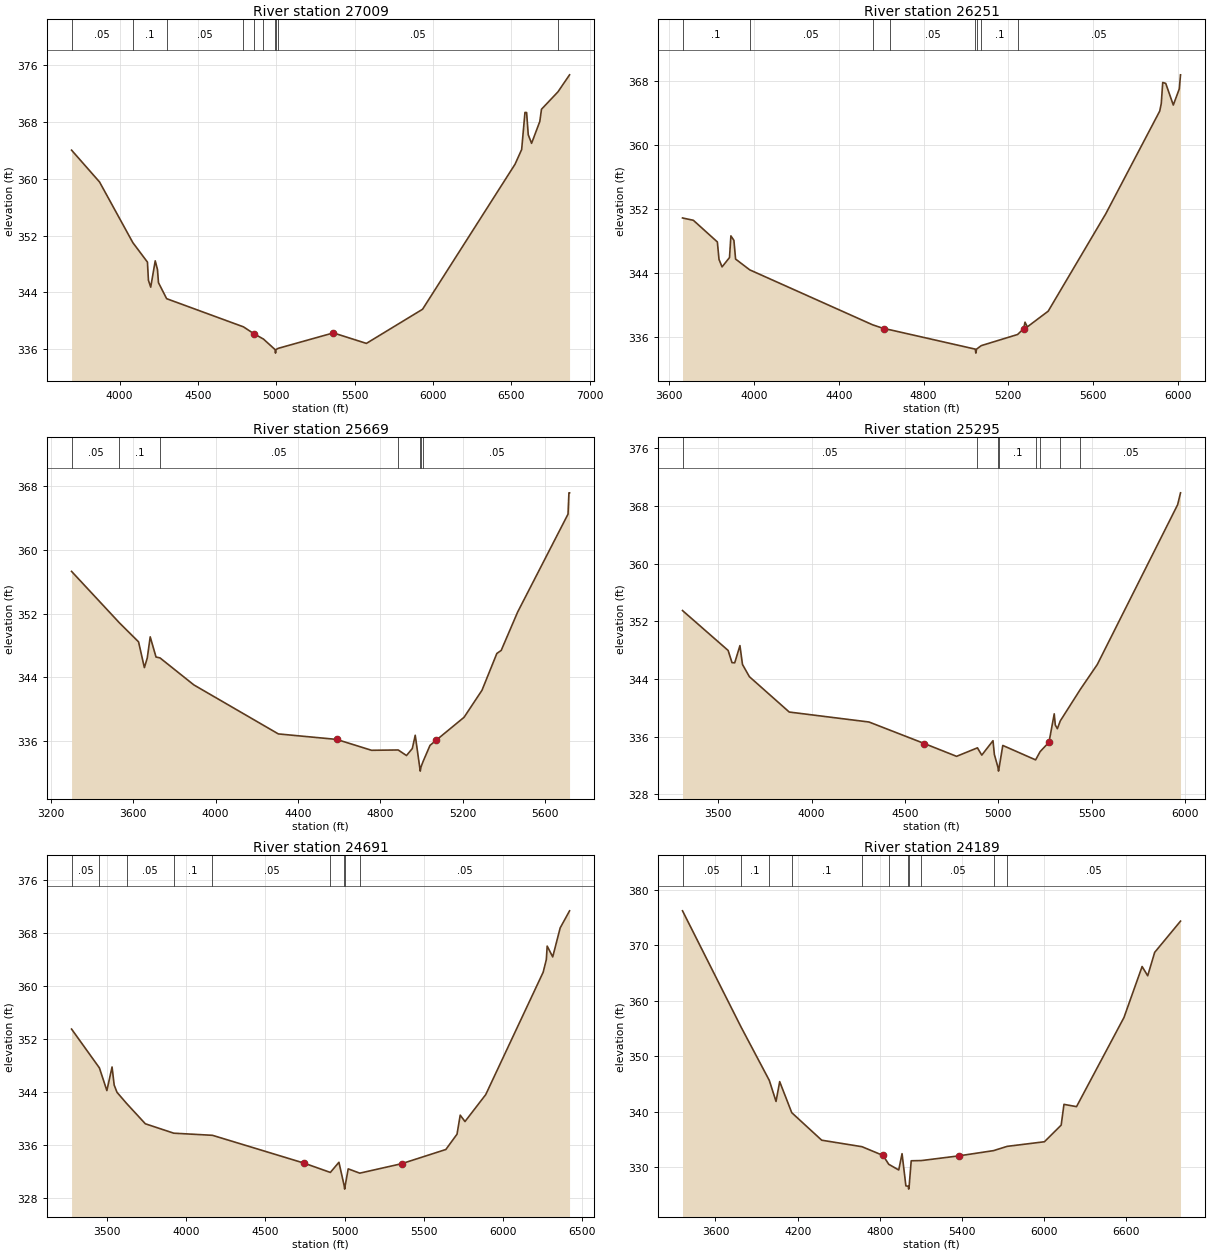
Type RM Length L Ch R = 1 ,27009   ,758,758,758
BEGIN DESCRIPTION:
SALT BRANCH RAMIRENA CREEK 19.0
END DESCRIPTION:
XS GIS Cut Line= 3
      2211937.72     13247196.86      2211137.72     13246196.85
      2209337.72     13245596.85
#Sta/Elev= 30
  3693.6  364.03  3872.1  359.55  4084.5  351.01  4177.8  348.26  4184.2  345.69
  4198.7  344.73  4227.5  348.44  4241.9  347.21  4248.3  345.36  4300.3  343.11
  4790.6  339.14  4858.2  338.16  4918.3  337.42  4992.3  335.94  4995.1  335.44
  4998.3  335.94  5011.6  336.11  5364.2  338.29  5575.1  336.81  5933.5  341.62
  6523.7  362.05  6565.9  364.12    6587  369.34  6597.5  369.33  6608.1  366.19
  6629.2  364.99  6681.9  368.08  6692.4  369.79  6797.8  372.25  6871.6  374.64
#Mann= 10 ,-1 , 0
  3693.6     .05       0  4084.5      .1       0  4300.3     .05       0
  4790.6      .1       0  4858.2     .05       0  4918.3      .1       0
  4992.3     .07       0  4998.3      .1       0  5011.6     .05       0
  6797.8      .1       0
Bank Sta=4858.2,5364.2
XS Rating Curve= 0 ,0
Exp/Cntr=0.3,0.1

Type RM Length L Ch R = 1 ,26251   ,582,582,582
BEGIN DESCRIPTION:
SALT BRANCH RAMIRENA CREEK 18.0
END DESCRIPTION:
XS GIS Cut Line= 4
       2212033.6     13246223.32      2211547.46     13245820.52
       2210380.8     13245299.68      2210054.82     13245001.44
#Sta/Elev= 30
  3662.4   350.9  3713.6  350.61  3826.9   347.9  3834.7  345.71  3849.1  344.78
  3884.2  345.95  3890.8  348.66    3905   348.1  3912.9  345.76  3979.6  344.41
    4560  337.53  4612.9  337.06  4643.6   336.9  5044.3  334.49    5047  333.99
  5050.3  334.49  5072.9  334.93  5243.9  336.32  5272.6  337.04  5279.1  337.86
    5290  337.27  5388.6  339.24  5660.3  351.42    5915  364.27  5922.4  365.22
  5929.2  367.85  5943.4  367.74  5979.2  365.03  6007.5  367.06  6013.2  368.81
#Mann= 8 ,-1 , 0
  3662.4      .1       0  3979.6     .05       0    4560      .1       0
  4643.6     .05       0  5044.3     .03       0  5050.3     .05       0
  5072.9      .1       0  5243.9     .05       0
Bank Sta=4612.9,5272.6
XS Rating Curve= 0 ,0
Exp/Cntr=0.3,0.1

Type RM Length L Ch R = 1 ,25669   ,374,374,374
BEGIN DESCRIPTION:
SALT BRANCH RAMIRENA CREEK 17.0
END DESCRIPTION:
XS GIS Cut Line= 3
      2212187.73     13246196.87      2210987.72     13244996.85
      2210387.71     13244596.85
#Sta/Elev= 30
  3300.8  357.31  3533.5  350.83  3626.1  348.45  3654.4  345.21  3668.5  346.43
  3682.7  349.08  3710.9  346.54  3730.2  346.43  3894.8  343.03  4304.9  336.87
  4587.8  336.18  4757.5  334.81  4886.9  334.85  4927.2  334.15  4955.4  335.03
  4969.6   336.7  4991.3  332.69  4994.1  332.19  4997.3  332.69    5008  333.42
  5041.4  335.43    5070  336.05  5206.7  338.96  5293.8  342.36  5365.9  346.99
    5387  347.37  5466.6  352.18  5711.5  364.51    5716  367.19    5719  367.19
#Mann= 7 ,-1 , 0
  3300.8     .05       0  3533.5      .1       0  3730.2     .05       0
  4886.9      .1       0  4991.3     .07       0  4997.3      .1       0
    5008     .05       0
Bank Sta=4587.8,5070
XS Rating Curve= 0 ,0
Exp/Cntr=0.3,0.1

Type RM Length L Ch R = 1 ,25295   ,604,604,604
BEGIN DESCRIPTION:
SALT BRANCH RAMIRENA CREEK 16.0
END DESCRIPTION:
XS GIS Cut Line= 4
      2212436.36     13245889.97      2211714.13     13244959.41
      2210762.74     13244494.13      2210332.46     13244459.43
#Sta/Elev= 30
  3307.9  353.49  3552.3  347.96  3573.1  346.27  3587.6  346.24  3615.6  348.63
  3629.2  346.02  3666.3  344.32  3879.9  339.42  4307.1  338.04  4604.3  335.05
  4776.5  333.28  4888.4  334.46  4911.6  333.45  4971.7  335.45  4979.1  333.54
  4998.6  331.73  5001.4  331.23  5004.6  331.73  5024.2  334.79    5200  332.79
  5224.5  333.94  5271.8  335.24  5299.9  339.17  5305.6  337.62  5316.7  337.11
  5332.2  338.19  5439.9  342.57  5530.6  346.01  5961.3  368.17  5976.6  369.81
#Mann= 8 ,-1 , 0
  3307.9     .05       0  4888.4      .1       0  4998.6     .07       0
  5004.6      .1       0    5200     .05       0  5224.5      .1       0
  5332.2     .08       0  5439.9     .05       0
Bank Sta=4604.3,5271.8
XS Rating Curve= 0 ,0
Exp/Cntr=0.3,0.1

Type RM Length L Ch R = 1 ,24691   ,502,502,502
BEGIN DESCRIPTION:
SALT BRANCH RAMIRENA CREEK 15.0
END DESCRIPTION:
XS GIS Cut Line= 4
      2212721.07     13245570.49      2212290.52     13244605.24
      2211346.08     13244153.85      2210312.09     13244278.76
#Sta/Elev= 30
  3275.7  353.51  3451.6  347.65  3498.7  344.23  3531.5  347.79  3544.8  345.07
  3562.6  343.97  3623.2  342.29  3741.6  339.22  3921.1   337.8  4165.7  337.48
  4745.8  333.27  4910.1  331.88  4964.3  333.41  4997.7  329.86  5000.5  329.36
  5003.7  329.86  5022.9  332.42  5095.8  331.77  5360.9   333.2  5639.6  335.34
  5710.1  337.65  5730.3  340.52  5760.5  339.56  5891.4  343.62  6254.1  362.08
  6274.2  363.99  6279.6  366.03  6314.5   364.4  6361.6  368.77  6420.9  371.35
#Mann= 9 ,-1 , 0
  3275.7     .05       0  3451.6      .1       0  3623.2     .05       0
  3921.1      .1       0  4165.7     .05       0  4910.1      .1       0
  4997.7     .07       0  5003.7      .1       0  5095.8     .05       0
Bank Sta=4745.8,5360.9
XS Rating Curve= 0 ,0
Exp/Cntr=0.3,0.1

Type RM Length L Ch R = 1 ,24189   ,1177,1177,1177
BEGIN DESCRIPTION:
Mapping XS 9508ba6a
END DESCRIPTION:
XS GIS Cut Line= 3
      2213633.25     13244440.99      2211494.39       13243816.
      2210112.58     13244086.81
#Sta/Elev= 30
  3359.5  376.22  3786.4   355.3  3993.1  345.66  4042.4  341.86    4069  345.43
  4157.2  339.83  4375.8  334.87  4669.9   333.7  4823.8  332.12  4865.3  330.53
  4938.4   329.5  4962.6  332.44  4990.5  326.65  5008.3  326.55  5011.1  326.05
  5014.3  326.55  5029.5  331.16  5104.1   331.2    5376  332.04  5630.5  332.99
  5730.3  333.76  6002.2  334.59  6124.5  337.59  6144.9  341.33  6236.6  340.92
    6583  356.99  6715.5  366.18  6756.3  364.51  6807.2  368.73  6995.9  374.36
#Mann= 11 ,-1 , 0
  3359.5     .05       0  3786.4      .1       0  3993.1     .05       0
  4157.2      .1       0  4669.9     .05       0  4865.3      .1       0
  5008.3     .07       0  5014.3      .1       0  5104.1     .05       0
  5630.5      .1       0  5730.3     .05       0
Bank Sta=4823.8,5376
XS Rating Curve= 0 ,0
Exp/Cntr=0.3,0.1

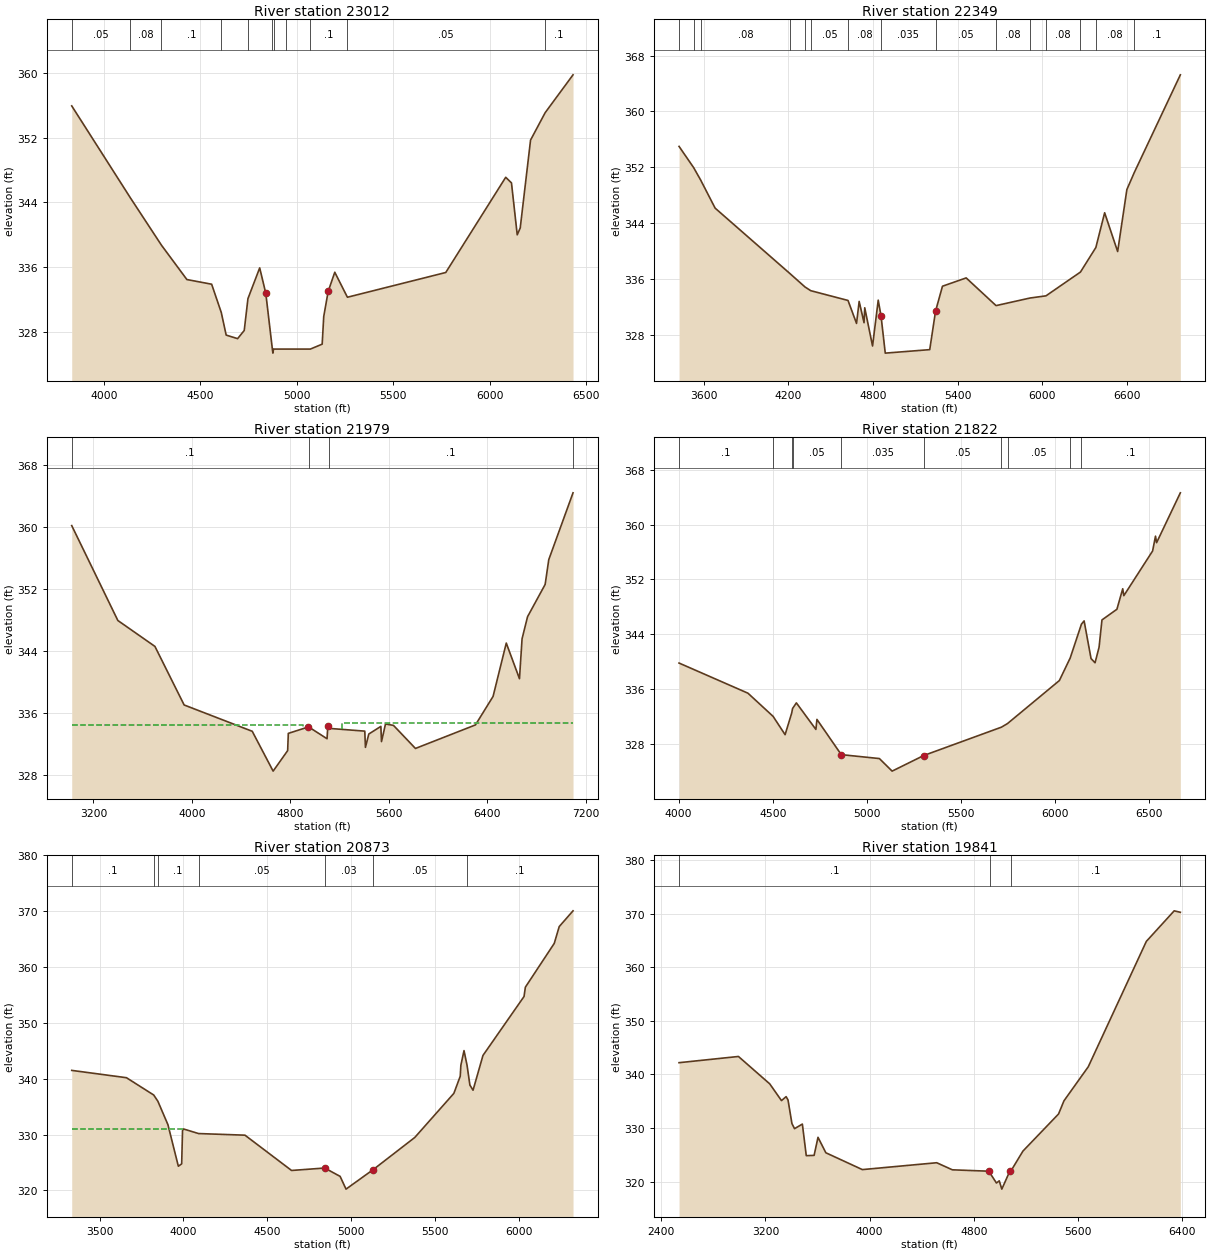
Type RM Length L Ch R = 1 ,23012   ,663,663,663
BEGIN DESCRIPTION:
Mapping XS 0192aba2
END DESCRIPTION:
XS GIS Cut Line= 4
      2213422.22     13243766.64      2213000.34      13243183.3
      2212338.88     13242813.51      2211292.34     13242407.39
#Sta/Elev= 30
  3832.3  355.91  4137.1  344.52  4297.9  338.68  4429.6  334.44  4558.1  333.86
  4608.1  330.36  4633.4  327.57  4692.7  327.13  4727.1  328.14  4746.4  332.08
  4807.3  335.88    4839  332.73    4873  325.84  4875.7  325.34    4879  325.84
  4943.7  325.84  5070.2  325.84  5131.4  326.45  5139.5  329.87  5162.4  332.96
  5196.8  335.34  5262.3  332.25  5772.5  335.31  6083.4  347.08  6113.3  346.39
  6143.2  339.97  6158.7  340.81  6212.3  351.68  6287.8  355.06  6432.6  359.75
#Mann= 11 ,-1 , 0
  3832.3     .05       0  4137.1     .08       0  4297.9      .1       0
  4608.1     .07       0  4746.4      .1       0    4873     .07       0
    4879      .1       0  4943.7     .08       0  5070.2      .1       0
  5262.3     .05       0  6287.8      .1       0
Bank Sta=4839,5162.4
XS Rating Curve= 0 ,0
Exp/Cntr=0.3,0.1

Type RM Length L Ch R = 1 ,22349   ,370,370,370
BEGIN DESCRIPTION:
Mapping XS c394869e
END DESCRIPTION:
XS GIS Cut Line= 6
      2213474.62     13243588.58      2213118.73     13242364.66
      2212537.13     13242399.38      2212441.64      13242703.2
      2212354.84     13242720.56      2211313.18     13241982.72
#Sta/Elev= 30
  3425.9  354.97  3529.4  351.93  3579.1  350.15  3681.8  346.12  4212.8  336.73
  4318.4  334.83  4359.4  334.29  4623.8  332.89  4684.1   329.6  4702.8  332.75
  4737.3   329.7  4742.3  331.84  4797.7  326.36  4837.9  332.93  4857.9  330.66
  4887.8  325.34  5203.1  325.84  5244.3  331.35  5293.4  334.93  5461.4  336.12
  5673.3  332.15  5914.3  333.24  6027.1  333.55  6271.6  336.96  6380.8  340.48
  6443.1  345.46  6535.3   339.9  6600.6  348.78  6652.2  351.18  6979.8  365.23
#Mann= 15 ,-1 , 0
  3425.9     .08       0  3529.4      .1       0  3579.1     .08       0
  4212.8     .05       0  4318.4      .1       0  4359.4     .05       0
  4623.8     .08       0  4857.9    .035       0  5244.3     .05       0
  5673.3     .08       0  5914.3     .05       0  6027.1     .08       0
  6271.6     .05       0  6380.8     .08       0  6652.2      .1       0
Bank Sta=4857.9,5244.3
XS Rating Curve= 0 ,0
Exp/Cntr=0.3,0.1

Type RM Length L Ch R = 1 ,21979   ,157,157,157
BEGIN DESCRIPTION:
Mapping XS fc04b2b8
END DESCRIPTION:
XS GIS Cut Line= 6
      2213591.04     13243633.75      2213183.04     13242244.83
      2213026.79     13242053.86      2212688.25      13242079.9
      2212371.41     13242687.88      2211317.95     13241951.32
#Sta/Elev= 30
  3023.9  360.18  3398.5  347.96  3699.9  344.62  3937.1  337.08  4490.5  333.69
  4660.2  328.56  4778.2   331.2  4783.5  333.42  4946.6  334.25    4949  334.25
  5098.2  332.73  5104.3  334.35  5110.3  334.07  5404.8  333.71  5410.1  331.62
  5437.5  333.34  5535.4  334.32  5540.6  332.36  5573.2  334.63    5638  334.45
  5816.5  331.48  6303.9  334.51  6447.1  338.18  6554.4  345.05  6661.6  340.46
  6682.6   345.6  6727.1  348.44  6870.1   352.6  6899.7   355.8  7096.7   364.4
#Mann= 4 ,-1 , 0
  3023.9      .1       0    4949    .035       0  5110.3      .1       0
  7096.7      .1       0
#XS Ineff= 2 , 0
       0 4903.41  334.56 5215.91       0  334.79
Permanent Ineff=
       T       T
Bank Sta=4946.6,5104.3
XS Rating Curve= 0 ,0
Exp/Cntr=0.3,0.1

Type RM Length L Ch R = 1 ,21822   ,949,949,949
BEGIN DESCRIPTION:
Mapping XS 314c3224
END DESCRIPTION:
XS GIS Cut Line= 6
      2213349.29     13242480.15      2213151.38     13241985.38
      2212969.09     13241886.43      2212427.43     13241912.47
      2211995.13     13242271.84      2211297.19     13241844.74
#Sta/Elev= 30
  4002.1  339.83  4368.1  335.44  4501.5  332.07  4565.5   329.4  4600.1  332.51
  4605.3  333.21  4625.3  334.03    4729  330.16  4734.6  331.62  4863.9  326.49
  5066.4  325.92    5134  324.09  5301.6  326.36  5714.5  330.49  5747.1  331.02
  6022.4  337.28    6080  340.57  6139.6  345.49  6153.9  345.97  6190.7  340.48
    6212  339.87  6233.3  342.13  6248.7  346.11  6328.1  347.66    6359  350.65
  6364.8  349.64  6517.7  356.15  6533.1  358.31    6539  357.36  6665.1  364.62
#Mann= 10 ,-1 , 0
  4002.1      .1       0  4501.5     .05       0  4600.1      .1       0
  4605.3     .05       0  4863.9    .035       0  5301.6     .05       0
  5714.5      .1       0  5747.1     .05       0    6080     .08       0
  6139.6      .1       0
Bank Sta=4863.9,5301.6
XS Rating Curve= 0 ,0
Exp/Cntr=0.3,0.1

Type RM Length L Ch R = 1 ,20873   ,1032,1032,1032
BEGIN DESCRIPTION:
Mapping XS 2a26181b
END DESCRIPTION:
XS GIS Cut Line= 5
      2213406.58     13242433.26      2213187.84     13241579.13
       2213036.8     13241360.38      2212208.68     13240532.26
      2211583.68     13240282.26
#Sta/Elev= 30
  3333.4  341.49    3660  340.18  3822.7  337.08  3847.6  335.96  3907.8  331.75
  3969.7  324.33  3989.5  324.75  3994.7   330.7  4000.7     331  4090.5  330.18
  4367.3  329.89  4645.4  323.57  4843.4  324.01  4935.3  322.51  4970.4  320.23
  5133.3  323.74  5380.8  329.48  5614.1  337.38  5652.1  340.45  5655.8  342.41
  5674.6  345.03  5692.9  342.38  5709.7  338.86  5728.5  337.94  5787.8  344.17
  6032.8  354.72  6040.8  356.39  6213.2  364.23  6242.8  367.24  6325.2  370.06
#Mann= 7 ,-1 , 0
  3333.4      .1       0  3822.7     .05       0  3847.6      .1       0
  4090.5     .05       0  4843.4     .03       0  5133.3     .05       0
  5692.9      .1       0
#XS Ineff= 2 , 0
         4004.02  331.07
Permanent Ineff=
       F       F
Bank Sta=4843.4,5133.3
XS Rating Curve= 0 ,0
Exp/Cntr=0.3,0.1

Type RM Length L Ch R = 1 ,19841   ,812,812,812
BEGIN DESCRIPTION:
Mapping XS db9d4173
END DESCRIPTION:
XS GIS Cut Line= 3
      2213478.46     13242652.13      2213328.97     13240449.59
      2212890.45     13238864.95
#Sta/Elev= 30
  2535.8   342.2  2992.1  343.36  3232.7  338.25  3322.9  335.13  3358.5  335.87
    3373  335.26  3403.1  330.86  3423.1   329.9  3483.3  330.76  3513.3  324.87
  3573.5  324.92  3603.5  328.29  3663.7  325.41  3944.3  322.27  4515.6  323.55
  4635.9  322.23  4917.1  321.97  4922.6  321.72  4974.5  319.77  4996.1  320.18
  5015.8  318.63  5078.3  322.03  5088.6  322.13  5178.1  325.72  5451.8  332.64
  5493.3  335.09  5680.1  341.44  6126.2  364.81  6340.3  370.51  6387.6  370.24
#Mann= 4 ,-1 , 0
  2535.8      .1       0  4922.6     .03       0  5088.6      .1       0
  6387.6      .1       0
Bank Sta=4917.1,5078.3
XS Rating Curve= 0 ,0
Exp/Cntr=0.3,0.1