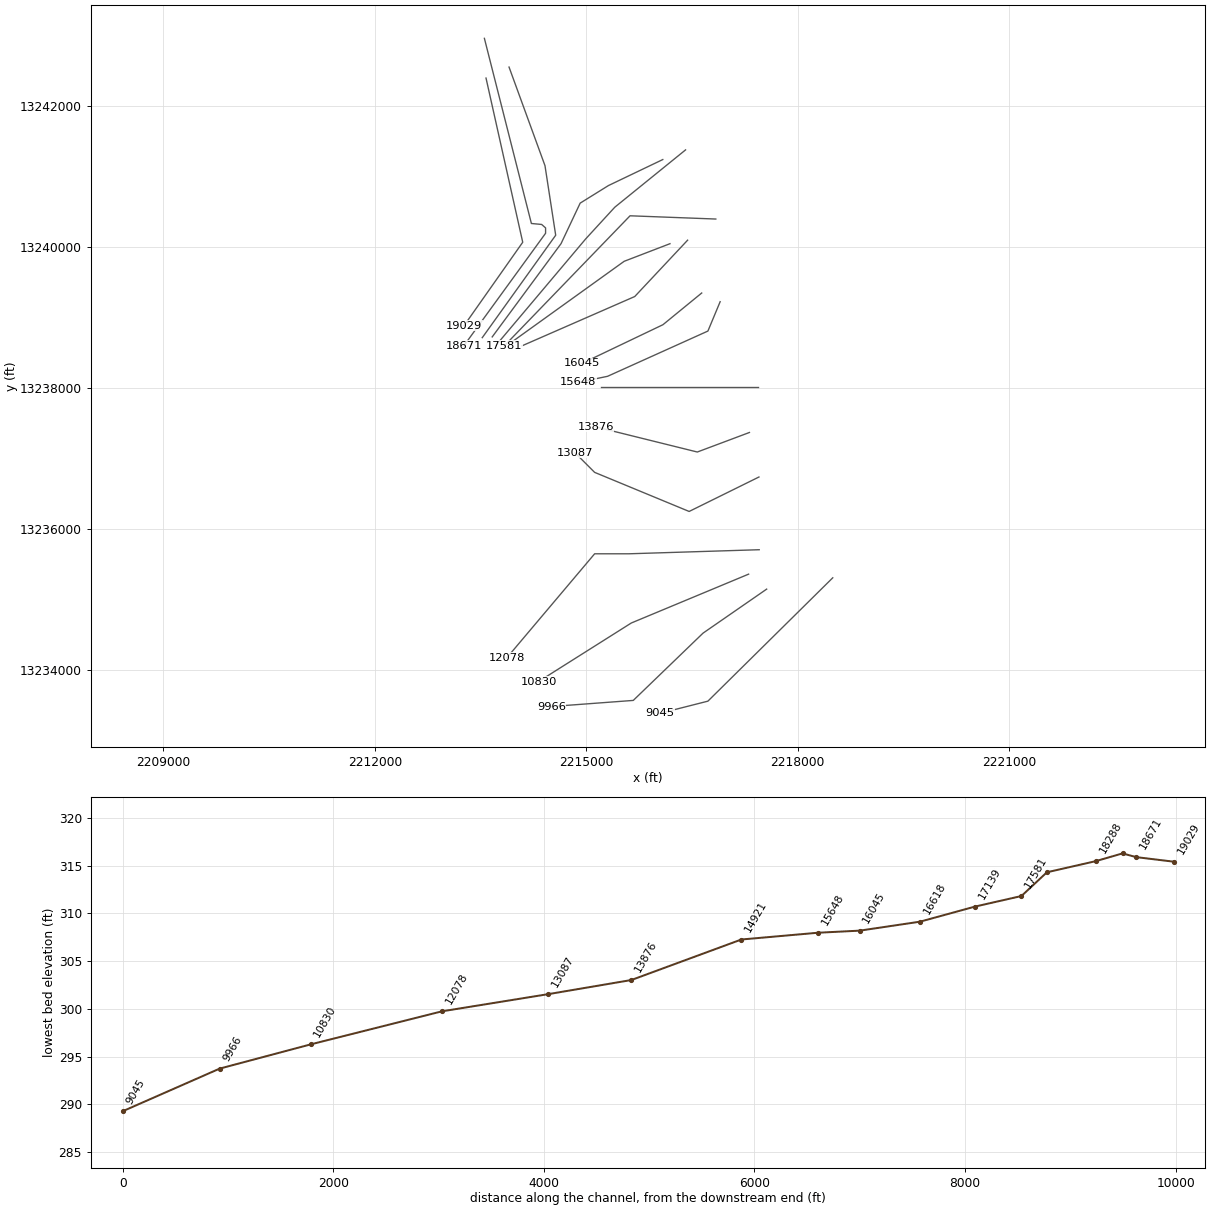
HEC-RAS study SALT BRANCH RAMIRENA CREEK.prj: SALT BRANCH RAMIRENA CREEK Base Level Engineering

--- SALT BRANCH RAMIRENA CREEK.g01 (geometry) --- (continued)

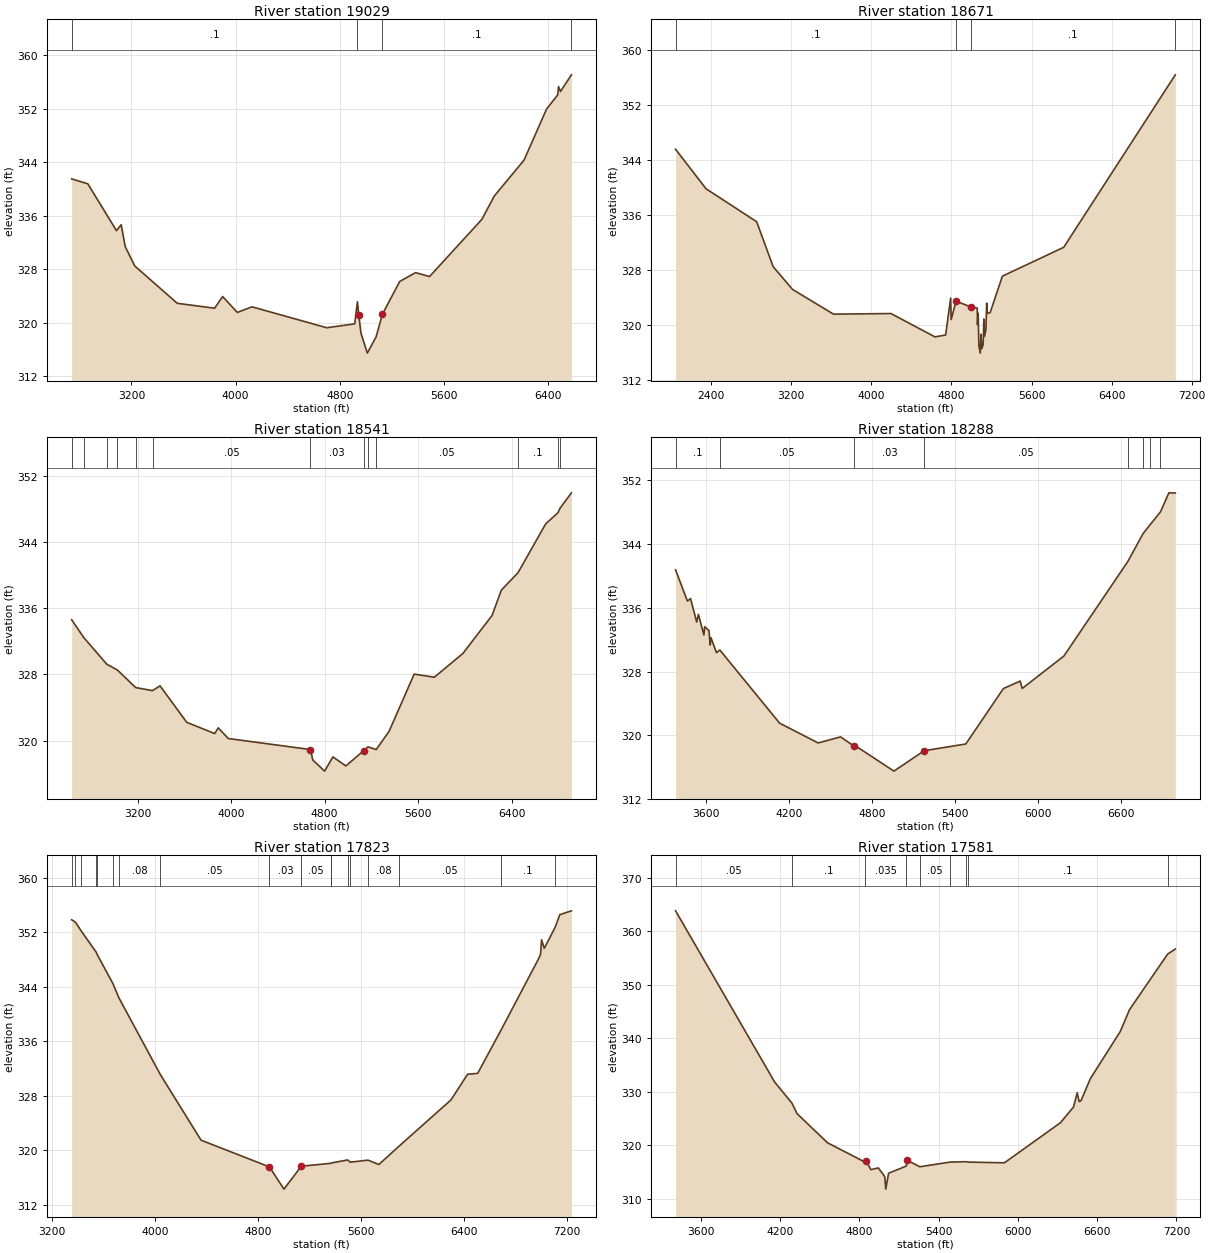
Type RM Length L Ch R = 1 ,19029   ,358,358,358
BEGIN DESCRIPTION:
Mapping XS 346c94fe
END DESCRIPTION:
XS GIS Cut Line= 3
      2213577.73     13242398.01      2214098.56      13240067.3
      2213265.21     13238882.39
#Sta/Elev= 30
  2741.5  341.51  2865.6  340.77  3085.7  333.76  3121.8  334.65  3152.5  331.39
  3226.2  328.47  3552.2  322.89  3839.1  322.15  3900.6   323.9  4013.3  321.52
    4126  322.36  4699.8  319.23  4914.7  319.81  4935.5  323.12  4945.7  321.12
  4963.2  318.39  5011.5  315.43  5078.9  317.87  5127.4  321.25  5260.1  326.15
    5382  327.48  5489.2  326.89  5890.8  335.44  5985.8  338.93  6214.9  344.32
  6387.4  351.95  6473.6  354.09  6479.7  355.32  6494.5  354.58  6578.3  357.08
#Mann= 4 ,-1 , 0
  2741.5      .1       0  4935.5    .035       0  5127.4      .1       0
  6578.3      .1       0
Bank Sta=4945.7,5127.4
XS Rating Curve= 0 ,0
Exp/Cntr=0.3,0.1

Type RM Length L Ch R = 1 ,18671   ,130,130,130
BEGIN DESCRIPTION:
Mapping XS efa57e1c
END DESCRIPTION:
XS GIS Cut Line= 6
      2213554.57     13242961.86      2214221.47     13240333.68
       2214367.3     13240319.79      2214422.86     13240271.18
      2214422.86     13240194.79      2213263.12     13238597.56
#Sta/Elev= 30
  2043.7  345.58  2348.1  339.83    2854  335.03  3018.7  328.49  3212.4  325.18
    3622  321.58  4195.5  321.67  4635.8  318.27  4741.6  318.55  4791.9  323.91
    4797   320.8    4846  323.47  4995.4  322.62  5057.5  322.47  5059.7  320.06
  5066.7  321.72  5073.8  317.04  5087.7  315.91    5095  318.66  5102.1  316.57
  5116.2   317.1  5123.3  320.88  5130.4  318.34  5144.5  319.37  5151.6  323.19
  5158.7  321.67  5186.9  321.82  5308.7  327.11  5921.4  331.31  7036.2  356.41
#Mann= 4 ,-1 , 0
  2043.7      .1       0    4846    .035       0  4995.4      .1       0
  7036.2     .05       0
#XS Ineff= 2 ,-1
 3295.45 4843.18  323.31  5037.5  7036.2   322.5
Permanent Ineff=
       T       T
Bank Sta=4846,4995.4
XS Rating Curve= 0 ,0
Exp/Cntr=0.3,0.1

Type RM Length L Ch R = 1 ,18541   ,253,253,253
BEGIN DESCRIPTION:
SALT BRANCH RAMIRENA CREEK 13.0
END DESCRIPTION:
XS GIS Cut Line= 4
      2213904.36     13242554.09      2214414.35     13241154.33
      2214566.26     13240166.92      2213524.61     13238712.95
#Sta/Elev= 30
  2634.8   334.6  2738.4  332.45  2935.1  329.23  3025.8  328.53  3182.8   326.4
    3327  326.03  3391.2  326.61  3619.8   322.2    3859  320.84  3889.6  321.53
    3976  320.24  4678.5  318.91  4698.7  317.65  4799.7   316.3  4870.7  318.02
    4982  316.93    5136  318.79  5170.4  319.23  5241.7  318.91  5352.1  321.12
  5566.5  328.03  5738.8  327.65  5983.4  330.52  6232.8  335.11  6312.6  338.18
  6455.1  340.28  6692.2  346.19  6798.1  347.55  6814.6  348.07  6912.2  349.94
#Mann= 13 ,-1 , 0
  2634.8      .1       0  2738.4     .05       0  2935.1      .1       0
  3025.8     .05       0  3182.8      .1       0    3327     .05       0
  4678.5     .03       0    5136     .05       0  5170.4      .1       0
  5241.7     .05       0  6455.1      .1       0  6798.1     .05       0
  6814.6      .1       0
Bank Sta=4678.5,5136
XS Rating Curve= 0 ,0
Exp/Cntr=0.3,0.1

Type RM Length L Ch R = 1 ,18288   ,465,465,465
BEGIN DESCRIPTION:
Mapping XS f83ecd10
END DESCRIPTION:
XS GIS Cut Line= 5
      2216085.34     13241241.13      2215314.96     13240872.21
      2214913.48     13240622.65      2214642.21     13240047.56
      2213665.63     13238723.74
#Sta/Elev= 30
  3383.5  340.77  3469.2  336.84  3491.7  337.16  3536.1  334.21  3548.3  335.18
  3588.1  332.59  3593.6  333.62  3624.8  333.14  3633.4  331.32    3639  332.25
  3678.7  330.37  3703.1   330.7  4134.8  321.51  4412.9  319.03  4574.6  319.79
  4669.1  318.66    4675  318.75  4959.8  315.49  5178.3  318.05  5478.9   318.9
  5750.3  325.86  5871.4   326.8    5886  325.87  6186.8  329.94  6647.5  341.79
  6758.7  345.32  6806.4  346.37  6884.2  348.05  6944.8  350.44  6991.3  350.42
#Mann= 8 ,-1 , 0
  3383.5      .1       0  3703.1     .05       0    4675     .03       0
  5178.3     .05       0  6647.5      .1       0  6758.7     .05       0
  6806.4      .1       0  6884.2     .05       0
#XS Ineff= 2 , 0
          4575.4  319.76
Permanent Ineff=
       F       F
Bank Sta=4669.1,5178.3
XS Rating Curve= 0 ,0
Exp/Cntr=0.3,0.1

Type RM Length L Ch R = 1 ,17823   ,242,242,242
BEGIN DESCRIPTION:
SALT BRANCH RAMIRENA CREEK 12.0
END DESCRIPTION:
XS GIS Cut Line= 4
      2216408.71     13241378.49      2215404.46     13240564.53
      2214992.18     13240115.25      2213716.66     13238601.05
#Sta/Elev= 30
  3354.5  353.82    3384  353.47  3427.2  352.22  3546.9  349.02  3550.6   348.8
    3674   344.5    3723  342.32  4044.1   331.1  4359.5   321.5  4890.8  317.58
    5004  314.32  5138.6  317.68  5366.6   318.1  5370.9  318.15  5499.1   318.6
  5518.1  318.27  5656.9  318.57  5741.2  317.93  5896.7   320.6  6301.8  327.41
  6430.4  331.17  6508.5  331.29    6692   337.7  6983.2  348.15  6997.5  348.78
  7005.2  350.89  7026.1  349.63  7109.3  352.67    7147  354.57  7236.8  355.13
#Mann= 18 ,-1 , 0
  3354.5     .08       0    3384     .05       0  3427.2     .08       0
  3546.9     .05       0  3550.6     .08       0    3674      .1       0
    3723     .08       0  4044.1     .05       0  4890.8     .03       0
  5138.6     .05       0  5366.6     .08       0  5370.9     .05       0
  5499.1     .08       0  5518.1     .05       0  5656.9     .08       0
  5896.7     .05       0    6692      .1       0  7109.3     .05       0
Bank Sta=4890.8,5138.6
XS Rating Curve= 0 ,0
Exp/Cntr=0.3,0.1

Type RM Length L Ch R = 1 ,17581   ,442,442,442
BEGIN DESCRIPTION:
SALT BRANCH RAMIRENA CREEK 11.0
END DESCRIPTION:
XS GIS Cut Line= 3
      2216837.69     13240396.86      2215621.17     13240442.96
      2213837.69     13238596.82
#Sta/Elev= 30
  3407.8  363.84  4158.3  331.84  4289.1   327.9  4327.7  325.94  4558.6  320.49
    4844  316.86  4851.2  317.11  4886.5  315.47  4943.1  315.79  4985.5  314.41
  4992.7  314.02  4999.4  311.83    5021   314.8  5155.3  316.14  5162.2  317.21
  5257.4  316.01  5486.1  316.88  5608.8  316.96  5623.1  316.88    5898  316.75
  6322.2  324.24  6421.2  327.17  6449.5  329.84  6463.7   328.2  6477.8  328.35
  6548.5  332.47  6774.9  341.27  6845.4  345.37  7134.1  355.76  7192.1   356.7
#Mann= 9 ,-1 , 0
  3407.8     .05       0  4289.1      .1       0    4844    .035       0
  5155.3      .1       0  5257.4     .05       0  5486.1      .1       0
  5608.8     .05       0  5623.1      .1       0  7134.1     .05       0
Bank Sta=4851.2,5162.2
XS Rating Curve= 0 ,0
Exp/Cntr=0.3,0.1

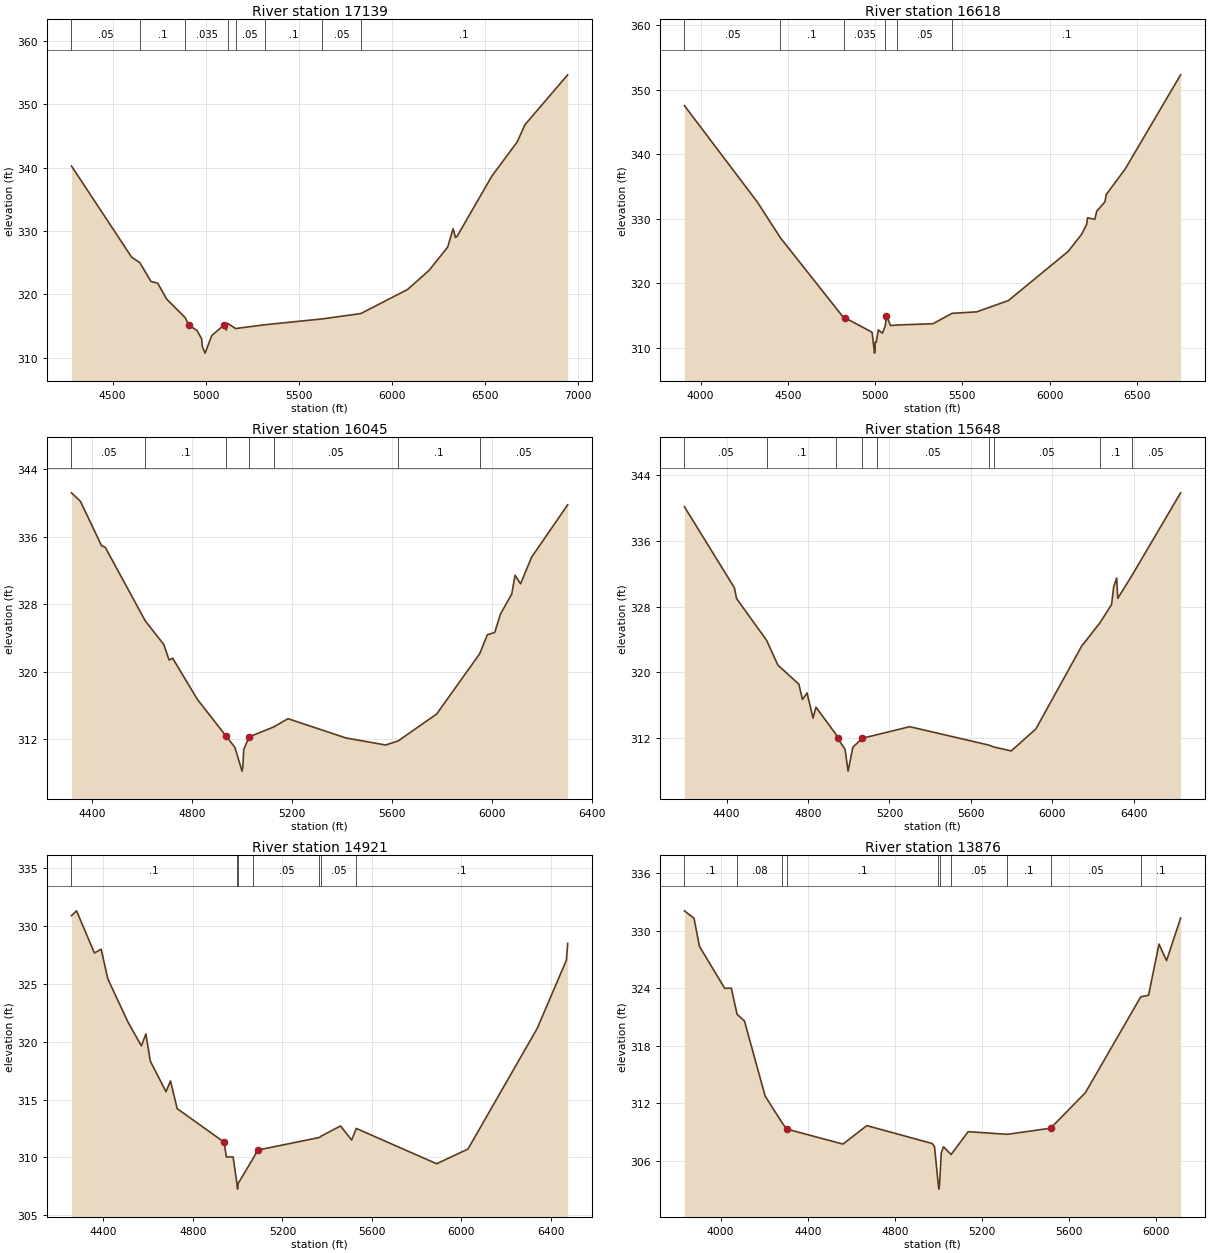
Type RM Length L Ch R = 1 ,17139   ,521,521,521
BEGIN DESCRIPTION:
SALT BRANCH RAMIRENA CREEK 10.0
END DESCRIPTION:
XS GIS Cut Line= 3
      2216187.68     13240046.84      2215537.72     13239796.85
      2213937.71     13238646.84
#Sta/Elev= 30
  4279.1  340.27  4602.6  325.87  4646.2  325.02  4706.6  322.03  4741.9  321.79
  4791.2  319.24  4889.8  316.34  4911.2  315.11    4954  314.29  4978.6  312.98
  4982.8  311.71  4997.3  310.72  5033.2   313.5  5098.2  315.14  5110.9  314.37
  5119.1  315.42  5160.9   314.6  5317.8   315.2  5625.7  316.12  5834.2  316.97
  6085.3  320.77  6200.7  323.78  6301.3  327.48  6330.1  330.37  6343.1  328.98
  6351.7  329.17  6538.3  338.67  6674.5  344.06  6716.3  346.79  6945.9  354.67
#Mann= 8 ,-1 , 0
  4279.1     .05       0  4646.2      .1       0  4889.8    .035       0
  5119.1      .1       0  5160.9     .05       0  5317.8      .1       0
  5625.7     .05       0  5834.2      .1       0
Bank Sta=4911.2,5098.2
XS Rating Curve= 0 ,0
Exp/Cntr=0.3,0.1

Type RM Length L Ch R = 1 ,16618   ,573,573,573
BEGIN DESCRIPTION:
SALT BRANCH RAMIRENA CREEK 9.0
END DESCRIPTION:
XS GIS Cut Line= 3
      2216437.72     13240096.85      2215687.72     13239296.85
      2214087.72     13238596.86
#Sta/Elev= 30
  3907.1  347.51  4324.5  332.58  4457.5  327.01  4819.8  314.62  4826.6  314.62
  4982.4  312.38  4996.3  309.14  4999.6  309.64  5000.3  310.84  5006.4  310.84
  5018.1  312.75  5041.5  312.23  5058.3   313.4  5064.9  314.97  5088.3  313.42
  5126.8   313.5  5331.1   313.7  5440.4  315.31  5582.2  315.54  5763.5  317.29
  6106.1  324.91  6182.5  327.54  6211.8   329.1  6217.2  330.12  6258.5  329.88
  6269.8  331.16  6316.2  332.57  6324.4  333.73  6433.2  337.71  6750.1  352.28
#Mann= 6 ,-1 , 0
  3907.1     .05       0  4457.5      .1       0  4819.8    .035       0
  5058.3      .1       0  5126.8     .05       0  5440.4      .1       0
Bank Sta=4826.6,5064.9
XS Rating Curve= 0 ,0
Exp/Cntr=0.3,0.1

Type RM Length L Ch R = 1 ,16045   ,397,397,397
BEGIN DESCRIPTION:
SALT BRANCH RAMIRENA CREEK 8.0
END DESCRIPTION:
XS GIS Cut Line= 3
      2216637.71     13239346.85      2216087.72     13238896.85
       2214937.7     13238346.84
#Sta/Elev= 30
  4318.6  341.21  4354.5   340.2  4439.2  334.93  4453.5  334.76  4613.7  326.03
  4688.3  323.21  4709.1  321.38  4723.4  321.59  4822.5  316.71  4937.3  312.35
  4972.5  311.02    5001   308.2  5004.2   308.7  5007.7  310.75  5029.2  312.26
  5127.9  313.44  5184.9  314.42  5417.2  312.13  5575.9   311.3  5626.1  311.79
    5780  314.98  5952.1  322.13  5982.5  324.37  6012.2  324.65  6034.9  326.82
  6080.3  329.21  6093.4  331.44  6115.5  330.42  6159.9  333.59    6304  339.79
#Mann= 7 ,-1 , 0
  4318.6     .05       0  4613.7      .1       0  4937.3    .035       0
  5029.2      .1       0  5127.9     .05       0  5626.1      .1       0
  5952.1     .05       0
Bank Sta=4937.3,5029.2
XS Rating Curve= 0 ,0
Exp/Cntr=0.3,0.1

Type RM Length L Ch R = 1 ,15648   ,727,727,727
BEGIN DESCRIPTION:
SALT BRANCH RAMIRENA CREEK 7.0
END DESCRIPTION:
XS GIS Cut Line= 4
       2216899.4      13239223.5      2216725.78     13238806.81
      2215302.17     13238164.45      2214885.55     13238077.66
#Sta/Elev= 30
  4192.4  340.17  4437.9  330.31    4449  328.98  4596.3  323.91  4651.5   320.9
    4755  318.56  4772.6  316.71  4795.3   317.5  4824.4  314.44  4839.2  315.76
  4937.9  312.44  4945.5  311.98  4981.8  310.65    4997  307.98  5020.4  310.89
  5066.6  311.98  5139.5  312.42  5299.9  313.39    5687  311.16  5713.3  310.92
  5798.9  310.44    5920  313.12  6144.7  323.19  6234.3  326.02  6291.9  328.26
  6302.1  330.38  6316.9   331.5  6322.5  329.02  6391.4  331.77  6631.2  341.86
#Mann= 9 ,-1 , 0
  4192.4     .05       0  4596.3      .1       0  4937.9    .035       0
  5066.6      .1       0  5139.5     .05       0    5687      .1       0
  5713.3     .05       0  6234.3      .1       0  6391.4     .05       0
Bank Sta=4945.5,5066.6
XS Rating Curve= 0 ,0
Exp/Cntr=0.3,0.1

Type RM Length L Ch R = 1 ,14921   ,1045,1045,1045
BEGIN DESCRIPTION:
SALT BRANCH RAMIRENA CREEK 6.0
END DESCRIPTION:
XS GIS Cut Line= 2
      2217430.33     13238014.33      2215212.03     13238014.33
#Sta/Elev= 30
  4257.1  330.87  4279.7  331.29  4359.7  327.65  4389.7  327.98  4419.7  325.41
  4509.7  321.69  4569.7  319.63  4589.7  320.67  4609.7  318.31  4679.7  315.68
  4699.7  316.61  4729.7  314.22  4939.7  311.32  4949.7  310.04  4979.7  310.05
  4996.7  307.77  4999.5  307.27  5002.7  307.77  5070.3  309.96  5089.7  310.64
  5365.9  311.73  5373.9  311.85  5459.7  312.72  5509.7  311.51  5530.3  312.51
  5889.7  309.46  6029.7  310.73  6339.7  321.16  6469.7  327.03  6475.4  328.48
#Mann= 7 ,-1 , 0
  4257.1      .1       0  4996.7     .07       0  5002.7      .1       0
  5070.3     .05       0  5365.9     .08       0  5373.9     .05       0
  5530.3      .1       0
Bank Sta=4939.7,5089.7
XS Rating Curve= 0 ,0
Exp/Cntr=0.3,0.1

Type RM Length L Ch R = 1 ,13876   ,789,789,789
BEGIN DESCRIPTION:
SALT BRANCH RAMIRENA CREEK 5.0
END DESCRIPTION:
XS GIS Cut Line= 3
      2217314.75     13237367.13      2216575.05     13237089.74
      2215131.58     13237447.72
#Sta/Elev= 30
  3833.6  332.07  3877.8  331.29  3902.7  328.36  4018.4  323.98  4048.7     324
  4075.5  321.27  4109.2  320.57  4204.2  312.73  4283.6  309.89  4304.1  309.28
    4305  309.28  4561.3  307.72  4670.6  309.65  4971.1  307.78  4981.5  307.45
  4998.6  303.52  5001.3  303.02  5004.6  303.52  5012.4   306.8  5022.7  307.44
  5057.5  306.63    5136  309.02  5315.7  308.74  5514.3  309.38  5673.9  313.09
  5928.1   323.1  5963.6  323.25  6011.7   328.6  6046.3  326.87  6110.8  331.31
#Mann= 10 ,-1 , 0
  3833.6      .1       0  4075.5     .08       0  4283.6     .05       0
  4304.1      .1       0  4998.6     .07       0  5004.6      .1       0
  5057.5     .05       0  5315.7      .1       0  5514.3     .05       0
  5928.1      .1       0
Bank Sta=4305,5514.3
XS Rating Curve= 0 ,0
Exp/Cntr=0.3,0.1

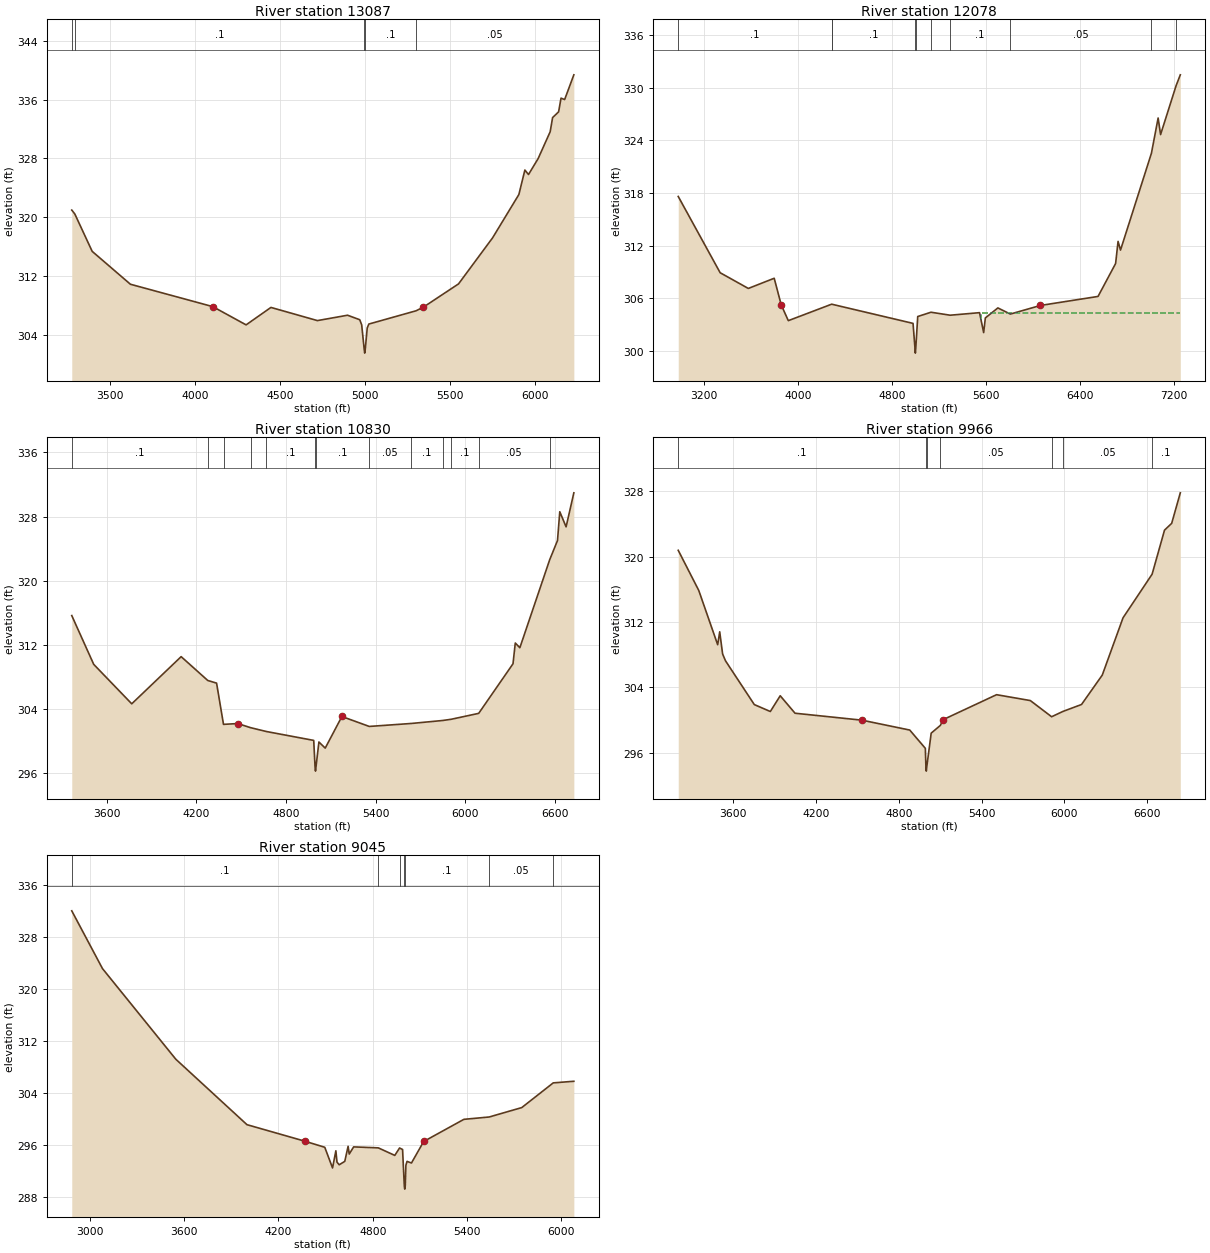
Type RM Length L Ch R = 1 ,13087   ,1009,1009,1009
BEGIN DESCRIPTION:
Mapping XS cc2fdbcf
END DESCRIPTION:
XS GIS Cut Line= 4
      2217449.82     13236735.07      2216459.47     13236246.05
      2215118.81     13236800.81      2214842.05     13237077.57
#Sta/Elev= 30
  3278.3  320.98  3296.2  320.45  3398.1  315.37  3622.6   310.9  4105.9  307.86
  4301.5  305.38  4447.3  307.75  4720.2  305.96  4896.8  306.69  4968.5  306.08
  4979.9  305.38  4994.8  302.04  4997.6  301.54  5000.8  302.04  5012.4  304.95
  5021.7  305.49  5298.6  307.29    5341  307.77  5548.4  310.95  5748.3  317.21
  5902.4  323.09  5937.7  326.42    5959  325.81  6015.5  327.98  6086.2  331.62
  6100.4  333.55  6135.7  334.33  6149.9  336.19  6171.1     336  6225.1  339.36
#Mann= 5 ,-1 , 0
  3278.3     .05       0  3296.2      .1       0  4994.8     .07       0
  5000.8      .1       0  5298.6     .05       0
Bank Sta=4105.9,5341
XS Rating Curve= 0 ,0
Exp/Cntr=0.3,0.1

Type RM Length L Ch R = 1 ,12078   ,1248,1248,1248
BEGIN DESCRIPTION:
SALT BRANCH RAMIRENA CREEK 4.0
END DESCRIPTION:
XS GIS Cut Line= 4
      2217453.39     13235702.85      2215604.23     13235645.07
      2215118.81     13235645.07      2213871.69     13234166.99
#Sta/Elev= 30
  2984.1  317.59  3340.6   308.9  3580.1  307.11  3800.2  308.27  3860.2  305.22
  3920.2  303.44  4287.5  305.31  4290.6  305.31  4980.7  303.13  4997.7  300.24
  5000.4  299.74  5003.7  300.24  5020.7  303.91  5133.5   304.4  5296.2  304.06
  5546.2  304.35  5581.3  302.08  5595.6  303.75  5702.2  304.89  5808.2  304.19
  6063.7  305.17  6553.9   306.2  6703.4  309.95  6724.2  312.47  6745.1  311.48
  7007.8  322.51  7064.9  326.53  7085.7  324.64  7217.6  330.21  7253.5  331.45
#Mann= 10 ,-1 , 0
  2984.1      .1       0  4287.5     .16       0  4290.6      .1       0
  4997.7     .07       0  5003.7      .1       0  5133.5     .16       0
  5296.2      .1       0  5808.2     .05       0  7007.8      .1       0
  7217.6     .05       0
#XS Ineff= 2 , 0
                            5559          304.26
Permanent Ineff=
       F       F
Bank Sta=3860.2,6063.7
XS Rating Curve= 0 ,0
Exp/Cntr=0.3,0.1

Type RM Length L Ch R = 1 ,10830   ,864,864,864
BEGIN DESCRIPTION:
SALT BRANCH RAMIRENA CREEK 3.0
END DESCRIPTION:
XS GIS Cut Line= 3
       2217303.2     13235356.15       2215638.9     13234662.69
      2214323.05     13233831.63
#Sta/Elev= 30
  3367.5  315.66  3514.3  309.58  3768.8  304.66  4099.3  310.54  4277.3  307.57
  4336.4  307.24  4382.7   302.1  4478.4   302.2  4563.4  301.69  4669.1  301.21
  4986.4   300.1  4995.4  296.77  4998.2  296.27  5001.4  296.77  5021.1   299.9
  5063.3  299.14  5174.9  303.08    5358  301.84  5638.7  302.21  5848.4  302.58
  5905.3  302.73  6090.2  303.47  6319.7  309.65    6335  312.24  6365.6  311.65
  6565.4  322.63  6617.4  325.01  6632.7   328.6    6675  326.72  6726.8  330.96
#Mann= 13 ,-1 , 0
  3367.5      .1       0  4277.3     .16       0  4382.7      .1       0
  4563.4     .16       0  4669.1      .1       0  4995.4     .07       0
  5001.4      .1       0    5358     .05       0  5638.7      .1       0
  5848.4     .05       0  5905.3      .1       0  6090.2     .05       0
  6565.4      .1       0
Bank Sta=4478.4,5174.9
XS Rating Curve= 0 ,0
Exp/Cntr=0.3,0.1

Type RM Length L Ch R = 1 ,9966    ,921,921,921
BEGIN DESCRIPTION:
SALT BRANCH RAMIRENA CREEK 2.0
END DESCRIPTION:
XS GIS Cut Line= 4
      2217559.13     13235143.63      2216656.33     13234518.62
      2215666.75     13233563.76      2214503.57     13233476.95
#Sta/Elev= 30
  3200.5  320.77  3349.2  315.86  3486.4  309.21  3501.2  310.79  3522.2  308.08
  3543.1  307.24  3751.9  301.88  3868.1  301.03  3939.8  302.96  4047.2  300.82
  4532.3  299.97  4878.8  298.76  4991.8  296.52    4996  294.23  4998.7  293.73
    5002  294.23  5034.2  298.38  5101.4  299.34  5119.1  300.02  5508.1  303.09
  5752.9  302.37  5907.2  300.39  5989.3  301.04    6124  301.89  6274.4  305.49
  6424.8   312.5  6635.8  317.85  6725.6  323.24  6777.5  324.07  6840.1  327.81
#Mann= 7 ,-1 , 0
  3200.5      .1       0    4996     .07       0    5002      .1       0
  5101.4     .05       0  5907.2      .1       0  5989.3     .05       0
  6635.8      .1       0
Bank Sta=4532.3,5119.1
XS Rating Curve= 0 ,0
Exp/Cntr=0.3,0.1

Type RM Length L Ch R = 1 ,9045    ,136,136,136
BEGIN DESCRIPTION:
Mapping XS ade5d647
END DESCRIPTION:
XS GIS Cut Line= 3
      2218496.66     13235304.19      2216725.29     13233553.18
      2216043.43     13233379.82
#Sta/Elev= 30
  2885.1  332.09  3080.5   323.2  3547.1  309.25  3999.7  299.18  4367.4  296.64
  4494.7   295.7  4544.2  292.52  4565.4  295.16  4572.5  293.41  4586.6  293.01
    4622  293.53  4643.2  295.85  4650.3  294.66  4678.6  295.76  4835.4  295.61
  4940.2  294.45  4970.6  295.59  4989.7  295.36  5000.8  289.76  5003.6  289.26
  5006.8  289.76  5010.9  292.93    5018  293.53  5046.3  293.28    5124  296.59
  5379.9     300  5540.7  300.36  5748.2  301.81  5948.3  305.61  6079.4  305.86
#Mann= 7 ,-1 , 0
  2885.1      .1       0  4835.4     .16       0  4970.6      .1       0
  5000.8     .07       0  5006.8      .1       0  5540.7     .05       0
  5948.3      .1       0
Bank Sta=4367.4,5124
XS Rating Curve= 0 ,0
Exp/Cntr=0.3,0.1