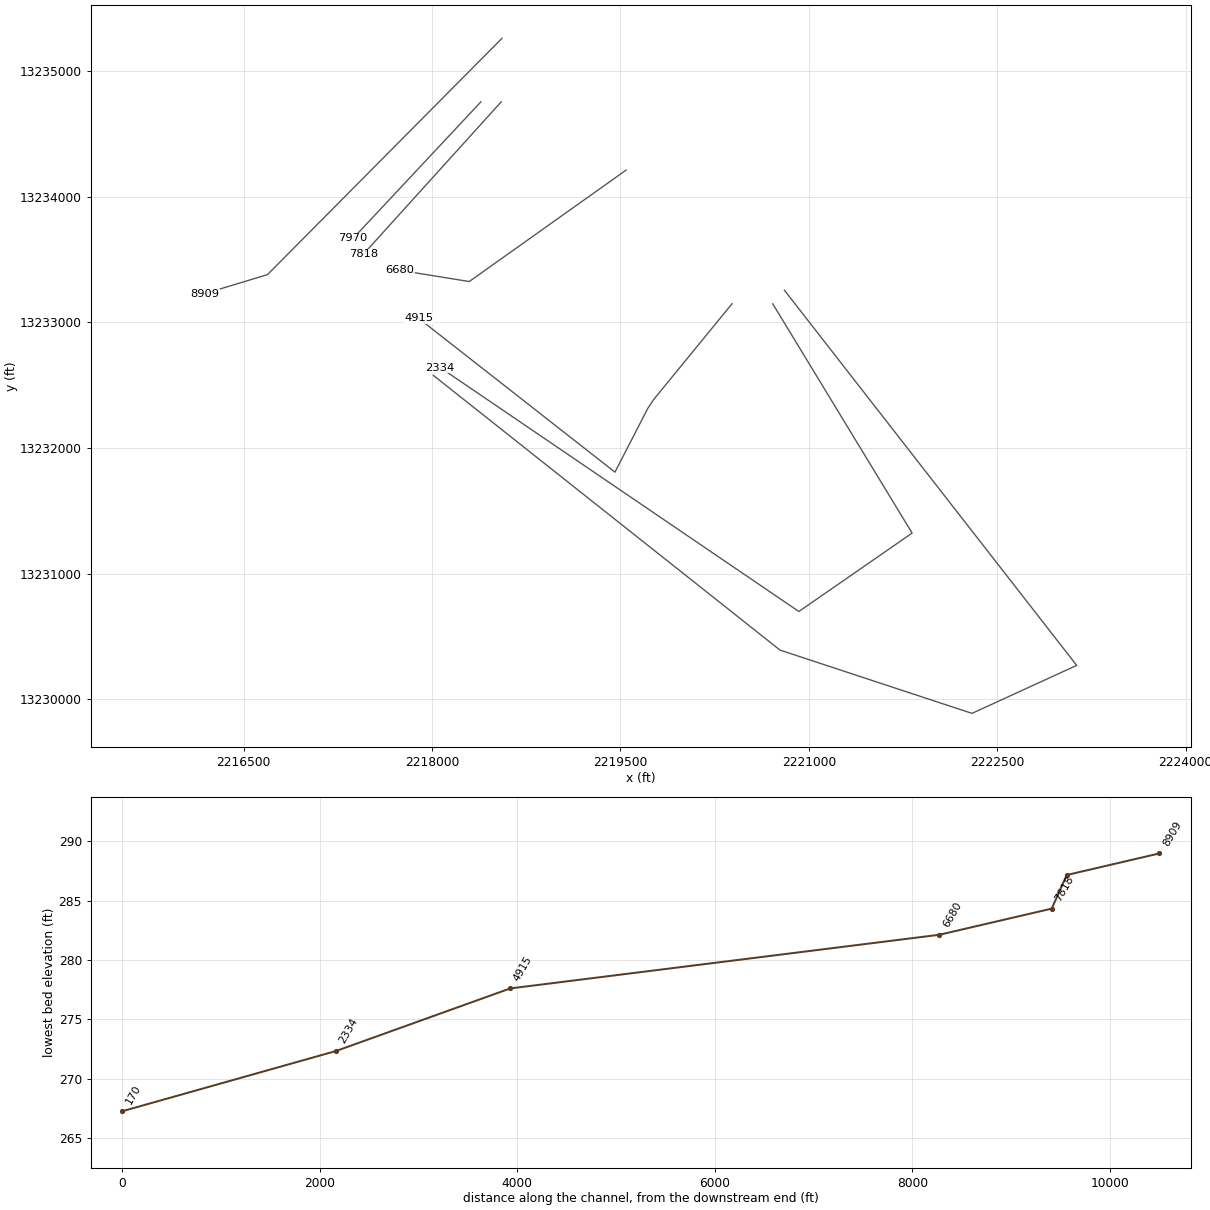
HEC-RAS study SALT BRANCH RAMIRENA CREEK.prj: SALT BRANCH RAMIRENA CREEK Base Level Engineering

--- SALT BRANCH RAMIRENA CREEK.g01 (geometry) --- (continued)

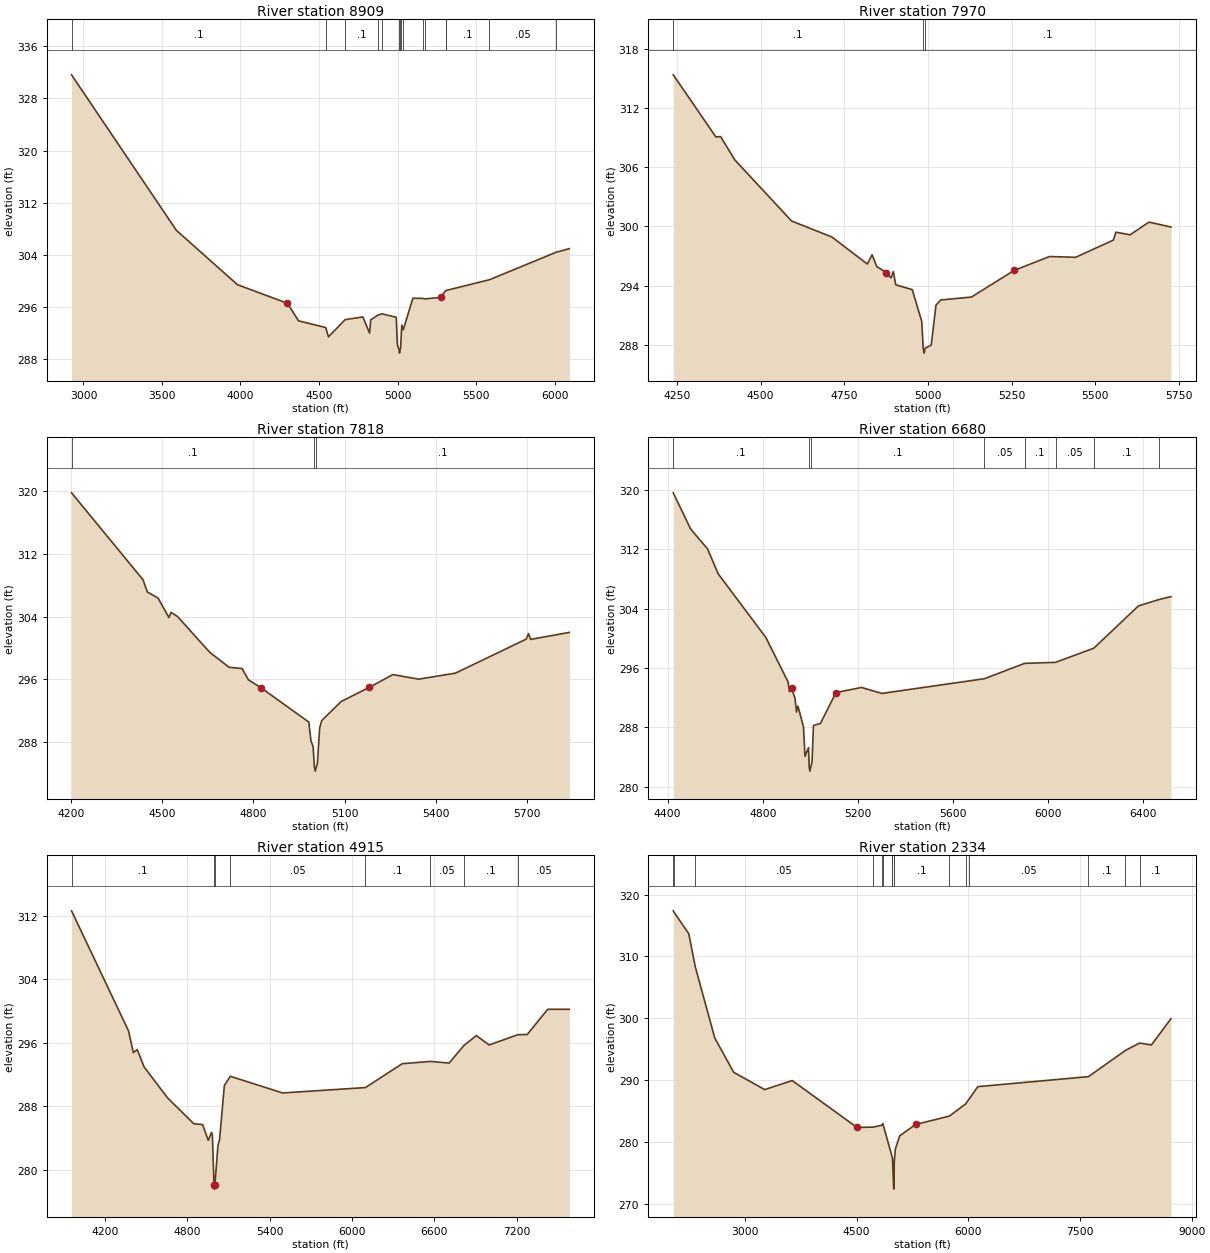
Type RM Length L Ch R = 1 ,8909    ,939,939,939
BEGIN DESCRIPTION:
Mapping XS 57a24d55
END DESCRIPTION:
XS GIS Cut Line= 3
      2218557.43     13235260.79      2216690.62     13233379.82
      2216193.63     13233229.57
#Sta/Elev= 30
  2924.3  331.59  3591.6  307.78  3980.5  299.45  4298.7  296.61  4369.4  293.92
  4542.4  292.89  4560.3  291.47  4666.2   294.1  4779.5  294.51  4821.9  292.03
    4829  294.07  4875.6   294.8  4901.3  294.99  4991.6  294.46  4998.7  290.31
  5009.9  289.47  5012.6  288.97  5015.9  289.47  5019.1  289.65    5027  293.27
  5036.6  292.55  5097.7  297.38  5162.6  297.35  5171.9  297.27  5274.5   297.5
  5306.1  298.54  5307.1  298.55  5585.1  300.21  6008.8  304.41  6093.6  304.97
#Mann= 15 ,-1 , 0
  2924.3      .1       0  4542.4     .08       0  4666.2      .1       0
  4875.6     .08       0  4901.3      .1       0  5009.9     .07       0
  5015.9      .1       0  5019.1     .08       0  5036.6      .1       0
  5162.6     .08       0  5171.9      .1       0  5306.1     .08       0
  5307.1      .1       0  5585.1     .05       0  6008.8      .1       0
Bank Sta=4298.7,5274.5
XS Rating Curve= 0 ,0
Exp/Cntr=0.3,0.1

Type RM Length L Ch R = 1 ,7970    ,152,152,152
BEGIN DESCRIPTION:
Mapping XS 4357b273
END DESCRIPTION:
XS GIS Cut Line= 2
      2218389.59     13234755.19      2217372.59     13233668.84
#Sta/Elev= 30
  4238.6  315.38  4366.1  309.08  4380.2  309.11  4422.7  306.75  4592.5  300.55
  4712.9  298.93  4818.9  296.19  4833.1  297.13  4847.2  295.92  4875.6  295.32
  4889.7  294.79  4896.6  295.42  4903.9  294.08  4953.2  293.59  4981.6  290.35
  4985.9  287.65  4988.6  287.15  4991.9  287.65  5009.9  287.97  5024.1  292.02
  5038.2  292.54  5130.1  292.84  5257.6  295.54  5363.6  296.95  5441.7  296.87
  5554.6  298.62  5561.9  299.42  5604.4  299.15  5660.9  300.44  5726.7  299.94
#Mann= 3 ,-1 , 0
  4238.6      .1       0  4985.9     .07       0  4991.9      .1       0
Bank Sta=4875.6,5257.6
XS Rating Curve= 0 ,0
Exp/Cntr=0.3,0.1

Type RM Length L Ch R = 1 ,7818    ,1138,1138,1138
BEGIN DESCRIPTION:
Mapping XS 4cd164c0
END DESCRIPTION:
XS GIS Cut Line= 2
      2218551.33     13234755.12      2217453.52     13233541.74
#Sta/Elev= 30
  4202.6  319.75  4437.6  308.68  4451.8  307.13    4487  306.35  4522.8  303.87
  4529.5  304.53  4550.9  304.01  4657.3  299.43  4720.8  297.54  4763.4  297.38
  4784.4  295.93  4826.9  294.89  4982.4  290.57  4989.8  288.14  4996.6  287.46
    5001  284.82  5003.8  284.32    5007  284.82  5010.8  285.26  5018.2  289.81
    5025  290.76  5089.2  293.19  5181.1  294.98  5258.8  296.61    5344  296.03
  5464.3  296.79  5697.5  301.13  5704.9  301.83  5711.7  301.09  5838.9  301.98
#Mann= 3 ,-1 , 0
  4202.6      .1       0    5001     .07       0    5007      .1       0
Bank Sta=4826.9,5181.1
XS Rating Curve= 0 ,0
Exp/Cntr=0.3,0.1

Type RM Length L Ch R = 1 ,6680    ,4346,4346,4346
BEGIN DESCRIPTION:
Mapping XS 1bc032f6
END DESCRIPTION:
XS GIS Cut Line= 3
      2219545.32     13234211.97      2218296.99       13233325.
      2217742.51     13233414.46
#Sta/Elev= 30
  4423.8  319.58  4496.8  314.72  4568.2  312.03  4612.5  308.69  4813.4   300.1
  4906.4  294.14  4912.5  292.81  4921.2  293.26  4935.9  291.92  4942.1  290.08
  4948.3  290.87  4971.6  288.04  4977.7  284.12  4992.5  285.28  4995.6  282.62
  4998.4  282.12  5001.6  282.62  5007.3  283.32  5013.4  288.26  5042.9  288.54
  5107.8  292.69  5215.1  293.38  5301.2  292.58  5732.1  294.56  5902.1  296.63
  6031.3  296.76  6192.2  298.67  6379.9  304.36  6467.1  305.22  6516.8  305.61
#Mann= 8 ,-1 , 0
  4423.8      .1       0  4995.6     .07       0  5001.6      .1       0
  5732.1     .05       0  5902.1      .1       0  6031.3     .05       0
  6192.2      .1       0  6467.1     .05       0
Bank Sta=4921.2,5107.8
XS Rating Curve= 0 ,0
Exp/Cntr=0.3,0.1

Type RM Length L Ch R = 1 ,4915    ,1765,1765,1765
BEGIN DESCRIPTION:
Mapping XS 53434fb4
END DESCRIPTION:
XS GIS Cut Line= 5
      2220389.01      13233148.7      2219764.89     13232385.88
      2219717.33     13232313.94      2219456.76     13231807.67
      2217893.44     13233032.43
#Sta/Elev= 30
  3957.2  312.62  4372.2  297.52  4407.3  294.78    4436  295.15  4485.6  292.98
  4656.4  289.09  4848.1  285.83    4912  285.72  4953.6  283.74  4977.3  284.74
  4983.3  284.46  4995.4   278.1  4998.1   277.6  5001.4   278.1  5024.3  283.15
  5035.3  283.75  5070.8  290.64  5113.9   291.8  5495.3   289.7  6098.8  290.38
  6366.6  293.38  6572.8  293.67  6708.3  293.46  6816.6  295.68  6907.2  296.92
  7000.3  295.74    7209  297.03  7277.9  297.06  7427.1  300.23  7584.4  300.23
#Mann= 8 ,-1 , 0
  3957.2      .1       0  4995.4     .07       0  5001.4      .1       0
  5113.9     .05       0  6098.8      .1       0  6572.8     .05       0
  6816.6      .1       0    7209     .05       0
Bank Sta=4995.4,5001.4
XS Rating Curve= 0 ,0
Exp/Cntr=0.3,0.1

Type RM Length L Ch R = 1 ,2334    ,2164,2164,2164
BEGIN DESCRIPTION:
Mapping XS 5f3280c1
END DESCRIPTION:
XS GIS Cut Line= 4
      2220712.75     13233147.44       2221822.1      13231322.6
      2220920.63      13230698.5      2218065.97     13232640.13
#Sta/Elev= 30
  2037.2  317.36  2051.4  317.07  2245.8  313.66  2333.6  308.28  2594.6  296.79
  2848.5  291.24    3265  288.43  3635.1   289.9  4504.2  282.32  4719.6  282.36
  4836.5  282.66  4851.3  282.94  4968.5  277.91  4981.2  277.31  4996.4  272.83
  4999.2  272.33  5002.4  272.83  5005.5  276.86  5020.4  278.85  5078.1  280.95
  5291.9  282.79  5745.9  284.15  5964.1  286.12  6009.9  286.89    6127  288.91
    7613  290.53  8110.5  294.78  8301.8  295.97  8458.7  295.66  8721.6  299.91
#Mann= 16 ,-1 , 0
  2037.2     .05       0  2051.4      .1       0  2333.6     .05       0
  4719.6      .1       0  4836.5     .05       0  4851.3      .1       0
  4968.5     .05       0  4981.2      .1       0  4996.4     .07       0
  5002.4      .1       0  5745.9     .05       0  5964.1      .1       0
  6009.9     .05       0    7613      .1       0  8110.5     .05       0
  8301.8      .1       0
Bank Sta=4504.2,5291.9
XS Rating Curve= 0 ,0
Exp/Cntr=0.3,0.1

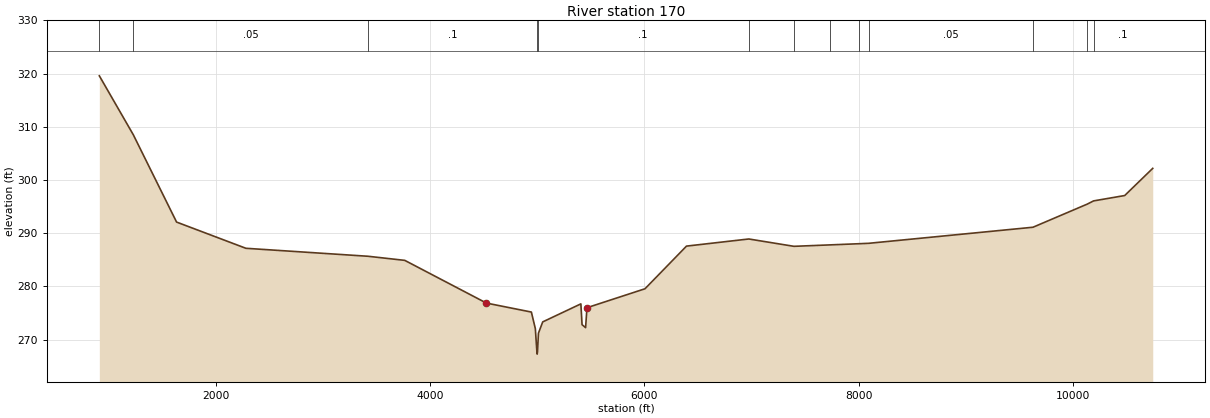
Type RM Length L Ch R = 1 ,170     ,0,0,0
BEGIN DESCRIPTION:
SALT BRANCH RAMIRENA CREEK 1.0
END DESCRIPTION:
XS GIS Cut Line= 5
      2220805.65     13233255.58      2223132.06     13230269.45
      2222298.73      13229887.5      2220770.95     13230390.97
       2218011.6     13232577.63
#Sta/Elev= 30
   914.5  319.59  1231.8   308.5  1635.4  292.09  2282.4  287.16  3422.7  285.66
  3765.1  284.89    4527  276.86  4946.7  275.17  4983.6  272.06  4998.1  267.76
  5000.9  267.26  5004.1  267.76  5012.7   271.2  5052.6  273.32  5408.7  276.71
  5419.7   272.8  5452.7  272.24  5465.7  275.99  6007.2  279.55  6394.4  287.57
    6976  288.91  7397.2  287.53  7734.8   287.8  8005.6  288.02  8096.5   288.1
  9628.3  291.12 10134.9  295.47 10193.3  296.07 10484.1  297.08 10745.9  302.19
#Mann= 13 ,-1 , 0
   914.5      .1       0  1231.8     .05       0  3422.7      .1       0
  4998.1     .07       0  5004.1      .1       0    6976     .05       0
  7397.2      .1       0  7734.8     .05       0  8005.6      .1       0
  8096.5     .05       0  9628.3      .1       0 10134.9     .05       0
 10193.3      .1       0
Bank Sta=4527,5465.7
XS Rating Curve= 0 ,0
Exp/Cntr=0.3,0.1

Chan Stop Cuts=-1
Use User Specified Reach Order=0
Composite Channel Slope=5