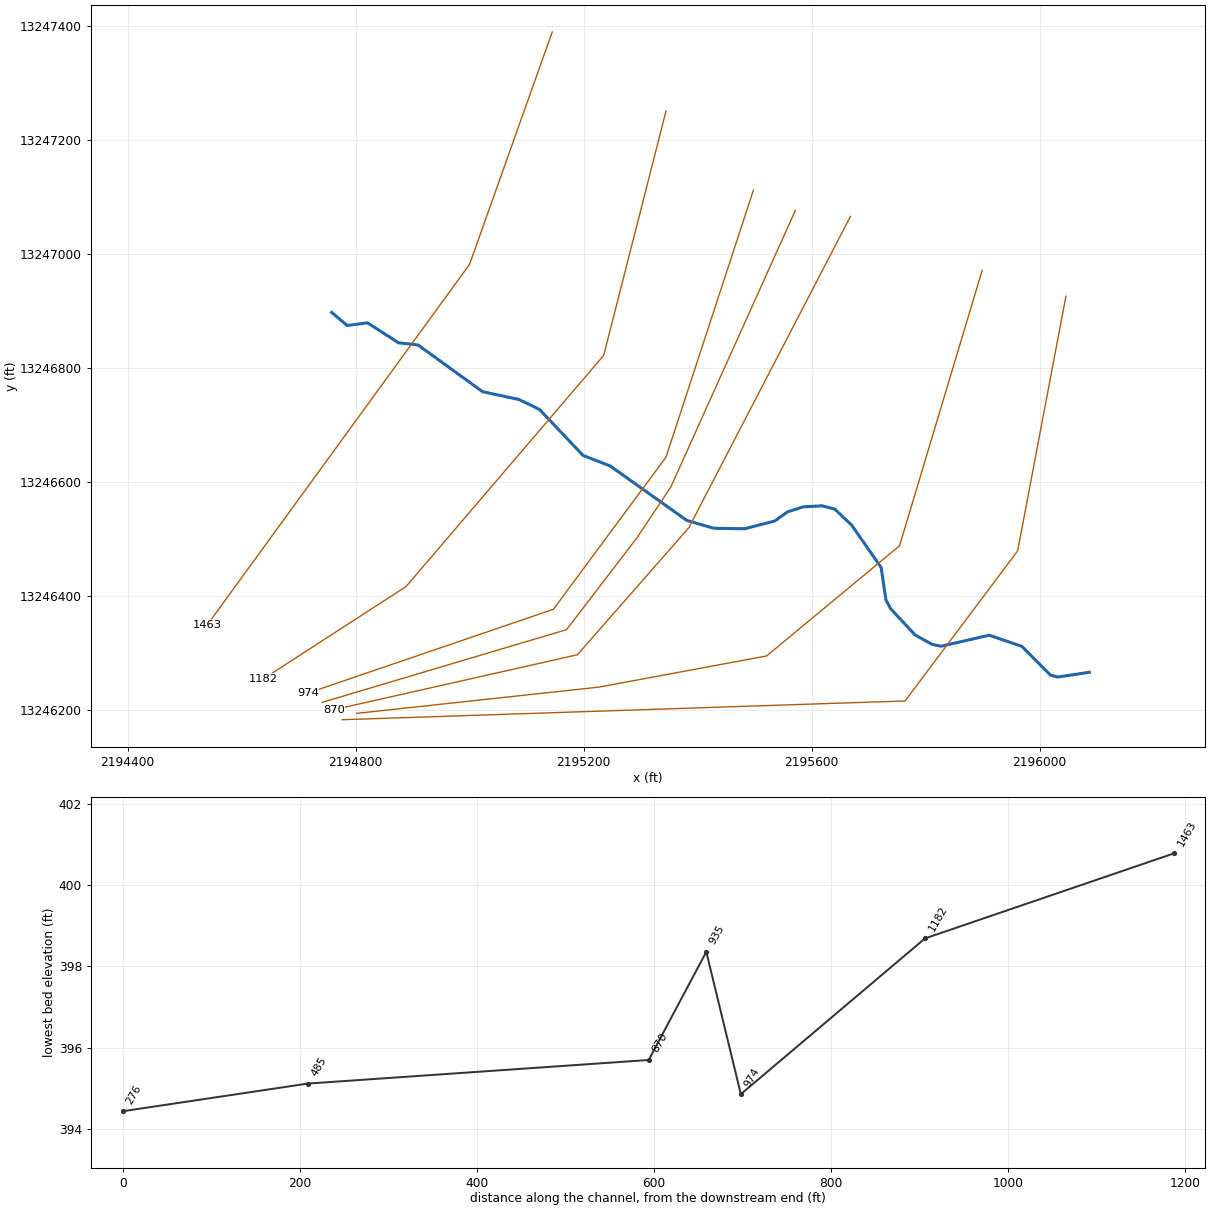
--- UNT 002 IN RACR.prj (project) ---

Proj Title=UNT 002 IN RACR Base Level Engineering
Current Plan=p01
Default Exp/Contr=0.3,0.1
English Units
Geom File=g01
Flow File=f01
Plan File=p01
BEGIN DESCRIPTION:
UNT 002 IN RACR
END DESCRIPTION:

--- UNT 002 IN RACR.p01 (plan) ---

Plan Title=Multiple Run
Short Identifier=Multiple
Geom File=g01
Flow File=f01
Subcritical Flow
K Sum by GR= 0
Std Step Tol= 0.01
Critical Tol= 0.01
Num of Std Step Trials= 20
Max Error Tol= 0.3
Flow Tol Ratio= 0.001
Split Flow NTrial= 30
Split Flow Tol= 0.02
Split Flow Ratio= 0.02
Log Output Level= 0
Friction Slope Method= 1
Unsteady Friction Slope Method= 2
Unsteady Bridges Friction Slope Method= 1
Parabolic Critical Depth
Global Vel Dist=  1 , 1 , 1
Global Log Level= 0
CheckData=True
Encroach Param= -1, 0, 0, 0
BEGIN DESCRIPTION:
Multiple Run
END DESCRIPTION:

--- UNT 002 IN RACR.f01 (steady flow) ---

Flow Title=Multiple
Number of Profiles=7
Profile Names=10-year,25-year,50-year,1pct_min,100-year,1pct_plu,500-year
River Rch & RM= UNT 002 IN RACR,Reach-1,1463
     228     317     391     355     480     650     736
Boundary for River Rch & Prof#=UNT 002 IN RACR,Reach-1,1
Up Type=0
Dn Type=3
Dn Slope=0.005
Boundary for River Rch & Prof#=UNT 002 IN RACR,Reach-1,2
Up Type=0
Dn Type=3
Dn Slope=0.005
Boundary for River Rch & Prof#=UNT 002 IN RACR,Reach-1,3
Up Type=0
Dn Type=3
Dn Slope=0.005
Boundary for River Rch & Prof#=UNT 002 IN RACR,Reach-1,4
Up Type=0
Dn Type=3
Dn Slope=0.005
Boundary for River Rch & Prof#=UNT 002 IN RACR,Reach-1,5
Up Type=0
Dn Type=3
Dn Slope=0.005
Boundary for River Rch & Prof#=UNT 002 IN RACR,Reach-1,6
Up Type=0
Dn Type=3
Dn Slope=0.005
Boundary for River Rch & Prof#=UNT 002 IN RACR,Reach-1,7
Up Type=0
Dn Type=3
Dn Slope=0.005

--- UNT 002 IN RACR.g01 (geometry) ---

Geom Title=Existing Conditions

River Reach=UNT 002 IN RACR,Reach-1
Reach XY= 30
      2194757.72     13246896.85      2194784.86     13246873.84
      2194820.74     13246878.45      2194875.06     13246843.46
      2194909.16     13246839.69      2195022.63     13246757.66
      2195086.49     13246743.94      2195122.23     13246726.64
      2195198.87     13246645.80      2195246.41     13246627.39
      2195380.80     13246531.78      2195428.18     13246518.06
      2195482.42     13246517.21      2195534.84     13246530.67
      2195557.72     13246546.85      2195585.36     13246555.63
      2195617.99     13246557.43      2195640.43     13246551.71
      2195670.16     13246523.52      2195721.81     13246449.12
      2195730.27     13246392.44      2195738.43     13246376.98
      2195781.42     13246330.76      2195811.11     13246314.43
      2195826.91     13246311.02      2195911.39     13246330.45
      2195968.87     13246310.74      2196019.02     13246260.28
      2196031.68     13246256.99      2196087.04     13246265.39

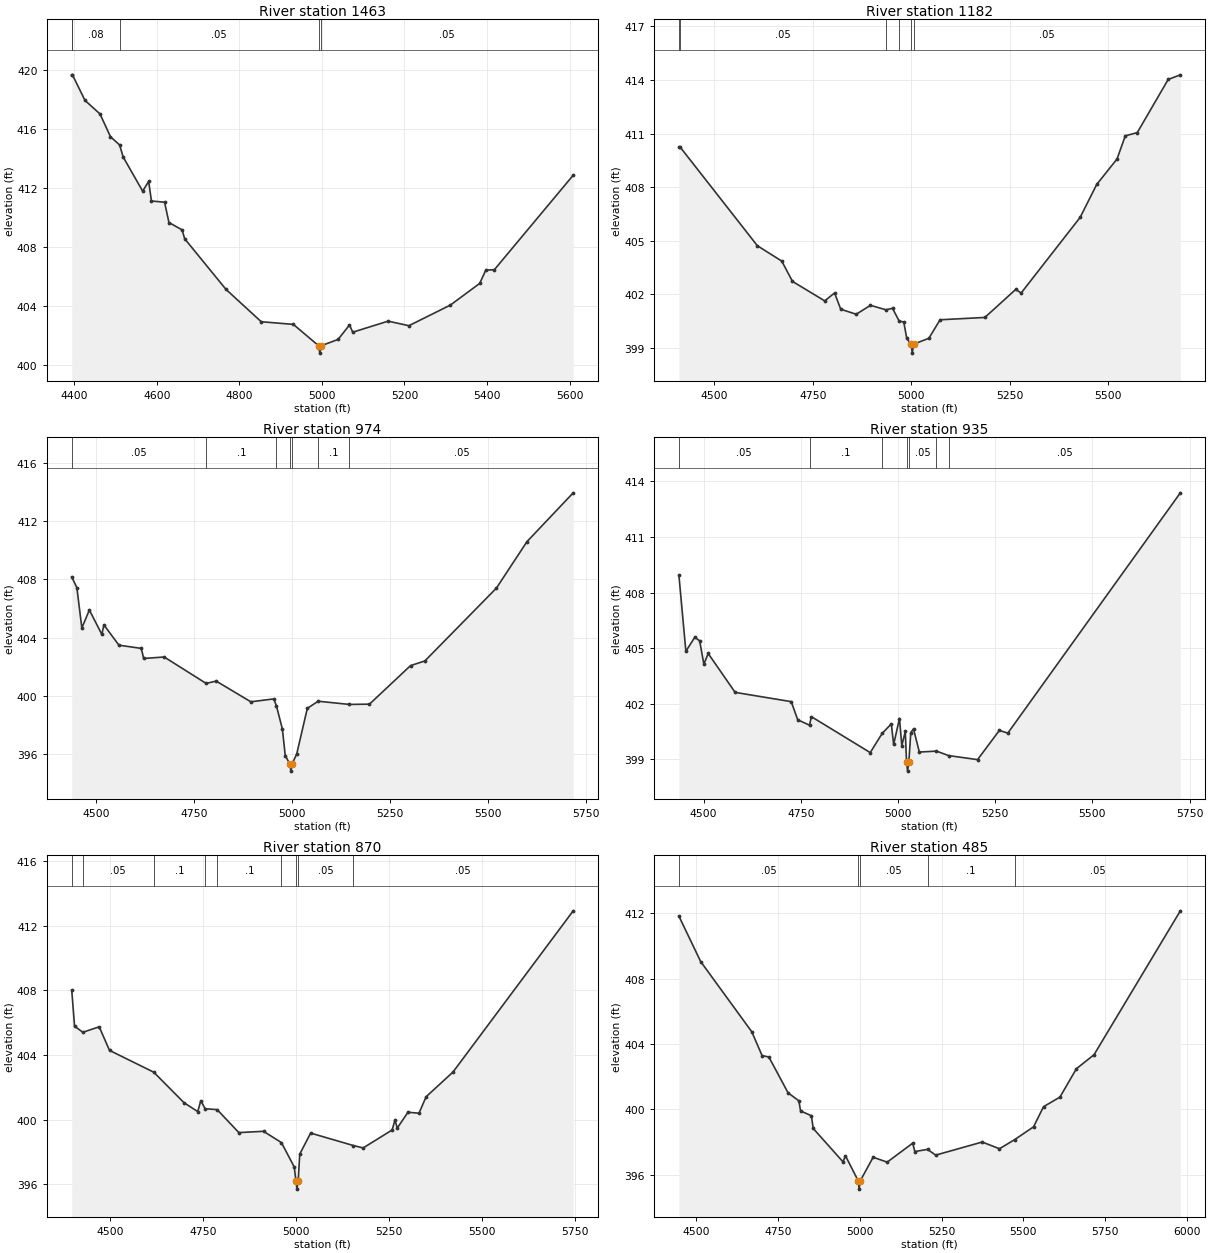
Type RM Length L Ch R = 1,1463,281,281,281
BEGIN DESCRIPTION:
UNT 002 IN RACR 3.0
END DESCRIPTION:
XS GIS Cut Line= 3
      2195144.75     13247388.76      2194999.76     13246981.11
      2194539.55     13246348.58
#Sta/Elev= 30
  4394.0  419.66  4395.7  419.66  4426.2  417.92  4462.4  417.01  4487.9  415.46
  4510.0  414.90  4518.7  414.08  4565.8  411.77  4580.4  412.43  4587.1  411.10
  4618.9  411.02  4629.5  409.64  4661.4  409.14  4667.6  408.54  4767.5  405.11
  4853.1  402.91  4930.9  402.73  4992.2  401.28  4995.0  400.78  4998.2  401.28
  5039.3  401.71  5066.9  402.69  5074.8  402.20  5160.6  402.95  5210.8  402.64
  5311.3  404.04  5382.4  405.51  5397.1  406.41  5417.9  406.44  5608.9  412.85
#Mann=5,-1,0
  4394.0    0.05       0  4395.7    0.08       0  4510.0    0.05       0
  4992.2    0.03       0  4998.2    0.05       0
Bank Sta=4992.2,4998.2
Exp/Cntr=0.3,0.1

Type RM Length L Ch R = 1,1182,208,208,208
BEGIN DESCRIPTION:
Mapping XS c258af0e
END DESCRIPTION:
XS GIS Cut Line= 4
      2195344.37     13247250.08      2195235.10     13246821.41
      2194888.39     13246415.86      2194638.30     13246254.04
#Sta/Elev= 30
  4409.7  410.22  4413.6  410.22  4609.1  404.71  4671.0  403.85  4698.3  402.71
  4780.1  401.62  4805.2  402.06  4820.9  401.15  4860.2  400.87  4896.4  401.37
  4935.5  401.12  4952.4  401.20  4969.2  400.49  4981.0  400.43  4988.6  399.51
  4999.8  399.19  5002.5  398.69  5005.8  399.19  5044.6  399.52  5073.2  400.56
  5187.0  400.69  5265.3  402.26  5279.1  402.06  5429.0  406.30  5471.2  408.15
  5522.6  409.57  5543.7  410.87  5574.1  411.05  5652.6  414.03  5683.5  414.29
#Mann=6,-1,0
  4409.7    0.08       0  4413.6    0.05       0  4935.5     0.1       0
  4969.2    0.05       0  4999.8    0.03       0  5005.8    0.05       0
Bank Sta=4999.8,5005.8
Exp/Cntr=0.3,0.1

Type RM Length L Ch R = 1,974,39,39,39
BEGIN DESCRIPTION:
UNT 002 IN RACR 2.0
END DESCRIPTION:
XS GIS Cut Line= 4
      2195497.76     13247111.38      2195344.37     13246642.80
      2195146.85     13246375.93      2194716.12     13246228.86
#Sta/Elev= 30
  4437.6  408.17  4450.7  407.43  4463.4  404.67  4482.6  405.90  4514.4  404.23
  4519.7  404.88  4558.1  403.49  4615.2  403.27  4621.2  402.58  4673.7  402.68
  4780.7  400.87  4806.4  401.03  4894.8  399.61  4953.5  399.81  4960.3  399.32
  4975.4  397.74  4982.7  395.92  4994.3  395.36  4997.1  394.86  5000.3  395.36
  5012.0  396.04  5039.0  399.16  5066.6  399.65  5146.6  399.43  5197.7  399.45
  5302.5  402.09  5339.1  402.41  5521.7  407.40  5599.9  410.59  5717.8  413.93
#Mann=7,-1,0
  4437.6    0.05       0  4780.7     0.1       0  4960.3    0.05       0
  4994.3    0.03       0  5000.3    0.05       0  5066.6     0.1       0
  5146.6    0.05       0
Bank Sta=4994.3,5000.3
Exp/Cntr=0.3,0.1

Type RM Length L Ch R = 1,935,65,65,65
BEGIN DESCRIPTION:
Mapping XS 51b6e23d
END DESCRIPTION:
XS GIS Cut Line= 5
      2195571.29     13247075.62      2195352.77     13246590.27
      2195293.94     13246502.01      2195169.96     13246340.21
      2194740.93     13246212.55
#Sta/Elev= 30
  4436.3  408.95  4454.3  404.83  4477.4  405.59  4489.8  405.39  4500.6  404.13
  4511.7  404.71  4581.0  402.61  4725.3  402.11  4742.0  401.13  4772.3  400.84
  4777.1  401.30  4928.5  399.36  4959.3  400.40  4982.7  400.91  4988.7  399.80
  5003.7  401.20  5009.7  399.74  5018.7  400.50  5021.8  398.86  5024.5  398.36
  5027.8  398.86  5032.8  400.44  5039.8  400.64  5054.8  399.39  5098.8  399.44
  5129.9  399.20  5204.5  398.98  5260.7  400.56  5282.3  400.41  5726.1  413.38
#Mann=7,-1,0
  4436.3    0.05       0  4772.3     0.1       0  4959.3    0.05       0
  5021.8    0.03       0  5027.8    0.05       0  5098.8     0.1       0
  5129.9    0.05       0
Bank Sta=5021.8,5027.8
Exp/Cntr=0.3,0.1

Type RM Length L Ch R = 1,870,385,385,385
BEGIN DESCRIPTION:
Mapping XS 7ad0d438
END DESCRIPTION:
XS GIS Cut Line= 4
      2195667.97     13247065.17      2195384.29     13246518.82
      2195188.87     13246296.09      2194761.42     13246199.70
#Sta/Elev= 30
  4396.1  408.02  4403.7  405.79  4426.0  405.41  4470.0  405.75  4497.8  404.29
  4616.9  402.94  4698.4  401.05  4735.4  400.50  4743.5  401.17  4755.2  400.68
  4787.7  400.62  4846.0  399.20  4912.5  399.28  4960.7  398.58  4995.2  397.07
  4999.7  396.20  5002.4  395.70  5005.7  396.20  5010.0  397.87  5039.3  399.17
  5154.1  398.40  5180.7  398.25  5258.6  399.36  5266.1  399.96  5272.8  399.49
  5301.3  400.46  5331.0  400.40  5350.2  401.42  5422.6  402.95  5746.2  412.93
#Mann=9,-1,0
  4396.1    0.08       0  4426.0    0.05       0  4616.9     0.1       0
  4755.2    0.05       0  4787.7     0.1       0  4960.7    0.05       0
  4999.7    0.03       0  5005.7    0.05       0  5154.1    0.05       0
Bank Sta=4999.7,5005.7
Exp/Cntr=0.3,0.1

Type RM Length L Ch R = 1,485,209,209,209
BEGIN DESCRIPTION:
Mapping XS 8b508f05
END DESCRIPTION:
XS GIS Cut Line= 5
      2195899.11     13246970.60      2195754.12     13246487.30
      2195520.88     13246293.98      2195226.69     13246239.35
      2194801.42     13246193.26
#Sta/Elev= 30
  4446.3  411.82  4512.9  409.04  4669.5  404.74  4700.8  403.29  4721.7  403.20
  4780.4  401.01  4813.5  400.52  4818.7  399.90  4851.8  399.61  4857.4  398.83
  4948.5  396.79  4956.1  397.16  4995.2  395.62  4997.9  395.12  5001.2  395.62
  5040.7  397.07  5083.7  396.77  5161.8  397.93  5168.3  397.42  5207.2  397.55
  5232.1  397.20  5374.5  398.00  5427.3  397.59  5474.0  398.15  5531.6  398.93
  5562.1  400.16  5612.4  400.75  5662.6  402.48  5716.7  403.34  5980.8  412.14
#Mann=5,-1,0
  4446.3    0.05       0  4995.2    0.03       0  5001.2    0.05       0
  5207.2     0.1       0  5474.0    0.05       0
Bank Sta=4995.2,5001.2
Exp/Cntr=0.3,0.1

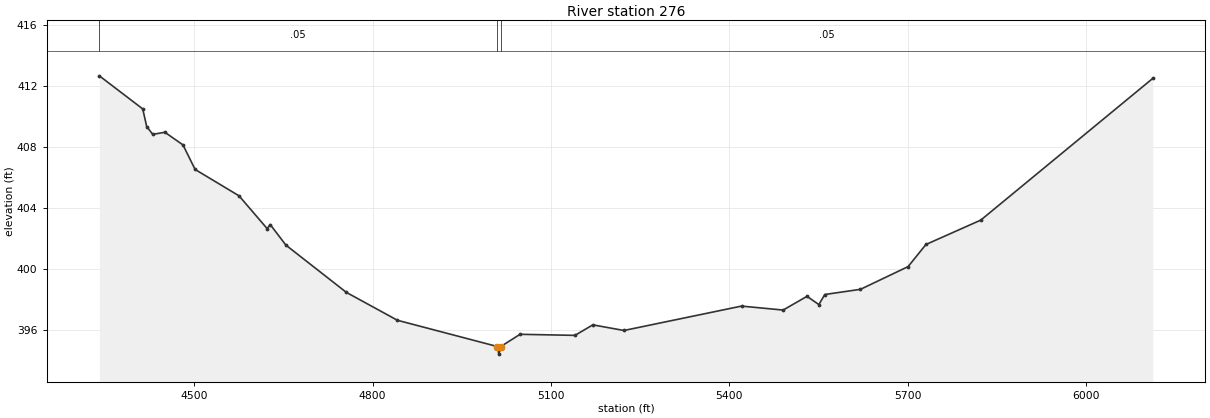
Type RM Length L Ch R = 1,276,0,0,0
BEGIN DESCRIPTION:
UNT 002 IN RACR 1.0
END DESCRIPTION:
XS GIS Cut Line= 4
      2196046.03     13246925.14      2195961.38     13246478.38
      2195763.88     13246215.05      2194776.41     13246182.13
#Sta/Elev= 30
  4340.5  412.69  4413.5  410.52  4420.2  409.36  4430.4  408.85  4450.7  408.99
  4481.2  408.16  4501.6  406.55  4575.5  404.82  4622.8  402.67  4627.9  402.94
  4654.3  401.59  4756.0  398.49  4841.9  396.66  5009.8  394.94  5012.5  394.44
  5015.8  394.94  5048.2  395.74  5140.5  395.67  5170.6  396.36  5222.9  395.99
  5420.7  397.59  5490.7  397.33  5530.8  398.23  5550.8  397.69  5560.8  398.35
  5620.8  398.69  5700.9  400.18  5730.9  401.63  5823.2  403.23  6112.4  412.52
#Mann=3,-1,0
  4340.5    0.05       0  5009.8    0.03       0  5015.8    0.05       0
Bank Sta=5009.8,5015.8
Exp/Cntr=0.3,0.1

Chan Stop Cuts=-1