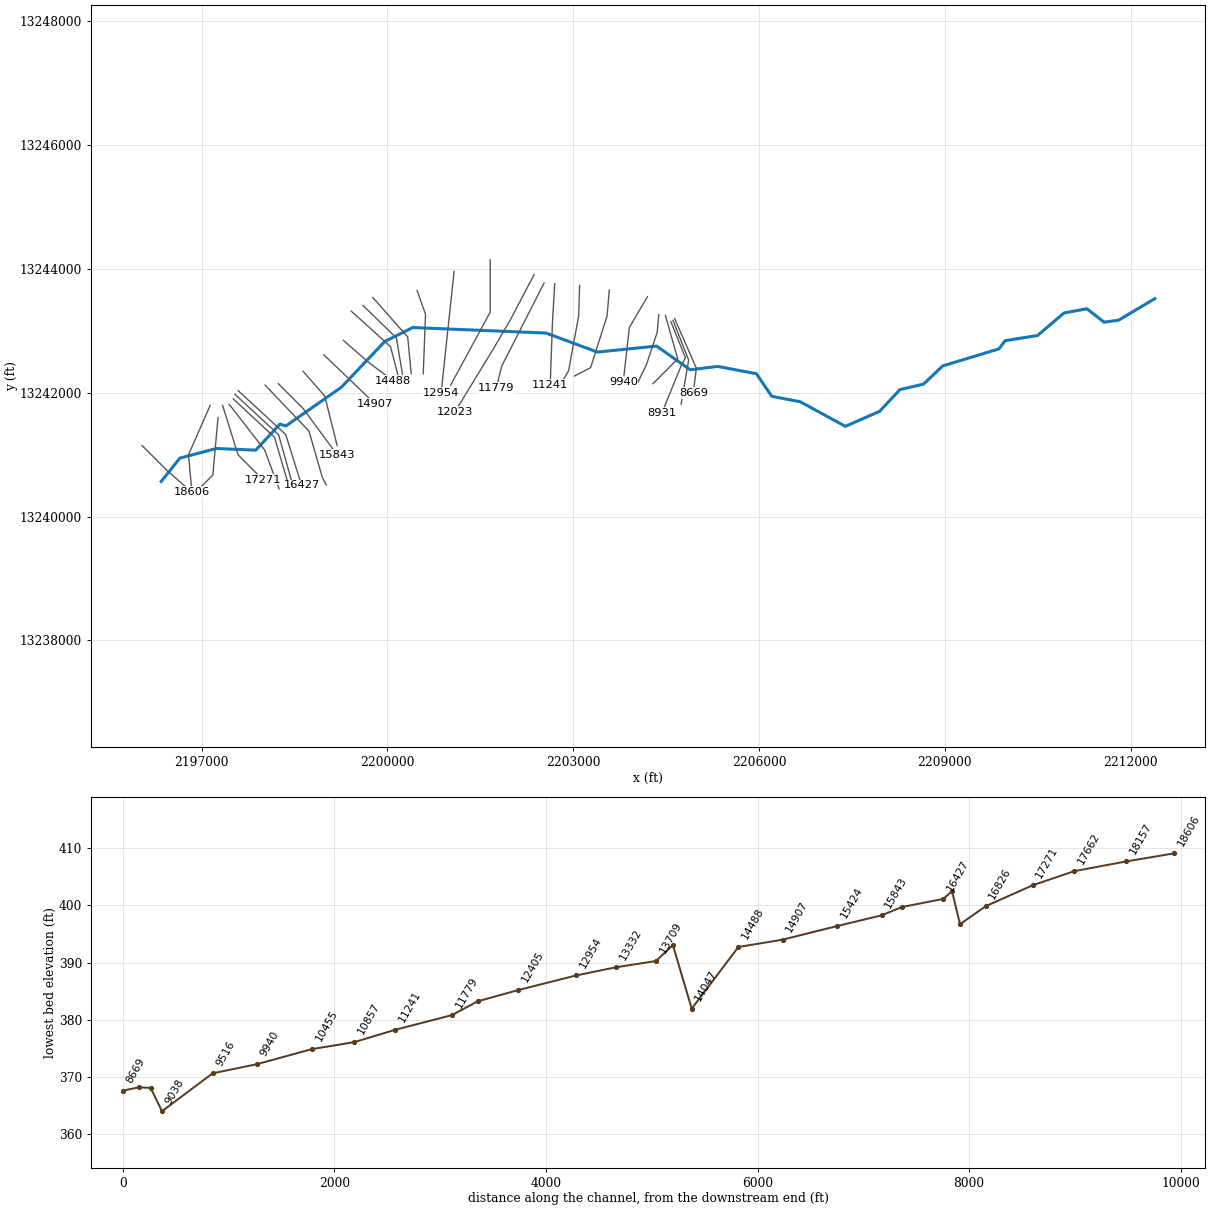
--- UNT 003 IN RACR.prj (project) ---

Proj Title=UNT 003 IN RACR Base Level Engineering
Current Plan=p01
Default Exp/Contr=0.3,0.1
English Units
Geom File=g01
Flow File=f01
Plan File=p01
BEGIN DESCRIPTION:
UNT 003 IN RACR
END DESCRIPTION:

--- UNT 003 IN RACR.p01 (plan) ---

Plan Title=Multiple Run
Short Identifier=Multiple
Geom File=g01
Flow File=f01
Subcritical Flow
K Sum by GR= 0
Std Step Tol= 0.01
Critical Tol= 0.01
Num of Std Step Trials= 20
Max Error Tol= 0.3
Flow Tol Ratio= 0.001
Split Flow NTrial= 30
Split Flow Tol= 0.02
Split Flow Ratio= 0.02
Log Output Level= 0
Friction Slope Method= 1
Unsteady Friction Slope Method= 2
Unsteady Bridges Friction Slope Method= 1
Parabolic Critical Depth
Global Vel Dist=  1 , 1 , 1
Global Log Level= 0
CheckData=True
Encroach Param= -1, 0, 0, 0
BEGIN DESCRIPTION:
Multiple Run
END DESCRIPTION:

--- UNT 003 IN RACR.f01 (steady flow) ---

Flow Title=Multiple
Number of Profiles=7
Profile Names=10-year,25-year,50-year,1pct_min,100-year,1pct_plu,500-year
River Rch & RM= UNT 003 IN RACR,Reach-1,18606
     266     371     460     418     566     765     870
River Rch & RM= UNT 003 IN RACR,Reach-1,11779
     343     486     606     555     751    1016    1173
River Rch & RM= UNT 003 IN RACR,Reach-1,6260
     394     560     701     645     872    1179    1370
Boundary for River Rch & Prof#=UNT 003 IN RACR,Reach-1,1
Up Type=0
Dn Type=3
Dn Slope=0.005
Boundary for River Rch & Prof#=UNT 003 IN RACR,Reach-1,2
Up Type=0
Dn Type=3
Dn Slope=0.005
Boundary for River Rch & Prof#=UNT 003 IN RACR,Reach-1,3
Up Type=0
Dn Type=3
Dn Slope=0.005
Boundary for River Rch & Prof#=UNT 003 IN RACR,Reach-1,4
Up Type=0
Dn Type=3
Dn Slope=0.005
Boundary for River Rch & Prof#=UNT 003 IN RACR,Reach-1,5
Up Type=0
Dn Type=3
Dn Slope=0.005
Boundary for River Rch & Prof#=UNT 003 IN RACR,Reach-1,6
Up Type=0
Dn Type=3
Dn Slope=0.005
Boundary for River Rch & Prof#=UNT 003 IN RACR,Reach-1,7
Up Type=0
Dn Type=3
Dn Slope=0.005

--- UNT 003 IN RACR.g01 (geometry) ---

Geom Title=Existing Conditions

River Reach=UNT 003 IN RACR,Reach-1
Reach XY= 30
      2196347.72     13240566.85      2196649.06     13240943.56
      2197237.56     13241099.10      2197873.12     13241072.50
      2198264.36     13241493.07      2198360.72     13241464.02
      2199253.85     13242086.91      2199959.05     13242830.31
      2200408.84     13243053.51      2202561.89     13242964.53
      2203389.13     13242657.28      2204345.02     13242754.20
      2204888.65     13242370.81      2205332.62     13242425.27
      2205957.72     13242306.86      2206205.25     13241942.46
      2206666.45     13241853.72      2207393.96     13241456.80
      2207946.62     13241699.40      2208275.37     13242051.14
      2208656.67     13242139.39      2208964.62     13242432.96
      2209873.67     13242708.77      2209973.19     13242840.85
      2210497.50     13242925.05      2210925.02     13243289.63
      2211293.94     13243356.91      2211571.72     13243139.89
      2211806.09     13243172.45      2212389.84     13243520.19

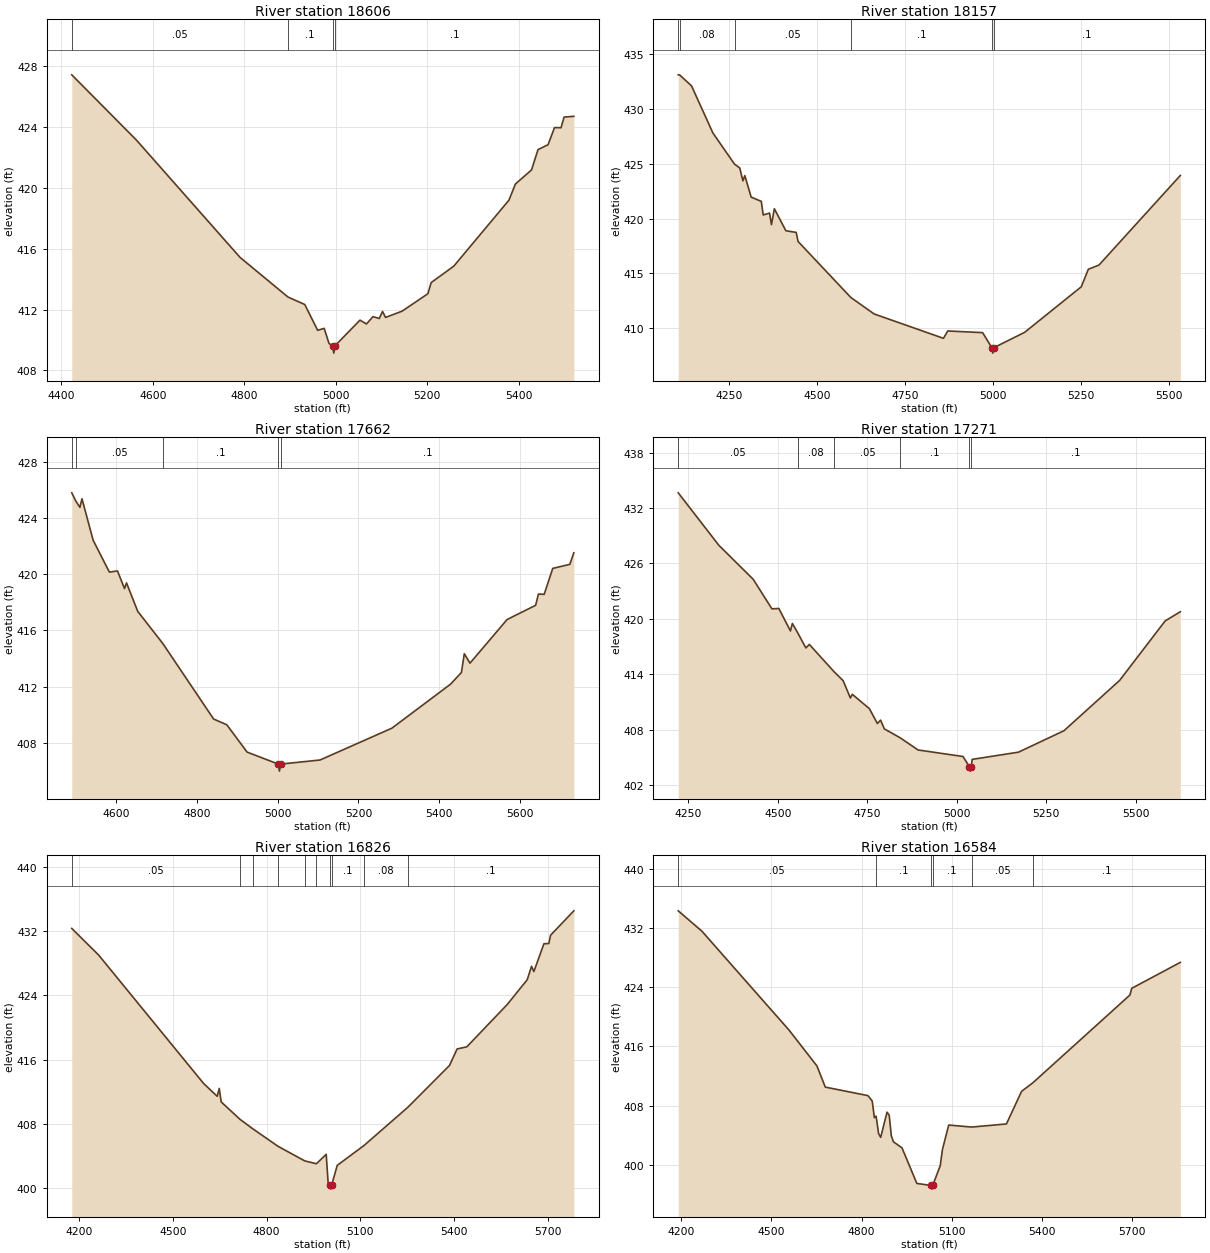
Type RM Length L Ch R = 1,18606,449,449,449
BEGIN DESCRIPTION:
UNT 003 IN RACR 40.0
END DESCRIPTION:
XS GIS Cut Line= 3
      2196037.70     13241146.88      2196437.72     13240746.85
      2196837.70     13240396.87
#Sta/Elev= 30
  4423.1  427.44  4564.6  423.14  4790.8  415.43  4895.6  412.82  4932.3  412.33
  4960.5  410.63  4974.7  410.76  4985.3  409.76  4992.9  409.63  4995.7  409.13
  4998.9  409.63  5052.9  411.30  5067.1  411.05  5081.4  411.53  5095.1  411.41
  5102.2  411.87  5108.9  411.48  5145.0  411.89  5201.4  413.04  5208.5  413.77
  5257.9  414.85  5378.4  419.19  5392.7  420.26  5427.8  421.18  5442.0  422.52
  5463.9  422.84  5478.1  423.97  5492.3  423.96  5499.0  424.66  5520.3  424.71
#Mann=4,-1,0
  4423.1    0.05       0  4895.6     0.1       0  4992.9    0.07       0
  4998.9     0.1       0
Bank Sta=4992.9,4998.9
Exp/Cntr=0.3,0.1

Type RM Length L Ch R = 1,18157,495,495,495
BEGIN DESCRIPTION:
UNT 003 IN RACR 39.0
END DESCRIPTION:
XS GIS Cut Line= 3
      2197137.72     13241796.86      2196787.72     13240996.85
      2196837.72     13240446.84
#Sta/Elev= 30
  4105.8  433.11  4110.2  433.09  4143.6  432.10  4204.0  427.82  4265.7  424.96
  4280.4  424.62  4289.4  423.44  4294.9  423.92  4312.8  421.96  4341.6  421.57
  4347.1  420.33  4365.0  420.50  4370.5  419.45  4378.7  420.90  4411.4  418.89
  4440.7  418.74  4446.1  417.91  4595.7  412.81  4662.1  411.30  4858.9  409.08
  4871.0  409.75  4970.0  409.60  4996.1  408.23  4998.8  407.73  5002.1  408.23
  5089.5  409.63  5250.1  413.78  5270.2  415.38  5300.3  415.76  5531.3  423.93
#Mann=6,-1,0
  4105.8    0.05       0  4110.2    0.08       0  4265.7    0.05       0
  4595.7     0.1       0  4996.1    0.07       0  5002.1     0.1       0
Bank Sta=4996.1,5002.1
Exp/Cntr=0.3,0.1

Type RM Length L Ch R = 1,17662,391,391,391
BEGIN DESCRIPTION:
UNT 003 IN RACR 38.0
END DESCRIPTION:
XS GIS Cut Line= 3
      2197264.77     13241599.67      2197180.24     13240669.90
      2196960.47     13240450.14
#Sta/Elev= 30
  4489.5  425.78  4499.5  425.20  4509.7  424.75  4514.8  425.36  4542.5  422.41
  4582.7  420.15  4602.8  420.23  4620.2  418.98  4625.2  419.38  4653.0  417.36
  4715.3  415.07  4841.1  409.71  4873.9  409.30  4924.1  407.36  5001.4  406.51
  5004.2  406.01  5007.4  406.51  5104.8  406.80  5282.9  409.06  5428.4  412.19
  5455.3  413.02  5462.4  414.35  5476.5  413.68  5568.5  416.78  5639.2  417.79
  5646.2  418.59  5660.4  418.57  5681.6  420.41  5724.0  420.70  5733.9  421.52
#Mann=5,-1,0
  4489.5    0.08       0  4499.5    0.05       0  4715.3     0.1       0
  5001.4    0.07       0  5007.4     0.1       0
Bank Sta=5001.4,5007.4
Exp/Cntr=0.3,0.1

Type RM Length L Ch R = 1,17271,445,445,445
BEGIN DESCRIPTION:
UNT 003 IN RACR 37.0
END DESCRIPTION:
XS GIS Cut Line= 3
      2197337.71     13241796.89      2197587.72     13240996.85
      2197987.74     13240596.84
#Sta/Elev= 30
  4221.4  433.64  4335.1  427.96  4431.0  424.29  4483.4  421.09  4502.7  421.13
  4535.2  418.70  4540.5  419.51  4555.6  418.49  4578.2  416.87  4588.1  417.24
  4658.1  414.25  4682.4  413.33  4702.8  411.45  4708.1  411.85  4755.8  410.30
  4778.3  408.69  4787.2  409.06  4797.7  408.11  4842.6  407.13  4892.0  405.83
  5017.7  405.12  5035.1  404.04  5037.9  403.54  5041.1  404.04  5043.3  404.81
  5172.7  405.59  5300.0  407.91  5455.6  413.35  5582.8  419.78  5625.3  420.78
#Mann=6,-1,0
  4221.4    0.05       0  4555.6    0.08       0  4658.1    0.05       0
  4842.6     0.1       0  5035.1    0.07       0  5041.1     0.1       0
Bank Sta=5035.1,5041.1
Exp/Cntr=0.3,0.1

Type RM Length L Ch R = 1,16826,242,242,242
BEGIN DESCRIPTION:
UNT 003 IN RACR 36.0
END DESCRIPTION:
XS GIS Cut Line= 3
      2197443.45     13241814.29      2198016.38     13241076.43
      2198250.74     13240447.13
#Sta/Elev= 30
  4177.2  432.34  4263.2  429.02  4599.0  413.02  4642.4  411.43  4648.8  412.41
  4655.1  410.73  4715.3  408.56  4755.6  407.40  4837.4  405.19  4922.1  403.39
  4959.6  403.03  4990.9  404.21  4997.3  400.55  5002.4  400.37  5005.2  399.87
  5008.4  400.37  5026.2  402.83  5112.0  405.31  5251.9  410.06  5385.2  415.27
  5409.7  417.33  5440.6  417.59  5569.8  422.86  5633.8  425.95  5647.6  427.62
  5655.1  426.97  5687.2  430.43  5702.9  430.46  5708.5  431.49  5782.9  434.53
#Mann=10,-1,0
  4177.2    0.05       0  4715.3     0.1       0  4755.6    0.05       0
  4837.4     0.1       0  4922.1    0.05       0  4959.6     0.1       0
  5002.4    0.07       0  5008.4     0.1       0  5112.0    0.08       0
  5251.9     0.1       0
Bank Sta=5002.4,5008.4
Exp/Cntr=0.3,0.1

Type RM Length L Ch R = 1,16584,76,76,76
BEGIN DESCRIPTION:
Mapping XS 8253f9e5
END DESCRIPTION:
XS GIS Cut Line= 4
      2197510.33     13241901.05      2198176.97     13241279.55
      2198385.30     13240567.75      2198385.30     13240551.13
#Sta/Elev= 30
  4190.2  434.33  4268.9  431.58  4559.1  418.19  4651.5  413.36  4679.3  410.50
  4821.0  409.35  4835.2  408.63  4842.5  406.37  4848.3  406.57  4856.6  404.20
  4863.5  403.71  4884.5  407.11  4891.8  406.70  4898.7  403.95  4906.0  403.10
  4934.3  402.29  4983.7  397.48  5030.5  397.21  5033.3  396.71  5036.5  397.21
  5061.6  399.89  5068.7  402.04  5089.7  405.37  5166.0  405.10  5281.6  405.52
  5332.1  409.93  5370.0  411.10  5692.4  422.95  5698.3  423.85  5859.9  427.36
#Mann=6,-1,0
  4190.2    0.05       0  4848.3     0.1       0  5030.5    0.07       0
  5036.5     0.1       0  5166.0    0.05       0  5370.0     0.1       0
Bank Sta=5030.5,5036.5
Exp/Cntr=0.3,0.1

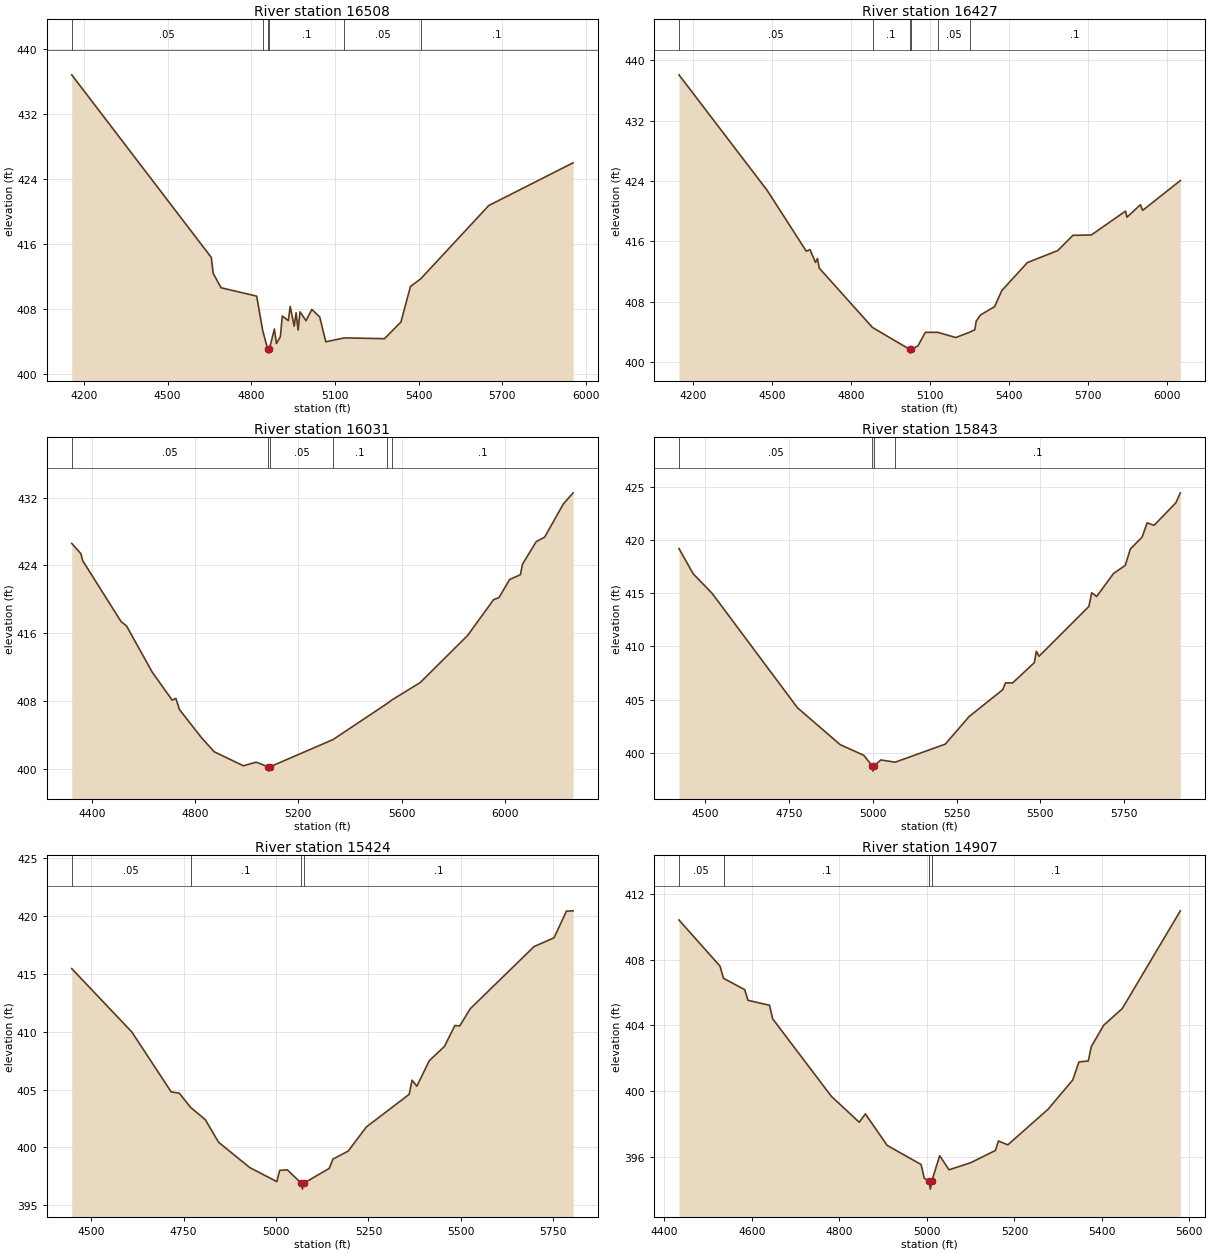
Type RM Length L Ch R = 1,16508,81,81,81
BEGIN DESCRIPTION:
Mapping XS ea9b6ca7
END DESCRIPTION:
XS GIS Cut Line= 3
      2197538.08     13241973.99      2198242.94     13241321.22
      2198468.64     13240515.63
#Sta/Elev= 30
  4156.7  436.84  4657.0  414.32  4663.8  412.36  4692.1  410.58  4819.7  409.55
  4841.5  405.26  4859.2  403.02  4862.0  402.52  4865.2  403.02  4883.2  405.49
  4890.5  403.71  4904.7  404.55  4911.5  407.10  4933.1  406.53  4939.9  408.28
  4954.1  405.84  4960.9  407.50  4968.2  405.37  4975.0  407.61  4996.6  406.52
  5017.6  407.91  5045.9  406.96  5067.4  403.92  5134.3  404.40  5277.7  404.30
  5336.9  406.36  5371.0  410.74  5407.4  411.67  5651.6  420.72  5954.0  425.99
#Mann=6,-1,0
  4156.7    0.05       0  4841.5     0.1       0  4859.2    0.07       0
  4865.2     0.1       0  5134.3    0.05       0  5407.4     0.1       0
Bank Sta=4859.2,4865.2
Exp/Cntr=0.3,0.1

Type RM Length L Ch R = 1,16427,396,396,396
BEGIN DESCRIPTION:
Mapping XS 2156136e
END DESCRIPTION:
XS GIS Cut Line= 3
      2197590.13     13242033.05      2198357.52     13241324.69
      2198614.45     13240501.82
#Sta/Elev= 30
  4145.2  438.09  4480.7  422.75  4629.3  414.69  4643.4  414.89  4664.4  413.20
  4671.8  413.72  4678.6  412.44  4881.1  404.56  5022.6  401.66  5025.4  401.16
  5028.6  401.66  5053.7  402.11  5081.8  403.92  5129.3  403.92  5197.8  403.23
  5250.2  403.93  5270.0  404.26  5275.2  405.38  5292.0  406.23  5345.4  407.33
  5372.7  409.46  5470.1  413.18  5585.4  414.77  5643.1  416.79  5713.3  416.84
  5843.3  420.01  5848.5  419.19  5899.7  420.85  5908.2  420.10  6051.6  424.06
#Mann=6,-1,0
  4145.2    0.05       0  4881.1     0.1       0  5022.6    0.07       0
  5028.6     0.1       0  5129.3    0.05       0  5250.2     0.1       0
Bank Sta=5022.6,5028.6
Exp/Cntr=0.3,0.1

Type RM Length L Ch R = 1,16031,188,188,188
BEGIN DESCRIPTION:
UNT 003 IN RACR 35.0
END DESCRIPTION:
XS GIS Cut Line= 4
      2198024.16     13242123.34      2198732.52     13241380.25
      2198947.80     13240633.72      2199012.41     13240511.30
#Sta/Elev= 30
  4322.2  426.60  4357.7  425.38  4364.6  424.56  4513.1  417.38  4534.5  416.85
  4633.6  411.42  4711.3  408.09  4725.4  408.30  4739.6  406.98  4824.5  403.67
  4873.9  402.00  4987.1  400.34  5036.5  400.77  5083.2  400.21  5085.9  399.71
  5089.2  400.21  5334.0  403.43  5542.3  407.66  5563.6  408.14  5672.1  410.17
  5856.0  415.74  5956.0  419.95  5976.8  420.19  6018.4  422.34  6060.1  422.90
  6068.3  424.15  6121.5  426.81  6154.1  427.34  6225.8  431.23  6264.2  432.57
#Mann=6,-1,0
  4322.2    0.05       0  5083.2    0.03       0  5089.2    0.05       0
  5334.0     0.1       0  5542.3    0.05       0  5563.6     0.1       0
Bank Sta=5083.2,5089.2
Exp/Cntr=0.3,0.1

Type RM Length L Ch R = 1,15843,419,419,419
BEGIN DESCRIPTION:
UNT 003 IN RACR 34.0
END DESCRIPTION:
XS GIS Cut Line= 3
      2198237.70     13242146.87      2198637.72     13241746.85
      2199187.74     13240996.83
#Sta/Elev= 30
  4421.8  419.18  4464.3  416.81  4520.8  414.97  4775.4  404.22  4902.7  400.76
  4973.4  399.75  4998.0  398.77  5000.8  398.27  5004.0  398.77  5024.2  399.32
  5066.8  399.11  5216.4  400.81  5287.4  403.40  5387.7  405.92  5396.2  406.57
  5417.0  406.55  5481.9  408.46  5488.1  409.54  5495.9  409.06  5644.8  413.75
  5653.2  415.03  5667.9  414.68  5718.0  416.83  5753.5  417.61  5768.2  419.13
  5803.7  420.27  5818.4  421.60  5839.2  421.37  5904.0  423.47  5917.6  424.42
#Mann=4,-1,0
  4421.8    0.05       0  4998.0    0.03       0  5004.0    0.05       0
  5066.8     0.1       0
Bank Sta=4998,5004
Exp/Cntr=0.3,0.1

Type RM Length L Ch R = 1,15424,517,517,517
BEGIN DESCRIPTION:
UNT 003 IN RACR 33.0
END DESCRIPTION:
XS GIS Cut Line= 3
      2198637.75     13242346.82      2198987.72     13241946.85
      2199187.72     13241146.84
#Sta/Elev= 30
  4447.6  415.45  4610.3  409.97  4716.6  404.80  4738.5  404.69  4769.3  403.45
  4808.7  402.41  4844.8  400.45  4929.2  398.26  5002.3  397.05  5010.0  398.02
  5030.6  398.07  5068.8  396.90  5071.6  396.40  5074.8  396.90  5144.0  398.19
  5154.3  399.00  5195.5  399.69  5244.5  401.77  5360.4  404.59  5368.2  405.81
  5381.1  405.29  5414.6  407.49  5455.8  408.73  5484.1  410.54  5497.0  410.49
  5525.4  411.98  5698.0  417.35  5752.1  418.11  5785.6  420.41  5803.7  420.44
#Mann=4,-1,0
  4447.6    0.05       0  4769.3     0.1       0  5068.8    0.07       0
  5074.8     0.1       0
Bank Sta=5068.8,5074.8
Exp/Cntr=0.3,0.1

Type RM Length L Ch R = 1,14907,419,419,419
BEGIN DESCRIPTION:
UNT 003 IN RACR 32.0
END DESCRIPTION:
XS GIS Cut Line= 2
      2198972.16     13242613.93      2199799.21     13241820.64
#Sta/Elev= 30
  4433.3  410.43  4527.0  407.62  4535.2  406.87  4583.6  406.18  4590.9  405.53
  4640.2  405.23  4647.5  404.40  4781.7  399.67  4845.3  398.09  4859.4  398.60
  4909.1  396.68  4986.8  395.51  4994.0  394.67  5005.2  394.51  5007.9  394.01
  5011.2  394.51  5029.2  396.05  5050.6  395.19  5100.0  395.62  5156.6  396.37
  5163.5  396.95  5184.9  396.71  5276.8  398.88  5333.4  400.67  5347.5  401.77
  5368.9  401.83  5375.8  402.71  5404.1  404.01  5446.6  405.03  5579.3  410.99
#Mann=4,-1,0
  4433.3    0.05       0  4535.2     0.1       0  5005.2    0.07       0
  5011.2     0.1       0
Bank Sta=5005.2,5011.2
Exp/Cntr=0.3,0.1

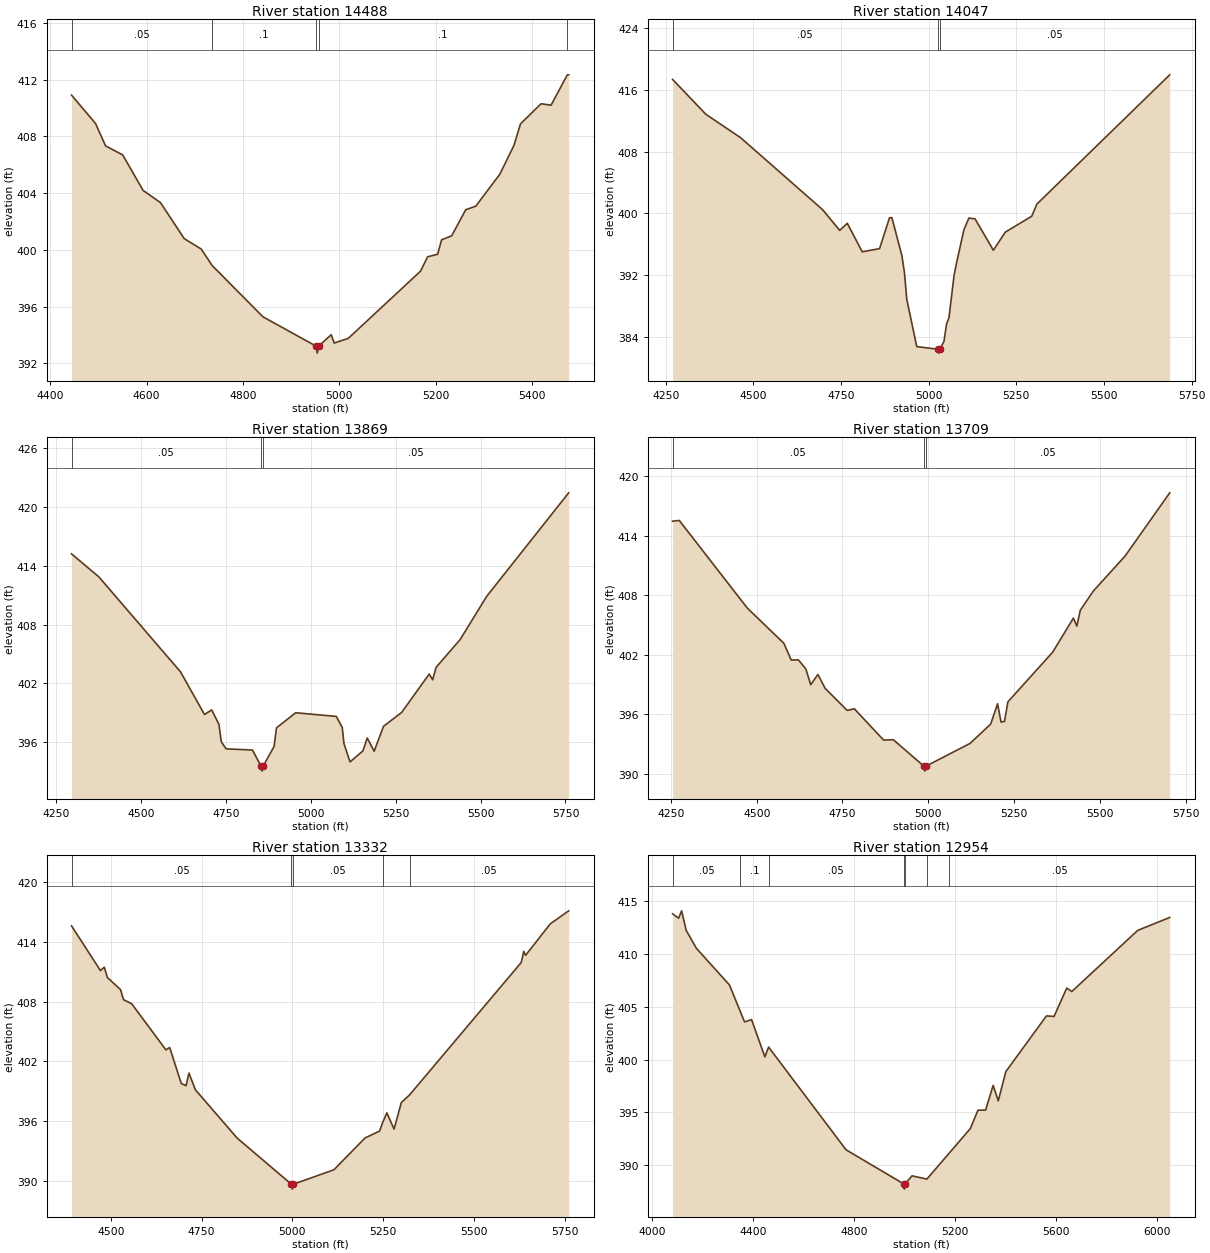
Type RM Length L Ch R = 1,14488,441,441,441
BEGIN DESCRIPTION:
UNT 003 IN RACR 31.0
END DESCRIPTION:
XS GIS Cut Line= 3
      2199287.74     13242846.84      2199687.72     13242496.85
      2200087.73     13242196.85
#Sta/Elev= 30
  4444.2  410.91  4494.0  408.91  4514.9  407.33  4550.5  406.69  4592.7  404.19
  4628.8  403.33  4678.1  400.79  4713.3  400.06  4735.9  398.90  4841.4  395.28
  4951.3  393.22  4954.1  392.72  4957.3  393.22  4983.0  394.02  4989.2  393.43
  5018.4  393.76  5168.4  398.50  5183.0  399.51  5203.8  399.69  5212.1  400.71
  5233.0  400.99  5262.1  402.83  5283.0  403.08  5333.0  405.34  5362.1  407.36
  5375.7  408.88  5418.4  410.30  5439.2  410.20  5472.9  412.34  5475.7  412.34
#Mann=5,-1,0
  4444.2    0.05       0  4735.9     0.1       0  4951.3    0.07       0
  4957.3     0.1       0  5472.9    0.05       0
Bank Sta=4951.3,4957.3
Exp/Cntr=0.3,0.1

Type RM Length L Ch R = 1,14047,178,178,178
BEGIN DESCRIPTION:
UNT 003 IN RACR 30.0
END DESCRIPTION:
XS GIS Cut Line= 3
      2199415.71     13243318.59      2200049.36     13242745.70
      2200192.20     13242200.32
#Sta/Elev= 30
  4269.4  417.37  4364.3  412.85  4463.0  409.83  4696.9  400.51  4746.2  397.80
  4767.8  398.72  4810.4  395.03  4859.8  395.44  4888.1  399.43  4894.9  399.46
  4923.3  394.57  4930.7  392.37  4937.5  388.86  4965.9  382.75  5026.4  382.40
  5029.1  381.90  5032.4  382.40  5043.6  383.45  5051.0  385.70  5057.8  386.48
  5072.0  391.88  5079.4  393.59  5100.4  397.88  5114.6  399.40  5132.2  399.29
  5184.5  395.23  5218.2  397.57  5293.9  399.64  5308.5  401.21  5687.4  417.96
#Mann=3,-1,0
  4269.4    0.05       0  5026.4    0.03       0  5032.4    0.05       0
Bank Sta=5026.4,5032.4
Exp/Cntr=0.3,0.1

Type RM Length L Ch R = 1,13869,160,160,160
BEGIN DESCRIPTION:
UNT 003 IN RACR 29.0
END DESCRIPTION:
XS GIS Cut Line= 3
      2199606.66     13243409.75      2200144.85     13242884.59
      2200262.01     13242181.65
#Sta/Elev= 30
  4294.8  415.21  4375.4  412.86  4615.9  403.18  4686.6  398.83  4707.7  399.30
  4729.0  397.84  4736.0  396.06  4750.2  395.33  4827.9  395.21  4853.2  393.56
  4855.9  393.06  4859.2  393.56  4891.6  395.58  4898.6  397.47  4955.2  399.01
  5074.9  398.64  5092.4  397.50  5097.4  395.87  5115.4  394.00  5153.2  395.12
  5166.1  396.44  5186.4  395.09  5214.0  397.63  5267.5  399.05  5348.6  402.96
  5358.7  402.37  5368.9  403.64  5439.8  406.48  5518.2  410.89  5759.4  421.43
#Mann=3,-1,0
  4294.8    0.05       0  4853.2    0.03       0  4859.2    0.05       0
Bank Sta=4853.2,4859.2
Exp/Cntr=0.3,0.1

Type RM Length L Ch R = 1,13709,377,377,377
BEGIN DESCRIPTION:
Mapping XS 109f9dfa
END DESCRIPTION:
XS GIS Cut Line= 3
      2199762.88     13243540.00      2200327.14     13242901.95
      2200383.56     13242307.38
#Sta/Elev= 30
  4254.8  415.44  4274.3  415.52  4472.6  406.69  4579.4  403.13  4600.6  401.45
  4621.5  401.47  4643.2  400.56  4657.5  398.97  4678.4  400.00  4699.5  398.60
  4763.7  396.38  4784.6  396.54  4869.9  393.39  4898.4  393.42  4987.4  390.76
  4990.1  390.26  4993.4  390.76  5121.7  393.05  5182.0  395.00  5202.1  397.05
  5212.1  395.21  5222.2  395.27  5232.2  397.24  5362.8  402.25  5423.1  405.68
  5433.1  404.87  5443.2  406.47  5480.8  408.39  5573.7  411.93  5703.8  418.30
#Mann=3,-1,0
  4254.8    0.05       0  4987.4    0.03       0  4993.4    0.05       0
Bank Sta=4987.4,4993.4
Exp/Cntr=0.3,0.1

Type RM Length L Ch R = 1,13332,378,378,378
BEGIN DESCRIPTION:
UNT 003 IN RACR 28.0
END DESCRIPTION:
XS GIS Cut Line= 3
      2200478.98     13243652.08      2200614.61     13243266.04
      2200578.10     13242306.21
#Sta/Elev= 30
  4391.5  415.61  4471.2  411.12  4481.8  411.46  4490.2  410.43  4526.5  409.21
  4534.8  408.20  4557.5  407.78  4651.4  403.16  4662.0  403.39  4693.8  399.78
  4707.1  399.56  4715.0  400.82  4732.8  399.15  4847.7  394.30  4997.0  389.67
  4999.8  389.17  5003.0  389.67  5114.3  391.11  5200.2  394.31  5240.2  395.00
  5248.6  395.84  5260.2  396.83  5280.2  395.20  5300.2  397.87  5322.8  398.63
  5630.5  411.93  5637.5  413.05  5642.5  412.65  5710.5  415.81  5761.2  417.12
#Mann=5,-1,0
  4391.5    0.05       0  4997.0    0.03       0  5003.0    0.05       0
  5248.6     0.1       0  5322.8    0.05       0
Bank Sta=4997,5003
Exp/Cntr=0.3,0.1

Type RM Length L Ch R = 1,12954,549,549,549
BEGIN DESCRIPTION:
UNT 003 IN RACR 27.0
END DESCRIPTION:
XS GIS Cut Line= 2
      2201076.19     13243960.74      2200867.17     13242000.95
#Sta/Elev= 30
  4081.1  413.83  4105.1  413.41  4117.0  414.11  4135.3  412.25  4175.5  410.56
  4306.8  407.08  4349.5  404.57  4366.6  403.58  4394.2  403.80  4447.0  400.27
  4461.9  401.19  4768.8  391.46  4997.2  388.23  4999.9  387.73  5003.2  388.23
  5030.3  388.99  5089.3  388.68  5177.0  391.12  5261.6  393.47  5291.8  395.21
  5322.0  395.22  5352.1  397.56  5372.3  396.10  5402.4  398.87  5563.3  404.15
  5593.5  404.10  5643.8  406.79  5663.9  406.46  5925.4  412.26  6052.0  413.48
#Mann=7,-1,0
  4081.1    0.05       0  4349.5     0.1       0  4461.9    0.05       0
  4997.2    0.03       0  5003.2    0.05       0  5089.3     0.1       0
  5177.0    0.05       0
Bank Sta=4997.2,5003.2
Exp/Cntr=0.3,0.1

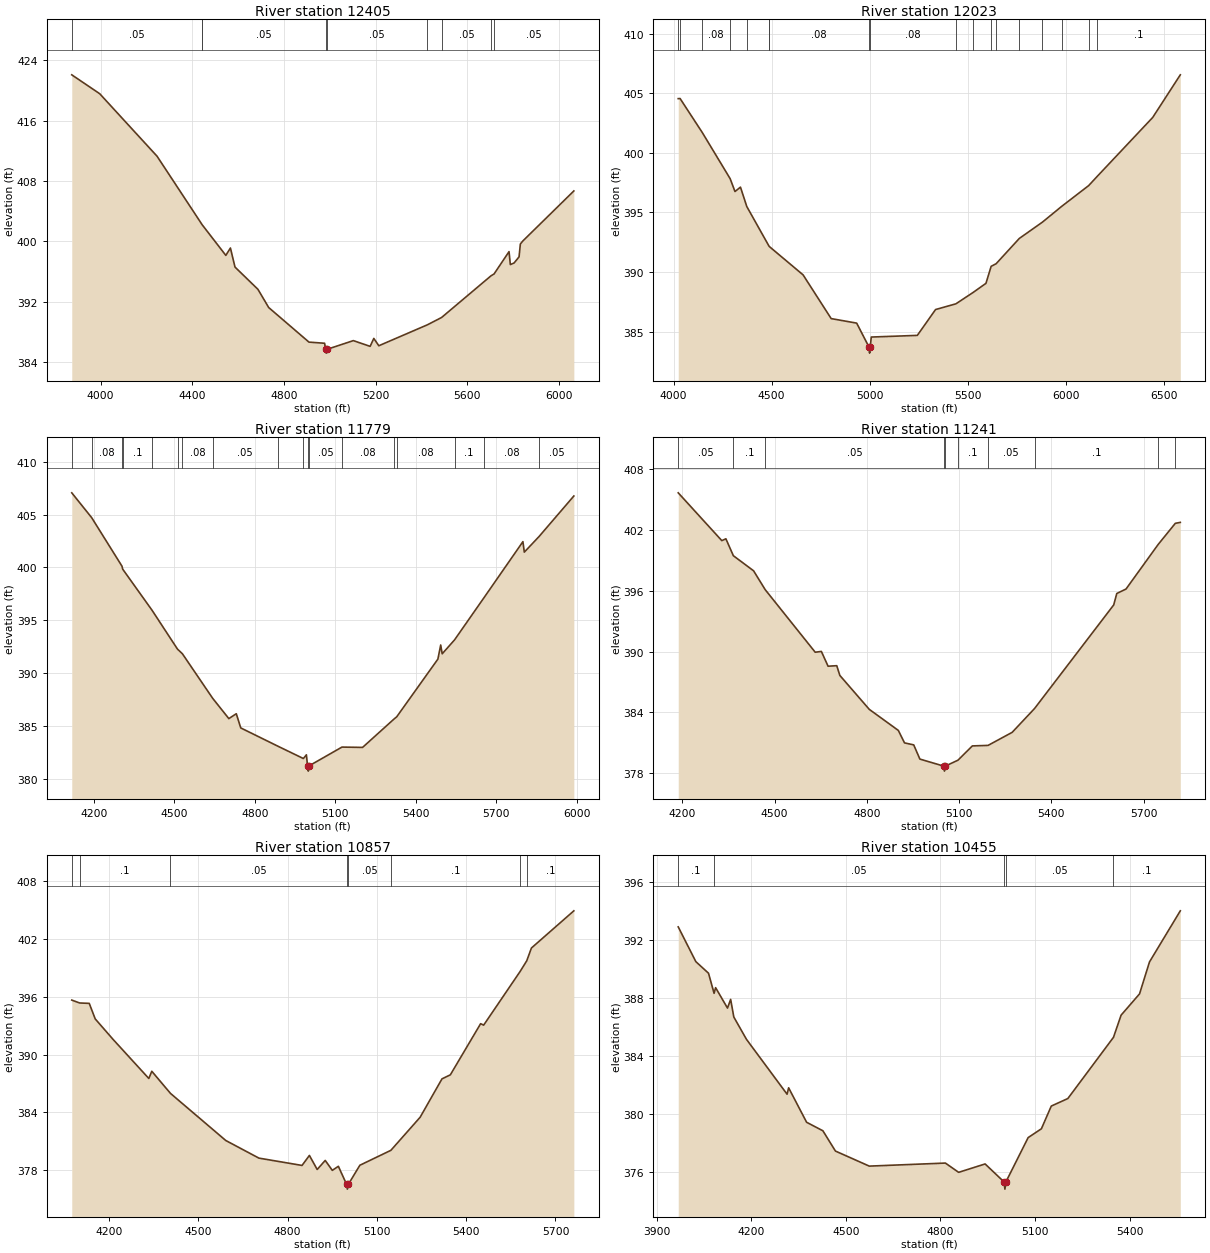
Type RM Length L Ch R = 1,12405,382,382,382
BEGIN DESCRIPTION:
Mapping XS 9dd94a3b
END DESCRIPTION:
XS GIS Cut Line= 3
      2201659.04     13244148.82      2201659.04     13243302.44
      2201019.45     13242120.82
#Sta/Elev= 30
  3874.4  422.09  3996.4  419.58  4246.4  411.29  4441.6  402.27  4442.8  402.21
  4546.4  398.13  4566.4  399.11  4586.4  396.58  4686.4  393.63  4733.4  391.21
  4909.1  386.62  4977.3  386.47  4981.6  385.66  4984.3  385.16  4987.6  385.66
  5102.4  386.82  5175.8  386.06  5191.9  387.11  5213.8  386.14  5425.8  388.92
  5487.6  389.89  5703.5  395.43  5716.3  395.66  5781.7  398.63  5787.4  396.91
  5803.6  397.12  5825.4  397.93  5831.1  399.64  5841.5  400.03  6064.4  406.68
#Mann=9,-1,0
  3874.4    0.05       0  4441.6    0.08       0  4442.8    0.05       0
  4981.6    0.03       0  4987.6    0.05       0  5425.8     0.1       0
  5487.6    0.05       0  5703.5     0.1       0  5716.3    0.05       0
Bank Sta=4981.6,4987.6
Exp/Cntr=0.3,0.1

Type RM Length L Ch R = 1,12023,244,244,244
BEGIN DESCRIPTION:
UNT 003 IN RACR 26.0
END DESCRIPTION:
XS GIS Cut Line= 4
      2202367.32     13243907.69      2201981.29     13243172.15
      2201710.04     13242707.89      2201089.66     13241691.31
#Sta/Elev= 30
  4024.0  404.56  4033.4  404.57  4146.8  401.71  4288.6  397.84  4313.3  396.76
  4341.2  397.13  4373.5  395.50  4486.9  392.17  4488.4  392.14  4660.5  389.76
  4803.6  386.09  4933.6  385.71  4996.8  383.69  4999.5  383.19  5002.8  383.69
  5008.0  384.54  5242.8  384.68  5335.7  386.85  5439.4  387.33  5526.7  388.28
  5592.6  389.05  5619.1  390.48  5644.6  390.70  5762.6  392.82  5880.5  394.19
  5978.3  395.51  6116.3  397.26  6157.9  398.00  6442.6  402.98  6583.3  406.56
#Mann=18,-1,0
  4024.0    0.08       0  4033.4     0.1       0  4146.8    0.08       0
  4288.6    0.05       0  4373.5    0.08       0  4486.9     0.1       0
  4488.4    0.08       0  4996.8    0.07       0  5002.8    0.08       0
  5439.4     0.1       0  5526.7    0.08       0  5619.1    0.05       0
  5644.6    0.08       0  5762.6     0.1       0  5880.5    0.08       0
  5978.3     0.1       0  6116.3    0.08       0  6157.9     0.1       0
Bank Sta=4996.8,5002.8
Exp/Cntr=0.3,0.1

Type RM Length L Ch R = 1,11779,538,538,538
BEGIN DESCRIPTION:
UNT 003 IN RACR 25.0
END DESCRIPTION:
XS GIS Cut Line= 3
      2202528.99     13243771.99      2201845.67     13242431.43
      2201756.99     13242076.71
#Sta/Elev= 30
  4118.1  407.05  4192.4  404.70  4305.0  400.13  4307.9  399.84  4417.7  395.94
  4512.0  392.29  4530.3  391.85  4642.9  387.65  4703.2  385.73  4731.0  386.19
  4747.6  384.85  4885.5  383.13  4980.8  381.96  4992.2  382.31  4996.3  381.27
  4999.1  380.77  5002.3  381.27  5124.5  383.04  5201.4  383.01  5318.6  385.69
  5328.6  385.90  5482.0  391.35  5492.4  392.68  5498.0  391.85  5543.9  393.16
  5653.5  397.14  5798.7  402.44  5803.9  401.45  5858.7  402.92  5988.4  406.75
#Mann=18,-1,0
  4118.1     0.1       0  4192.4    0.08       0  4305.0    0.05       0
  4307.9     0.1       0  4417.7    0.08       0  4512.0     0.1       0
  4530.3    0.08       0  4642.9    0.05       0  4885.5    0.08       0
  4980.8    0.05       0  4996.3    0.04       0  5002.3    0.05       0
  5124.5    0.08       0  5318.6     0.1       0  5328.6    0.08       0
  5543.9     0.1       0  5653.5    0.08       0  5858.7    0.05       0
Bank Sta=4996.3,5002.3
Exp/Cntr=0.3,0.1

Type RM Length L Ch R = 1,11241,384,384,384
BEGIN DESCRIPTION:
UNT 003 IN RACR 24.0
END DESCRIPTION:
XS GIS Cut Line= 3
      2202701.14     13243761.56      2202664.63     13243140.85
      2202628.17     13242130.39
#Sta/Elev= 30
  4186.4  405.67  4328.1  400.95  4341.4  401.13  4365.7  399.46  4431.5  397.97
  4469.2  396.11  4631.9  389.93  4651.9  390.01  4673.7  388.55  4702.0  388.60
  4712.0  387.64  4807.7  384.29  4902.2  382.21  4922.3  380.98  4952.3  380.78
  4972.3  379.38  5049.3  378.69  5052.1  378.19  5055.3  378.69  5096.2  379.27
  5142.9  380.68  5194.0  380.73  5272.5  382.02  5345.2  384.37  5602.7  394.60
  5612.7  395.73  5642.7  396.17  5747.5  400.58  5803.1  402.66  5819.3  402.75
#Mann=10,-1,0
  4186.4    0.05       0  4365.7     0.1       0  4469.2    0.05       0
  5049.3    0.03       0  5055.3    0.05       0  5096.2     0.1       0
  5194.0    0.05       0  5345.2     0.1       0  5747.5    0.05       0
  5803.1     0.1       0
Bank Sta=5049.3,5055.3
Exp/Cntr=0.3,0.1

Type RM Length L Ch R = 1,10857,402,402,402
BEGIN DESCRIPTION:
UNT 003 IN RACR 23.0
END DESCRIPTION:
XS GIS Cut Line= 4
      2203102.80     13243735.50      2203087.15     13243239.96
      2202925.44     13242358.40      2202779.41     13242102.84
#Sta/Elev= 30
  4075.3  395.67  4101.9  395.37  4134.0  395.33  4154.0  393.72  4214.0  391.59
  4334.1  387.53  4344.1  388.28  4406.9  385.98  4592.6  381.09  4703.9  379.26
  4848.7  378.50  4873.5  379.54  4899.6  378.08  4926.6  379.02  4950.4  377.99
  4970.8  378.41  4998.3  376.54  5001.0  376.04  5004.3  376.54  5043.0  378.52
  5147.2  380.07  5245.3  383.50  5318.8  387.49  5346.9  387.91  5448.6  393.22
  5458.8  393.07  5581.2  398.64  5603.5  399.75  5619.3  401.08  5761.7  404.94
#Mann=8,-1,0
  4075.3    0.05       0  4101.9     0.1       0  4406.9    0.05       0
  4998.3    0.03       0  5004.3    0.05       0  5147.2     0.1       0
  5581.2    0.05       0  5603.5     0.1       0
Bank Sta=4998.3,5004.3
Exp/Cntr=0.3,0.1

Type RM Length L Ch R = 1,10455,515,515,515
BEGIN DESCRIPTION:
UNT 003 IN RACR 22.0
END DESCRIPTION:
XS GIS Cut Line= 4
      2203582.70     13243662.48      2203546.19     13243239.96
      2203280.16     13242405.35      2203021.07     13242270.62
#Sta/Elev= 30
  3968.7  392.93  4024.5  390.53  4064.7  389.73  4082.4  388.34  4087.2  388.73
  4124.9  387.32  4134.9  387.92  4145.0  386.70  4185.1  385.16  4313.8  381.37
  4318.8  381.81  4375.8  379.43  4427.5  378.84  4467.2  377.44  4574.5  376.40
  4815.9  376.61  4857.9  375.97  4941.8  376.55  5001.8  375.31  5004.6  374.81
  5007.8  375.31  5078.3  378.37  5120.3  378.98  5151.7  380.55  5204.2  381.07
  5348.9  385.30  5373.0  386.83  5431.5  388.30  5463.1  390.51  5560.8  394.04
#Mann=5,-1,0
  3968.7     0.1       0  4082.4    0.05       0  5001.8    0.03       0
  5007.8    0.05       0  5348.9     0.1       0
Bank Sta=5001.8,5007.8
Exp/Cntr=0.3,0.1

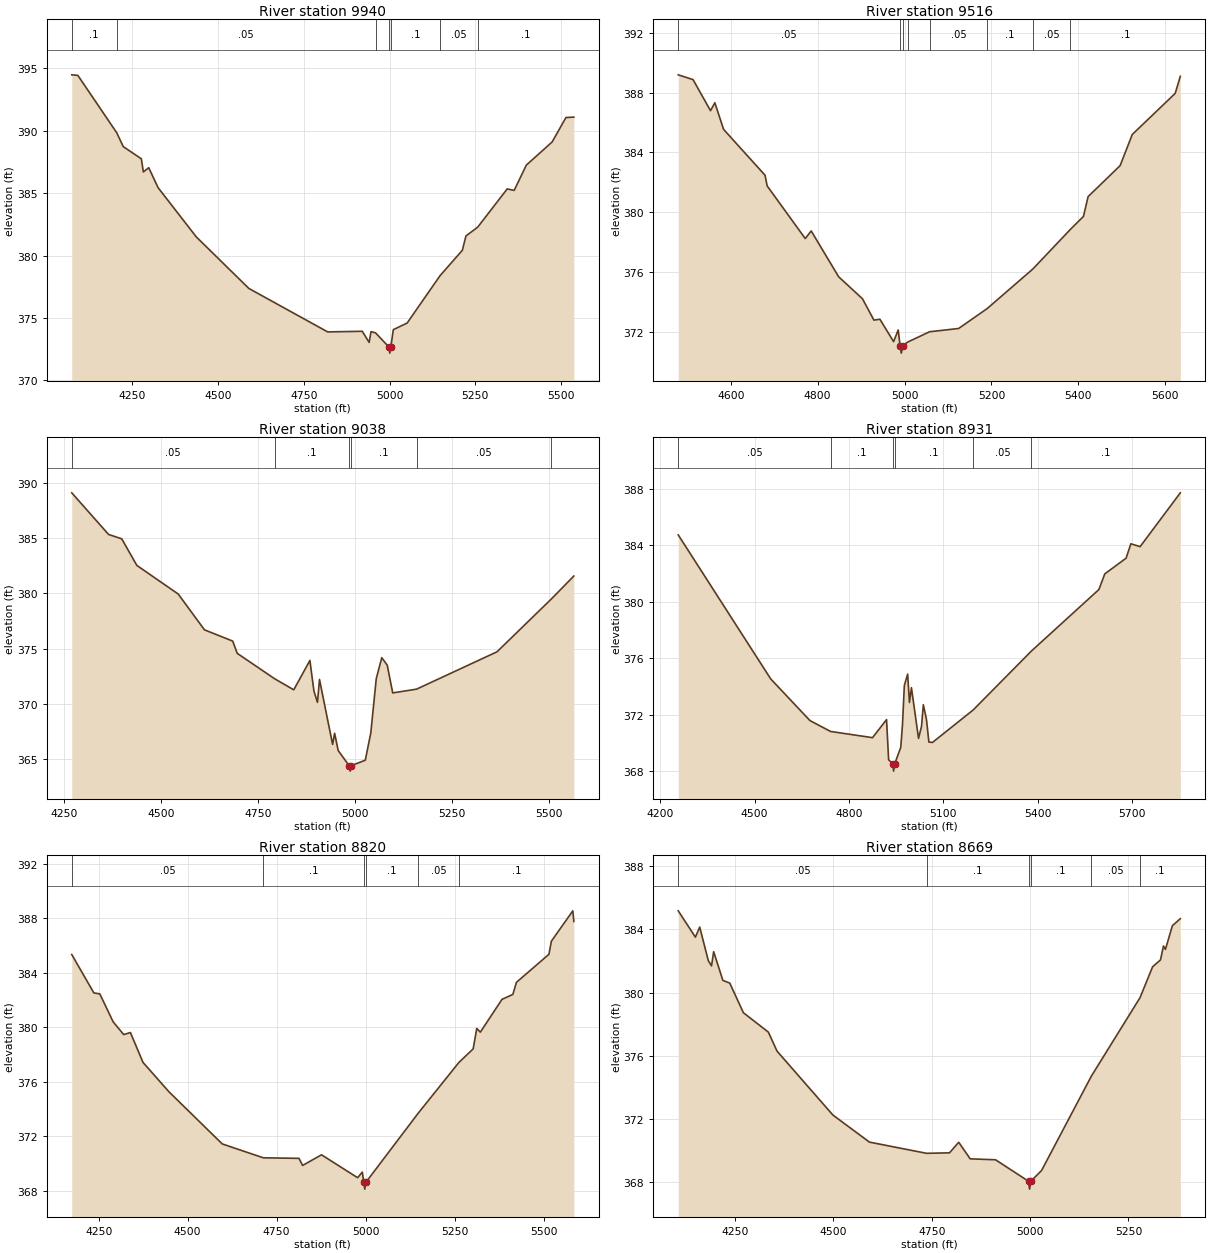
Type RM Length L Ch R = 1,9940,424,424,424
BEGIN DESCRIPTION:
UNT 003 IN RACR 21.0
END DESCRIPTION:
XS GIS Cut Line= 3
      2204198.13     13243552.04      2203905.14     13243052.87
      2203807.48     13242173.98
#Sta/Elev= 30
  4074.0  394.49  4091.6  394.45  4205.0  389.85  4224.0  388.74  4276.8  387.76
  4282.6  386.71  4298.3  387.05  4325.5  385.45  4437.0  381.50  4590.2  377.37
  4819.8  373.89  4920.5  373.94  4940.6  373.05  4946.0  373.91  4959.4  373.81
  4997.9  372.69  5000.7  372.19  5003.9  372.69  5011.0  374.07  5051.3  374.60
  5147.3  378.40  5212.2  380.43  5222.7  381.58  5256.8  382.28  5343.0  385.35
  5363.2  385.23  5398.8  387.26  5473.8  389.11  5514.1  391.07  5537.1  391.10
#Mann=7,-1,0
  4074.0     0.1       0  4205.0    0.05       0  4959.4     0.1       0
  4997.9    0.07       0  5003.9     0.1       0  5147.3    0.05       0
  5256.8     0.1       0
Bank Sta=4997.9,5003.9
Exp/Cntr=0.3,0.1

Type RM Length L Ch R = 1,9516,478,478,478
BEGIN DESCRIPTION:
UNT 003 IN RACR 20.0
END DESCRIPTION:
XS GIS Cut Line= 4
      2204380.80     13243260.85      2204354.72     13242973.93
      2204177.36     13242441.86      2204042.22     13242166.37
#Sta/Elev= 30
  4479.1  389.19  4513.2  388.87  4553.4  386.79  4563.4  387.32  4583.5  385.54
  4678.9  382.47  4683.9  381.75  4771.5  378.23  4785.2  378.74  4848.4  375.67
  4903.2  374.20  4929.6  372.77  4943.3  372.83  4974.9  371.33  4985.5  372.11
  4989.8  371.06  4992.6  370.56  4995.8  371.06  5007.4  371.30  5057.6  371.99
  5124.6  372.21  5190.2  373.54  5295.4  376.19  5382.1  378.85  5411.9  379.71
  5422.7  381.04  5496.3  383.11  5524.4  385.20  5623.2  387.95  5634.9  389.09
#Mann=8,-1,0
  4479.1    0.05       0  4989.8    0.03       0  4995.8    0.05       0
  5007.4     0.1       0  5057.6    0.05       0  5190.2     0.1       0
  5295.4    0.05       0  5382.1     0.1       0
Bank Sta=4989.8,4995.8
Exp/Cntr=0.3,0.1

Type RM Length L Ch R = 1,9038,107,107,107
BEGIN DESCRIPTION:
UNT 003 IN RACR 19.0
END DESCRIPTION:
XS GIS Cut Line= 3
      2204487.71     13243246.89      2204687.72     13242546.85
      2204287.75     13242146.88
#Sta/Elev= 30
  4269.4  389.11  4364.3  385.34  4398.1  384.95  4437.1  382.54  4543.7  379.95
  4611.3  376.71  4684.1  375.69  4695.8  374.58  4792.2  372.28  4841.4  371.28
  4883.0  373.94  4893.4  371.16  4902.5  370.15  4907.7  372.22  4941.5  366.34
  4946.7  367.35  4955.8  365.79  4984.0  364.42  4986.8  363.92  4990.0  364.42
  5025.7  364.91  5039.9  367.37  5054.0  372.29  5068.2  374.19  5082.3  373.51
  5096.4  371.00  5157.8  371.34  5365.1  374.72  5505.4  379.51  5563.1  381.58
#Mann=6,-1,0
  4269.4    0.05       0  4792.2     0.1       0  4984.0    0.07       0
  4990.0     0.1       0  5157.8    0.05       0  5505.4     0.1       0
Bank Sta=4984,4990
Exp/Cntr=0.3,0.1

Type RM Length L Ch R = 1,8931,111,111,111
BEGIN DESCRIPTION:
Mapping XS 32ecbe38
END DESCRIPTION:
XS GIS Cut Line= 4
      2204575.40     13243149.36      2204811.52     13242566.01
      2204738.60     13242427.12      2204433.06     13241677.16
#Sta/Elev= 30
  4257.0  384.75  4551.0  374.55  4675.7  371.60  4741.2  370.83  4874.6  370.39
  4919.2  371.67  4925.8  368.83  4938.8  368.52  4941.6  368.02  4944.8  368.52
  4964.3  369.70  4969.9  371.32  4975.7  374.08  4986.3  374.89  4992.0  372.88
  4998.3  373.93  5020.9  370.34  5030.4  371.19  5036.1  372.72  5046.0  371.70
  5053.8  370.08  5065.1  370.05  5194.5  372.35  5379.9  376.53  5594.2  380.88
  5612.9  381.99  5680.6  383.10  5695.8  384.12  5725.3  383.92  5853.0  387.73
#Mann=6,-1,0
  4257.0    0.05       0  4741.2     0.1       0  4938.8    0.07       0
  4944.8     0.1       0  5194.5    0.05       0  5379.9     0.1       0
Bank Sta=4938.8,4944.8
Exp/Cntr=0.3,0.1

Type RM Length L Ch R = 1,8820,151,151,151
BEGIN DESCRIPTION:
Mapping XS 83190cff
END DESCRIPTION:
XS GIS Cut Line= 3
      2204610.13     13243170.18      2204863.60     13242527.82
      2204742.40     13241817.95
#Sta/Elev= 30
  4174.4  385.34  4236.5  382.52  4253.2  382.45  4290.6  380.40  4320.4  379.46
  4339.2  379.61  4374.5  377.42  4446.7  375.28  4597.2  371.43  4712.6  370.41
  4812.8  370.37  4823.0  369.85  4876.1  370.63  4977.5  368.95  4990.9  369.36
  4994.8  368.61  4997.6  368.11  5000.8  368.61  5146.7  373.65  5262.0  377.41
  5302.2  378.41  5312.3  379.91  5322.4  379.64  5383.3  382.05  5413.7  382.41
  5423.9  383.30  5515.2  385.36  5522.0  386.32  5582.2  388.55  5585.1  387.77
#Mann=6,-1,0
  4174.4    0.05       0  4712.6     0.1       0  4994.8    0.07       0
  5000.8     0.1       0  5146.7    0.05       0  5262.0     0.1       0
Bank Sta=4994.8,5000.8
Exp/Cntr=0.3,0.1

Type RM Length L Ch R = 1,8669,255,255,255
BEGIN DESCRIPTION:
UNT 003 IN RACR 18.0
END DESCRIPTION:
XS GIS Cut Line= 3
      2204637.72     13243196.87      2204987.72     13242396.85
      2204937.73     13241996.89
#Sta/Elev= 30
  4105.6  385.18  4149.3  383.51  4160.2  384.15  4182.0  382.03  4190.2  381.69
  4195.7  382.59  4219.1  380.77  4236.6  380.60  4271.3  378.72  4334.8  377.49
  4356.7  376.29  4498.6  372.24  4591.7  370.52  4736.8  369.81  4795.2  369.84
  4818.6  370.51  4847.8  369.46  4912.2  369.40  4996.0  368.04  4998.7  367.54
  5002.0  368.04  5029.2  368.72  5156.0  374.71  5279.6  379.68  5311.4  381.63
  5331.5  382.07  5339.1  382.95  5344.1  382.74  5361.8  384.24  5381.9  384.68
#Mann=6,-1,0
  4105.6    0.05       0  4736.8     0.1       0  4996.0    0.07       0
  5002.0     0.1       0  5156.0    0.05       0  5279.6     0.1       0
Bank Sta=4996,5002
Exp/Cntr=0.3,0.1