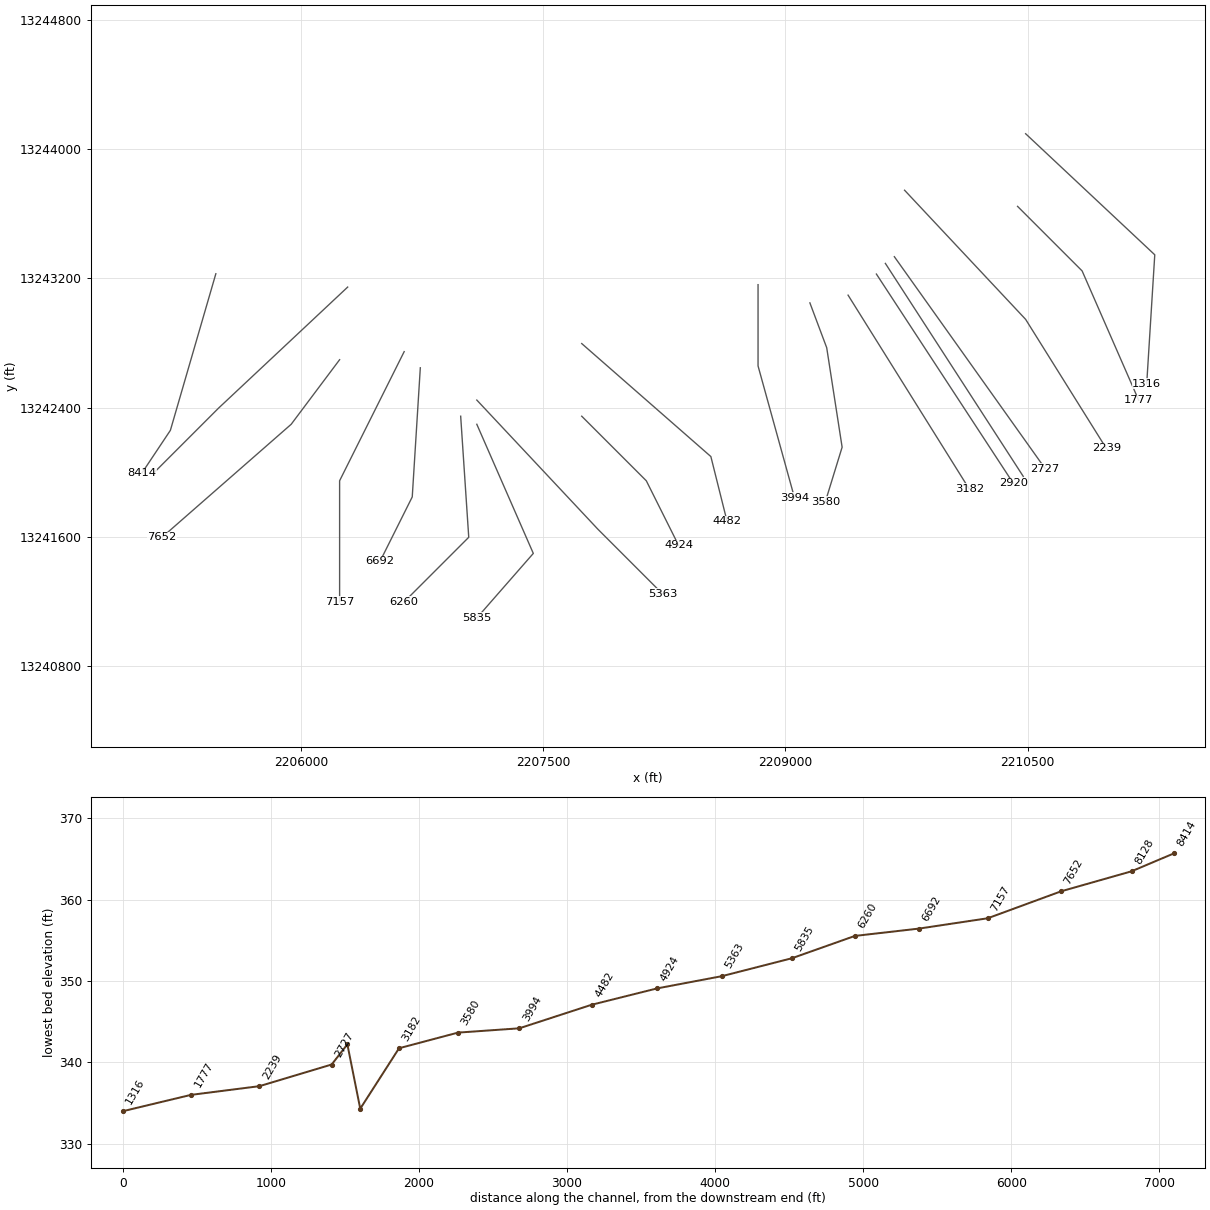
HEC-RAS study UNT 003 IN RACR.prj: UNT 003 IN RACR Base Level Engineering

--- UNT 003 IN RACR.g01 (geometry) --- (continued)

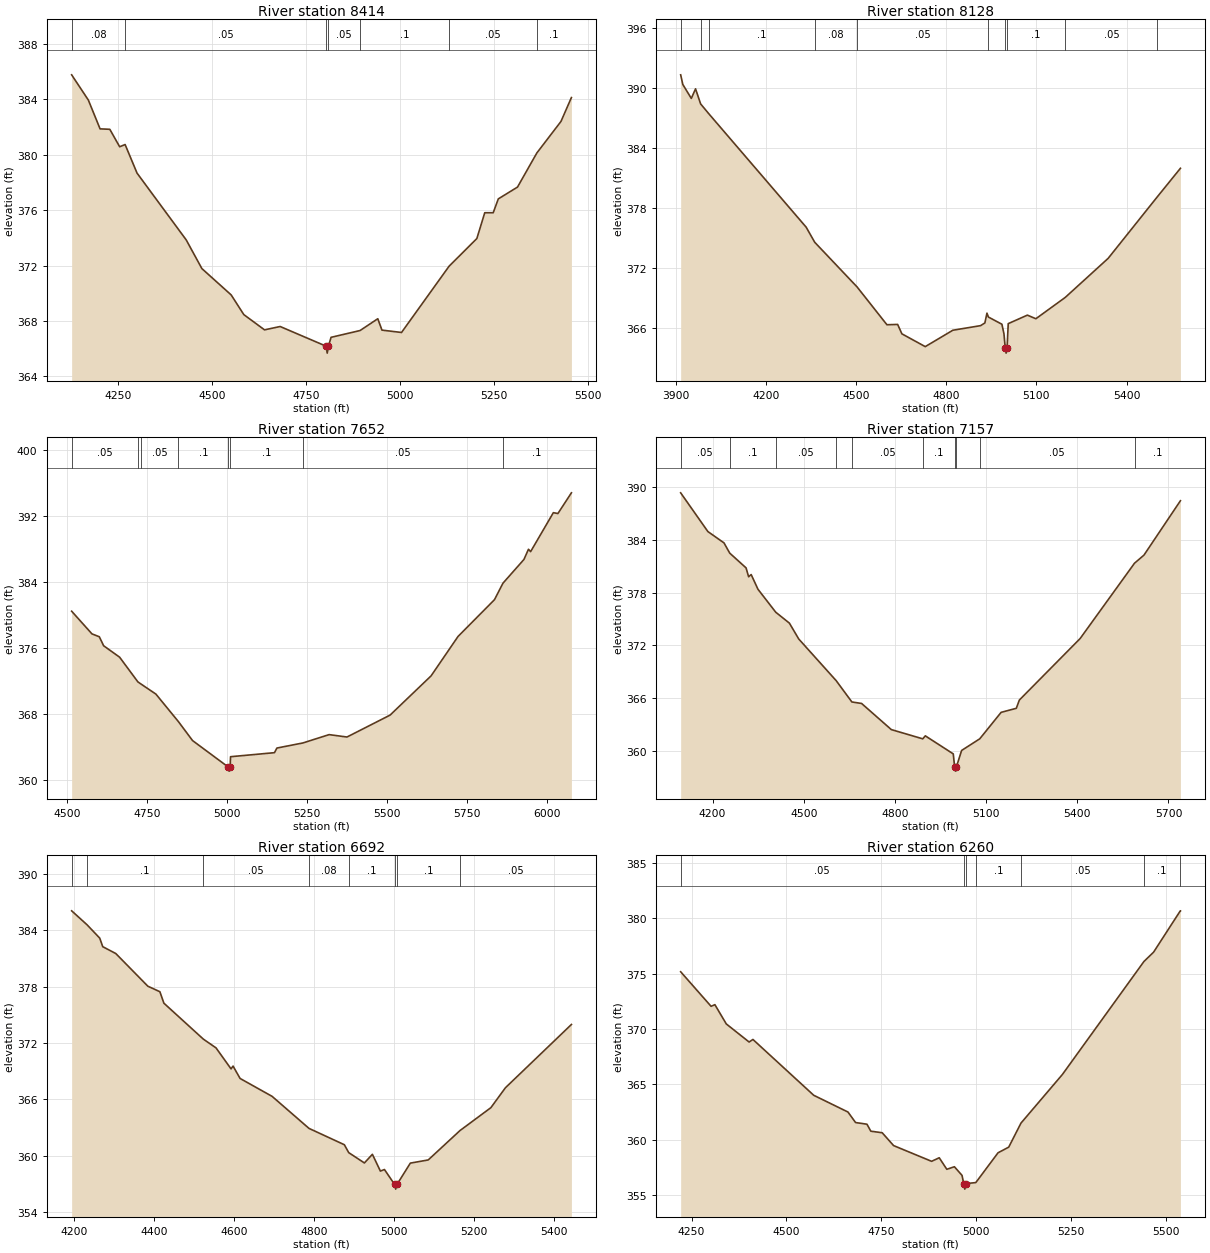
Type RM Length L Ch R = 1,8414,286,286,286
BEGIN DESCRIPTION:
Mapping XS 89754dc4
END DESCRIPTION:
XS GIS Cut Line= 3
      2205471.00     13243229.48      2205189.33     13242259.29
      2205012.36     13241993.83
#Sta/Elev= 30
  4127.3  385.76  4171.7  383.94  4202.9  381.86  4228.8  381.83  4255.0  380.57
  4269.5  380.73  4301.2  378.67  4432.0  373.85  4473.7  371.78  4551.6  369.88
  4585.2  368.46  4640.3  367.36  4681.9  367.60  4804.3  366.18  4807.1  365.68
  4810.3  366.18  4817.3  366.82  4894.4  367.31  4941.6  368.16  4952.7  367.34
  5004.7  367.17  5131.2  371.95  5205.1  373.95  5226.1  375.81  5248.6  375.81
  5262.2  376.81  5313.2  377.66  5364.6  380.12  5428.9  382.40  5456.6  384.12
#Mann=7,-1,0
  4127.3    0.08       0  4269.5    0.05       0  4804.3    0.07       0
  4810.3    0.05       0  4894.4     0.1       0  5131.2    0.05       0
  5364.6     0.1       0
Bank Sta=4804.3,4810.3
Exp/Cntr=0.3,0.1

Type RM Length L Ch R = 1,8128,476,476,476
BEGIN DESCRIPTION:
UNT 003 IN RACR 17.0
END DESCRIPTION:
XS GIS Cut Line= 3
      2206287.70     13243146.83      2205487.72     13242396.85
      2205087.75     13241996.88
#Sta/Elev= 30
  3916.8  391.32  3923.9  390.36  3952.2  388.96  3966.3  389.92  3983.2  388.41
  4010.3  387.43  4334.2  376.08  4362.7  374.57  4503.6  370.10  4602.8  366.32
  4638.5  366.35  4652.6  365.41  4730.3  364.13  4822.1  365.77  4914.4  366.23
  4928.6  366.50  4935.5  367.48  4940.3  367.09  4985.3  366.37  4992.1  365.41
  4996.4  363.98  4999.2  363.48  5002.4  363.98  5006.3  366.43  5069.9  367.28
  5098.2  366.92  5195.8  369.05  5338.6  372.96  5502.5  379.13  5579.0  381.97
#Mann=10,-1,0
  3916.8     0.1       0  3983.2    0.05       0  4010.3     0.1       0
  4362.7    0.08       0  4503.6    0.05       0  4940.3     0.1       0
  4996.4    0.07       0  5002.4     0.1       0  5195.8    0.05       0
  5502.5     0.1       0
Bank Sta=4996.4,5002.4
Exp/Cntr=0.3,0.1

Type RM Length L Ch R = 1,7652,495,495,495
BEGIN DESCRIPTION:
UNT 003 IN RACR 16.0
END DESCRIPTION:
XS GIS Cut Line= 3
      2206237.72     13242696.86      2205937.72     13242296.85
      2205137.73     13241596.87
#Sta/Elev= 30
  4514.8  380.43  4578.3  377.68  4601.3  377.33  4614.8  376.24  4664.8  374.85
  4722.0  371.85  4732.1  371.58  4778.3  370.37  4848.9  367.02  4892.9  364.73
  5004.5  361.52  5007.3  361.02  5010.5  361.52  5011.7  362.77  5149.1  363.26
  5156.7  363.82  5238.1  364.44  5319.9  365.45  5375.9  365.16  5510.7  367.82
  5638.9  372.58  5723.3  377.37  5837.2  381.83  5863.7  383.83  5929.3  386.71
  5943.5  387.95  5950.2  387.66  6021.3  392.39  6035.6  392.29  6077.8  394.80
#Mann=8,-1,0
  4514.8    0.05       0  4722.0    0.08       0  4732.1    0.05       0
  4848.9     0.1       0  5004.5    0.07       0  5010.5     0.1       0
  5238.1    0.05       0  5863.7     0.1       0
Bank Sta=5004.5,5010.5
Exp/Cntr=0.3,0.1

Type RM Length L Ch R = 1,7157,465,465,465
BEGIN DESCRIPTION:
UNT 003 IN RACR 15.0
END DESCRIPTION:
XS GIS Cut Line= 3
      2206637.73     13242746.88      2206237.72     13241946.85
      2206237.72     13241196.81
#Sta/Elev= 30
  4094.9  389.34  4184.4  384.94  4237.5  383.65  4256.3  382.49  4310.1  380.81
  4318.5  379.80  4326.9  380.05  4349.3  378.38  4407.8  375.77  4452.7  374.53
  4483.4  372.73  4606.7  367.99  4658.3  365.57  4690.3  365.40  4788.1  362.43
  4891.6  361.38  4899.9  361.72  4991.9  359.67  4996.4  358.21  4999.1  357.71
  5002.4  358.21  5019.4  360.06  5079.0  361.38  5149.4  364.39  5199.4  364.85
  5209.4  365.79  5409.4  372.78  5588.3  381.34  5619.4  382.26  5739.4  388.44
#Mann=10,-1,0
  4094.9    0.05       0  4256.3     0.1       0  4407.8    0.05       0
  4606.7    0.08       0  4658.3    0.05       0  4891.6     0.1       0
  4996.4    0.07       0  5002.4     0.1       0  5079.0    0.05       0
  5588.3     0.1       0
Bank Sta=4996.4,5002.4
Exp/Cntr=0.3,0.1

Type RM Length L Ch R = 1,6692,432,432,432
BEGIN DESCRIPTION:
UNT 003 IN RACR 14.0
END DESCRIPTION:
XS GIS Cut Line= 3
      2206737.72     13242646.89      2206687.72     13241846.85
      2206487.73     13241446.87
#Sta/Elev= 30
  4194.9  386.09  4233.2  384.61  4265.1  383.18  4272.6  382.27  4305.2  381.54
  4385.3  378.06  4415.4  377.47  4425.4  376.25  4524.0  372.42  4555.6  371.49
  4593.2  369.25  4598.2  369.55  4615.8  368.23  4695.9  366.32  4788.0  362.91
  4876.3  361.17  4887.2  360.33  4926.4  359.23  4946.4  360.15  4966.4  358.36
  4976.5  358.53  5001.9  356.94  5004.6  356.44  5007.9  356.94  5041.2  359.21
  5085.9  359.55  5165.3  362.68  5242.5  365.12  5278.8  367.24  5443.7  373.98
#Mann=8,-1,0
  4194.9    0.05       0  4233.2     0.1       0  4524.0    0.05       0
  4788.0    0.08       0  4887.2     0.1       0  5001.9    0.07       0
  5007.9     0.1       0  5165.3    0.05       0
Bank Sta=5001.9,5007.9
Exp/Cntr=0.3,0.1

Type RM Length L Ch R = 1,6260,425,425,425
BEGIN DESCRIPTION:
UNT 003 IN RACR 13.0
END DESCRIPTION:
XS GIS Cut Line= 3
      2206987.72     13242346.90      2207037.72     13241596.85
      2206637.72     13241196.85
#Sta/Elev= 30
  4221.2  375.16  4301.4  372.04  4311.4  372.19  4341.5  370.45  4401.6  368.82
  4411.7  369.05  4572.0  364.01  4662.2  362.50  4682.3  361.55  4712.3  361.40
  4722.4  360.77  4752.4  360.63  4782.5  359.47  4882.7  358.05  4902.8  358.37
  4922.8  357.33  4942.8  357.56  4962.9  356.78  4967.4  356.04  4970.2  355.54
  4973.4  356.04  4999.2  356.13  5057.8  358.82  5086.0  359.33  5118.3  361.50
  5227.5  365.89  5442.5  376.09  5467.9  376.93  5538.3  380.66  5538.6  380.66
#Mann=7,-1,0
  4221.2    0.05       0  4967.4    0.07       0  4973.4    0.05       0
  4999.2     0.1       0  5118.3    0.05       0  5442.5     0.1       0
  5538.3    0.05       0
Bank Sta=4967.4,4973.4
Exp/Cntr=0.3,0.1

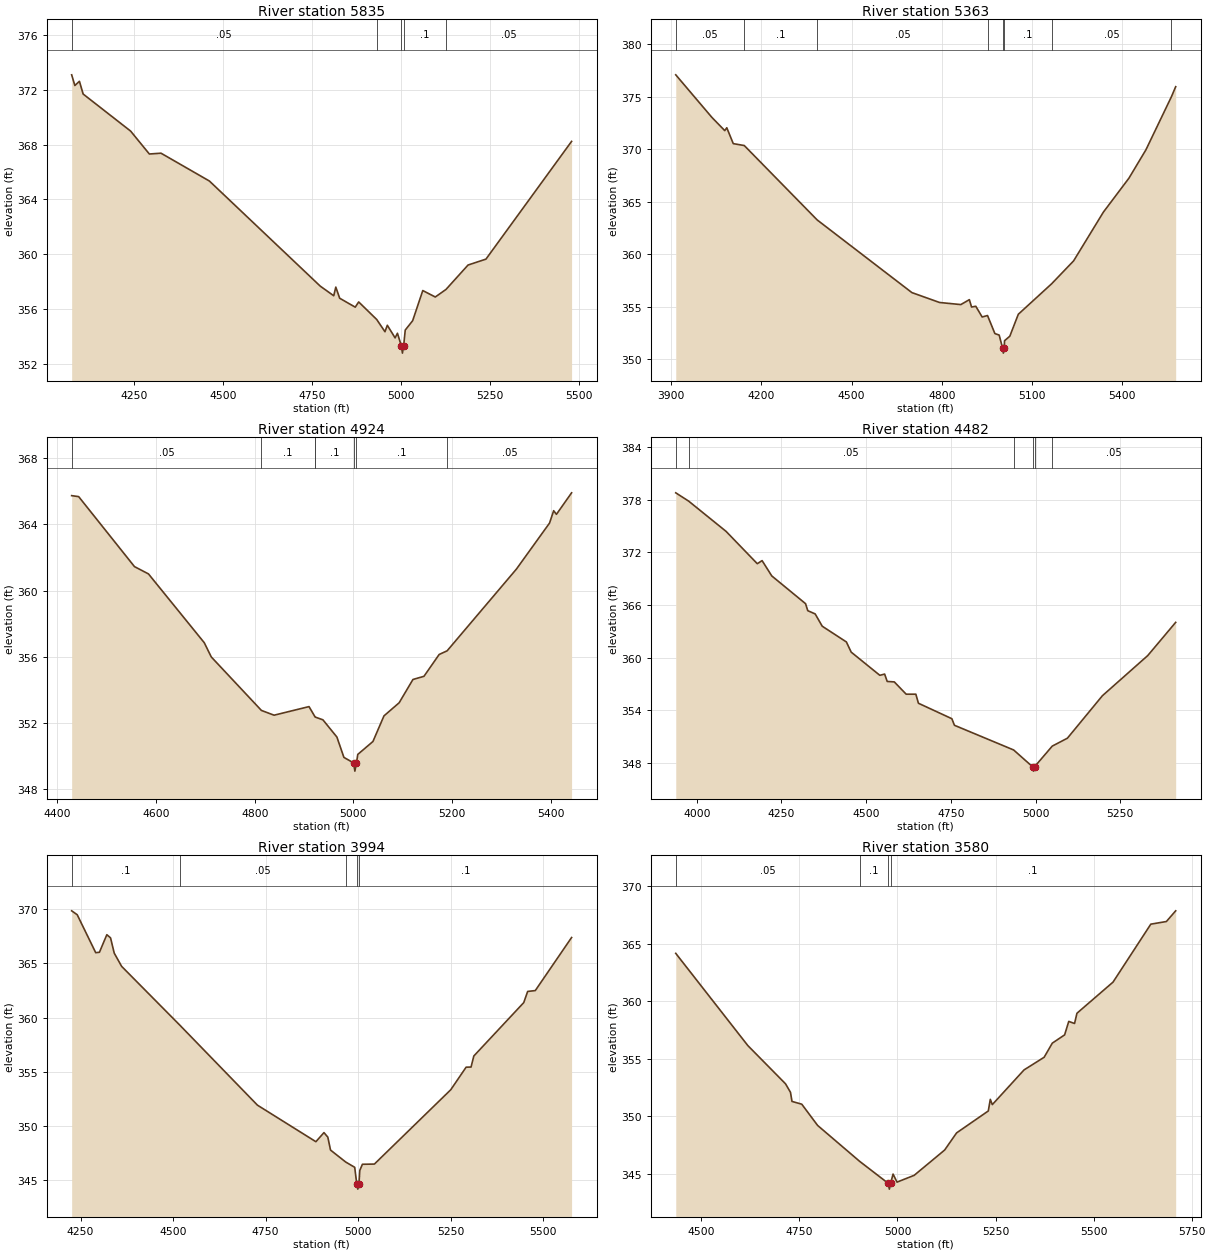
Type RM Length L Ch R = 1,5835,472,472,472
BEGIN DESCRIPTION:
UNT 003 IN RACR 12.0
END DESCRIPTION:
XS GIS Cut Line= 3
      2207087.73     13242296.84      2207437.72     13241496.85
      2207087.72     13241096.86
#Sta/Elev= 30
  4075.2  373.08  4084.2  372.30  4097.0  372.61  4107.5  371.68  4240.9  368.98
  4293.5  367.31  4326.2  367.37  4462.3  365.34  4773.8  357.68  4811.6  356.98
  4817.4  357.61  4828.3  356.80  4872.0  356.15  4881.7  356.53  4932.4  355.25
  4955.5  354.36  4962.2  354.83  4984.0  353.91  4990.6  354.25  5001.9  353.30
  5004.6  352.80  5007.9  353.30  5012.5  354.48  5033.3  355.16  5061.8  357.36
  5096.9  356.89  5127.0  357.44  5189.0  359.22  5239.3  359.65  5479.9  368.23
#Mann=5,-1,0
  4075.2    0.05       0  4932.4     0.1       0  5001.9    0.07       0
  5007.9     0.1       0  5127.0    0.05       0
Bank Sta=5001.9,5007.9
Exp/Cntr=0.3,0.1

Type RM Length L Ch R = 1,5363,439,439,439
BEGIN DESCRIPTION:
UNT 003 IN RACR 11.0
END DESCRIPTION:
XS GIS Cut Line= 3
      2207087.74     13242446.83      2207837.72     13241646.85
      2208237.69     13241246.89
#Sta/Elev= 30
  3915.4  377.09  4035.8  373.03  4078.3  371.78  4085.1  372.05  4106.6  370.54
  4143.2  370.36  4385.5  363.28  4700.6  356.36  4792.6  355.42  4863.2  355.22
  4891.6  355.69  4898.9  354.99  4913.0  355.06  4934.1  354.04  4952.0  354.18
  4976.5  352.46  4990.7  352.32  5001.9  351.10  5004.6  350.60  5007.9  351.10
  5008.5  351.78  5026.1  352.21  5054.4  354.30  5165.1  357.20  5238.2  359.38
  5337.2  364.02  5422.1  367.25  5478.6  369.95  5563.2  374.99  5577.6  375.96
#Mann=8,-1,0
  3915.4    0.05       0  4143.2     0.1       0  4385.5    0.05       0
  4952.0     0.1       0  5001.9    0.07       0  5007.9     0.1       0
  5165.1    0.05       0  5563.2     0.1       0
Bank Sta=5001.9,5007.9
Exp/Cntr=0.3,0.1

Type RM Length L Ch R = 1,4924,442,442,442
BEGIN DESCRIPTION:
UNT 003 IN RACR 10.0
END DESCRIPTION:
XS GIS Cut Line= 3
      2207737.70     13242346.87      2208137.72     13241946.85
      2208337.71     13241546.88
#Sta/Elev= 30
  4429.1  365.74  4443.3  365.68  4556.4  361.45  4584.7  361.01  4697.8  356.85
  4712.0  355.99  4813.5  352.76  4839.2  352.47  4910.0  352.99  4922.2  352.37
  4922.3  352.36  4938.2  352.19  4966.5  351.15  4980.7  349.92  5000.2  349.59
  5002.9  349.09  5006.2  349.59  5008.8  350.10  5039.5  350.88  5061.9  352.43
  5092.6  353.22  5120.6  354.63  5142.9  354.82  5173.7  356.14  5189.8  356.36
  5330.2  361.30  5397.3  364.08  5405.7  364.83  5411.3  364.61  5442.0  365.91
#Mann=7,-1,0
  4429.1    0.05       0  4813.5     0.1       0  4922.2    0.05       0
  4922.3     0.1       0  5000.2    0.07       0  5006.2     0.1       0
  5189.8    0.05       0
Bank Sta=5000.2,5006.2
Exp/Cntr=0.3,0.1

Type RM Length L Ch R = 1,4482,488,488,488
BEGIN DESCRIPTION:
UNT 003 IN RACR 9.0
END DESCRIPTION:
XS GIS Cut Line= 3
      2207737.72     13242796.85      2208537.72     13242096.85
      2208637.72     13241696.87
#Sta/Elev= 30
  3938.1  378.77  3976.0  377.83  4086.6  374.38  4178.7  370.70  4192.9  371.05
  4221.4  369.31  4321.1  366.15  4327.7  365.35  4349.5  364.98  4370.4  363.58
  4441.6  361.79  4455.8  360.63  4540.3  357.99  4554.5  358.13  4562.1  357.29
  4583.0  357.24  4618.1  355.84  4646.6  355.84  4654.2  354.81  4752.9  353.05
  4760.5  352.30  4935.2  349.49  4991.0  347.58  4993.7  347.08  4997.0  347.58
  5049.2  349.93  5093.9  350.83  5197.0  355.66  5331.0  360.24  5413.4  364.02
#Mann=6,-1,0
  3938.1     0.1       0  3976.0    0.05       0  4935.2     0.1       0
  4991.0    0.07       0  4997.0     0.1       0  5049.2    0.05       0
Bank Sta=4991,4997
Exp/Cntr=0.3,0.1

Type RM Length L Ch R = 1,3994,414,414,414
BEGIN DESCRIPTION:
UNT 003 IN RACR 8.0
END DESCRIPTION:
XS GIS Cut Line= 3
      2208830.00     13243161.83      2208830.00     13242658.31
      2209055.69     13241842.37
#Sta/Elev= 30
  4226.1  369.84  4241.1  369.48  4291.1  365.98  4301.1  366.02  4321.1  367.64
  4331.1  367.35  4341.1  365.94  4361.1  364.72  4518.0  359.31  4727.8  351.93
  4885.7  348.56  4907.5  349.40  4917.9  348.98  4925.2  347.79  4966.1  346.69
  4990.5  346.20  4996.0  344.69  4998.8  344.19  5002.0  344.69  5004.2  345.91
  5011.3  346.48  5043.7  346.50  5249.9  353.35  5291.4  355.43  5304.7  355.44
  5312.2  356.46  5447.0  361.38  5457.6  362.41  5478.2  362.49  5576.2  367.38
#Mann=5,-1,0
  4226.1     0.1       0  4518.0    0.05       0  4966.1     0.1       0
  4996.0    0.07       0  5002.0     0.1       0
Bank Sta=4996,5002
Exp/Cntr=0.3,0.1

Type RM Length L Ch R = 1,3580,398,398,398
BEGIN DESCRIPTION:
UNT 003 IN RACR 7.0
END DESCRIPTION:
XS GIS Cut Line= 4
      2209151.20     13243048.90      2209255.35     13242771.16
      2209350.84     13242154.84      2209246.67     13241816.30
#Sta/Elev= 30
  4434.8  364.17  4618.5  356.15  4714.7  352.82  4727.3  352.08  4731.1  351.29
  4756.0  351.05  4796.5  349.20  4903.5  346.08  4976.6  344.16  4979.4  343.66
  4982.6  344.16  4988.8  344.97  4998.9  344.27  5042.6  344.86  5120.3  347.06
  5150.7  348.55  5231.6  350.46  5236.7  351.47  5241.8  351.01  5322.7  354.03
  5373.9  355.13  5394.8  356.36  5426.2  357.08  5436.7  358.25  5451.5  358.07
  5457.6  358.96  5549.6  361.67  5645.9  366.71  5685.6  366.94  5709.3  367.87
#Mann=4,-1,0
  4434.8    0.05       0  4903.5     0.1       0  4976.6    0.07       0
  4982.6     0.1       0
Bank Sta=4976.6,4982.6
Exp/Cntr=0.3,0.1

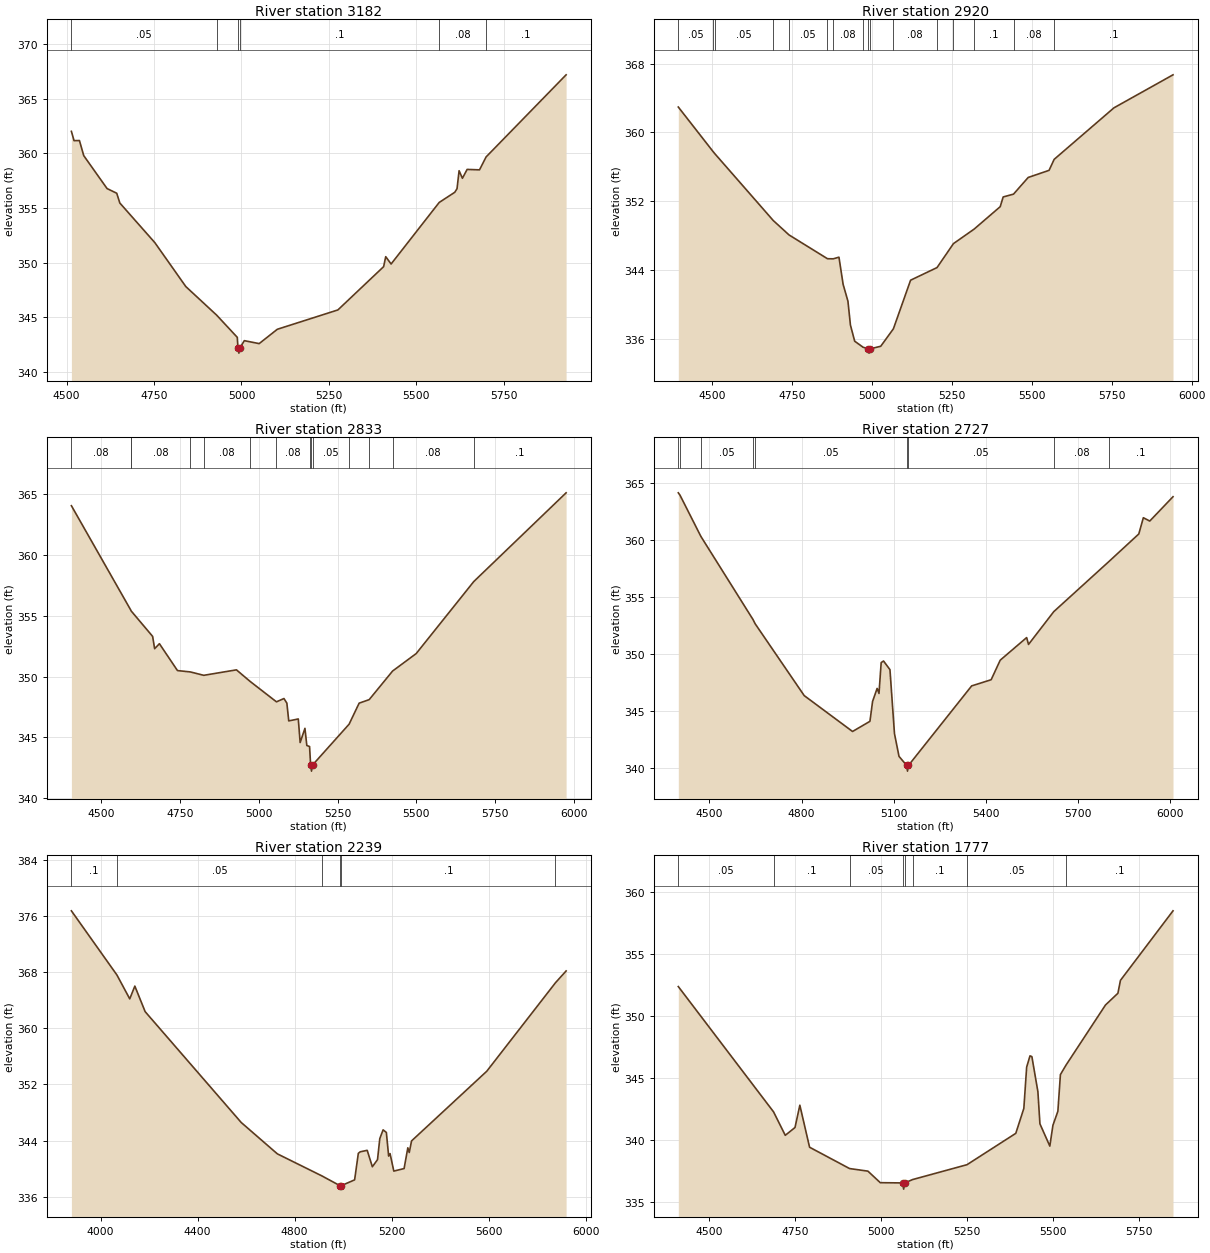
Type RM Length L Ch R = 1,3182,262,262,262
BEGIN DESCRIPTION:
UNT 003 IN RACR 6.0
END DESCRIPTION:
XS GIS Cut Line= 3
      2209387.74     13243096.82      2209637.72     13242696.85
      2210137.74     13241896.82
#Sta/Elev= 30
  4513.6  362.02  4521.2  361.17  4536.6  361.18  4548.9  359.80  4615.6  356.79
  4643.3  356.36  4652.1  355.47  4752.4  351.84  4840.8  347.83  4929.2  345.21
  4988.2  343.18  4989.9  342.24  4992.7  341.74  4995.9  342.24  5008.3  342.88
  5050.7  342.61  5102.6  343.92  5275.9  345.69  5406.8  349.65  5412.7  350.56
  5428.1  349.89  5565.7  355.52  5610.3  356.45  5616.7  356.78  5622.6  358.42
  5632.1  357.73  5645.6  358.54  5681.0  358.50  5699.8  359.68  5928.7  367.19
#Mann=6,-1,0
  4513.6    0.05       0  4929.2     0.1       0  4989.9    0.07       0
  4995.9     0.1       0  5565.7    0.08       0  5699.8     0.1       0
Bank Sta=4989.9,4995.9
Exp/Cntr=0.3,0.1

Type RM Length L Ch R = 1,2920,87,87,87
BEGIN DESCRIPTION:
Mapping XS 50048ca4
END DESCRIPTION:
XS GIS Cut Line= 2
      2209563.23     13243227.50      2210410.49     13241932.30
#Sta/Elev= 30
  4394.0  362.96  4503.1  357.76  4508.9  357.50  4691.0  349.75  4740.4  348.07
  4860.7  345.30  4878.9  345.29  4896.6  345.48  4909.6  342.32  4924.7  340.36
  4932.5  337.58  4945.8  335.70  4971.9  335.00  4988.1  334.81  4990.8  334.31
  4994.1  334.81  5027.3  335.11  5066.9  337.14  5120.7  342.80  5203.4  344.27
  5254.8  347.06  5319.2  348.74  5401.1  351.36  5410.3  352.49  5442.7  352.82
  5488.6  354.76  5553.9  355.59  5569.9  356.87  5757.0  362.87  5941.7  366.71
#Mann=16,-1,0
  4394.0    0.05       0  4503.1    0.08       0  4508.9    0.05       0
  4691.0    0.08       0  4740.4    0.05       0  4860.7     0.1       0
  4878.9    0.08       0  4971.9     0.1       0  4988.1    0.07       0
  4994.1     0.1       0  5066.9    0.08       0  5203.4     0.1       0
  5254.8    0.08       0  5319.2     0.1       0  5442.7    0.08       0
  5569.9     0.1       0
Bank Sta=4988.1,4994.1
Exp/Cntr=0.3,0.1

Type RM Length L Ch R = 1,2833,106,106,106
BEGIN DESCRIPTION:
Mapping XS 3e90d057
END DESCRIPTION:
XS GIS Cut Line= 2
      2209618.78     13243293.48      2210472.85     13241974.19
#Sta/Elev= 30
  4404.4  364.05  4592.7  355.48  4594.1  355.40  4662.5  353.30  4668.8  352.29
  4684.0  352.70  4741.4  350.49  4782.1  350.38  4824.9  350.10  4928.7  350.55
  4971.6  349.61  5055.8  347.92  5079.7  348.19  5088.9  347.81  5094.9  346.35
  5125.2  346.51  5131.1  344.57  5146.3  345.74  5152.3  344.33  5161.0  344.24
  5164.4  342.72  5167.2  342.22  5170.4  342.72  5286.6  346.08  5318.5  347.81
  5350.4  348.10  5424.7  350.45  5499.8  351.89  5682.6  357.81  5976.0  365.11
#Mann=14,-1,0
  4404.4    0.08       0  4592.7    0.05       0  4594.1    0.08       0
  4782.1    0.05       0  4824.9    0.08       0  4971.6    0.05       0
  5055.8    0.08       0  5161.0    0.05       0  5164.4    0.03       0
  5170.4    0.05       0  5286.6    0.08       0  5350.4     0.1       0
  5424.7    0.08       0  5682.6     0.1       0
Bank Sta=5164.4,5170.4
Exp/Cntr=0.3,0.1

Type RM Length L Ch R = 1,2727,488,488,488
BEGIN DESCRIPTION:
UNT 003 IN RACR 5.0
END DESCRIPTION:
XS GIS Cut Line= 2
      2209674.37     13243335.09      2210608.39     13242022.61
#Sta/Elev= 30
  4398.7  364.10  4404.3  363.89  4472.1  360.29  4641.7  353.02  4648.9  352.64
  4808.7  346.35  4966.1  343.21  5022.7  344.10  5031.3  345.84  5046.1  346.98
  5052.2  346.54  5059.3  349.24  5067.0  349.38  5087.9  348.62  5102.6  343.02
  5117.4  341.03  5142.2  340.24  5145.0  339.74  5148.2  340.24  5353.9  347.20
  5417.4  347.74  5446.9  349.45  5533.0  351.43  5539.1  350.83  5621.3  353.70
  5801.0  358.09  5898.2  360.50  5913.0  361.92  5933.9  361.63  6009.6  363.76
#Mann=9,-1,0
  4398.7    0.05       0  4404.3    0.08       0  4472.1    0.05       0
  4641.7    0.08       0  4648.9    0.05       0  5142.2    0.03       0
  5148.2    0.05       0  5621.3    0.08       0  5801.0     0.1       0
Bank Sta=5142.2,5148.2
Exp/Cntr=0.3,0.1

Type RM Length L Ch R = 1,2239,462,462,462
BEGIN DESCRIPTION:
UNT 003 IN RACR 4.0
END DESCRIPTION:
XS GIS Cut Line= 3
      2209737.73     13243746.84      2210487.72     13242946.85
      2210987.74     13242146.83
#Sta/Elev= 30
  3879.5  376.75  4067.3  367.60  4120.1  364.20  4141.1  366.02  4183.6  362.38
  4579.7  346.58  4728.7  342.11  4912.7  338.96  4986.6  337.58  4989.4  337.08
  4992.6  337.58  5047.4  338.40  5062.7  342.18  5070.4  342.40  5099.3  342.61
  5120.5  340.27  5141.8  341.28  5151.2  344.28  5164.8  345.53  5178.3  345.16
  5187.7  341.79  5193.6  342.14  5209.0  339.65  5251.4  340.01  5266.8  342.97
  5272.7  342.30  5282.1  343.95  5592.2  353.88  5875.7  366.50  5919.5  368.18
#Mann=6,-1,0
  3879.5     0.1       0  4067.3    0.05       0  4912.7     0.1       0
  4986.6    0.07       0  4992.6     0.1       0  5875.7    0.08       0
Bank Sta=4986.6,4992.6
Exp/Cntr=0.3,0.1

Type RM Length L Ch R = 1,1777,461,461,461
BEGIN DESCRIPTION:
UNT 003 IN RACR 3.0
END DESCRIPTION:
XS GIS Cut Line= 3
      2210437.75     13243646.82      2210837.72     13243246.85
      2211187.74     13242446.81
#Sta/Elev= 30
  4410.4  352.35  4687.5  342.24  4721.5  340.35  4749.8  340.98  4763.9  342.78
  4792.2  339.39  4908.5  337.67  4961.9  337.46  4997.9  336.53  5063.1  336.51
  5065.8  336.01  5069.1  336.51  5091.7  336.78  5250.0  337.98  5392.0  340.51
  5415.4  342.52  5423.6  345.85  5433.3  346.76  5438.8  346.70  5456.3  343.87
  5462.2  341.28  5491.0  339.48  5500.0  341.16  5514.4  342.29  5521.8  345.25
  5538.0  346.01  5652.8  350.86  5689.0  351.81  5696.4  352.85  5849.3  358.46
#Mann=8,-1,0
  4410.4    0.05       0  4687.5     0.1       0  4908.5    0.05       0
  5063.1    0.03       0  5069.1    0.05       0  5091.7     0.1       0
  5250.0    0.05       0  5538.0     0.1       0
Bank Sta=5063.1,5069.1
Exp/Cntr=0.3,0.1

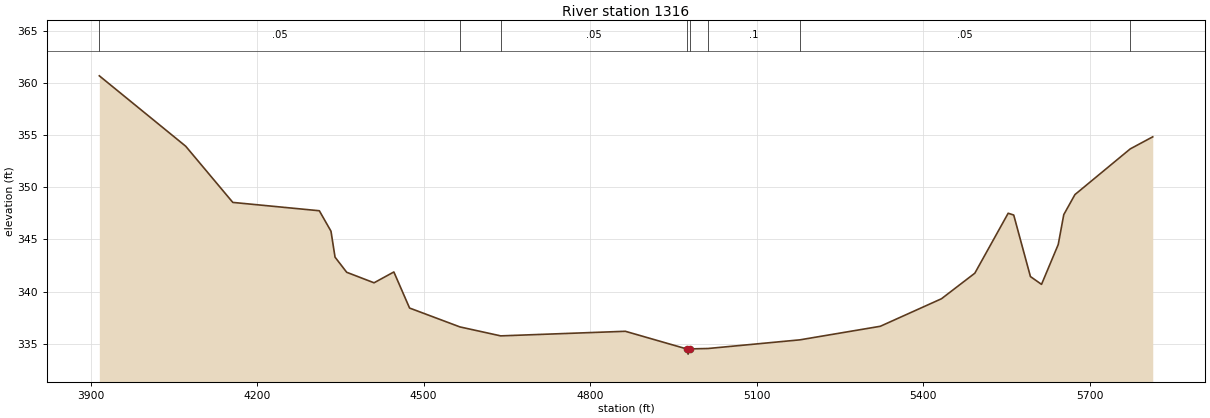
Type RM Length L Ch R = 1,1316,482,482,482
BEGIN DESCRIPTION:
UNT 003 IN RACR 2.0
END DESCRIPTION:
XS GIS Cut Line= 3
      2210487.73     13244096.84      2211287.72     13243346.85
      2211237.72     13242546.88
#Sta/Elev= 30
  3915.7  360.69  4071.3  353.94  4156.2  348.55  4312.1  347.75  4333.1  345.79
  4340.4  343.30  4361.4  341.85  4410.7  340.84  4446.4  341.88  4474.7  338.42
  4565.4  336.61  4638.9  335.75  4863.5  336.19  4973.9  334.50  4976.6  334.00
  4979.9  334.50  5012.7  334.54  5178.1  335.37  5322.9  336.67  5433.1  339.31
  5493.2  341.76  5553.3  347.51  5563.3  347.34  5593.4  341.44  5613.4  340.69
  5643.5  344.51  5653.5  347.38  5673.6  349.30  5773.2  353.68  5813.8  354.84
#Mann=8,-1,0
  3915.7    0.05       0  4565.4     0.1       0  4638.9    0.05       0
  4973.9    0.03       0  4979.9    0.05       0  5012.7     0.1       0
  5178.1    0.05       0  5773.2     0.1       0
Bank Sta=4973.9,4979.9
Exp/Cntr=0.3,0.1