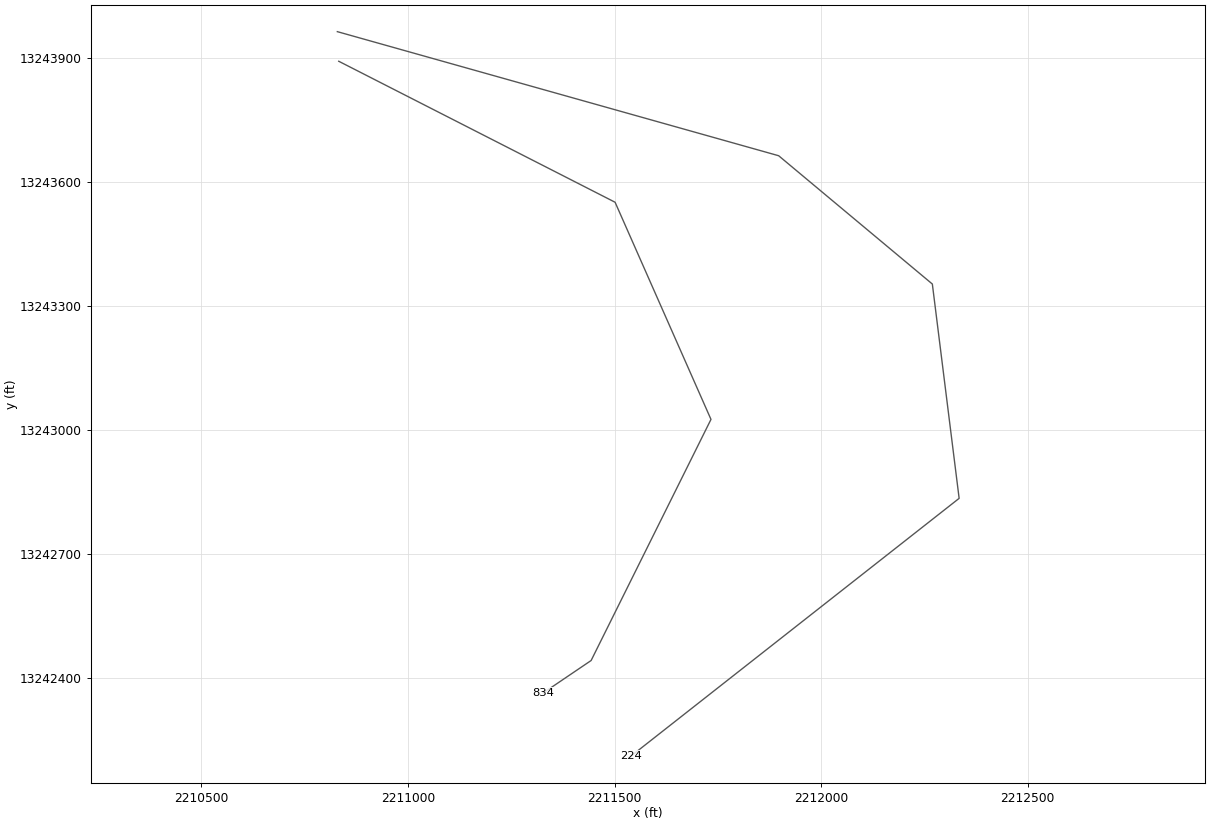
HEC-RAS study UNT 003 IN RACR.prj: UNT 003 IN RACR Base Level Engineering

--- UNT 003 IN RACR.g01 (geometry) --- (continued)

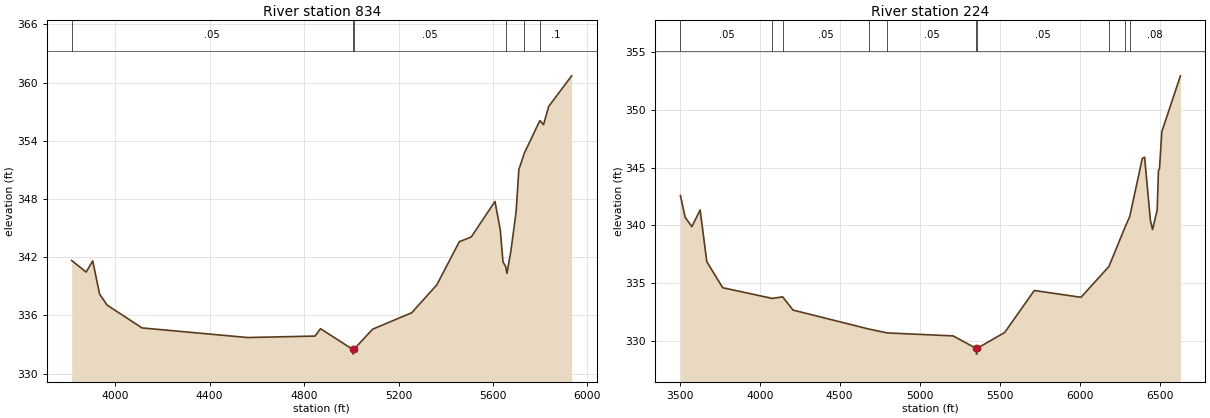
Type RM Length L Ch R = 1,834,610,610,610
BEGIN DESCRIPTION:
Mapping XS 1534eb26
END DESCRIPTION:
XS GIS Cut Line= 5
      2210832.35     13243891.95      2211501.23     13243550.68
      2211733.30     13243025.12      2211443.22     13242441.55
      2211327.19     13242363.06
#Sta/Elev= 30
  3815.9  341.67  3877.3  340.47  3905.1  341.62  3934.2  338.20  3966.2  337.07
  4113.8  334.72  4560.7  333.73  4846.3  333.88  4869.6  334.64  5005.3  332.52
  5008.0  332.02  5011.3  332.52  5090.3  334.59  5255.8  336.28  5362.2  339.16
  5457.4  343.60  5507.9  344.09  5608.4  347.75  5630.8  344.83  5642.2  341.53
  5653.8  341.03  5659.0  340.34  5675.4  342.58  5697.8  346.67  5709.4  351.02
  5732.6  352.72  5798.4  356.08  5814.0  355.66  5835.9  357.54  5933.1  360.69
#Mann=6,-1,0
  3815.9    0.05       0  5005.3    0.03       0  5011.3    0.05       0
  5653.8     0.1       0  5732.6    0.05       0  5798.4     0.1       0
Bank Sta=5005.3,5011.3
Exp/Cntr=0.3,0.1

Type RM Length L Ch R = 1,224,0,0,0
BEGIN DESCRIPTION:
UNT 003 IN RACR 1.0
END DESCRIPTION:
XS GIS Cut Line= 5
      2210828.93     13243963.61      2211897.11     13243663.29
      2212269.09     13243352.74      2212333.93     13242834.01
      2211540.29     13242210.68
#Sta/Elev= 30
  3504.3  342.59  3534.2  340.69  3575.8  339.89  3627.7  341.33  3669.2  336.85
  3768.7  334.59  4079.0  333.66  4143.4  333.80  4208.5  332.65  4680.8  331.01
  4797.6  330.67  5209.3  330.41  5353.3  329.33  5356.1  328.83  5359.3  329.33
  5531.8  330.71  5716.8  334.35  6008.8  333.76  6183.5  336.43  6284.1  339.84
  6313.4  340.76  6392.1  345.81  6406.5  345.91  6442.9  340.42  6456.2  339.64
  6485.1  341.33  6493.2  344.77  6499.6  344.90  6514.0  348.12  6630.4  352.97
#Mann=10,-1,0
  3504.3    0.05       0  4079.0     0.1       0  4143.4    0.05       0
  4680.8     0.1       0  4797.6    0.05       0  5353.3    0.03       0
  5359.3    0.05       0  6183.5    0.08       0  6284.1    0.05       0
  6313.4    0.08       0
Bank Sta=5353.3,5359.3
Exp/Cntr=0.3,0.1

Chan Stop Cuts=-1