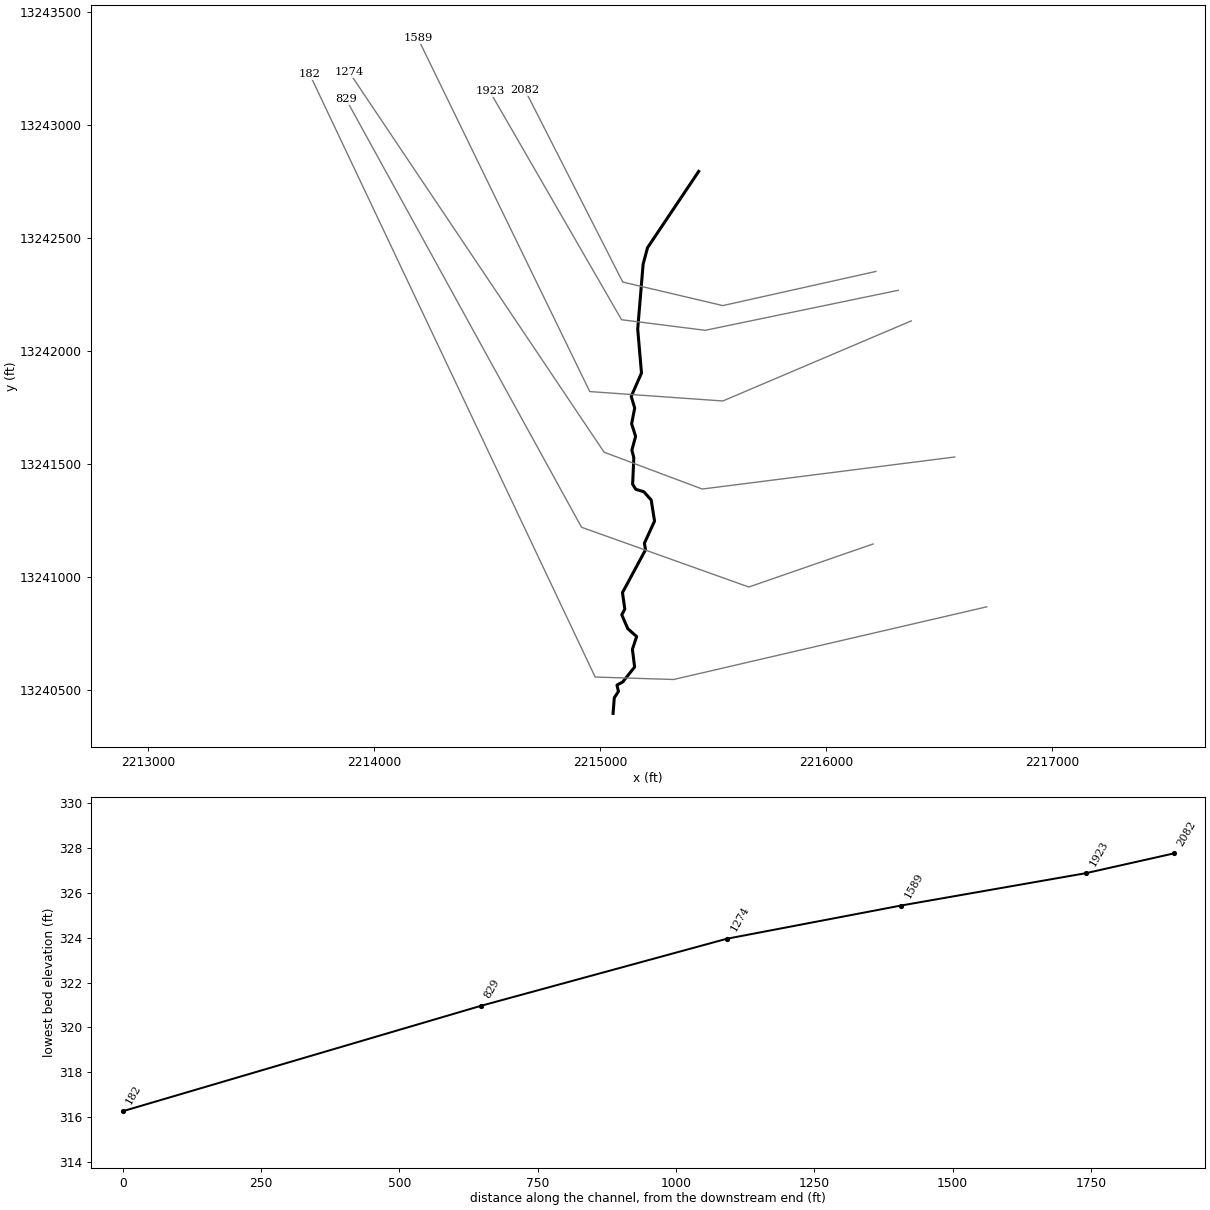
--- UNT 004 IN RACR.prj (project) ---

Proj Title=UNT 004 IN RACR Base Level Engineering
Current Plan=p01
Default Exp/Contr=0.3,0.1
English Units
Geom File=g01
Flow File=f01
Plan File=p01
Y Axis Title=Elevation
X Axis Title(PF)=Main Channel Distance
X Axis Title(XS)=Station
BEGIN DESCRIPTION:
UNT 004 IN RACR
END DESCRIPTION:
DSS Export Rating Curves= 0
DSS Export Rating Curve Sorted= 0
DSS Export Volume Flow Curves= 0
DXF OffsetX= 0
DXF OffsetY= 0
DXF ScaleX= 1
DXF ScaleY= 10

--- UNT 004 IN RACR.p01 (plan) ---

Plan Title=Multiple Run
Short Identifier=Multiple
Geom File=g01
Flow File=f01
Subcritical Flow
K Sum by GR= 0
Std Step Tol= 0.01
Critical Tol= 0.01
Num of Std Step Trials= 20
Max Error Tol= 0.3
Flow Tol Ratio= 0.001
Split Flow NTrial= 30
Split Flow Tol= 0.02
Split Flow Ratio= 0.02
Log Output Level= 0
Friction Slope Method= 1
Unsteady Friction Slope Method= 2
Unsteady Bridges Friction Slope Method= 1
Parabolic Critical Depth
Global Vel Dist=  1 , 1 , 1
Global Log Level= 0
CheckData=True
Encroach Param= -1, 0, 0, 0
BEGIN DESCRIPTION:
Multiple Run
END DESCRIPTION:

--- UNT 004 IN RACR.f01 (steady flow) ---

Flow Title=Multiple
Number of Profiles=7
Profile Names=10-year,25-year,50-year,1pct_min,100-year,1pct_plu,500-year
River Rch & RM= UNT 004 IN RACR,Reach-1,2082
     238     335     416     381     516     698     804
Boundary for River Rch & Prof#=UNT 004 IN RACR,Reach-1,1
Up Type=0
Dn Type=3
Dn Slope=0.005
Boundary for River Rch & Prof#=UNT 004 IN RACR,Reach-1,2
Up Type=0
Dn Type=3
Dn Slope=0.005
Boundary for River Rch & Prof#=UNT 004 IN RACR,Reach-1,3
Up Type=0
Dn Type=3
Dn Slope=0.005
Boundary for River Rch & Prof#=UNT 004 IN RACR,Reach-1,4
Up Type=0
Dn Type=3
Dn Slope=0.005
Boundary for River Rch & Prof#=UNT 004 IN RACR,Reach-1,5
Up Type=0
Dn Type=3
Dn Slope=0.005
Boundary for River Rch & Prof#=UNT 004 IN RACR,Reach-1,6
Up Type=0
Dn Type=3
Dn Slope=0.005
Boundary for River Rch & Prof#=UNT 004 IN RACR,Reach-1,7
Up Type=0
Dn Type=3
Dn Slope=0.005

--- UNT 004 IN RACR.g01 (geometry) ---

Geom Title=Existing Conditions
Program Version=4.10

River Reach=UNT 004 IN RACR ,Reach-1
Reach XY= 30
      2215436.48     13242793.72      2215210.09     13242456.22
      2215190.64      13242383.3      2215166.69     13242096.32
      2215183.41     13241902.09        2215138.      13241798.5
      2215153.34     13241747.28      2215139.86     13241677.43
      2215157.37     13241621.84      2215140.97     13241561.25
       2215149.5     13241526.89      2215144.23     13241410.38
      2215157.88     13241387.89       2215193.9     13241376.88
      2215226.33     13241340.57      2215241.16     13241247.22
      2215196.35     13241149.21      2215201.33     13241120.35
      2215099.34     13240930.96      2215109.64     13240857.78
       2215096.2      13240832.9      2215122.93     13240771.18
      2215161.99     13240736.76      2215143.27     13240680.13
      2215153.01     13240601.87       2215100.8     13240536.21
      2215074.92      13240521.8      2215081.44     13240493.88
      2215063.14     13240465.88      2215057.72     13240396.86

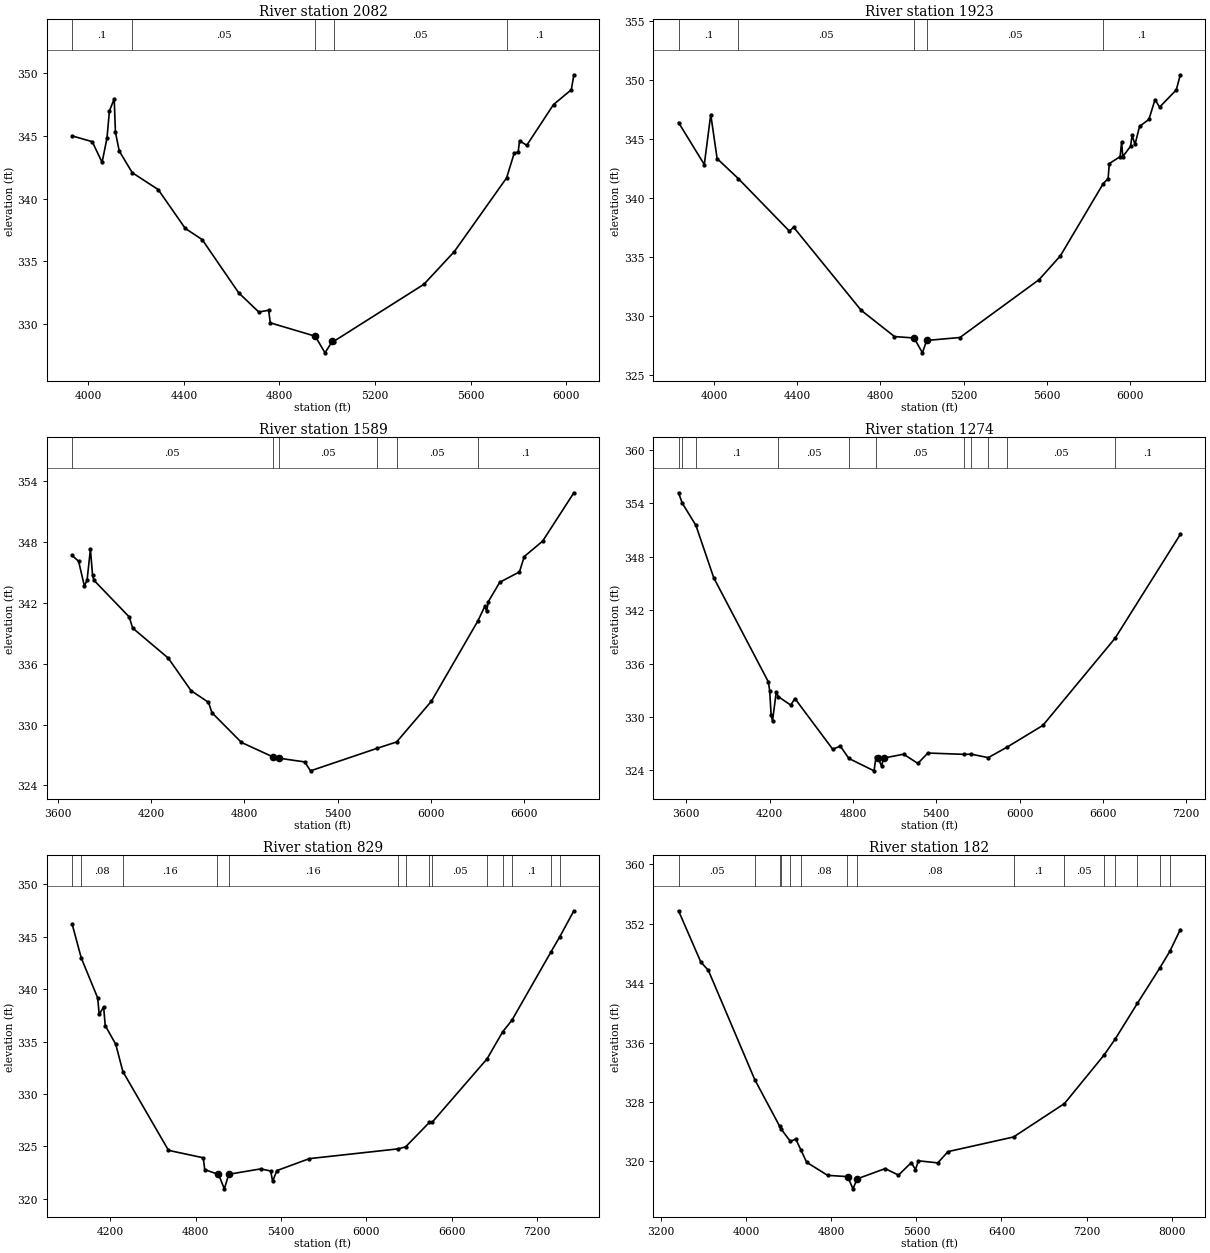
Type RM Length L Ch R = 1 ,2082    ,159,159,159
BEGIN DESCRIPTION:
UNT 004 IN RACR 5.0
END DESCRIPTION:
XS GIS Cut Line= 4
      2216220.35     13242351.28      2215543.23     13242200.23
      2215100.52      13242304.4      2214668.61      13243152.6
#Sta/Elev= 30
  3931.8  344.97  4016.2  344.51  4057.4  342.87  4077.9  344.79  4088.2  346.95
  4108.2  347.91  4113.3  345.27  4129.2  343.77  4183.7  342.05  4292.3  340.71
  4405.8  337.62  4476.4  336.74  4629.4  332.51  4713.4  330.99  4754.5  331.13
  4761.6  330.13  4949.7  329.07  4990.5  327.75    5021  328.66  5026.2  328.65
  5404.5  333.19    5532  335.79  5750.5  341.63  5782.6   343.6  5799.2  343.69
  5804.8  344.59    5835  344.22  5947.2  347.46  6021.6  348.63  6032.2  349.82
#Mann= 5 ,-1 , 0
  3931.8      .1       0  4183.7     .05       0  4949.7     .03       0
  5026.2     .05       0  5750.5      .1       0
Bank Sta=4949.7,5021
XS Rating Curve= 0 ,0
Exp/Cntr=0.3,0.1

Type RM Length L Ch R = 1 ,1923    ,334,334,334
BEGIN DESCRIPTION:
UNT 004 IN RACR 4.0
END DESCRIPTION:
XS GIS Cut Line= 4
       2216319.3     13242267.95       2215465.1     13242090.86
      2215095.31     13242137.73      2214512.34     13243147.52
#Sta/Elev= 30
  3829.8   346.4  3953.6  342.84  3984.6  347.08  4015.2  343.34  4116.9  341.65
  4362.5  337.19  4382.9  337.52  4707.3  330.48  4867.5  328.25  4961.6  328.13
  5001.7  326.87  5022.1  327.92  5181.9  328.17  5562.4  333.08  5664.3  335.09
  5870.8  341.23  5893.7  341.64  5899.8  342.92  5951.5  343.51  5958.7  344.73
  5964.5  343.51  6001.8  344.39  6009.2  345.31  6023.3  344.55  6044.9  346.07
    6090  346.67  6119.5  348.35  6141.1   347.7  6221.5  349.17  6240.9  350.45
#Mann= 5 ,-1 , 0
  3829.8      .1       0  4116.9     .05       0  4961.6     .03       0
  5022.1     .05       0  5870.8      .1       0
Bank Sta=4961.6,5022.1
XS Rating Curve= 0 ,0
Exp/Cntr=0.3,0.1

Type RM Length L Ch R = 1 ,1589    ,315,315,315
BEGIN DESCRIPTION:
UNT 004 IN RACR 3.0
END DESCRIPTION:
XS GIS Cut Line= 4
      2216376.58     13242132.53      2215543.23     13241778.36
      2214954.69     13241820.02      2214194.45     13243382.15
#Sta/Elev= 30
  3689.4  346.69  3731.6  346.11  3768.7  343.66    3786  344.24  3807.7   347.3
  3821.5  344.72  3829.4  344.25  4057.6  340.62  4079.7  339.52  4308.8  336.56
  4456.2  333.34  4568.3  332.19  4590.4  331.17  4780.9  328.23  4981.4  326.82
  5021.5  326.68  5188.2  326.31  5225.6  325.43  5652.1  327.64  5780.4  328.28
  6004.4   332.3  6303.7  340.22  6349.1  341.68  6360.3  341.17  6371.4  342.14
    6445  344.04  6571.6  345.06  6602.8  346.58  6721.1   348.1  6922.2  352.87
#Mann= 6 ,-1 , 0
  3689.4     .05       0  4981.4     .03       0  5021.5     .05       0
  5652.1      .1       0  5780.4     .05       0  6303.7      .1       0
Bank Sta=4981.4,5021.5
XS Rating Curve= 0 ,0
Exp/Cntr=0.3,0.1

Type RM Length L Ch R = 1 ,1274    ,445,445,445
BEGIN DESCRIPTION:
UNT 004 IN RACR 2.0
END DESCRIPTION:
XS GIS Cut Line= 4
      2216569.17     13241530.69      2215452.14     13241388.93
      2215018.11     13241551.69      2213890.19     13243232.72
#Sta/Elev= 30
  3543.9  355.17  3570.6  354.01  3669.1  351.51  3797.4  345.63  4190.5  333.95
  4200.6  332.93  4210.7   330.2  4220.7  329.55  4247.7   332.8  4262.6  332.28
  4351.8  331.33    4382  332.07  4654.2  326.38  4709.3  326.72  4770.7  325.34
    4952  323.95  4965.7  325.46 4979.14  325.44  5005.7  324.49  5020.8  325.38
  5165.4  325.82  5267.4  324.78  5339.4  325.95  5601.7   325.8    5653  325.82
  5774.5  325.43  5907.7  326.59  6167.7  329.05  6688.4  338.85  7157.8   350.5
#Mann= 11 ,-1 , 0
  3543.9     .05       0  3570.6     .08       0  3669.1      .1       0
  4262.6     .05       0  4770.7     .03       0  4965.7     .05       0
  5601.7      .1       0    5653     .05       0  5774.5      .1       0
  5907.7     .05       0  6688.4      .1       0
Bank Sta=4979.14,5020.8
XS Rating Curve= 0 ,0
Exp/Cntr=0.3,0.1

Type RM Length L Ch R = 1 ,829     ,647,647,647
BEGIN DESCRIPTION:
Mapping XS 6d0b1fb6
END DESCRIPTION:
XS GIS Cut Line= 4
      2216207.92     13241145.96      2215658.17     13240955.66
      2214918.19     13241219.95      2213877.03     13243111.99
#Sta/Elev= 30
  3932.3  346.23  3996.9  342.97  4112.4  339.16    4123  337.59  4154.1  338.31
  4165.3  336.53  4239.4  334.74  4289.4  332.14  4610.1  324.63  4854.3  323.92
  4864.9  322.79    4952  322.38  4960.5  322.38  5002.7  320.96  5033.7  322.35
  5257.8  322.86  5328.4  322.66  5341.9  321.68  5371.9   322.7  5600.1  323.84
    6224  324.77  6276.6  324.96  6443.6  327.29    6464  327.32  6849.1  333.35
    6960  335.95  7023.5  337.02  7298.1  343.54  7361.1  345.01  7459.4  347.47
#Mann= 14 ,-1 , 0
  3932.3     .05       0  3996.9     .08       0  4289.4     .16       0
    4952     .07       0  5033.7     .16       0    6224      .1       0
  6276.6     .05       0  6443.6      .1       0    6464     .05       0
  6849.1     .08       0    6960     .05       0  7023.5      .1       0
  7298.1     .05       0  7361.1      .1       0
Bank Sta=4960.5,5033.7
XS Rating Curve= 0 ,0
Exp/Cntr=0.3,0.1

Type RM Length L Ch R = 1 ,182     ,0,0,0
BEGIN DESCRIPTION:
UNT 004 IN RACR 1.0
END DESCRIPTION:
XS GIS Cut Line= 4
      2216710.81     13240868.09      2215325.81     13240546.69
      2214978.59     13240557.54      2213716.23     13243222.26
#Sta/Elev= 30
  3363.7  353.76  3572.8  346.86    3644  345.73  4080.9  330.98  4315.6  324.68
  4329.3  324.31  4415.7  322.66  4465.3  322.99  4515.8  321.47    4568  319.85
  4765.4  318.09  4949.7  317.92  4954.8  317.88  5003.4  316.27  5043.7  317.62
  5306.9     319  5431.7  318.12  5552.6  319.81  5590.9  318.86  5619.2  320.05
  5801.1  319.77  5897.6  321.29  6513.2  323.26  6992.2  327.77  7362.9  334.28
  7470.6   336.5  7677.3  341.27    7890  346.08  7983.4  348.31  8081.5  351.23
#Mann= 15 ,-1 , 0
  3363.7     .05       0  4080.9      .1       0  4315.6     .08       0
  4329.3      .1       0  4415.7     .08       0  4515.8     .08       0
  4949.7     .05       0  5043.7     .08       0  6513.2      .1       0
  6992.2     .05       0  7362.9     .08       0  7470.6      .1       0
  7677.3     .05       0    7890      .1       0  7983.4     .05       0
Bank Sta=4954.8,5043.7
XS Rating Curve= 0 ,0
Exp/Cntr=0.3,0.1

Chan Stop Cuts=-1
Use User Specified Reach Order=0
Composite Channel Slope=5