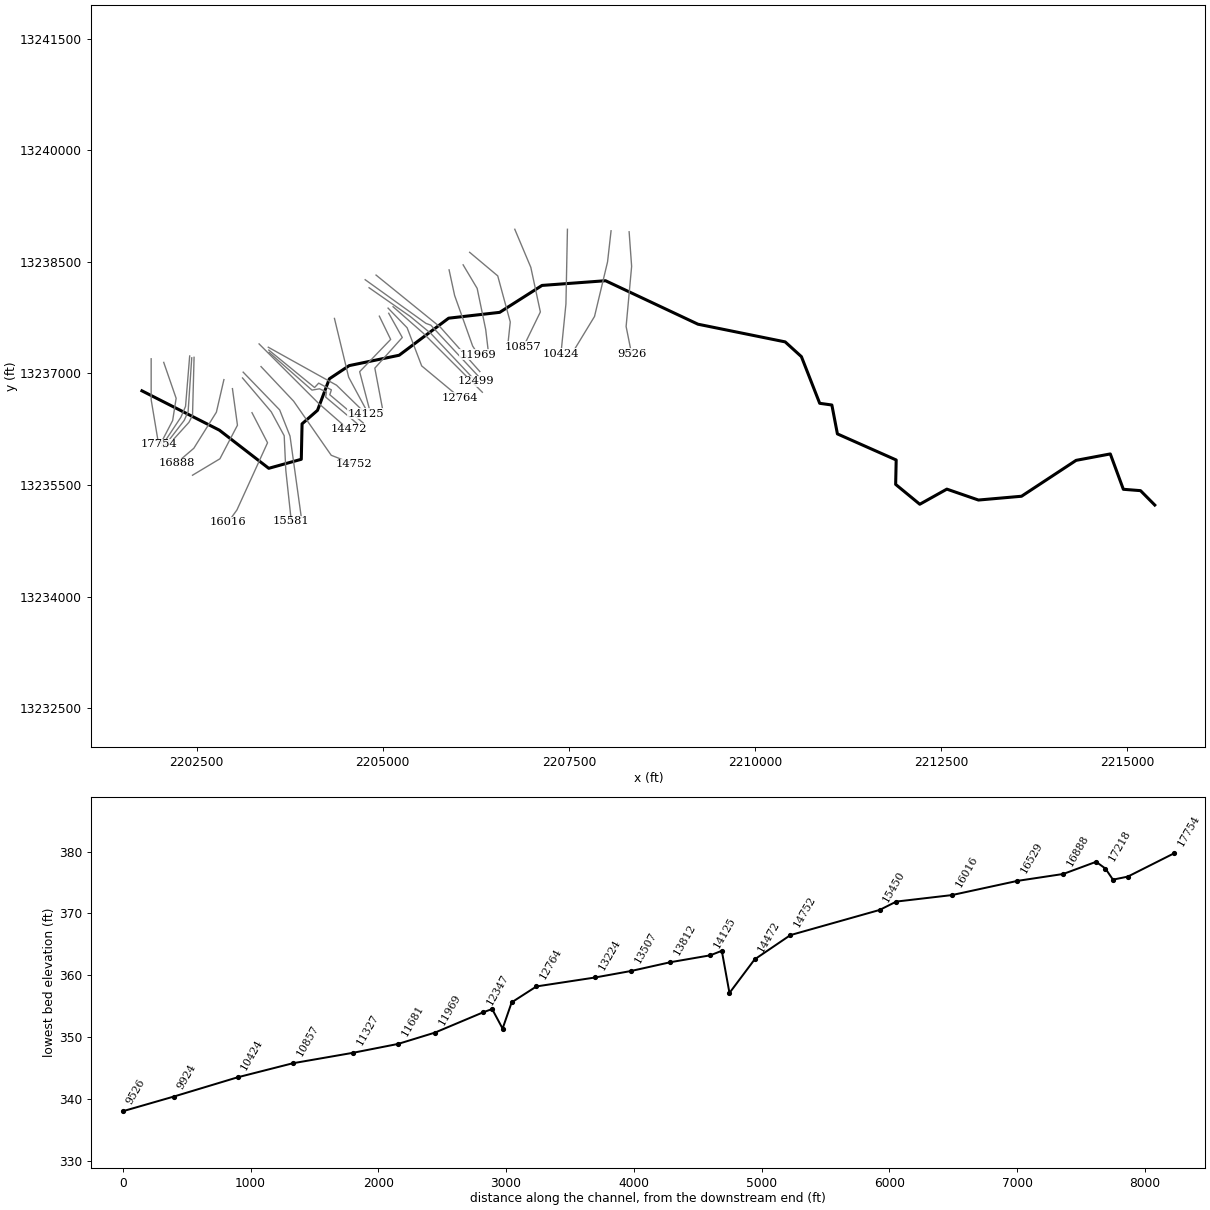
--- UNT 005 IN RACR.prj (project) ---

Proj Title=UNT 005 IN RACR Base Level Engineering
Current Plan=p01
Default Exp/Contr=0.3,0.1
English Units
Geom File=g01
Flow File=f01
Plan File=p01
Y Axis Title=Elevation
X Axis Title(PF)=Main Channel Distance
X Axis Title(XS)=Station
BEGIN DESCRIPTION:
UNT 005 IN RACR
END DESCRIPTION:
DSS Export Rating Curves= 0
DSS Export Rating Curve Sorted= 0
DSS Export Volume Flow Curves= 0
DXF OffsetX= 0
DXF OffsetY= 0
DXF ScaleX= 1
DXF ScaleY= 10

--- UNT 005 IN RACR.p01 (plan) ---

Plan Title=Multiple Run
Short Identifier=Multiple
Geom File=g01
Flow File=f01
Subcritical Flow
K Sum by GR= 0
Std Step Tol= 0.01
Critical Tol= 0.01
Num of Std Step Trials= 20
Max Error Tol= 0.3
Flow Tol Ratio= 0.001
Split Flow NTrial= 30
Split Flow Tol= 0.02
Split Flow Ratio= 0.02
Log Output Level= 0
Friction Slope Method= 1
Unsteady Friction Slope Method= 2
Unsteady Bridges Friction Slope Method= 1
Parabolic Critical Depth
Global Vel Dist=  1 , 1 , 1
Global Log Level= 0
CheckData=True
Encroach Param= -1, 0, 0, 0
BEGIN DESCRIPTION:
Multiple Run
END DESCRIPTION:

--- UNT 005 IN RACR.f01 (steady flow) ---

Flow Title=Multiple
Program Version=4.10
Number of Profiles= 7
Profile Names=10-year,25-year,50-year,1pct_min,100-year,1pct_plu,500-year
River Rch & RM=UNT 005 IN RACR,Reach-1         ,17754
     193     267     328     297     402     543     612
River Rch & RM=UNT 005 IN RACR,Reach-1         ,17393
     242     337     417     379     512     693     787
River Rch & RM=UNT 005 IN RACR,Reach-1         ,13224
     332     469     585     537     726     982    1134
River Rch & RM=UNT 005 IN RACR,Reach-1         ,8285
     420     600     753     694     938    1269    1481
Boundary for River Rch & Prof#=UNT 005 IN RACR,Reach-1         , 1
Up Type= 0
Dn Type= 3
Dn Slope=0.005
Boundary for River Rch & Prof#=UNT 005 IN RACR,Reach-1         , 2
Up Type= 0
Dn Type= 3
Dn Slope=0.005
Boundary for River Rch & Prof#=UNT 005 IN RACR,Reach-1         , 3
Up Type= 0
Dn Type= 3
Dn Slope=0.005
Boundary for River Rch & Prof#=UNT 005 IN RACR,Reach-1         , 4
Up Type= 0
Dn Type= 3
Dn Slope=0.005
Boundary for River Rch & Prof#=UNT 005 IN RACR,Reach-1         , 5
Up Type= 0
Dn Type= 3
Dn Slope=0.005
Boundary for River Rch & Prof#=UNT 005 IN RACR,Reach-1         , 6
Up Type= 0
Dn Type= 3
Dn Slope=0.005
Boundary for River Rch & Prof#=UNT 005 IN RACR,Reach-1         , 7
Up Type= 0
Dn Type= 3
Dn Slope=0.005
DSS Import GetInterval= 0
DSS Import GetPeak= 0
DSS Import FillOption= 0

--- UNT 005 IN RACR.g01 (geometry) ---

Geom Title=Existing Conditions
Program Version=4.10

River Reach=UNT 005 IN RACR ,Reach-1
Reach XY= 30
      2201763.73     13236766.09       2202804.3     13236237.26
      2203467.67     13235724.21      2203904.86      13235845.7
      2203915.28     13236322.09      2204122.84     13236504.08
      2204281.94     13236927.65      2204548.45     13237105.05
      2205219.72     13237244.45      2205884.43      13237742.7
      2206570.61      13237821.2      2207139.24      13238183.2
       2207992.6      13238246.5      2209234.57     13237661.84
      2210406.23     13237424.11       2210624.5     13237225.52
      2210870.06      13236598.3      2211033.63      13236575.5
      2211108.12     13236186.91      2211897.86     13235836.32
       2211890.7     13235508.01      2212214.82     13235241.08
      2212578.63     13235444.32      2213003.18     13235297.66
      2213581.94     13235348.69      2214315.24     13235831.27
      2214774.74     13235917.61      2214949.91     13235442.19
      2215180.64     13235423.96      2215372.23     13235230.33

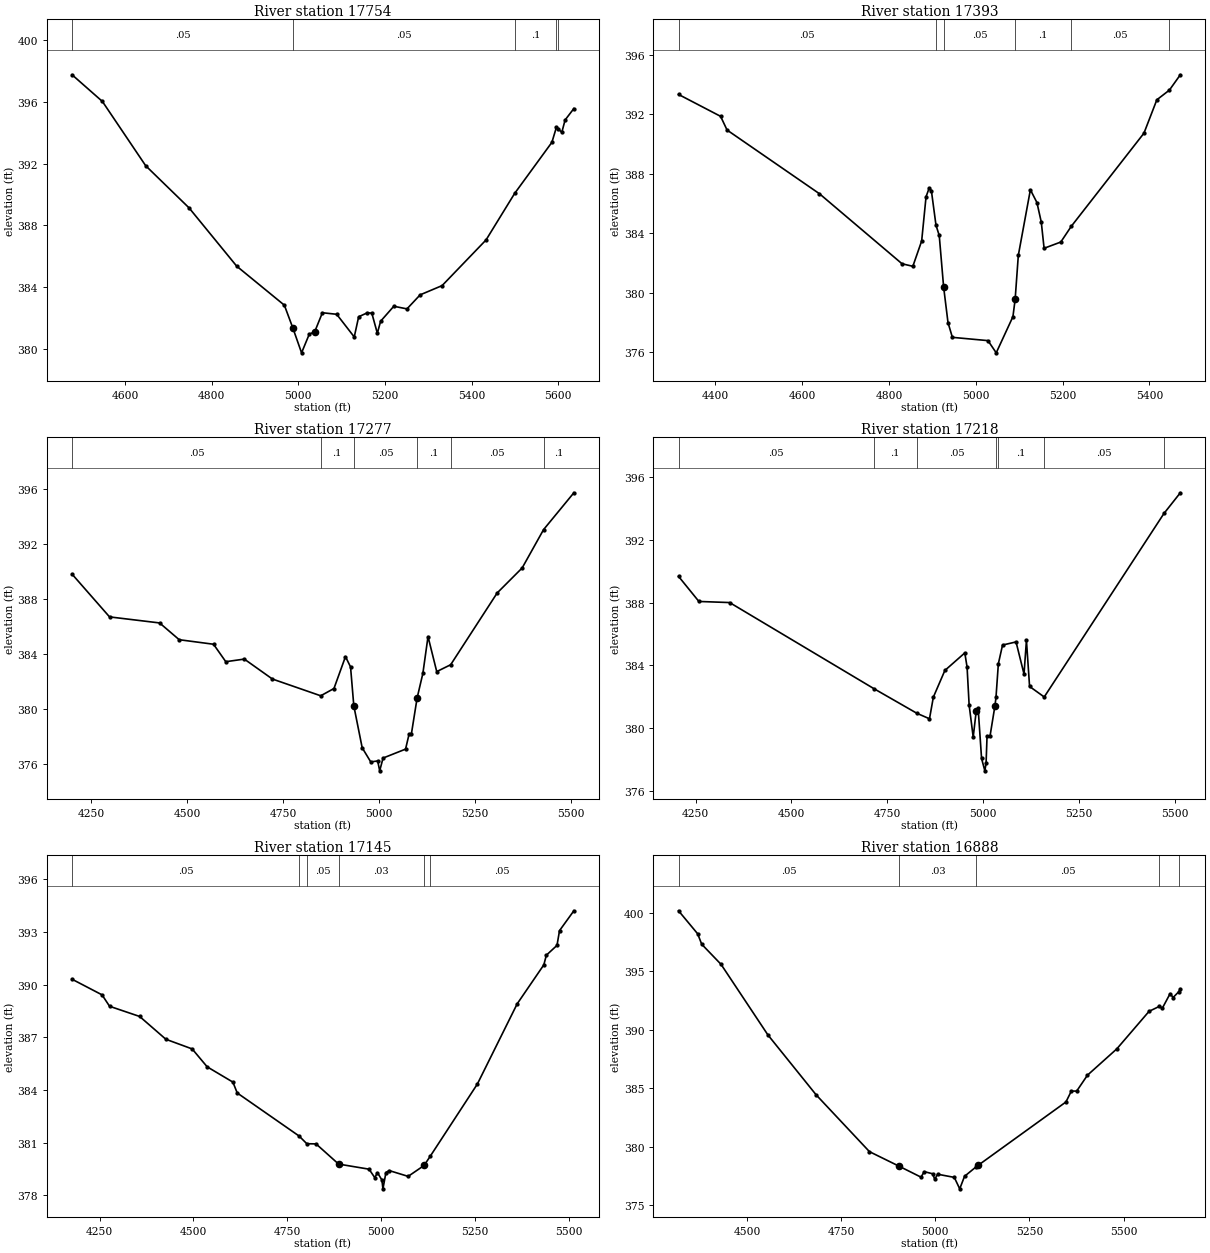
Type RM Length L Ch R = 1 ,17754   ,361,361,361
BEGIN DESCRIPTION:
UNT 005 IN RACR 36.0
END DESCRIPTION:
XS GIS Cut Line= 3
      2201887.72     13237196.81      2201887.72     13236646.85
      2201987.71     13236046.89
#Sta/Elev= 30
    4478  397.76    4548  396.03    4648  391.86    4748  389.13    4858  385.35
    4968  382.82    4988  381.31  5007.7  379.73  5025.5  380.94  5038.1   381.1
  5055.8  382.33  5088.8  382.23  5129.3  380.76  5139.5  382.07  5159.8  382.33
  5169.9   382.3  5182.6     381  5190.2  381.78  5220.6  382.75    5251  382.58
  5281.4  383.49  5332.1  384.09  5433.5  387.05  5499.6  390.07  5585.5  393.38
    5596  394.36  5599.2  394.27  5608.4  394.03    5616  394.83  5636.2  395.57
#Mann= 5 ,-1 , 0
    4478     .05       0    4988     .05       0  5499.6      .1       0
    5596     .05       0  5599.2      .1       0
Bank Sta=4988,5038.1
XS Rating Curve= 0 ,0
Exp/Cntr=0.3,0.1

Type RM Length L Ch R = 1 ,17393   ,116,116,116
BEGIN DESCRIPTION:
Mapping XS 3e9bf1e3
END DESCRIPTION:
XS GIS Cut Line= 4
      2202056.54     13237148.42      2202223.39     13236665.44
      2202176.56      13236366.9      2202018.49     13236062.47
#Sta/Elev= 30
  4315.2  393.32  4412.1  391.85    4427  390.93    4640  386.65  4830.2  381.95
  4855.1  381.78  4875.4  383.48  4885.5  386.45  4892.8  387.04  4897.8  386.86
  4908.4  384.54  4915.9  383.85    4926  380.39  4936.1     378  4946.2  377.01
  5028.2  376.79  5047.2  375.97  5085.7   378.4  5090.8  379.56  5098.1  382.51
  5125.9  386.92    5141  386.06    5151  384.75  5157.5  382.99    5196  383.41
    5220  384.46  5387.6  390.72  5417.3  392.96  5446.2  393.61  5471.4  394.64
#Mann= 6 ,-1 , 0
  4315.2     .05       0  4908.4     .07       0    4926     .05       0
  5090.8      .1       0    5220     .05       0  5446.2      .1       0
Bank Sta=4926,5090.8
XS Rating Curve= 0 ,0
Exp/Cntr=0.3,0.1

Type RM Length L Ch R = 1 ,17277   ,59,59,59
BEGIN DESCRIPTION:
Mapping XS 2a5477c3
END DESCRIPTION:
XS GIS Cut Line= 4
      2202405.21      13237234.1      2202349.65       13236557.
      2202287.15     13236411.17      2202027.76     13236020.35
#Sta/Elev= 30
  4200.7  389.79  4298.3  386.68  4428.7  386.24  4479.8  385.02  4569.2  384.69
  4601.1  383.42  4649.4  383.61  4722.5  382.16  4848.4  380.94  4882.9  381.47
  4912.9  383.79  4926.1  383.04  4934.6  380.21  4956.4  377.16  4978.7  376.13
  4996.8   376.2    5002  375.48  5010.8  376.41  5069.4  377.06  5078.4  378.13
  5084.4  378.13  5099.5  380.78  5114.5  382.57  5127.9  385.25  5150.6   382.7
  5186.9   383.2    5308  388.42  5373.1  390.24  5428.9  393.03  5507.8  395.71
#Mann= 6 ,-1 , 0
  4200.7     .05       0  4848.4      .1       0  4934.6     .05       0
  5099.5      .1       0  5186.9     .05       0  5428.9      .1       0
Bank Sta=4934.6,5099.5
XS Rating Curve= 0 ,0
Exp/Cntr=0.3,0.1

Type RM Length L Ch R = 1 ,17218   ,73,73,73
BEGIN DESCRIPTION:
Mapping XS 2e1fc7ad
END DESCRIPTION:
XS GIS Cut Line= 4
      2202432.99     13237209.82      2202384.37     13236487.56
      2202332.29      13236369.5      2202054.53     13236008.41
#Sta/Elev= 30
  4205.6  389.68  4258.7  388.08  4338.9  388.01  4714.4  382.53  4827.1  380.95
    4860   380.6  4870.1  381.98  4900.1  383.68  4952.1   384.8    4958   383.9
  4963.4  381.47    4974  379.43    4982  381.12  4986.8  381.29  4995.8  378.07
  5004.4  377.28  5007.6  377.78  5010.1   379.5  5017.7  379.47  5030.7  381.43
  5033.4  381.96  5039.6  384.11  5050.5   385.3  5085.7   385.5  5106.5  383.45
  5112.8   385.6    5121  382.66  5159.2  381.99  5471.4  393.69  5514.1  395.01
#Mann= 7 ,-1 , 0
  4205.6     .05       0  4714.4      .1       0  4827.1     .05       0
  5033.4     .07       0  5039.6      .1       0  5159.2     .05       0
  5471.4      .1       0
Bank Sta=4982,5030.7
XS Rating Curve= 0 ,0
Exp/Cntr=0.3,0.1

Type RM Length L Ch R = 1 ,17145   ,257,257,257
BEGIN DESCRIPTION:
UNT 005 IN RACR 35.0
END DESCRIPTION:
XS GIS Cut Line= 4
      2202464.24     13237216.76       2202443.4     13236435.48
      2202394.79     13236341.73      2202092.72     13236008.41
#Sta/Elev= 30
  4176.6  390.31  4256.5  389.42  4276.5  388.77  4356.6  388.19  4426.6  386.89
  4496.6  386.34  4536.6  385.32  4605.1  384.45  4616.7  383.83  4781.4  381.38
  4802.1  380.94  4826.7  380.93  4886.8  379.78  4967.9  379.49  4983.1  379.01
  4990.4  379.29  5002.2  378.87  5004.9  378.37  5012.9   379.3  5021.7  379.41
    5072  379.08  5114.5   379.7  5130.7  380.22  5256.5  384.34  5362.6  388.91
  5433.6  391.13  5440.3  391.68  5468.7  392.24  5475.4  393.08  5513.6  394.21
#Mann= 6 ,-1 , 0
  4176.6     .05       0  4781.4      .1       0  4802.1     .05       0
  4886.8     .03       0  5114.5      .1       0  5130.7     .05       0
Bank Sta=4886.8,5114.5
XS Rating Curve= 0 ,0
Exp/Cntr=0.3,0.1

Type RM Length L Ch R = 1 ,16888   ,359,359,359
BEGIN DESCRIPTION:
UNT 005 IN RACR 34.0
END DESCRIPTION:
XS GIS Cut Line= 4
       2202865.2      13236916.8      2202764.13     13236478.83
      2202460.91     13235993.68      2202225.23     13235791.67
#Sta/Elev= 30
  4318.5  400.18  4369.3  398.21    4380  397.32  4431.3   395.6  4555.8  389.56
    4684  384.43  4825.3  379.58  4904.3  378.33  4962.1   377.4  4970.8  377.87
  4992.8  377.69  4998.7  377.22  5006.2  377.65  5050.5  377.38  5064.9   376.4
  5077.7  377.47  5108.3  378.28  5114.2  378.42  5346.9  383.83  5361.2  384.76
  5375.4  384.76    5404  386.12  5481.9  388.37  5567.5  391.58  5595.2  392.01
  5602.6  391.84  5623.5   393.1  5631.2  392.76  5646.2  393.25  5650.5   393.5
#Mann= 5 ,-1 , 0
  4318.5     .05       0  4904.3     .03       0  5108.3     .05       0
  5595.2      .1       0  5646.2     .05       0
Bank Sta=4904.3,5114.2
XS Rating Curve= 0 ,0
Exp/Cntr=0.3,0.1

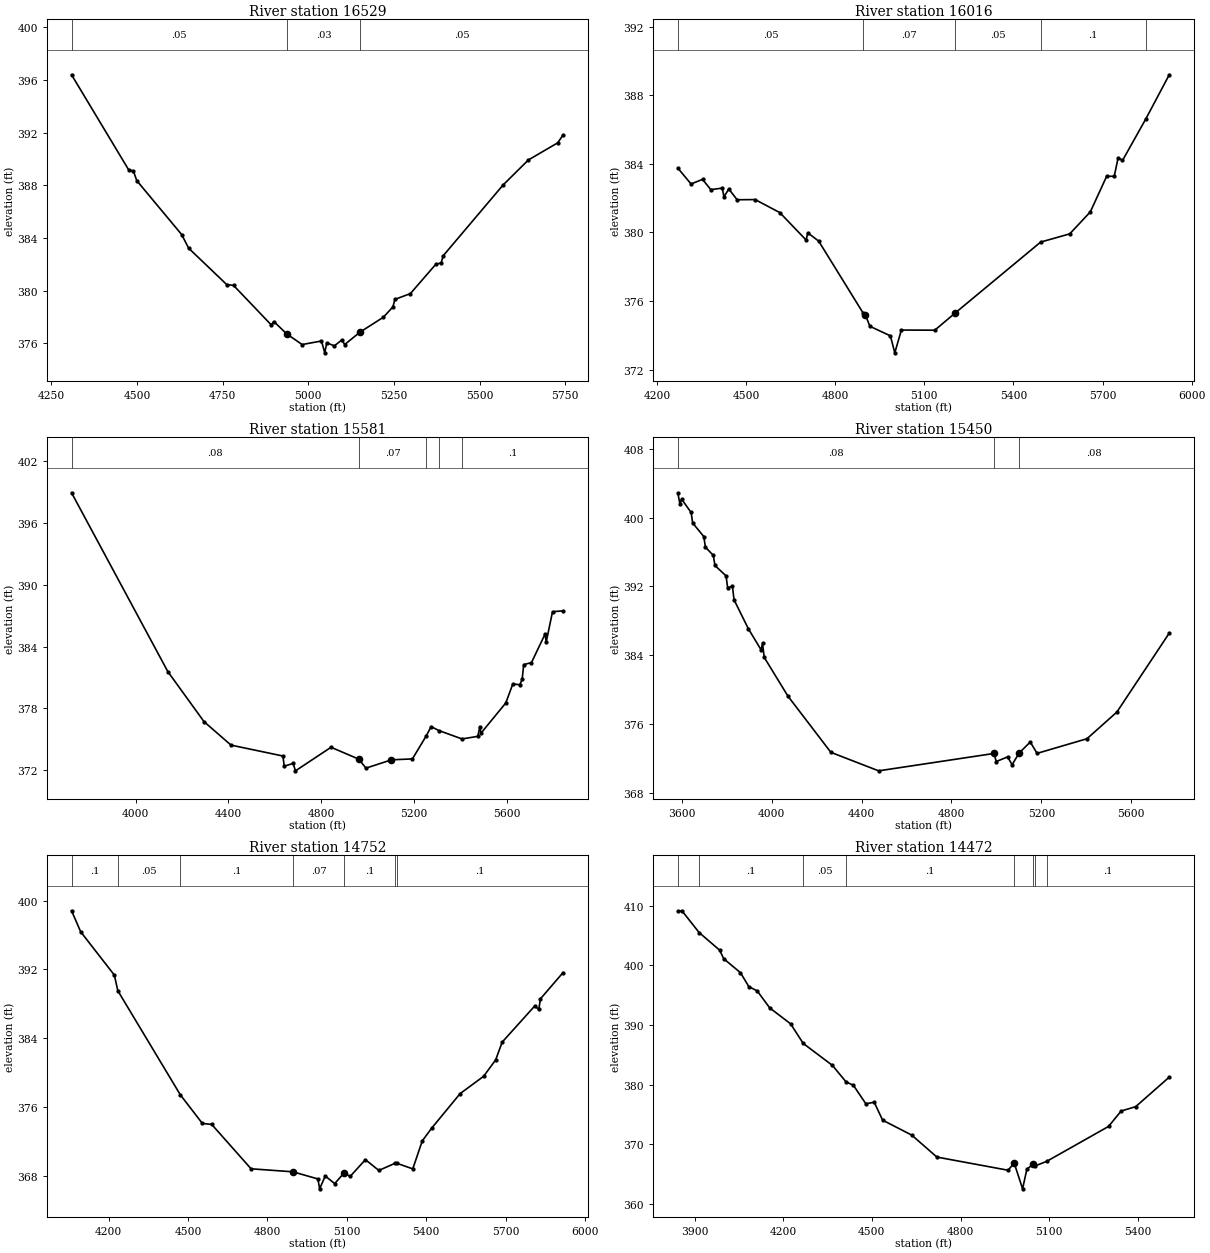
Type RM Length L Ch R = 1 ,16529   ,513,513,513
BEGIN DESCRIPTION:
UNT 005 IN RACR 33.0
END DESCRIPTION:
XS GIS Cut Line= 4
      2202979.75     13236795.47      2203047.13     13236303.64
       2202811.3     13235852.18       2202443.4     13235631.45
#Sta/Elev= 30
  4308.6   396.4  4475.8  389.16  4488.9   389.1    4499  388.36  4630.2  384.26
  4650.4  383.23  4761.4  380.47  4781.6   380.4  4891.7   377.4  4899.1  377.66
  4936.8  376.72  4981.8  375.91  5038.3  376.18  5047.8  375.28  5053.7  376.04
  5075.8  375.81  5097.8  376.26    5106  375.91  5151.1  376.86  5218.8  377.98
  5246.8  378.77  5252.7  379.34  5297.8  379.78  5372.2  382.01  5387.7  382.11
  5393.5  382.65  5568.5  388.03  5642.3  389.93  5727.9  391.23  5743.4  391.82
#Mann= 3 , 0 , 0
  4308.6     .05       0  4936.8     .03       0  5151.1     .05       0
Bank Sta=4936.8,5151.1
XS Rating Curve= 0 ,0
Exp/Cntr=0.3,0.1

Type RM Length L Ch R = 1 ,16016   ,435,435,435
BEGIN DESCRIPTION:
UNT 005 IN RACR 32.0
END DESCRIPTION:
XS GIS Cut Line= 4
      2203242.52     13236472.11      2203451.41      13236067.8
      2203040.39      13235164.9      2202919.12     13234996.46
#Sta/Elev= 30
  4269.8  383.76  4314.5  382.83  4353.1   383.1  4380.9   382.5  4419.6  382.59
  4425.2  382.08  4441.7  382.54  4469.5  381.91  4530.3  381.92  4613.3  381.16
  4701.9  379.56  4707.5  379.98  4744.1   379.5  4893.5  375.31  4901.7  375.19
  4916.5  374.53  4985.7  373.97  5000.4  372.98  5022.6  374.31    5135   374.3
  5204.2  375.31  5491.5  379.44  5589.5  379.92  5658.7   381.2  5714.1  383.29
  5739.2  383.27  5752.4  384.36  5767.1   384.2  5845.5  386.62  5924.5   389.2
#Mann= 5 ,-1 , 0
  4269.8     .05       0  4893.5     .07       0  5204.2     .05       0
  5491.5      .1       0  5845.5     .05       0
Bank Sta=4901.7,5204.2
XS Rating Curve= 0 ,0
Exp/Cntr=0.3,0.1

Type RM Length L Ch R = 1 ,15581   ,131,131,131
BEGIN DESCRIPTION:
Mapping XS a043ac0d
END DESCRIPTION:
XS GIS Cut Line= 5
       2203115.3     13236938.92      2203501.56     13236483.22
      2203675.17     13236162.04      2203696.87     13235697.63
      2203770.66     13235011.88
#Sta/Elev= 30
  3724.2  398.95  4138.8  381.58  4294.8  376.71  4411.1  374.43  4634.8  373.37
  4640.4  372.38  4678.5  372.65  4688.9  371.93    4842  374.22  4962.2  373.06
  4992.2  372.19  5102.3     373  5192.6  373.09    5253  375.36  5273.1  376.23
  5307.1  375.84  5406.1  375.03  5474.2  375.28    5483  376.22    5488  375.59
  5594.9  378.53  5625.1  380.37  5655.3   380.3  5665.3  380.81    5672  382.25
  5705.5  382.45    5764  385.22    5769  384.45  5796.1  387.39  5841.3  387.48
#Mann= 5 ,-1 , 0
  3724.2     .08       0  4962.2     .07       0    5253     .08       0
  5307.1     .05       0  5406.1      .1       0
Bank Sta=4962.2,5102.3
XS Rating Curve= 0 ,0
Exp/Cntr=0.3,0.1

Type RM Length L Ch R = 1 ,15450   ,698,698,698
BEGIN DESCRIPTION:
Mapping XS 2bee923e
END DESCRIPTION:
XS GIS Cut Line= 4
      2203123.99     13237017.04      2203614.41     13236509.26
       2203753.3      13236157.7      2203905.21     13235063.95
#Sta/Elev= 30
  3581.3  402.88  3591.2  401.53  3598.1  402.15  3640.6  400.59  3647.8  399.36
  3697.2  397.79  3704.4  396.56  3739.6   395.6  3746.8  394.43  3796.2  393.22
  3803.4  391.82  3824.5  392.04  3831.7  390.45  3895.3  387.09  3951.9  384.64
  3958.8  385.38    3966  383.76    4072  379.24  4262.9  372.72  4475.6  370.57
  4989.2  372.59  4999.3  371.65  5049.7  372.19  5069.9  371.28  5101.2  372.64
  5150.7  373.92    5181   372.6  5403.1   374.3  5536.4   377.4  5769.5  386.57
#Mann= 3 , 0 , 0
  3581.3     .08       0  4989.2     .07       0  5101.2     .08       0
Bank Sta=4989.2,5101.2
XS Rating Curve= 0 ,0
Exp/Cntr=0.3,0.1

Type RM Length L Ch R = 1 ,14752   ,280,280,280
BEGIN DESCRIPTION:
UNT 005 IN RACR 31.0
END DESCRIPTION:
XS GIS Cut Line= 4
      2203363.82     13237091.99       2203801.8     13236627.06
      2204307.15     13235899.35      2204617.06     13235778.08
#Sta/Elev= 30
  4059.5  398.82    4094  396.38  4221.4  391.34  4234.3  389.53  4470.4  377.44
    4554   374.1  4589.2  373.99    4738  368.83    4896  368.48  4990.7  367.65
  4997.1   366.5  5018.3  367.99  5054.1  367.11  5089.9  368.36  5112.4  367.94
  5170.2  369.89  5220.9  368.64  5283.7  369.49  5288.1  369.48  5349.2  368.82
    5385  372.07  5420.8  373.56  5528.2  377.57    5617  379.58  5662.5  381.49
    5687  383.55  5810.3  387.76  5825.4  387.35  5831.8  388.59    5917  391.63
#Mann= 7 ,-1 , 0
  4059.5      .1       0  4234.3     .05       0  4470.4      .1       0
    4896     .07       0  5089.9      .1       0  5283.7     .08       0
  5288.1      .1       0
Bank Sta=4896,5089.9
XS Rating Curve= 0 ,0
Exp/Cntr=0.3,0.1

Type RM Length L Ch R = 1 ,14472   ,197,197,197
BEGIN DESCRIPTION:
UNT 005 IN RACR 30.0
END DESCRIPTION:
XS GIS Cut Line= 3
      2203337.73     13237396.85      2204137.72     13236596.85
      2204537.75     13236246.83
#Sta/Elev= 30
  3843.4  409.09  3857.5  409.15  3915.5  405.51  3984.8  402.56    3999  401.11
  4055.5  398.78  4083.8  396.44  4112.1  395.73  4154.5  392.88  4225.2  390.21
  4267.8  386.93  4366.6  383.25    4413  380.47  4437.4  379.93  4479.8  376.82
  4508.1  377.08  4536.4  374.08  4635.3  371.56  4720.2  367.89  4960.6  365.69
  4981.9  366.86  5010.1  362.57  5024.6  365.88  5045.5  366.66  5052.6  366.41
  5091.9  367.18  5300.8  373.02  5343.5   375.6  5392.8  376.34  5506.3  381.28
#Mann= 8 ,-1 , 0
  3843.4     .08       0  3915.5      .1       0  4267.8     .05       0
    4413      .1       0  4981.9     .07       0  5045.5      .1       0
  5052.6     .08       0  5091.9      .1       0
Bank Sta=4981.9,5045.5
XS Rating Curve= 0 ,0
Exp/Cntr=0.3,0.1

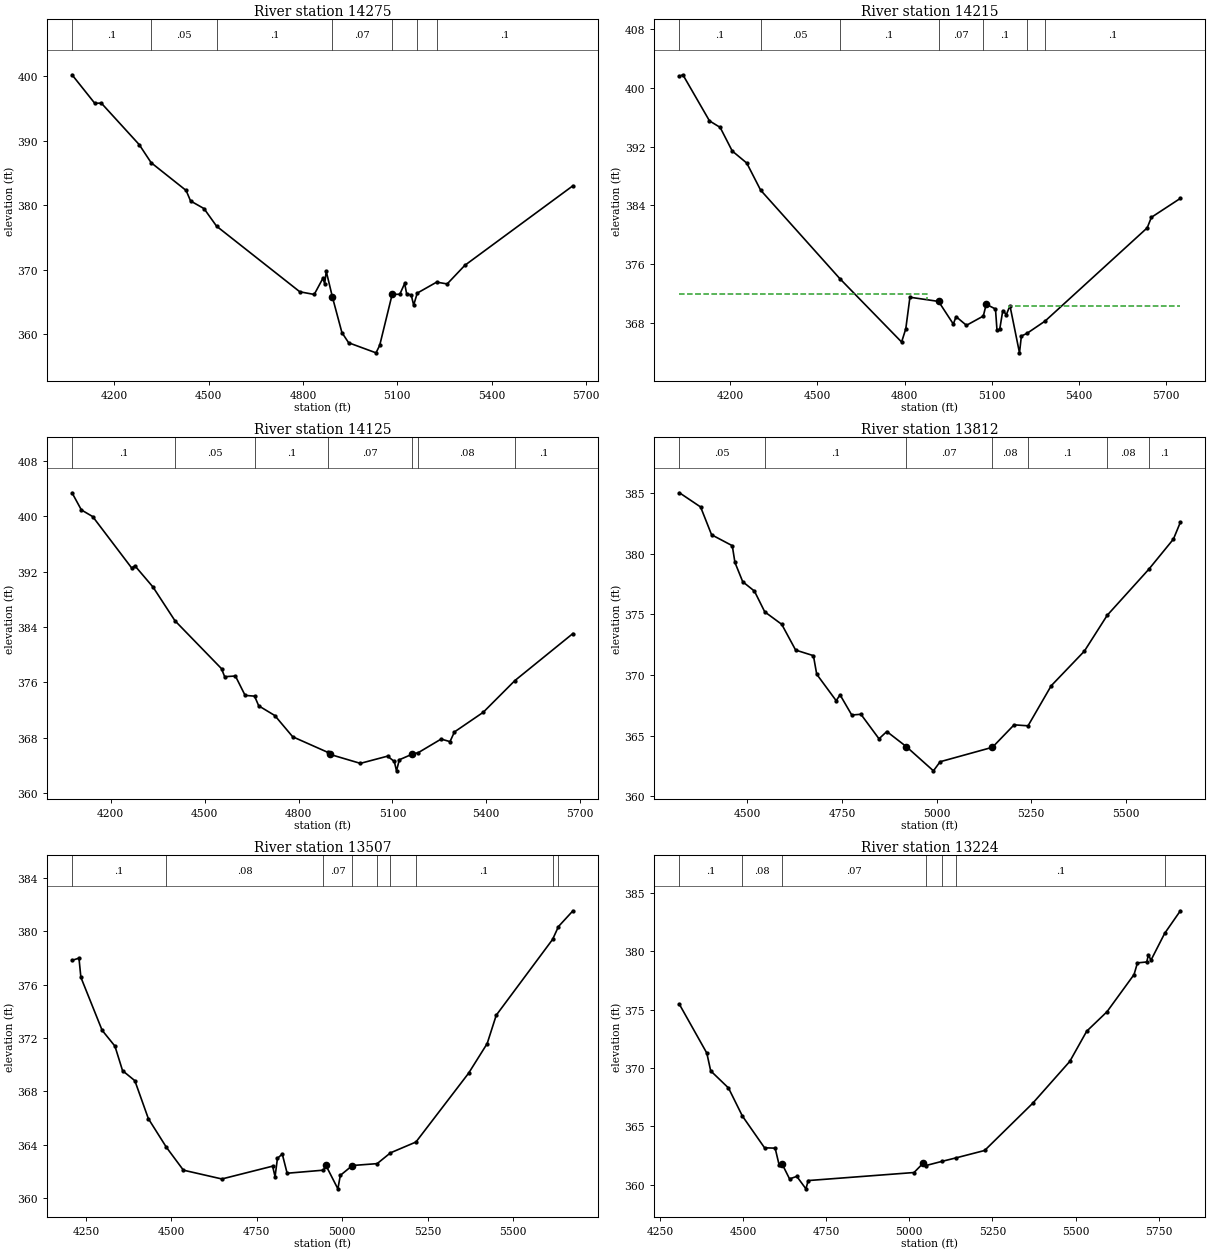
Type RM Length L Ch R = 1 ,14275   ,60,60,60
BEGIN DESCRIPTION:
Mapping XS 0b3c79e9
END DESCRIPTION:
XS GIS Cut Line= 6
      2203472.03     13237282.71      2204048.44     13236775.75
      2204149.13     13236793.12      2204242.88     13236751.45
      2204232.46       13236682.      2204652.59     13236327.85
#Sta/Elev= 30
    4066  400.23  4138.3  395.81  4159.1  395.84  4279.6   389.4  4317.5   386.6
  4428.6   382.3  4442.8  380.67  4485.5  379.49  4525.5  376.76  4790.1  366.59
  4835.8  366.18  4863.3  368.68    4869  367.86    4874  369.77  4893.8  365.74
  4923.8  360.27  4945.2  358.69  5032.1  357.13  5043.8  358.27  5083.5  366.19
  5107.8  366.21  5123.2  367.88  5129.7  366.25    5144  366.11  5151.8  364.53
  5163.3  366.39  5224.9  368.09  5258.4  367.81  5314.4  370.69  5658.1  383.03
#Mann= 7 ,-1 , 0
    4066      .1       0  4317.5     .05       0  4525.5      .1       0
  4893.8     .07       0  5083.5      .1       0  5163.3     .08       0
  5224.9      .1       0
Bank Sta=4893.8,5083.5
XS Rating Curve= 0 ,0
Exp/Cntr=0.3,0.1

Type RM Length L Ch R = 1 ,14215   ,90,90,90
BEGIN DESCRIPTION:
Mapping XS eca22372
END DESCRIPTION:
XS GIS Cut Line= 6
      2203468.56     13237313.96      2204083.16     13236810.48
      2204138.71      13236869.5      2204308.85     13236779.23
      2204288.02     13236713.25       2204735.9     13236334.81
#Sta/Elev= 30
  4025.2  401.56    4037  401.76  4128.6  395.49  4165.2  394.61  4206.8   391.4
  4256.8  389.76  4304.5  386.08  4577.5  374.03  4789.6  365.43    4804  367.22
  4818.3  371.52  4916.8  370.95  4967.6  367.87  4977.1  368.88  5012.8   367.7
  5070.8  368.96  5080.8  370.56  5112.7  369.92  5117.9  367.03  5127.3  367.17
  5137.8   369.7  5150.2  369.16  5162.5  370.37  5195.3  363.96  5201.8  366.24
  5221.2  366.61  5283.5  368.28  5634.8  380.95  5649.1  382.38  5748.9  384.96
#Mann= 7 ,-1 , 0
  4025.2      .1       0  4304.5     .05       0  4577.5      .1       0
  4916.8     .07       0  5070.8      .1       0  5221.2     .08       0
  5283.5      .1       0
#XS Ineff= 2 , 0
         4875.89  371.94 5158.75          370.34
Permanent Ineff=
       F       F
Bank Sta=4916.8,5080.8
XS Rating Curve= 0 ,0
Exp/Cntr=0.3,0.1

Type RM Length L Ch R = 1 ,14125   ,313,313,313
BEGIN DESCRIPTION:
Mapping XS a417ee6c
END DESCRIPTION:
XS GIS Cut Line= 3
      2203461.61     13237352.16       2204378.3     13236841.73
      2204773.42       13236457.
#Sta/Elev= 30
  4076.2   403.4  4106.1  400.92  4142.3  399.96  4266.9  392.53  4277.2  392.85
    4335  389.78  4405.2  384.91  4553.9  377.99  4563.9  376.83  4598.3  376.93
  4629.3  374.13  4659.5  374.02  4672.8  372.62  4724.2  371.22  4781.4  368.15
  4894.6  365.88  4900.3  365.61  4997.5  364.31  5084.4  365.35  5106.1  364.58
  5113.1  363.23  5122.1  364.83  5163.9  365.65  5182.8  365.86  5255.7  367.82
    5284  367.45  5298.2  368.85    5390  371.68  5491.4  376.27  5676.9  383.07
#Mann= 7 ,-1 , 0
  4076.2      .1       0  4405.2     .05       0  4659.5      .1       0
  4894.6     .07       0  5163.9      .1       0  5182.8     .08       0
  5491.4      .1       0
Bank Sta=4900.3,5163.9
XS Rating Curve= 0 ,0
Exp/Cntr=0.3,0.1

Type RM Length L Ch R = 1 ,13812   ,305,305,305
BEGIN DESCRIPTION:
Mapping XS 0c29d7e5
END DESCRIPTION:
XS GIS Cut Line= 3
      2204350.37     13237739.37      2204541.35     13236949.41
      2204783.56     13236499.59
#Sta/Elev= 30
  4320.6  385.02  4376.5  383.85  4405.5  381.56  4460.2  380.66  4467.2  379.28
  4487.8  377.69  4518.7  376.92    4546  375.21  4590.9  374.18  4627.6  372.06
  4674.6   371.6  4683.3  370.07  4734.7  367.89    4745  368.37  4775.9  366.71
  4800.1  366.77  4847.9  364.75  4868.5  365.35  4919.9  364.11  4991.7  362.11
  5009.4  362.86  5147.6  364.05  5204.8   365.9  5241.7  365.82  5302.9  369.12
  5390.5  371.97    5451  374.93  5560.6  378.71  5625.8   381.2  5644.2  382.59
#Mann= 7 ,-1 , 0
  4320.6     .05       0    4546      .1       0  4919.9     .07       0
  5147.6     .08       0  5241.7      .1       0    5451     .08       0
  5560.6      .1       0
Bank Sta=4919.9,5147.6
XS Rating Curve= 0 ,0
Exp/Cntr=0.3,0.1

Type RM Length L Ch R = 1 ,13507   ,283,283,283
BEGIN DESCRIPTION:
Mapping XS f0cd0fcc
END DESCRIPTION:
XS GIS Cut Line= 4
      2204953.67     13237769.74      2205105.59     13237457.22
      2204688.92     13237023.19      2204819.13     13236524.04
#Sta/Elev= 30
  4209.5  377.83  4229.8     378  4235.4  376.56  4297.5  372.59    4335   371.4
  4357.3  369.56  4393.2  368.81  4432.8  365.96  4485.4  363.82  4535.2   362.1
  4647.7  361.44  4796.1   362.4  4803.3  361.61  4810.3  362.99  4824.4  363.31
  4838.6  361.87  4944.9   362.1  4951.8  362.47    4987   360.7  4994.2  361.71
  5029.5  362.45  5101.9  362.59  5140.9   363.4  5215.3  364.21  5369.3  369.37
  5423.6  371.59  5450.2  373.72  5614.9   379.4  5632.2  380.37  5674.5  381.55
#Mann= 9 ,-1 , 0
  4209.5      .1       0  4485.4     .08       0  4944.9     .07       0
  5029.5     .08       0  5101.9      .1       0  5140.9     .08       0
  5215.3      .1       0  5614.9     .08       0  5632.2      .1       0
Bank Sta=4951.8,5029.5
XS Rating Curve= 0 ,0
Exp/Cntr=0.3,0.1

Type RM Length L Ch R = 1 ,13224   ,460,460,460
BEGIN DESCRIPTION:
Mapping XS 47368637
END DESCRIPTION:
XS GIS Cut Line= 4
      2205079.57     13237808.75      2205261.84     13237483.26
      2204892.91     13237070.94      2205001.06     13236499.91
#Sta/Elev= 30
  4308.1  375.46  4390.5  371.28  4402.1  369.76  4455.7  368.29  4497.4  365.89
  4564.2  363.16  4596.1  363.13  4608.3  361.66  4617.8  361.73  4639.5  360.49
  4661.2  360.71  4688.7  359.64  4695.6  360.35  5014.1  361.04  5042.5  361.87
    5050  361.64  5098.6     362  5141.1   362.3  5226.5  362.93  5370.9  366.97
  5482.8  370.57  5533.7  373.16  5594.8  374.83  5676.2  378.02  5686.4  379.02
  5714.4   379.1  5719.5  379.72  5727.1  379.25  5768.3  381.55  5815.6  383.49
#Mann= 7 ,-1 , 0
  4308.1      .1       0  4497.4     .08       0  4617.8     .07       0
    5050      .1       0  5098.6     .08       0  5141.1      .1       0
  5768.3     .08       0
Bank Sta=4617.8,5042.5
XS Rating Curve= 0 ,0
Exp/Cntr=0.3,0.1

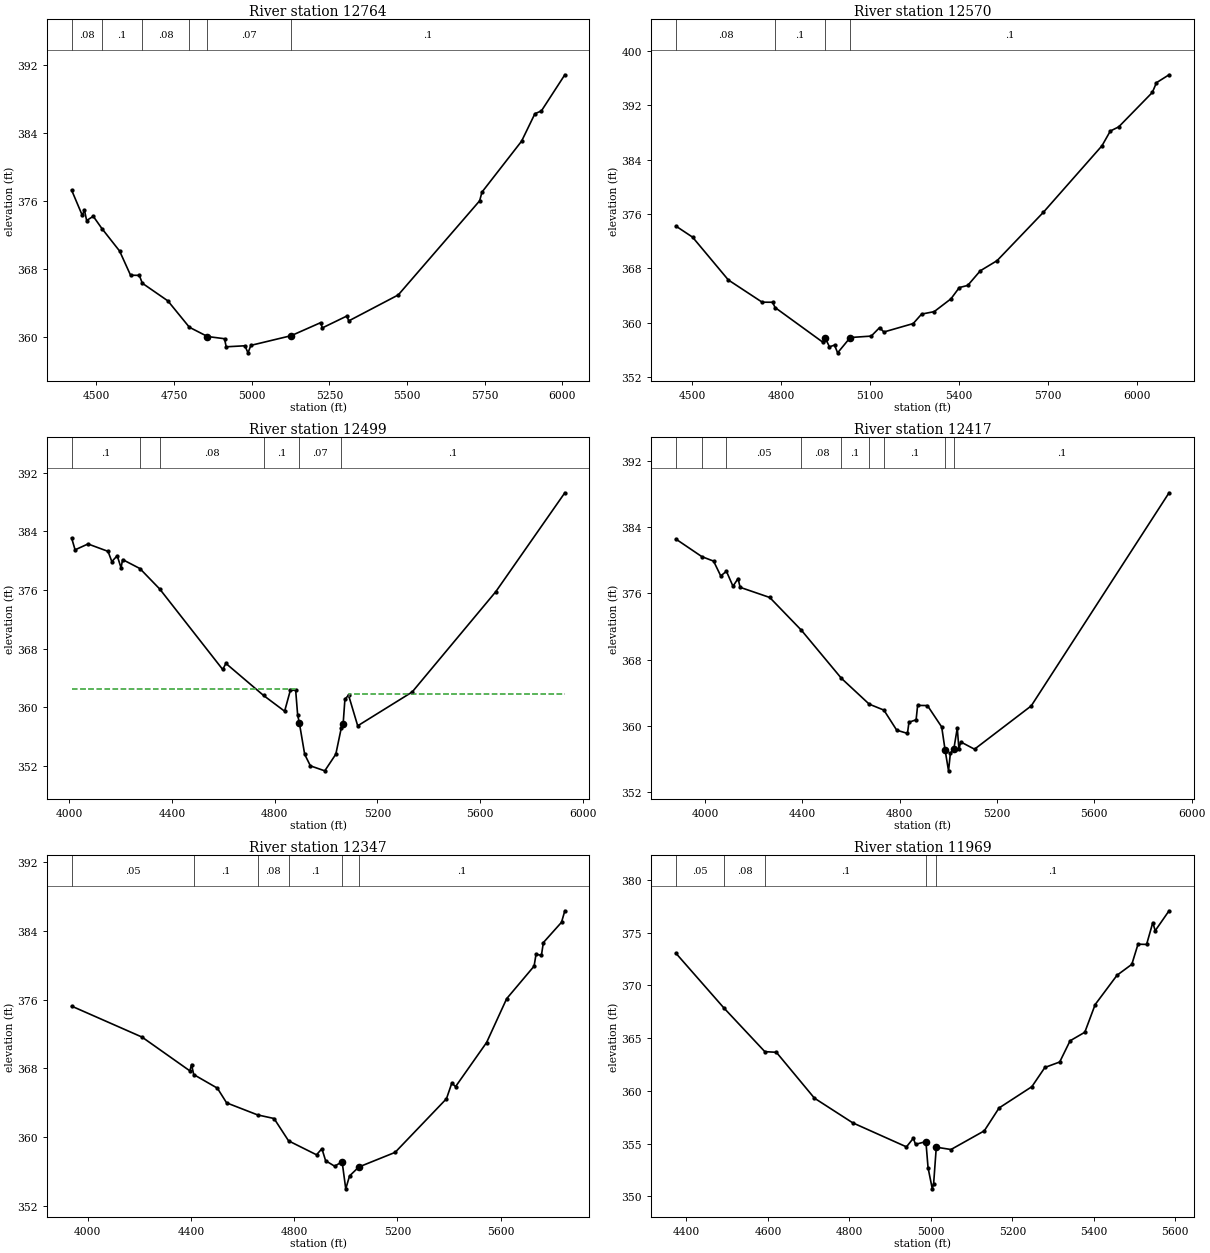
Type RM Length L Ch R = 1 ,12764   ,194,194,194
BEGIN DESCRIPTION:
Mapping XS ba60787c
END DESCRIPTION:
XS GIS Cut Line= 4
      2205070.83     13237878.26      2205326.94     13237613.47
      2205522.25     13237101.32      2206038.62     13236671.74
#Sta/Elev= 30
  4420.2  377.32  4454.3  374.37  4461.5  374.96  4468.5  373.75  4489.8  374.25
  4517.8   372.8  4574.7  370.16  4609.9  367.32  4638.2   367.3  4647.7  366.38
  4730.1   364.3  4799.3   361.2  4857.7  360.11  4912.5  359.85  4917.9   358.9
  4978.1  359.02  4988.1  358.19  4997.5  359.07  5127.4  360.21  5222.1  361.74
  5227.4  361.12    5307  362.53  5312.3  361.94    5472     365  5734.1  376.07
  5741.5  377.09  5869.1  383.08    5912  386.31  5932.9  386.64  6008.4  390.89
#Mann= 6 ,-1 , 0
  4420.2     .08       0  4517.8      .1       0  4647.7     .08       0
  4799.3      .1       0  4857.7     .07       0  5127.4      .1       0
Bank Sta=4857.7,5127.4
XS Rating Curve= 0 ,0
Exp/Cntr=0.3,0.1

Type RM Length L Ch R = 1 ,12570   ,71,71,71
BEGIN DESCRIPTION:
UNT 005 IN RACR 26.0
END DESCRIPTION:
XS GIS Cut Line= 3
      2205137.75     13237896.83      2205537.72     13237546.85
      2206337.69     13236746.88
#Sta/Elev= 30
  4445.1  374.23  4501.5   372.6  4622.1  366.31    4736  363.05  4771.1  363.04
  4779.7  362.26    4941  357.16  4948.6   357.8  4962.8   356.5  4980.1  356.74
  4990.5  355.61  5033.1  357.86  5103.8  358.07  5132.1  359.32  5146.3  358.67
  5245.3  359.91  5273.6   361.3    5316  361.66  5372.5  363.54  5400.8   365.2
  5429.1  365.51  5471.5  367.66  5528.1  369.15  5683.7  376.23  5881.7  386.02
  5909.9  388.19  5938.2   388.8  6051.4  393.85  6065.5  395.29  6107.9  396.45
#Mann= 4 ,-1 , 0
  4445.1     .08       0  4779.7      .1       0  4948.6     .07       0
  5033.1      .1       0
Bank Sta=4948.6,5033.1
XS Rating Curve= 0 ,0
Exp/Cntr=0.3,0.1

Type RM Length L Ch R = 1 ,12499   ,82,82,82
BEGIN DESCRIPTION:
Mapping XS 2cffae9f
END DESCRIPTION:
XS GIS Cut Line= 4
       2204815.5     13238152.21      2205367.59     13237766.78
      2205645.37     13237537.62      2206252.82     13236891.98
#Sta/Elev= 30
  4009.6  383.11    4023   381.5  4073.3   382.3  4151.3  381.29  4166.1  379.89
    4187   380.7  4201.9  379.04    4208  380.17  4275.2  378.95  4352.4  376.16
  4597.7  365.18  4610.1  366.01  4756.7  361.64  4838.7  359.49  4860.8  362.32
  4881.6   362.4  4889.5  358.94    4896  357.91  4916.8  353.61    4939  352.04
    4995  351.36    5038  353.63  5059.2   357.2  5066.5  357.77  5073.4  361.11
  5087.5  361.69  5123.2   357.5  5335.2  362.11  5660.9   375.8  5929.5  389.28
#Mann= 6 ,-1 , 0
  4009.6      .1       0  4275.2     .05       0  4352.4     .08       0
  4756.7      .1       0    4896     .07       0  5059.2      .1       0
#XS Ineff= 2 , 0
         4878.57  362.46 5089.29           361.8
Permanent Ineff=
       F       F
Bank Sta=4896,5066.5
XS Rating Curve= 0 ,0
Exp/Cntr=0.3,0.1

Type RM Length L Ch R = 1 ,12417   ,70,70,70
BEGIN DESCRIPTION:
Mapping XS 36fc727f
END DESCRIPTION:
XS GIS Cut Line= 5
      2204763.43     13238259.84       2205579.4     13237673.03
      2205645.37     13237648.73      2205687.04     13237603.59
      2206293.23     13236952.36
#Sta/Elev= 30
  3880.6  382.58  3987.5  380.45  4035.6  379.91    4065  378.12  4088.4  378.68
  4115.3  376.87  4136.2   377.8  4144.6  376.74  4266.3  375.51  4396.6  371.54
  4560.7  365.73  4675.1   362.6  4735.4  361.88  4788.1  359.45  4832.2  359.06
  4838.4  360.41  4867.8  360.71    4874  362.45  4914.3  362.43  4972.9  359.84
    4987  357.03    5001  354.53  5008.6  356.66  5022.8  357.18  5036.9  359.71
  5043.8  357.14  5051.1  358.03  5107.8  357.15  5340.8  362.39  5907.1  388.18
#Mann= 9 ,-1 , 0
  3880.6     .05       0  3987.5      .1       0  4088.4     .05       0
  4396.6     .08       0  4560.7      .1       0  4675.1     .08       0
  4735.4      .1       0    4987     .07       0  5022.8      .1       0
Bank Sta=4987,5022.8
XS Rating Curve= 0 ,0
Exp/Cntr=0.3,0.1

Type RM Length L Ch R = 1 ,12347   ,378,378,378
BEGIN DESCRIPTION:
Mapping XS 87302696
END DESCRIPTION:
XS GIS Cut Line= 3
      2204909.27     13238322.33      2205773.84     13237620.95
      2206303.89     13237025.08
#Sta/Elev= 30
  3938.1  375.25  4210.8  371.65  4396.2  367.72  4402.6  368.46  4411.1  367.29
  4502.7  365.71  4538.5     364  4658.5   362.6  4722.3  362.18  4778.6  359.58
  4886.9  357.96  4907.7  358.67  4922.1  357.27  4957.3  356.63    4986  357.16
  5000.1     354  5014.8   355.5  5050.7  356.54  5191.3  358.24  5390.3  364.48
  5411.2  366.31  5425.4  365.88  5545.8  371.02  5623.6  376.12  5729.8   379.9
  5737.3  381.28  5758.2  381.16  5765.7  382.64    5836     385  5848.9  386.34
#Mann= 6 ,-1 , 0
  3938.1     .05       0  4411.1      .1       0  4658.5     .08       0
  4778.6      .1       0    4986     .07       0  5050.7      .1       0
Bank Sta=4986,5050.7
XS Rating Curve= 0 ,0
Exp/Cntr=0.3,0.1

Type RM Length L Ch R = 1 ,11969   ,288,288,288
BEGIN DESCRIPTION:
UNT 005 IN RACR 25.0
END DESCRIPTION:
XS GIS Cut Line= 4
       2205890.6     13238392.46      2205964.72      13238048.8
       2206207.3     13237368.26      2206281.42     13237253.69
#Sta/Elev= 30
  4374.1  373.06  4492.1  367.86  4592.5  363.72  4620.8  363.66  4714.2  359.31
  4808.2  356.97  4940.1  354.69    4957  355.51  4962.3  354.93  4987.8  355.19
  4993.1  352.71  5003.5  350.71  5006.8  351.21  5013.3  354.66  5049.4  354.44
  5131.1  356.21  5167.4  358.38  5247.9   360.4  5279.8  362.22  5316.2  362.74
  5341.7  364.75  5377.8  365.56  5403.3  368.19    5457  370.97  5493.2     372
  5508.4  373.91  5529.5  373.89  5544.7  375.96  5550.6  375.19  5584.6  377.08
#Mann= 5 ,-1 , 0
  4374.1     .05       0  4492.1     .08       0  4592.5      .1       0
  4987.8     .07       0  5013.3      .1       0
Bank Sta=4987.8,5013.3
XS Rating Curve= 0 ,0
Exp/Cntr=0.3,0.1

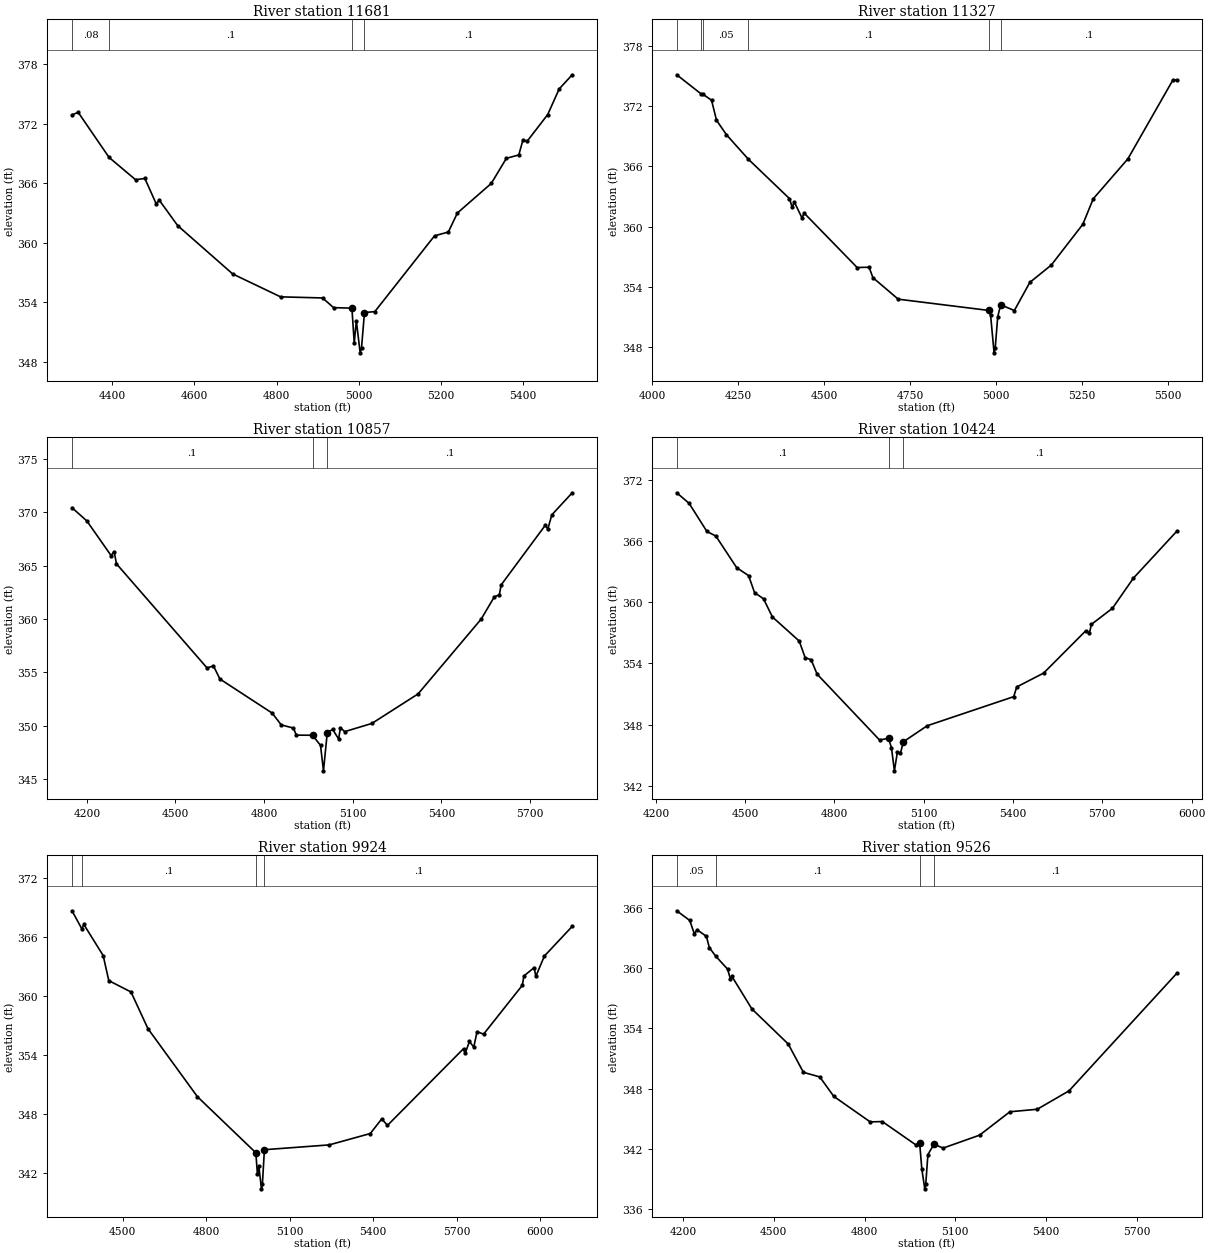
Type RM Length L Ch R = 1 ,11681   ,354,354,354
BEGIN DESCRIPTION:
UNT 005 IN RACR 24.0
END DESCRIPTION:
XS GIS Cut Line= 4
      2206079.25     13238459.86      2206267.94     13238143.14
      2206382.49     13237590.61      2206416.17     13237307.65
#Sta/Elev= 30
    4302  372.89  4317.1  373.15  4392.3   368.6  4456.8  366.35  4479.4  366.48
  4506.7  363.95    4515  364.26  4559.3  361.72  4693.3  356.84  4809.8  354.53
    4912  354.42    4939  353.44  4983.5  353.39  4989.2  349.88  4994.3  352.12
  5003.6  348.88  5006.9  349.38  5014.1  352.95  5039.3  353.04  5184.7  360.69
  5218.3  361.07  5240.3  362.99  5322.9  365.98  5359.6  368.51  5389.8  368.85
  5399.9  370.35  5410.5  370.25  5460.3  372.93  5488.1  375.51  5519.9  376.94
#Mann= 4 ,-1 , 0
    4302     .08       0  4392.3      .1       0  4983.5     .07       0
  5014.1      .1       0
Bank Sta=4983.5,5014.1
XS Rating Curve= 0 ,0
Exp/Cntr=0.3,0.1

Type RM Length L Ch R = 1 ,11327   ,470,470,470
BEGIN DESCRIPTION:
UNT 005 IN RACR 23.0
END DESCRIPTION:
XS GIS Cut Line= 4
      2206166.89     13238628.26       2206544.2     13238311.59
      2206712.65     13237691.68      2206678.96     13237374.95
#Sta/Elev= 30
  4072.2  375.11  4142.9  373.21  4148.8  373.16  4173.3  372.58  4187.7  370.59
  4216.3  369.16  4280.2  366.71  4399.7  362.79  4407.5  361.94    4414  362.44
  4436.1  360.87  4442.6  361.34  4596.4  355.93  4631.1  355.96  4642.2  354.92
  4715.8  352.78  4978.8  351.66  4984.2  351.18  4994.3  347.44  4997.6  347.94
  5004.9  351.04  5013.4  352.22  5053.2  351.65  5098.2  354.45  5160.4  356.17
  5252.3  360.24  5282.4  362.77    5383  366.74  5513.7  374.58  5525.7   374.6
#Mann= 6 ,-1 , 0
  4072.2     .05       0  4142.9     .08       0  4148.8     .05       0
  4280.2      .1       0  4978.8     .07       0  5013.4      .1       0
Bank Sta=4978.8,5013.4
XS Rating Curve= 0 ,0
Exp/Cntr=0.3,0.1

Type RM Length L Ch R = 1 ,10857   ,433,433,433
BEGIN DESCRIPTION:
UNT 005 IN RACR 22.0
END DESCRIPTION:
XS GIS Cut Line= 4
      2206773.28     13238938.27      2206988.91     13238426.14
      2207116.94     13237826.45      2206887.86     13237354.82
#Sta/Elev= 30
  4149.7  370.45  4199.9  369.21    4282  365.96  4292.3  366.33  4300.3  365.18
  4606.8  355.41  4628.6   355.6  4650.3  354.37  4827.3  351.17    4858  350.06
  4898.9  349.77  4909.2   349.1  4964.2  349.09    4991  348.13  5000.9  345.75
  5013.8  349.34  5031.9  349.64  5052.3  348.74  5058.2   349.8  5072.8  349.43
  5164.8   350.2  5321.1  352.97  5534.6  359.99  5579.7   362.1  5596.1  362.26
  5602.3   363.2  5751.7   368.8  5760.2  368.44  5773.9  369.78  5842.9  371.85
#Mann= 3 , 0 , 0
  4149.7      .1       0  4964.2     .07       0  5013.8      .1       0
Bank Sta=4964.2,5013.8
XS Rating Curve= 0 ,0
Exp/Cntr=0.3,0.1

Type RM Length L Ch R = 1 ,10424   ,500,500,500
BEGIN DESCRIPTION:
UNT 005 IN RACR 21.0
END DESCRIPTION:
XS GIS Cut Line= 3
       2207480.8     13238938.25      2207460.58     13237934.26
      2207393.27     13237261.11
#Sta/Elev= 30
    4270  370.72  4311.4  369.69  4371.4  366.93  4401.4  366.48  4471.4  363.38
  4511.4   362.6  4531.4  360.94  4561.5  360.33  4591.5  358.55  4681.5  356.19
  4701.5  354.56  4721.5  354.36  4741.5  352.95  4951.5  346.49  4981.5  346.66
  4991.5  345.72  5001.3  343.47  5011.5  345.34  5021.5  345.18  5031.5  346.32
  5111.6  347.89  5402.2  350.74  5412.3  351.69  5502.7  353.05  5643.4  357.17
  5656.6  357.01  5663.5  357.83  5733.9   359.4  5804.2  362.35  5950.7  366.97
#Mann= 3 , 0 , 0
    4270      .1       0  4981.5     .07       0  5031.5      .1       0
Bank Sta=4981.5,5031.5
XS Rating Curve= 0 ,0
Exp/Cntr=0.3,0.1

Type RM Length L Ch R = 1 ,9924    ,398,398,398
BEGIN DESCRIPTION:
UNT 005 IN RACR 20.0
END DESCRIPTION:
XS GIS Cut Line= 4
      2208067.01     13238918.04      2208019.84     13238500.26
      2207844.65      13237765.8      2207521.98     13237234.74
#Sta/Elev= 30
  4318.3   368.7  4353.8  366.85  4360.7  367.31  4430.2  364.14  4450.5  361.58
  4530.3  360.42  4591.2  356.68  4768.7  349.75  4978.7  344.03  4984.4  341.83
  4989.5  342.64    4999  340.35  5002.3  340.85  5009.5  344.34  5242.2  344.83
  5389.9  345.99    5431  347.48  5451.6  346.82  5724.7  354.64  5730.5  354.15
    5746  355.38  5761.5   354.8  5773.4  356.38  5796.8  356.12  5935.9   361.1
  5941.8  362.06  5978.6  362.91  5984.4  362.01  6015.4  364.09  6115.2  367.11
#Mann= 4 ,-1 , 0
  4318.3     .05       0  4353.8      .1       0  4978.7     .07       0
  5009.5      .1       0
Bank Sta=4978.7,5009.5
XS Rating Curve= 0 ,0
Exp/Cntr=0.3,0.1

Type RM Length L Ch R = 1 ,9526    ,475,475,475
BEGIN DESCRIPTION:
UNT 005 IN RACR 19.0
END DESCRIPTION:
XS GIS Cut Line= 4
      2208309.58     13238904.52      2208343.27     13238439.61
      2208269.15     13237631.04      2208342.85     13237262.53
#Sta/Elev= 30
    4179  365.76  4222.1  364.79  4236.8  363.49  4246.8  363.85  4276.9  363.21
  4286.9  362.07  4307.8  361.23  4347.1  359.93  4356.4  358.95  4361.5   359.2
  4427.3  355.96  4547.6  352.45  4597.8  349.62    4652  349.16  4698.1  347.22
  4818.6  344.67  4858.8   344.7  4969.2  342.38  4982.1  342.59  4989.3  339.95
  4999.1  337.98  5002.4  338.48  5009.4   341.4  5029.5  342.44  5059.6  342.05
  5180.1  343.34  5280.5  345.68  5370.9  345.93    5476  347.77  5832.9  359.53
#Mann= 4 ,-1 , 0
    4179     .05       0  4307.8      .1       0  4982.1     .07       0
  5029.5      .1       0
Bank Sta=4982.1,5029.5
XS Rating Curve= 0 ,0
Exp/Cntr=0.3,0.1