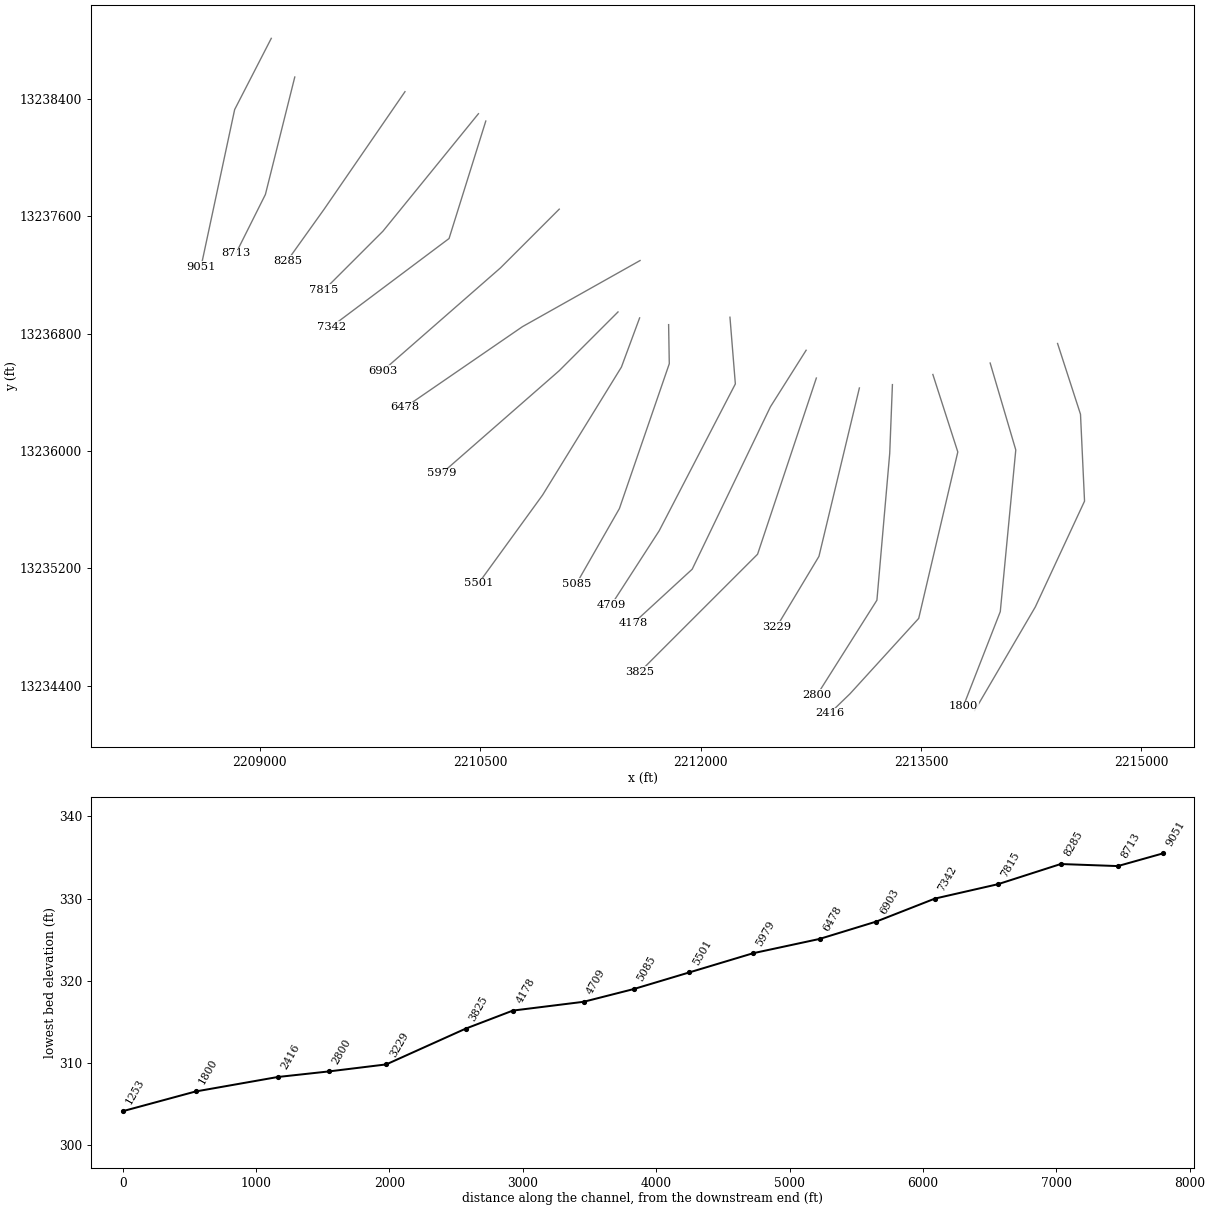
HEC-RAS study UNT 005 IN RACR.prj: UNT 005 IN RACR Base Level Engineering

--- UNT 005 IN RACR.g01 (geometry) --- (continued)

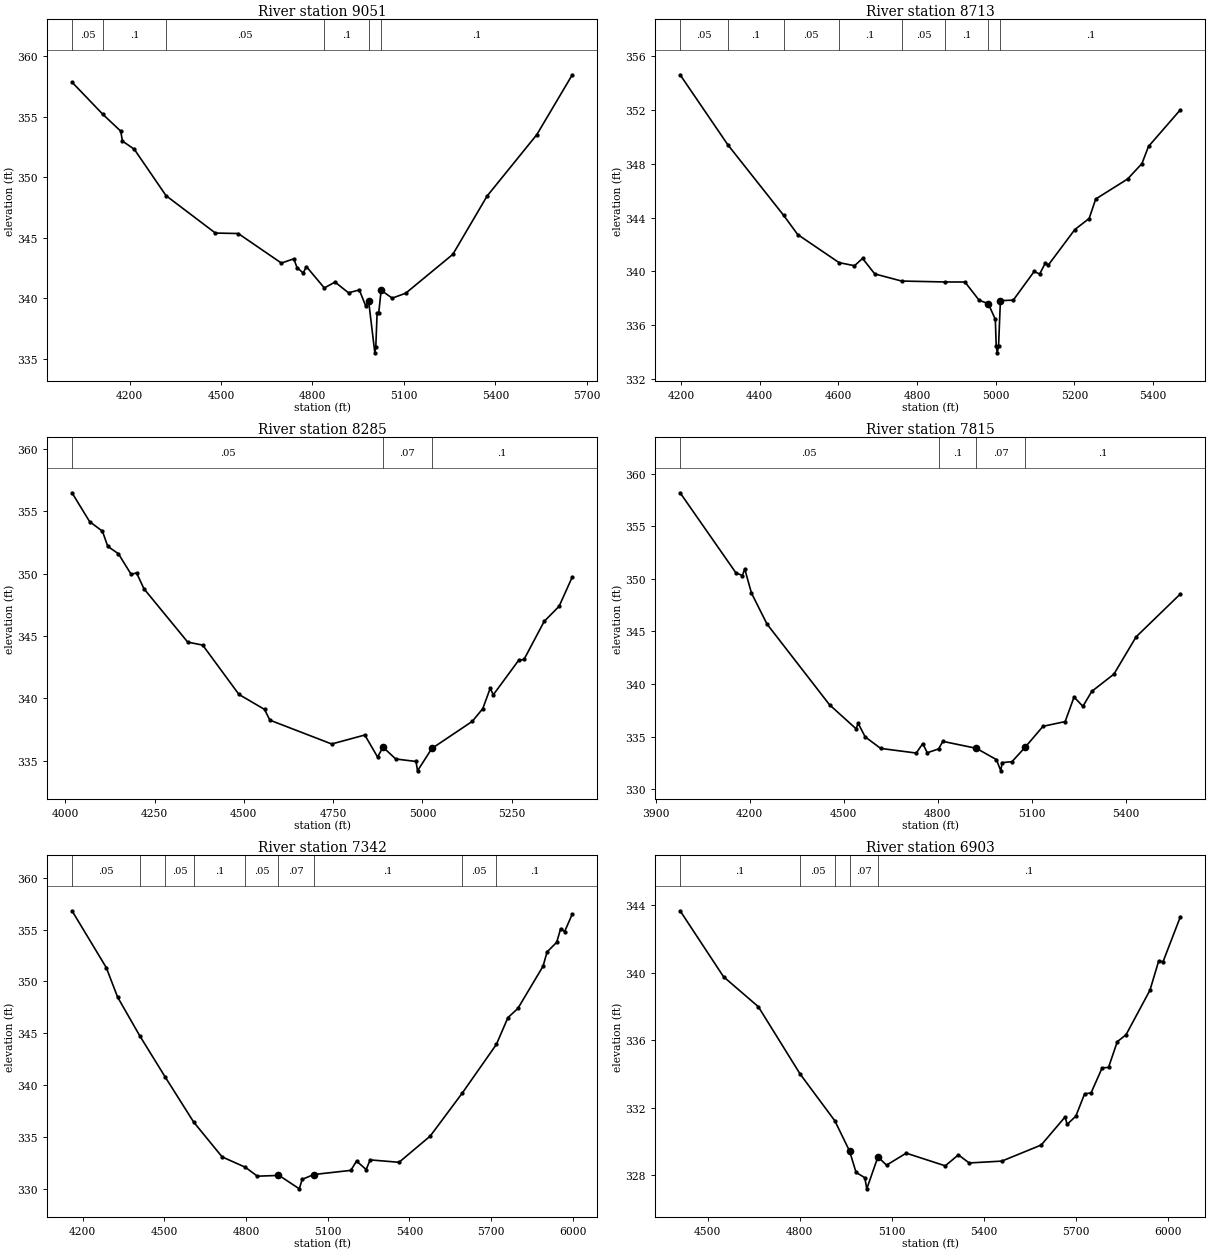
Type RM Length L Ch R = 1 ,9051    ,338,338,338
BEGIN DESCRIPTION:
UNT 005 IN RACR 18.0
END DESCRIPTION:
XS GIS Cut Line= 3
      2209077.74     13238810.24      2208828.41     13238325.06
      2208599.31     13237253.67
#Sta/Elev= 30
  4011.2  357.86  4112.5   355.2  4171.1  353.81  4176.7  352.99  4215.4  352.32
  4319.7  348.48  4481.6  345.39  4556.7  345.35    4698  342.91  4738.9  343.26
  4749.2  342.54  4769.6  342.09  4780.1  342.62    4839  340.85  4873.9  341.34
  4918.3  340.45  4953.7  340.69  4974.1   339.4  4984.4  339.74  5004.6  335.49
  5007.8  335.99  5012.1  338.81  5017.2  338.75  5025.3  340.66  5061.6  340.01
    5106  340.42  5260.5  343.63  5372.9  348.45  5535.9  353.52  5652.3  358.47
#Mann= 6 ,-1 , 0
  4011.2     .05       0  4112.5      .1       0  4319.7     .05       0
    4839      .1       0  4984.4     .07       0  5025.3      .1       0
Bank Sta=4984.4,5025.3
XS Rating Curve= 0 ,0
Exp/Cntr=0.3,0.1

Type RM Length L Ch R = 1 ,8713    ,428,428,428
BEGIN DESCRIPTION:
UNT 005 IN RACR 17.0
END DESCRIPTION:
XS GIS Cut Line= 3
      2209237.72     13238546.87      2209037.72     13237746.85
       2208837.7     13237346.81
#Sta/Elev= 30
  4197.6  354.63    4319  349.42  4460.7  344.18  4496.5  342.75  4601.7  340.66
  4640.9  340.43  4661.5  340.97  4692.4  339.82  4760.6  339.29  4872.3  339.22
  4921.7  339.22  4957.8  337.86    4981  337.61    4999  336.44  5001.2  334.45
  5003.9  333.95  5007.2  334.45  5011.9  337.83  5044.6  337.87  5097.7     340
  5111.7  339.81  5125.7  340.61    5134  340.49  5201.1  343.12  5237.5  343.94
  5254.2  345.39  5335.3  346.88  5371.6  348.02  5388.4   349.3  5469.5  352.03
#Mann= 8 ,-1 , 0
  4197.6     .05       0    4319      .1       0  4460.7     .05       0
  4601.7      .1       0  4760.6     .05       0  4872.3      .1       0
    4981     .07       0  5011.9      .1       0
Bank Sta=4981,5011.9
XS Rating Curve= 0 ,0
Exp/Cntr=0.3,0.1

Type RM Length L Ch R = 1 ,8285    ,470,470,470
BEGIN DESCRIPTION:
UNT 005 IN RACR 16.0
END DESCRIPTION:
XS GIS Cut Line= 3
      2209987.74     13238446.88      2209437.72     13237646.85
       2209187.7     13237296.83
#Sta/Elev= 30
  4018.8  356.47  4068.2  354.16  4104.1  353.39  4118.9  352.18  4148.7  351.59
  4184.6  349.93  4199.5  350.06  4220.4  348.78  4342.9  344.51  4384.8  344.27
  4486.3  340.32    4558  339.12  4572.9  338.26  4746.1  336.35  4838.8  337.07
  4874.6   335.3  4889.5   336.1  4925.4  335.15  4982.2  334.95  4986.4   334.2
  5026.5  335.99  5139.6  338.16  5169.1  339.18    5190  340.81  5198.6  340.29
  5269.8  343.06  5284.6  343.12  5341.1  346.17  5382.9  347.38  5419.8  349.73
#Mann= 3 , 0 , 0
  4018.8     .05       0  4889.5     .07       0  5026.5      .1       0
Bank Sta=4889.5,5026.5
XS Rating Curve= 0 ,0
Exp/Cntr=0.3,0.1

Type RM Length L Ch R = 1 ,7815    ,473,473,473
BEGIN DESCRIPTION:
UNT 005 IN RACR 15.0
END DESCRIPTION:
XS GIS Cut Line= 3
      2210487.71     13238296.84      2209837.72     13237496.85
      2209437.75     13237096.88
#Sta/Elev= 30
  3977.7  358.17  4155.8  350.56  4176.6  350.31  4183.8  350.94  4205.4  348.64
  4254.9   345.7  4454.4  338.03  4539.4  335.74  4545.8  336.27  4568.1  334.98
  4617.7  333.88  4731.2  333.44    4752  334.34  4766.4  333.47  4802.6  333.83
  4815.9  334.55    4923  333.89  4986.9  332.82    5001  331.75  5005.2  332.53
  5036.7  332.62  5079.2  334.01  5135.7  335.98  5206.4  336.43  5234.7  338.76
    5263  337.88  5291.3   339.3    5362  340.94  5432.7  344.48  5574.1  348.56
#Mann= 4 ,-1 , 0
  3977.7     .05       0  4802.6      .1       0    4923     .07       0
  5079.2      .1       0
Bank Sta=4923,5079.2
XS Rating Curve= 0 ,0
Exp/Cntr=0.3,0.1

Type RM Length L Ch R = 1 ,7342    ,439,439,439
BEGIN DESCRIPTION:
UNT 005 IN RACR 14.0
END DESCRIPTION:
XS GIS Cut Line= 3
      2210537.73     13238246.89      2210287.72     13237446.85
      2209487.71     13236846.85
#Sta/Elev= 30
  4160.4  356.81  4286.2  351.34  4328.1  348.48  4408.8  344.78  4502.9  340.78
  4607.4  336.44    4712  333.08  4797.5  332.08  4841.4  331.22  4915.7  331.29
  4917.4  331.36  4995.7     330  5005.9  330.91  5048.6  331.38    5185  331.78
  5205.9  332.68  5241.3  331.86  5255.9  332.79  5362.1  332.56  5476.7  335.09
    5594  339.22  5719.8  343.93  5762.1  346.51  5798.6  347.39  5891.3  351.47
  5905.9  352.84  5941.3  353.77  5955.9  355.09  5970.5  354.81  5998.6  356.49
#Mann= 9 ,-1 , 0
  4160.4     .05       0  4408.8      .1       0  4502.9     .05       0
  4607.4      .1       0  4797.5     .05       0  4915.7     .07       0
  5048.6      .1       0    5594     .05       0  5719.8      .1       0
Bank Sta=4917.4,5048.6
XS Rating Curve= 0 ,0
Exp/Cntr=0.3,0.1

Type RM Length L Ch R = 1 ,6903    ,425,425,425
BEGIN DESCRIPTION:
UNT 005 IN RACR 13.0
END DESCRIPTION:
XS GIS Cut Line= 3
      2211037.72     13237646.85      2210637.72     13237246.85
      2209837.71     13236546.85
#Sta/Elev= 30
  4410.4  343.65  4551.8  339.75    4665  337.98  4801.4  333.99  4914.2  331.23
  4961.9  329.45  4983.2  328.18  5011.7  327.87  5018.1  327.21  5054.4   329.1
  5082.4  328.61  5146.4  329.32  5273.6  328.57  5316.3  329.22  5351.5  328.74
  5457.8  328.85  5585.9   329.8  5663.7  331.46  5670.4  331.02  5698.8  331.51
  5727.3  332.83  5748.2  332.88  5784.3  334.36  5805.1  334.39  5833.6  335.91
  5862.1  336.32  5939.9  338.95  5968.4  340.68  5982.6  340.64  6039.1   343.3
#Mann= 5 ,-1 , 0
  4410.4      .1       0  4801.4     .05       0  4914.2      .1       0
  4961.9     .07       0  5054.4      .1       0
Bank Sta=4961.9,5054.4
XS Rating Curve= 0 ,0
Exp/Cntr=0.3,0.1

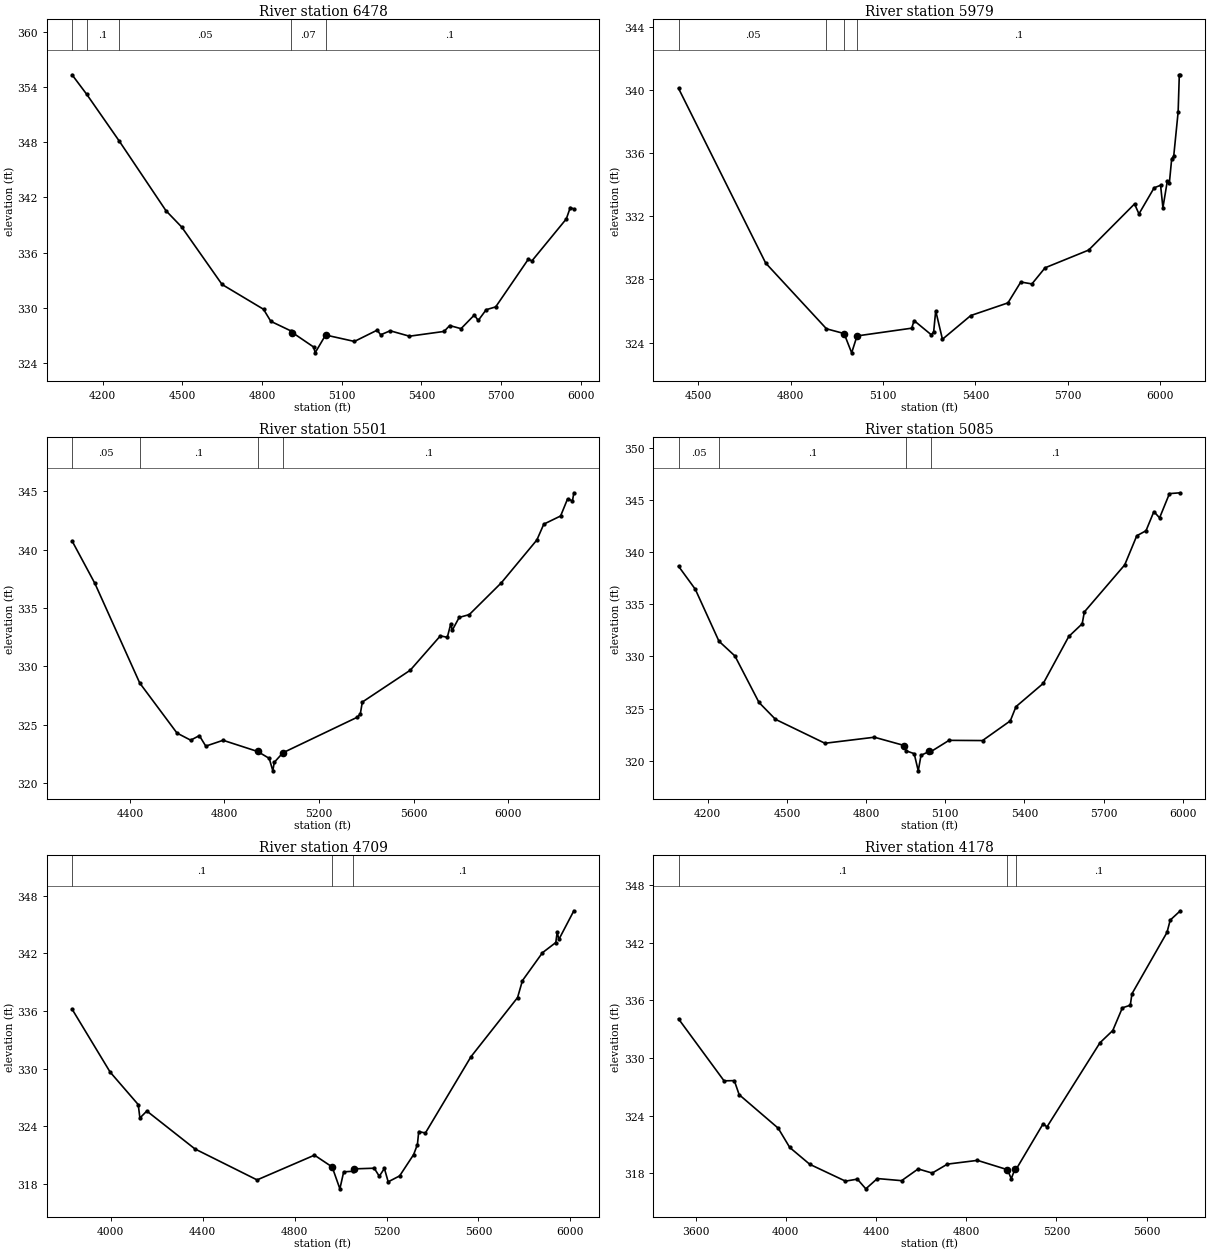
Type RM Length L Ch R = 1 ,6478    ,499,499,499
BEGIN DESCRIPTION:
UNT 005 IN RACR 12.0
END DESCRIPTION:
XS GIS Cut Line= 3
      2211587.75     13237296.87      2210787.72     13236846.85
      2209987.75     13236296.88
#Sta/Elev= 30
  4085.4  355.35  4140.4  353.23  4263.7  348.11  4438.9  340.56  4498.2  338.78
  4649.9  332.54    4806  329.84  4833.4  328.53  4908.7  327.49  4914.4  327.31
  4995.3  325.72  5000.2   325.1  5039.7  327.04  5148.1  326.34  5233.9  327.57
  5246.8  327.06  5282.7   327.5  5355.2  326.91  5485.7  327.43  5506.7  328.07
  5549.4  327.73  5599.3  329.21  5614.2  328.62    5644  329.79  5679.9   330.1
  5802.3  335.27  5816.4  335.11  5945.7  339.67  5960.6  340.91  5974.1  340.75
#Mann= 5 ,-1 , 0
  4085.4     .05       0  4140.4      .1       0  4263.7     .05       0
  4908.7     .07       0  5039.7      .1       0
Bank Sta=4914.4,5039.7
XS Rating Curve= 0 ,0
Exp/Cntr=0.3,0.1

Type RM Length L Ch R = 1 ,5979    ,478,478,478
BEGIN DESCRIPTION:
UNT 005 IN RACR 11.0
END DESCRIPTION:
XS GIS Cut Line= 3
       2211437.7     13236946.84      2211037.72     13236546.85
       2210237.7     13235846.84
#Sta/Elev= 30
  4436.4  340.09  4719.2  329.04  4916.6  324.88  4973.8  324.58  4998.3  323.36
  5015.8  324.43  5193.3  324.92  5200.9   325.4  5256.9   324.5  5264.5  324.69
  5271.1  326.02    5293  324.22    5385  325.72  5505.6  326.52  5547.3  327.84
  5583.4  327.72  5626.1  328.74  5767.5  329.86  5916.5  332.78  5930.8  332.15
  5980.1   333.8    6001  333.96  6008.6  332.54  6022.8  334.22  6029.5   334.1
  6037.1  335.64  6043.7  335.81    6058   338.6  6061.8  340.95  6065.1  340.95
#Mann= 4 ,-1 , 0
  4436.4     .05       0  4916.6      .1       0  4973.8     .07       0
  5015.8      .1       0
Bank Sta=4973.8,5015.8
XS Rating Curve= 0 ,0
Exp/Cntr=0.3,0.1

Type RM Length L Ch R = 1 ,5501    ,416,416,416
BEGIN DESCRIPTION:
UNT 005 IN RACR 10.0
END DESCRIPTION:
XS GIS Cut Line= 4
      2211584.87      13236906.3        2211461.     13236571.38
      2210924.17      13235699.6      2210488.27     13235098.52
#Sta/Elev= 30
    4155  340.75  4251.7   337.1  4441.4  328.56    4599  324.27  4656.9  323.66
  4693.6  324.05  4720.8  323.15  4794.1  323.65  4940.2  322.69  4989.3   322.1
  5004.5  321.03  5010.6  321.76  5047.3  322.58  5362.1  325.63  5374.7  325.91
  5383.3  326.93    5586  329.66  5713.6  332.61  5742.9  332.48  5757.6  333.65
  5763.8  333.09  5793.2  334.19  5835.8  334.43  5971.6  337.16  6121.8  340.83
  6151.2  342.19  6222.3  342.89  6251.7  344.35  6272.5  344.19  6278.4  344.88
#Mann= 4 ,-1 , 0
    4155     .05       0  4441.4      .1       0  4940.2     .07       0
  5047.3      .1       0
Bank Sta=4940.2,5047.3
XS Rating Curve= 0 ,0
Exp/Cntr=0.3,0.1

Type RM Length L Ch R = 1 ,5085    ,376,376,376
BEGIN DESCRIPTION:
UNT 005 IN RACR 9.0
END DESCRIPTION:
XS GIS Cut Line= 4
      2211782.18     13236860.39      2211786.77     13236594.32
      2211447.23     13235607.84      2211153.56     13235093.91
#Sta/Elev= 30
  4089.4  338.67  4152.9  336.46  4242.5  331.47    4303  330.05  4394.3  325.58
  4456.7  323.96  4644.1  321.66  4831.4  322.24  4945.1  321.44  4951.1  320.94
  4982.3  320.66  4997.7  319.01  5008.2   320.5  5039.4  320.88  5044.7  320.84
  5114.3  321.94  5241.2  321.92  5346.4  323.81  5368.1  325.18  5471.6  327.42
    5568  331.92  5618.8  333.14  5627.1  334.28    5780   338.8  5825.7   341.6
  5860.6  342.08  5890.5  343.92  5912.1  343.32  5949.5  345.65  5990.7  345.73
#Mann= 4 ,-1 , 0
  4089.4     .05       0  4242.5      .1       0  4951.1     .07       0
  5044.7      .1       0
Bank Sta=4945.1,5039.4
XS Rating Curve= 0 ,0
Exp/Cntr=0.3,0.1

Type RM Length L Ch R = 1 ,4709    ,531,531,531
BEGIN DESCRIPTION:
UNT 005 IN RACR 8.0
END DESCRIPTION:
XS GIS Cut Line= 4
      2212199.71     13236910.89      2212236.42     13236456.67
      2211717.94     13235456.42      2211392.47     13234952.17
#Sta/Elev= 30
  3832.4  336.19  3997.9  329.63  4120.2  326.24  4127.4  324.84  4157.5  325.57
  4366.8  321.62  4637.1  318.39  4886.7  320.97  4963.7  319.74  4997.2  317.46
  5013.8  319.23  5052.4  319.29  5058.1  319.54  5146.6  319.61  5168.7  318.77
  5190.8  319.59  5207.3  318.19  5257.2  318.81    5318  321.03  5334.5  322.08
  5340.1  323.43  5369.2  323.28  5567.4  331.23    5770  337.39  5791.2  339.16
  5878.4  342.07  5936.3  343.13  5942.3   344.2  5949.8  343.46  6014.9  346.44
#Mann= 3 ,-1 , 0
  3832.4      .1       0  4963.7     .07       0  5052.4      .1       0
Bank Sta=4963.7,5058.1
XS Rating Curve= 0 ,0
Exp/Cntr=0.3,0.1

Type RM Length L Ch R = 1 ,4178    ,353,353,353
BEGIN DESCRIPTION:
UNT 005 IN RACR 7.0
END DESCRIPTION:
XS GIS Cut Line= 4
      2212718.17     13236686.05      2212475.01     13236300.67
      2211942.77     13235194.89      2211543.57     13234827.81
#Sta/Elev= 30
  3524.4  334.06  3726.2  327.62  3771.8  327.64  3793.2  326.18  3966.2   322.7
  4017.6  320.69  4106.4  318.94  4264.7  317.19  4317.3   317.4  4354.9  316.39
    4406  317.46  4513.6  317.24    4587  318.46  4649.3  318.03  4716.8  318.96
    4850  319.35  4983.1  318.38  4999.8  317.44  5016.4  318.45  5022.5  318.46
  5141.1  323.15  5158.2  322.83  5393.3  331.58    5450  332.85  5492.6  335.21
  5527.7  335.48  5535.1  336.67  5690.5  343.05  5704.7  344.33  5749.6   345.3
#Mann= 3 ,-1 , 0
  3524.4      .1       0  4983.1     .07       0  5022.5      .1       0
Bank Sta=4983.1,5016.4
XS Rating Curve= 0 ,0
Exp/Cntr=0.3,0.1

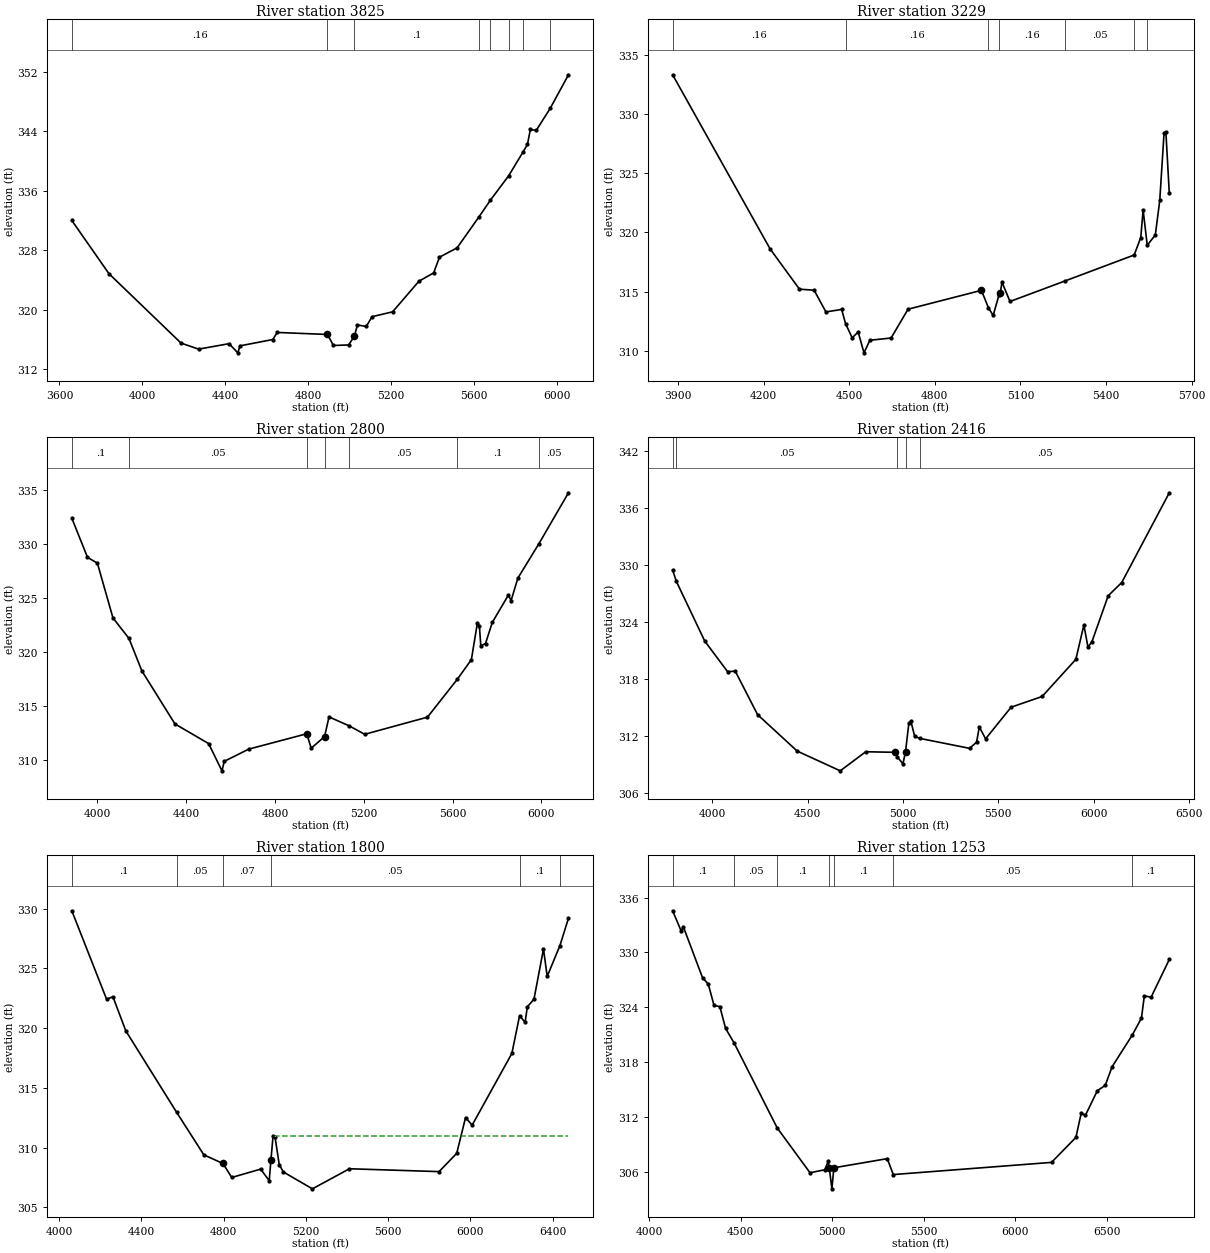
Type RM Length L Ch R = 1 ,3825    ,596,596,596
BEGIN DESCRIPTION:
UNT 005 IN RACR 6.0
END DESCRIPTION:
XS GIS Cut Line= 3
      2212787.71     13236496.83      2212387.72     13235296.85
      2211587.69     13234496.83
#Sta/Elev= 30
  3659.5  331.99  3838.7  324.84  4186.5  315.51  4270.9   314.7  4418.4  315.43
  4460.3   314.2  4471.1  315.14  4629.2  315.99  4650.3  316.94  4892.8  316.67
  4921.8  315.19  4995.1  315.26  5023.4  316.47  5037.5  317.95    5080  317.74
  5108.2  319.06  5207.2  319.71  5334.5  323.83  5405.2  324.94  5433.5  327.06
  5518.4  328.31  5625.1  332.52  5679.5  334.73  5767.3     338  5837.4  341.23
  5857.8   342.2  5871.9  344.22  5900.2  344.09  5967.3  347.04  6055.8  351.57
#Mann= 8 ,-1 , 0
  3659.5     .16       0  4892.8     .07       0  5023.4      .1       0
  5625.1     .05       0  5679.5      .1       0  5767.3     .05       0
  5837.4      .1       0  5967.3     .05       0
Bank Sta=4892.8,5023.4
XS Rating Curve= 0 ,0
Exp/Cntr=0.3,0.1

Type RM Length L Ch R = 1 ,3229    ,429,429,429
BEGIN DESCRIPTION:
UNT 005 IN RACR 5.0
END DESCRIPTION:
XS GIS Cut Line= 3
      2213080.65     13236429.09      2212805.37     13235282.07
      2212516.79      13234801.1
#Sta/Elev= 30
  3881.1   333.3  4222.8  318.61  4325.6  315.22    4377  315.13  4418.2   313.3
  4473.4  313.51  4487.1  312.31  4510.3  311.12  4531.3  311.61  4551.6  309.85
  4572.4  310.91  4646.6   311.1  4706.1  313.53  4963.2  315.12  4987.6  313.66
  5004.4     313  5024.5  314.71  5029.6  314.93  5035.2  315.81  5063.4  314.18
    5257  315.92  5498.5   318.1  5521.6  319.57  5529.9   321.9  5544.3  318.92
  5572.6  319.79  5588.2   322.7  5603.2  328.38  5609.6   328.5  5621.6  323.31
#Mann= 7 ,-1 , 0
  3881.1     .16       0  4487.1     .16       0  4987.6     .07       0
  5024.5     .16       0    5257     .05       0  5498.5      .1       0
  5544.3     .05       0
Bank Sta=4963.2,5029.6
XS Rating Curve= 0 ,0
Exp/Cntr=0.3,0.1

Type RM Length L Ch R = 1 ,2800    ,384,384,384
BEGIN DESCRIPTION:
UNT 005 IN RACR 4.0
END DESCRIPTION:
XS GIS Cut Line= 4
      2213305.49     13236452.05      2213287.14     13235984.08
      2213199.96     13234983.83      2212792.15     13234337.74
#Sta/Elev= 30
  3885.1  332.38  3955.6  328.76  4000.4  328.21  4070.4  323.15  4142.5  321.25
  4200.5  318.25  4349.5  313.34  4501.2  311.52  4561.2     309  4571.5  309.88
  4681.9  311.01  4942.9  312.43    4963  311.09  5023.2  312.17  5043.3  313.99
  5135.3  313.15  5203.9  312.38  5486.7  313.97  5621.2  317.48  5684.3  319.29
  5711.4  322.69  5720.5  322.38  5726.7  320.57  5747.9  320.78  5778.4  322.73
  5850.6  325.25  5863.2  324.76  5893.8  326.84  5988.8  330.03  6121.5  334.73
#Mann= 7 ,-1 , 0
  3885.1      .1       0  4142.5     .05       0  4942.9     .07       0
  5023.2      .1       0  5135.3     .05       0  5621.2      .1       0
  5988.8     .05       0
Bank Sta=4942.9,5023.2
XS Rating Curve= 0 ,0
Exp/Cntr=0.3,0.1

Type RM Length L Ch R = 1 ,2416    ,616,616,616
BEGIN DESCRIPTION:
UNT 005 IN RACR 3.0
END DESCRIPTION:
XS GIS Cut Line= 5
      2213580.78     13236520.92      2213750.56     13235993.25
      2213484.43     13234859.94      2213016.43     13234346.05
      2212878.75     13234212.96
#Sta/Elev= 30
  3792.5  329.47  3811.8  328.28  3960.8  321.99  4080.4  318.77  4121.2  318.81
    4238  314.24  4445.8   310.4  4671.6  308.32  4805.3  310.33  4959.4  310.27
  4969.7  309.82  5000.5  309.06 5014.03  310.34  5031.3  313.31    5042  313.56
  5062.1  311.94  5090.5  311.73  5349.8  310.69  5386.5  311.33  5401.1  312.94
    5434  311.69  5567.7  315.02  5730.5  316.15  5907.4  320.06  5949.4  323.67
  5971.1  321.34    5992  321.93  6077.1  326.76  6148.1  328.15  6397.5   337.6
#Mann= 5 ,-1 , 0
  3792.5      .1       0  3811.8     .05       0  4969.7     .07       0
 5014.03      .1       0  5090.5     .05       0
Bank Sta=4959.4,5014.03
XS Rating Curve= 0 ,0
Exp/Cntr=0.3,0.1

Type RM Length L Ch R = 1 ,1800    ,547,547,547
BEGIN DESCRIPTION:
UNT 005 IN RACR 2.0
END DESCRIPTION:
XS GIS Cut Line= 4
      2213970.78     13236598.94      2214145.15     13236007.02
      2214039.62     13234905.83      2213787.85      13234260.4
#Sta/Elev= 30
  4061.5  329.82  4230.5  322.43  4261.7  322.62  4324.3  319.77  4571.1  312.97
  4703.9   309.4  4796.9  308.68  4839.5  307.51  4980.1  308.21  5021.9  307.24
  5030.3     309  5040.4  310.95  5050.4  310.87  5070.5  308.59  5090.6  307.97
    5232  306.56  5412.1  308.24  5848.1     308    5934  309.53  5976.9  312.52
  6009.1  311.89  6202.3  317.89  6239.8  321.05  6266.5  320.48  6277.5  321.79
  6309.7  322.42  6356.1  326.62  6374.1  324.33  6435.8   326.9  6477.6  329.19
#Mann= 6 ,-1 , 0
  4061.5      .1       0  4571.1     .05       0  4796.9     .07       0
  5030.3     .05       0  6239.8      .1       0  6435.8     .05       0
#XS Ineff= 2 , 0
                         5047.72          311.01
Permanent Ineff=
       F       F
Bank Sta=4796.9,5030.3
XS Rating Curve= 0 ,0
Exp/Cntr=0.3,0.1

Type RM Length L Ch R = 1 ,1253    ,919,919,919
BEGIN DESCRIPTION:
Mapping XS 6e6f3506
END DESCRIPTION:
XS GIS Cut Line= 5
      2214429.61       13236732.      2214585.62      13236250.2
      2214613.15     13235658.31      2214278.21     13234937.94
      2213865.42     13234231.61
#Sta/Elev= 30
  4128.9  334.55  4176.5  332.29  4186.9  332.83    4292  327.24  4323.5  326.53
    4355   324.2  4386.6  324.08  4418.1  321.69  4463.5  320.14    4700  310.81
  4878.9  305.92    4959  306.24    4979  307.19 4984.07  306.44  4998.4  304.16
  5009.1  306.46  5300.6  307.46  5333.6  305.72  6197.4  307.05  6330.5  309.78
  6359.4  312.42  6382.6   312.2  6447.8  314.89  6490.8  315.47    6528   317.5
  6638.4  320.97  6688.4  322.82  6704.1  325.24  6741.3  325.11  6840.4  329.23
#Mann= 7 ,-1 , 0
  4128.9      .1       0  4463.5     .05       0    4700      .1       0
 4984.07     .07       0  5009.1      .1       0  5333.6     .05       0
  6638.4      .1       0
Bank Sta=4984.07,5009.1
XS Rating Curve= 0 ,0
Exp/Cntr=0.3,0.1