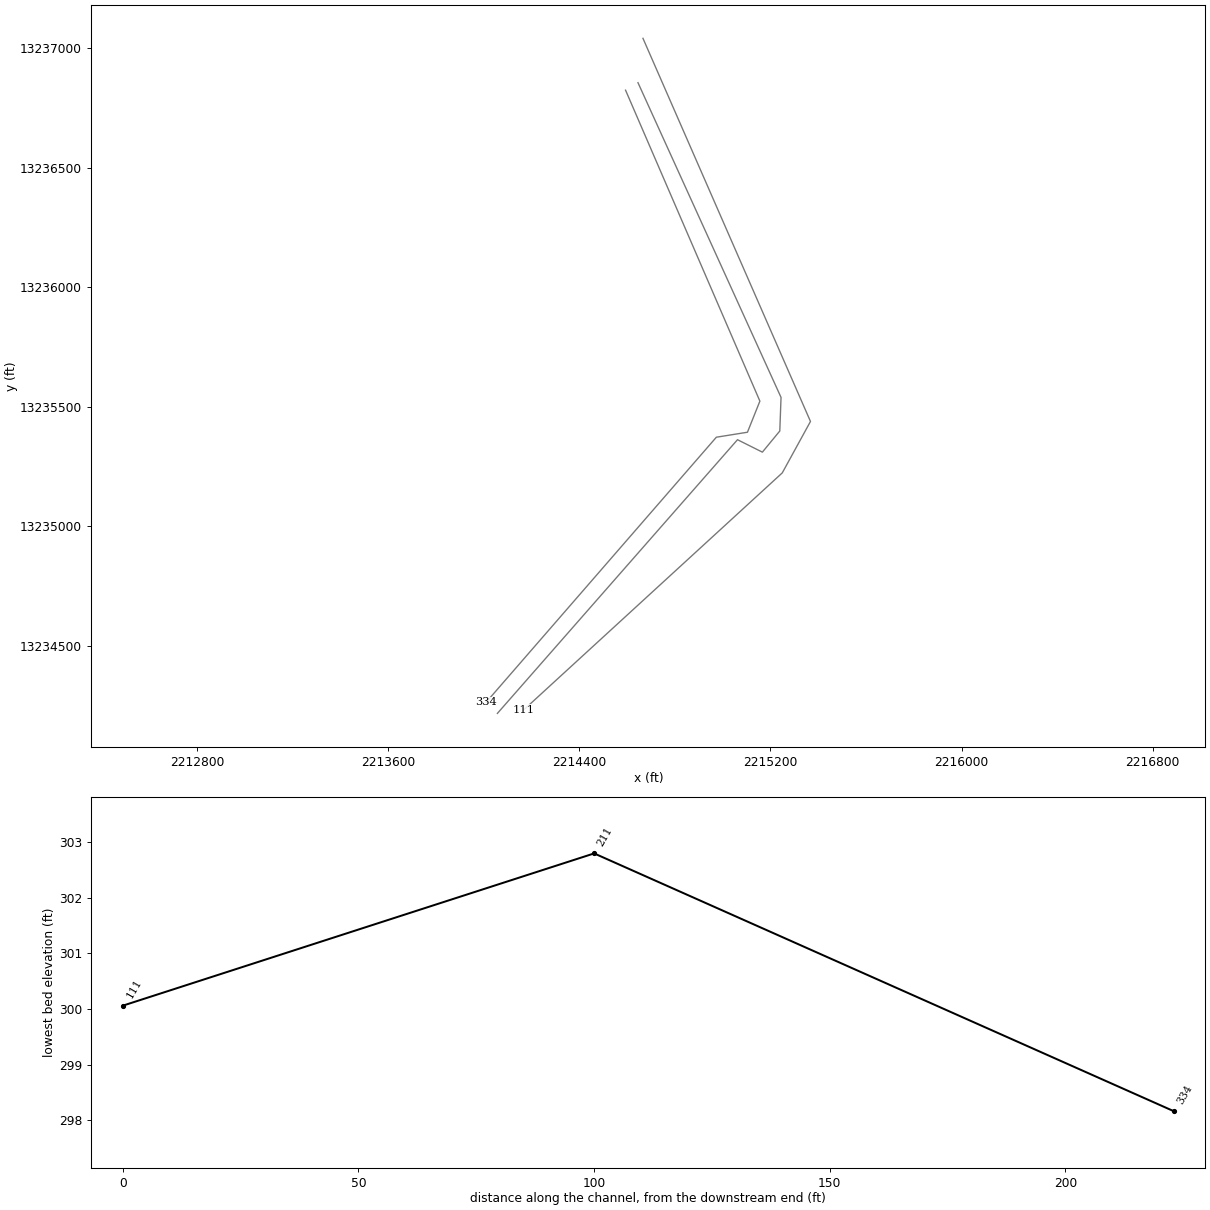
HEC-RAS study UNT 005 IN RACR.prj: UNT 005 IN RACR Base Level Engineering

--- UNT 005 IN RACR.g01 (geometry) --- (continued)

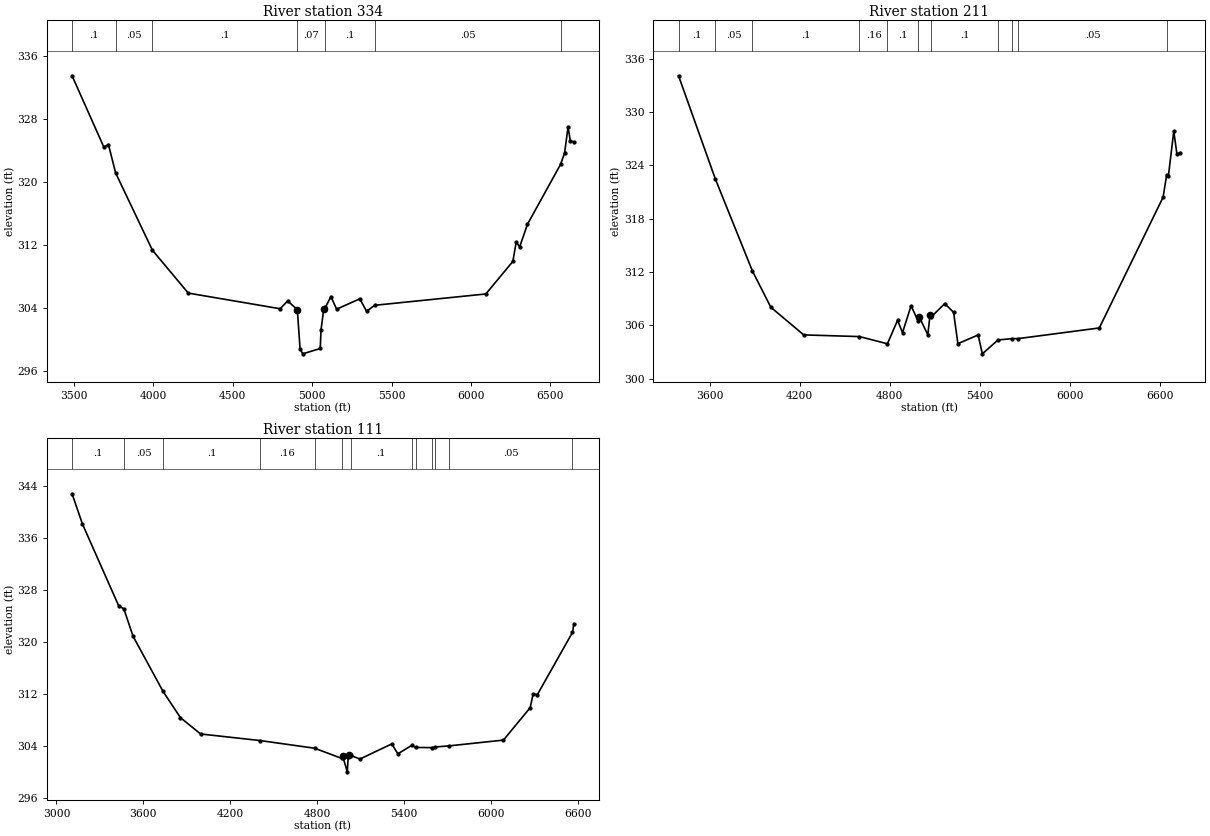
Type RM Length L Ch R = 1 ,334     ,123,123,123
BEGIN DESCRIPTION:
Mapping XS 21f263f8
END DESCRIPTION:
XS GIS Cut Line= 5
       2214593.3     13236825.26      2215155.79     13235523.21
       2215103.7       13235393.      2214973.49     13235372.17
      2214009.99     13234262.83
#Sta/Elev= 30
  3488.2   333.5  3688.2  324.44  3717.2  324.76  3762.7  321.14  3993.8  311.34
  4219.9  305.88  4798.5  303.89  4845.5  304.88  4906.5  303.79  4924.2  298.75
  4940.8  298.16  5050.9  298.84    5056  301.24  5073.1  303.83  5083.2  304.06
    5118  305.44  5154.1  303.84  5300.1  305.15  5342.8  303.57  5393.9  304.33
  6093.9  305.77  6263.9  309.91    6285  312.37  6306.6  311.75    6356  314.63
    6564  322.23  6589.7  323.69  6611.4     327  6625.7  325.24    6648   325.1
#Mann= 7 ,-1 , 0
  3488.2      .1       0  3762.7     .05       0  3993.8      .1       0
  4906.5     .07       0  5083.2      .1       0  5393.9     .05       0
    6564      .1       0
Bank Sta=4906.5,5073.1
XS Rating Curve= 0 ,0
Exp/Cntr=0.3,0.1

Type RM Length L Ch R = 1 ,211     ,100,100,100
BEGIN DESCRIPTION:
Mapping XS d406981f
END DESCRIPTION:
XS GIS Cut Line= 6
      2214645.38     13236856.51      2215244.33     13235538.83
      2215239.12     13235398.21       2215166.2     13235309.67
      2215062.04     13235361.75       2214056.8     13234215.89
#Sta/Elev= 30
  3392.4  334.06  3638.3  322.43  3884.6  312.12  4007.2  308.04  4226.6  304.93
  4598.2  304.74  4784.2  303.93  4851.8  306.56    4885  305.19  4941.9  308.21
  4989.7  306.45  4996.2  306.96  5053.5  304.94  5067.9  307.14  5074.4  306.92
  5166.7  308.45  5225.3  307.46  5253.8  303.94  5388.6  304.92  5416.8   302.8
  5521.3  304.36  5615.1  304.51  5654.9  304.51  6196.1  305.71  6621.3  320.41
  6645.2  322.95  6656.4  322.79  6692.4  327.82  6713.3  325.27    6736  325.43
#Mann= 11 ,-1 , 0
  3392.4      .1       0  3638.3     .05       0  3884.6      .1       0
  4598.2     .16       0  4784.2      .1       0  4989.7     .07       0
  5074.4      .1       0  5521.3     .05       0  5615.1      .1       0
  5654.9     .05       0  6645.2      .1       0
Bank Sta=4996.2,5067.9
XS Rating Curve= 0 ,0
Exp/Cntr=0.3,0.1

Type RM Length L Ch R = 1 ,111     ,0,0,0
BEGIN DESCRIPTION:
UNT 005 IN RACR 1.0
END DESCRIPTION:
XS GIS Cut Line= 4
      2214666.22     13237042.27      2215367.59     13235438.14
      2215249.54     13235222.86      2214167.31     13234230.82
#Sta/Elev= 30
  3108.1   342.8  3179.6  338.16  3430.5  325.55  3465.4  325.12    3529  320.91
  3735.8  312.44  3856.2  308.39  3995.3  305.88  4405.9  304.87  4782.4  303.69
  4970.8  302.12  4976.5  302.47  5008.3  300.06  5014.4  302.31  5020.1  302.63
  5030.5  302.59  5095.9  302.03  5315.1  304.35  5357.6  302.83  5453.4  304.13
  5480.9  303.81  5592.1  303.78  5616.4  303.88    5711  304.05  6086.5  304.94
  6270.9  309.92  6291.8  312.06  6320.2  311.91  6563.1   321.5  6572.5  322.81
#Mann= 13 ,-1 , 0
  3108.1      .1       0  3465.4     .05       0  3735.8      .1       0
  4405.9     .16       0  4782.4      .1       0  4970.8     .07       0
  5030.5      .1       0  5453.4     .05       0  5480.9      .1       0
  5592.1     .05       0  5616.4      .1       0    5711     .05       0
  6563.1      .1       0
Bank Sta=4976.5,5020.1
XS Rating Curve= 0 ,0
Exp/Cntr=0.3,0.1

Chan Stop Cuts=-1
Use User Specified Reach Order=0
Composite Channel Slope=5