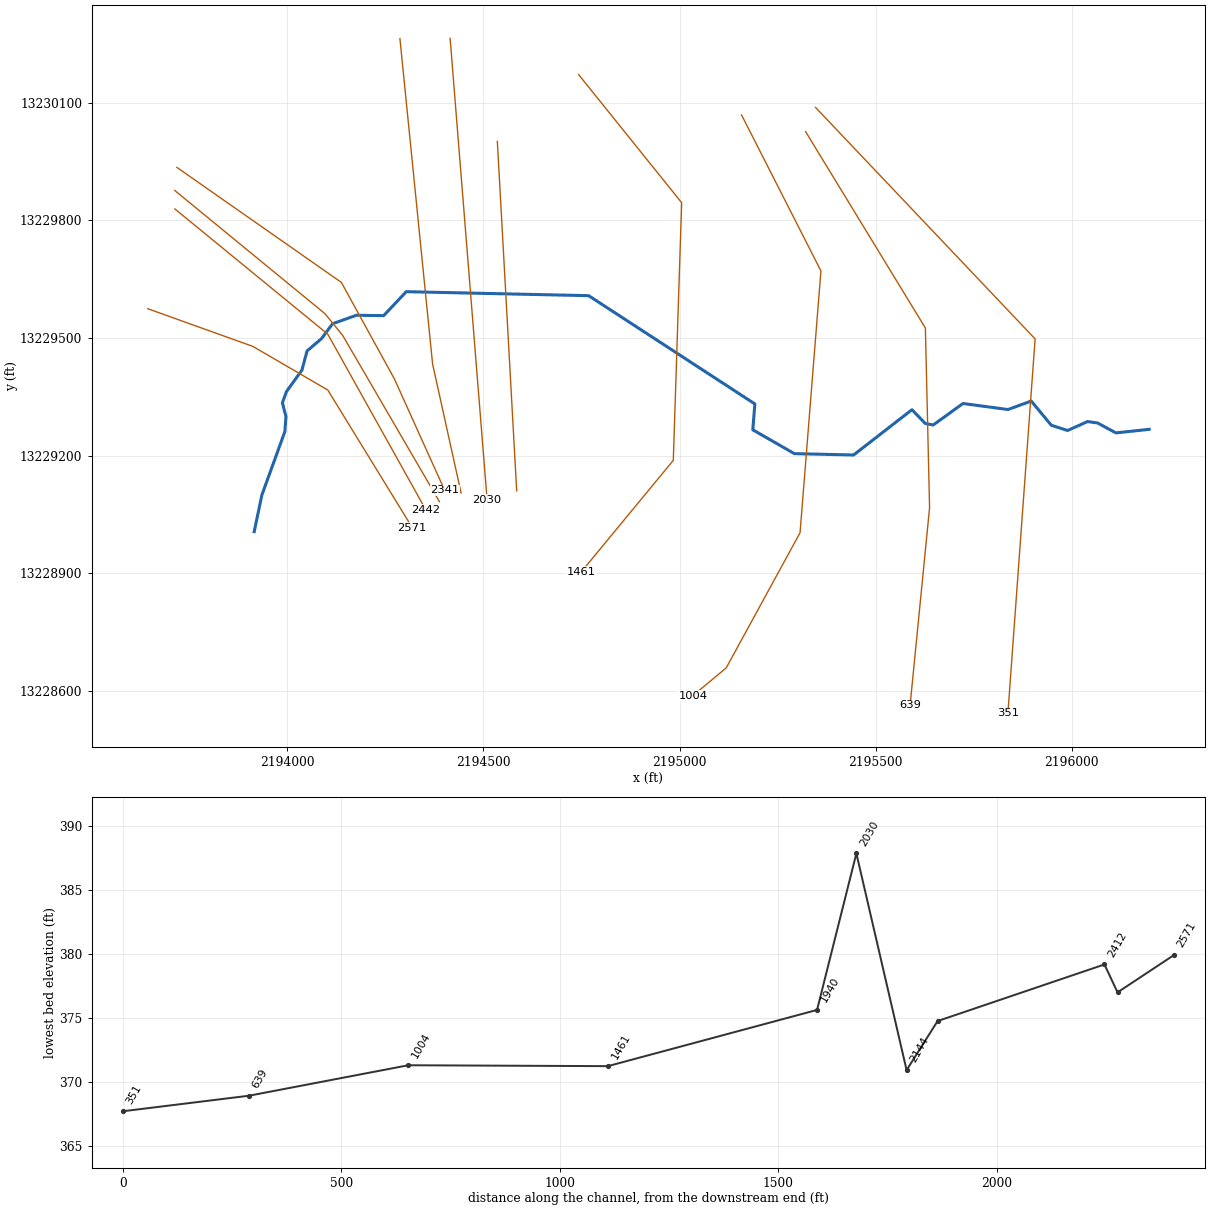
--- UNT 007 IN RACR.prj (project) ---

Proj Title=UNT 007 IN RACR Base Level Engineering
Current Plan=p01
Default Exp/Contr=0.3,0.1
English Units
Geom File=g01
Flow File=f01
Plan File=p01
Y Axis Title=Elevation
X Axis Title(PF)=Main Channel Distance
X Axis Title(XS)=Station
BEGIN DESCRIPTION:
UNT 007 IN RACR
END DESCRIPTION:
DSS File=dss
DSS Export Rating Curves= 0
DSS Export Rating Curve Sorted= 0
DSS Export Volume Flow Curves= 0
DXF OffsetX= 0
DXF OffsetY= 0
DXF ScaleX= 1
DXF ScaleY= 10

--- UNT 007 IN RACR.p01 (plan) ---

Plan Title=Multiple Run
Program Version=4.10
Short Identifier=Multiple Run
Geom File=g01
Flow File=f01
Subcritical Flow
K Sum by GR= 0
Std Step Tol= 0.01
Critical Tol= 0.01
Num of Std Step Trials= 20
Max Error Tol= 0.3
Flow Tol Ratio= 0.001
Split Flow NTrial= 30
Split Flow Tol= 0.02
Split Flow Ratio= 0.02
Log Output Level= 0
Friction Slope Method= 1
Unsteady Friction Slope Method= 2
Unsteady Bridges Friction Slope Method= 1
Parabolic Critical Depth
Global Vel Dist= 1 , 1 , 1
Global Log Level= 0
CheckData=True
Encroach Param=-1 ,0,0, 0
BEGIN DESCRIPTION:
Multiple Run
END DESCRIPTION:
Computation Interval=1HOUR
Output Interval=1HOUR
Run HTab= 0
Run UNet= 0
Run PostProcess= 0
Run WQNet= 0
UNET Theta= 1
UNET Theta Warmup= 1
UNET ZTol= 0.02
UNET ZSATol= 0.05
UNET MxIter= 20
UNET MaxInSteps= 0
UNET DtIC= 0
UNET DtMin= 0
UNET MaxCRTS= 20
UNET WFStab= 2
UNET SFStab= 1
UNET WFX= 1
UNET SFX= 1
UNET DSS MLevel= 4
UNET DZMax Abort= 100
UNET Convert EG Bridges= 0
UNET Use Existing IB Tables=-1
UNET Froude Reduction=False
UNET Froude Limit= 1
UNET Froude Power= 10
UNET Time Slicing=0,0, 5
UNET Junction Losses=0
Instantaneous Interval=1HOUR
DSS File=dss
Write IC File= 0
Write IC File at Sim End=0
Echo Input=False
Echo Parameters=False
Echo Output=False
Write Detailed= 0
WQ AD Non Conservative
WQ ULTIMATE=-1
WQ Max Comp Step=1HOUR
WQ Output Interval=15MIN
WQ Output Selected Increments= 0
WQ Output face flow=0
WQ Output face velocity=0
WQ Output face area=0
WQ Output face dispersion=0
WQ Output cell volume=0
WQ Output cell surface area=0
WQ Output cell continuity=0
WQ Output cumulative cell continuity=0
WQ Output face conc=0
WQ Output face dconc_dx=0
WQ Output face courant=0
WQ Output face peclet=0
WQ Output face adv mass=0
WQ Output face disp mass=0
WQ Output cell mass=0
WQ Output cell source sink temp=0
WQ Output cell source sink nsm=0
WQ Output MaxMinRange=-1
WQ Daily Max Min Mean=-1
WQ Daily Range=0
WQ Daily Time=0
WQ Create Restart=0
WQ Fixed Restart=0
WQ System Summary=0
WQ Use Fixed Temperature=0
Sorting and Armoring Iterations= 10
XS Update Threshold= 0.02
Hydraulics Update Threshold= 0.02
Energy Slope Method= 1
Volume Change Method= 0
XS Weighting Method= 0
Number of US Weighted Cross Sections= 1
Number of DS Weighted Cross Sections= 1
Upstream XS Weight=0.25
Main XS Weight=0.5
Downstream XS Weight=0.25
Number of DS XS's Weighted with US Boundary= 1
Upstream Boundary Weight= 1
Weight of XSs Associated with US Boundary= 0
Number of US XS's Weighted with DS Boundary= 1
Downstream Boundary Weight= 0.5
Weight of XSs Associated with DS Boundary= 0.5
Sediment Output Level= 4
Mass or Volume Output= 0
Output Increment Type= 1
Profile and TS Output Increment= 10
XS Output Flag= 0
XS Output Increment= 10
Disregard all LS=0
Disregard all Conn=0
Disregard all Breaches=0
Disregard all Pumps=0

--- UNT 007 IN RACR.f01 (steady flow) ---

Flow Title=Multiple
Program Version=4.10
Number of Profiles= 7
Profile Names=10-year,25-year,50-year,1pct_min,100-year,1pct_plu,500-year
River Rch & RM=UNT 007 IN RACR,Reach-1         ,2571
     261     369     461     424     573     775     900
Boundary for River Rch & Prof#=UNT 007 IN RACR,Reach-1         , 1
Up Type= 0
Dn Type= 3
Dn Slope=0.005
Boundary for River Rch & Prof#=UNT 007 IN RACR,Reach-1         , 2
Up Type= 0
Dn Type= 3
Dn Slope=0.005
Boundary for River Rch & Prof#=UNT 007 IN RACR,Reach-1         , 3
Up Type= 0
Dn Type= 3
Dn Slope=0.005
Boundary for River Rch & Prof#=UNT 007 IN RACR,Reach-1         , 4
Up Type= 0
Dn Type= 3
Dn Slope=0.005
Boundary for River Rch & Prof#=UNT 007 IN RACR,Reach-1         , 5
Up Type= 0
Dn Type= 3
Dn Slope=0.005
Boundary for River Rch & Prof#=UNT 007 IN RACR,Reach-1         , 6
Up Type= 0
Dn Type= 3
Dn Slope=0.005
Boundary for River Rch & Prof#=UNT 007 IN RACR,Reach-1         , 7
Up Type= 0
Dn Type= 3
Dn Slope=0.005
DSS Import GetInterval= 0
DSS Import GetPeak= 0
DSS Import FillOption= 0

--- UNT 007 IN RACR.g01 (geometry) ---

Geom Title=Existing Conditions
Program Version=4.10

River Reach=UNT 007 IN RACR ,Reach-1
Reach XY= 30
      2193915.35     13229005.72      2193935.09     13229099.51
      2193993.62       13229261.      2193996.44     13229299.78
      2193987.28     13229334.34      2193997.85     13229363.25
      2194037.19     13229417.81      2194050.21     13229466.64
       2194087.1      13229498.1      2194115.31     13229536.08
      2194176.08     13229557.78      2194245.52      13229556.7
      2194303.26     13229617.86       2194768.3     13229607.68
      2195192.15     13229331.62      2195186.94     13229265.64
      2195292.84     13229204.88      2195443.88     13229201.41
      2195592.72     13229316.85      2195626.78     13229281.72
      2195647.01     13229277.93       2195722.8     13229332.73
      2195837.72     13229317.32      2195896.85     13229338.97
      2195947.99      13229277.3      2195989.53     13229263.83
      2196040.47     13229286.66      2196065.91     13229283.12
      2196112.81     13229257.79      2196197.72     13229266.85

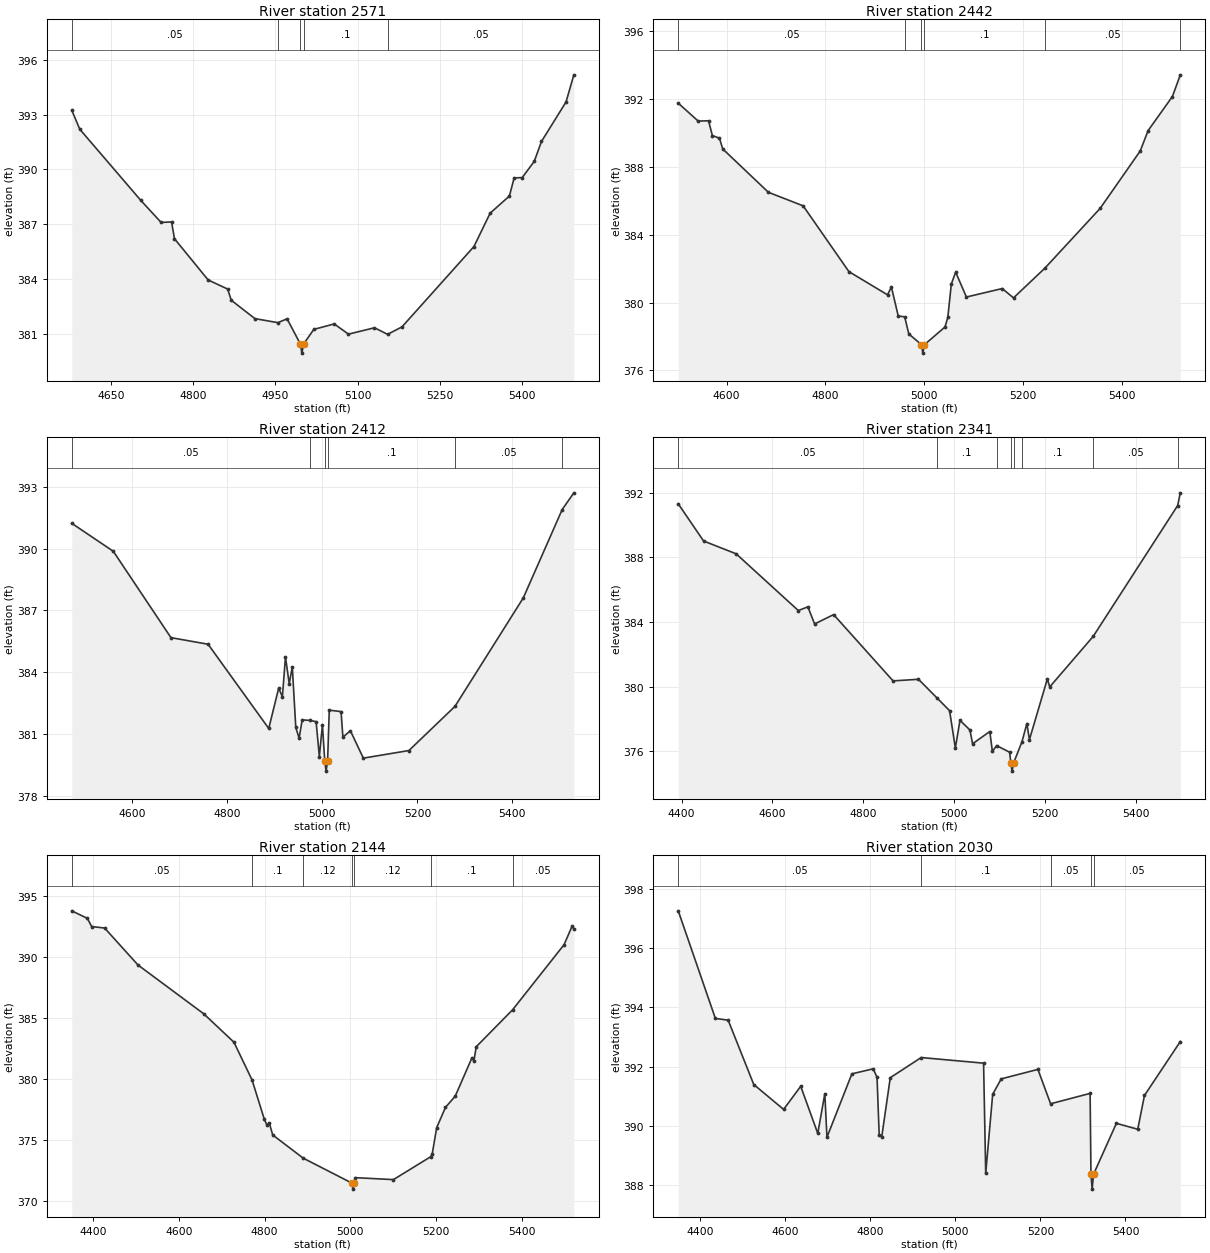
Type RM Length L Ch R = 1 ,2571    ,129,129,129
BEGIN DESCRIPTION:
UNT 007 IN RACR 5.0
END DESCRIPTION:
XS GIS Cut Line= 4
      2193644.02     13229574.45      2193912.06     13229478.31
      2194103.03      13229367.2       2194318.3     13229016.51
#Sta/Elev= 30
  4577.9  393.24  4592.5   392.2    4704   388.3  4741.2  387.09  4760.2  387.12
  4765.5   386.2    4827  383.94  4862.7  383.44  4869.2  382.83  4912.5  381.82
  4954.5   381.6  4971.2  381.81  4995.5  380.43  4998.3  379.93  5001.5  380.43
    5020  381.23  5057.3  381.53  5083.4  380.97  5130.9  381.32  5154.9  380.96
  5181.2  381.37  5312.6  385.77  5342.2   387.6  5377.4  388.54    5386  389.53
  5400.8  389.55  5422.8  390.44    5436  391.53  5480.8  393.69  5495.1  395.18
#Mann= 5 ,-1 , 0
  4577.9     .05       0  4954.5      .1       0  4995.5     .07       0
  5001.5      .1       0  5154.9     .05       0
Bank Sta=4995.5,5001.5
XS Rating Curve= 0 ,0
Exp/Cntr=0.3,0.1

Type RM Length L Ch R = 1 ,2442    ,30,30,30
BEGIN DESCRIPTION:
Mapping XS 798e460a
END DESCRIPTION:
XS GIS Cut Line= 3
      2193713.13     13229828.86      2194103.03     13229509.56
      2194352.82     13229062.01
#Sta/Elev= 30
    4502  391.77  4542.4  390.71  4563.3  390.73  4571.1  389.86  4585.5   389.7
    4592  389.07  4684.5  386.51  4754.9  385.71  4847.5  381.83  4925.7  380.46
  4933.6  380.92  4947.4  379.21  4960.5  379.16  4968.8  378.15  4994.5  377.52
  4997.2  377.02  5000.5  377.52    5042  378.56  5047.8  379.13  5054.9   381.1
  5063.7   381.8  5085.4  380.33  5157.9  380.83  5180.8  380.28  5244.2  382.03
  5356.2  385.56  5437.4  388.95  5453.3  390.15  5502.5  392.16  5518.5  393.44
#Mann= 6 ,-1 , 0
    4502     .05       0  4960.5      .1       0  4994.5     .07       0
  5000.5      .1       0  5244.2     .05       0  5518.5      .1       0
Bank Sta=4994.5,5000.5
XS Rating Curve= 0 ,0
Exp/Cntr=0.3,0.1

Type RM Length L Ch R = 1 ,2412    ,382,382,382
BEGIN DESCRIPTION:
Mapping XS 929afdce
END DESCRIPTION:
XS GIS Cut Line= 4
      2193713.11     13229875.75      2194096.08     13229561.64
      2194141.22     13229506.09      2194387.74     13229082.49
#Sta/Elev= 30
  4472.4  391.23  4559.9  389.87  4681.2  385.68  4759.4  385.36  4887.1  381.27
    4908  383.23  4915.8  382.81  4922.3  384.74  4930.2  383.45  4936.7  384.26
    4944  381.32    4951   380.8  4957.5  381.69  4974.7  381.66  4986.8   381.6
  4993.6  379.91  5000.1  381.44    5005   379.7  5007.8   379.2    5011   379.7
  5014.5  382.16  5039.3  382.09  5043.2  380.85    5059  381.16  5086.2  379.83
  5182.2   380.2    5279  382.34    5423  387.61  5504.9   391.9  5529.4  392.71
#Mann= 6 ,-1 , 0
  4472.4     .05       0  4974.7      .1       0    5005     .07       0
    5011      .1       0    5279     .05       0  5504.9      .1       0
Bank Sta=5005,5011
XS Rating Curve= 0 ,0
Exp/Cntr=0.3,0.1

Type RM Length L Ch R = 1 ,2341    ,71,71,71
BEGIN DESCRIPTION:
Mapping XS 4eb72633
END DESCRIPTION:
XS GIS Cut Line= 4
      2193718.33     13229934.77      2194137.75      13229641.5
      2194273.17     13229394.97      2194401.26     13229111.09
#Sta/Elev= 30
  4392.7  391.31  4448.5  389.01    4520  388.22  4656.9  384.71  4677.9  384.94
  4692.7  383.88  4734.5  384.46  4865.3  380.36  4921.2  380.46  4961.4  379.32
  4989.6  378.52  5002.3  376.21  5012.5  377.92  5034.5  377.32  5040.2  376.47
  5078.1  377.23  5083.8     376    5093  376.36  5121.7  375.95  5124.4  375.28
  5127.1  374.78  5130.4  375.28  5148.9   376.6  5159.6  377.72  5165.3  376.73
  5204.6  380.47    5210  379.99  5305.5  383.11  5491.3   391.2  5497.2  391.99
#Mann= 8 ,-1 , 0
  4392.7     .05       0  4961.4      .1       0    5093     .12       0
  5124.4     .07       0  5130.4     .12       0  5148.9      .1       0
  5305.5     .05       0  5491.3      .1       0
Bank Sta=5124.4,5130.4
XS Rating Curve= 0 ,0
Exp/Cntr=0.3,0.1

Type RM Length L Ch R = 1 ,2144    ,115,115,115
BEGIN DESCRIPTION:
Mapping XS c0eb2009
END DESCRIPTION:
XS GIS Cut Line= 3
      2194287.05     13230263.04      2194370.39     13229433.17
      2194443.01     13229104.65
#Sta/Elev= 30
  4350.5  393.76  4386.9  393.14  4396.9  392.47  4427.1  392.35  4504.9  389.32
  4658.2  385.32  4728.6  382.99  4770.8   379.9  4798.9  376.73  4805.7  376.17
  4810.8  376.39    4819  375.39    4890  373.49  5003.3  371.45  5006.1  370.95
  5009.3  371.45  5011.4  371.89  5100.4  371.73    5187   373.6  5190.6  373.79
  5201.3  375.99  5221.7  377.65  5244.5  378.57    5283  381.68  5288.2  381.49
  5293.4  382.62    5378  385.64  5498.3  390.99  5516.6  392.48    5521  392.31
#Mann= 7 ,-1 , 0
  4350.5     .05       0  4770.8      .1       0    4890     .12       0
  5003.3     .07       0  5009.3     .12       0    5187      .1       0
    5378     .05       0
Bank Sta=5003.3,5009.3
XS Rating Curve= 0 ,0
Exp/Cntr=0.3,0.1

Type RM Length L Ch R = 1 ,2030    ,90,90,90
BEGIN DESCRIPTION:
Mapping XS 2fd3edea
END DESCRIPTION:
XS GIS Cut Line= 2
      2194415.04     13230263.89       2194509.4     13229087.06
#Sta/Elev= 30
  4348.3  397.26  4435.6  393.63  4465.7  393.57  4525.9   391.4  4596.1  390.56
  4636.3  391.34  4676.4  389.75    4693  391.09    4698  389.62  4756.6  391.76
  4806.8  391.93  4815.8  391.64  4820.8  389.71  4826.9  389.64  4846.9  391.63
  4919.6  392.31  5066.3  392.12  5071.3   388.4  5087.7  391.07  5107.8  391.59
    5194  391.91  5223.9  390.75  5316.8   391.1  5318.8  388.37  5321.6  387.87
  5324.8  388.37  5378.6  390.09  5428.8  389.89  5444.6  391.03  5528.9  392.85
#Mann= 5 ,-1 , 0
  4348.3     .05       0  4919.6      .1       0  5223.9     .05       0
  5318.8     .07       0  5324.8     .05       0
Bank Sta=5318.8,5324.8
XS Rating Curve= 0 ,0
Exp/Cntr=0.3,0.1

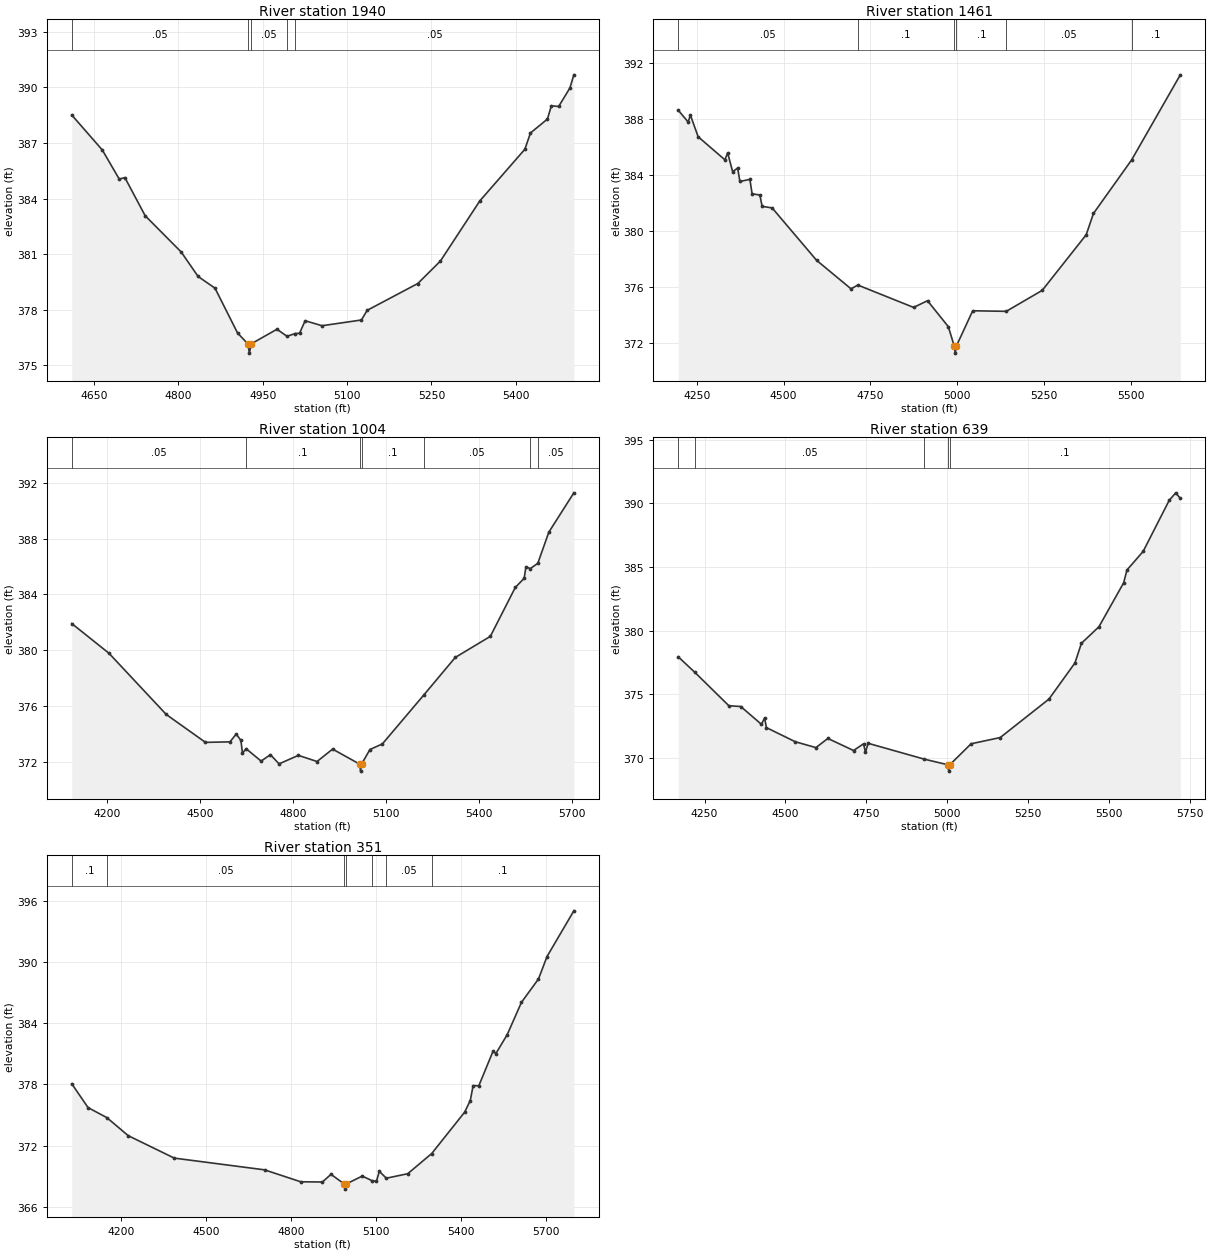
Type RM Length L Ch R = 1 ,1940    ,479,479,479
BEGIN DESCRIPTION:
UNT 007 IN RACR 4.0
END DESCRIPTION:
XS GIS Cut Line= 2
      2194535.45     13230001.11      2194584.81     13229109.88
#Sta/Elev= 30
  4610.6  388.51  4664.9  386.62    4695  385.05    4705  385.13  4741.1  383.07
  4805.2  381.11  4835.2  379.79  4865.2  379.16  4905.3  376.74  4923.6  376.15
  4926.4  375.65  4929.6  376.15  4975.4  376.94  4993.2  376.56    5008  376.71
  5015.5  376.72  5025.5   377.4  5055.5  377.13  5125.6  377.44  5135.7  377.96
  5225.8  379.41  5265.9  380.62    5336  383.87  5416.1  386.66  5426.1  387.54
  5456.2  388.29  5463.3  389.01  5476.2  388.97  5496.2  389.97  5503.2  390.68
#Mann= 5 ,-1 , 0
  4610.6     .05       0  4923.6     .07       0  4929.6     .05       0
  4993.2      .1       0    5008     .05       0
Bank Sta=4923.6,4929.6
XS Rating Curve= 0 ,0
Exp/Cntr=0.3,0.1

Type RM Length L Ch R = 1 ,1461    ,457,457,457
BEGIN DESCRIPTION:
UNT 007 IN RACR 3.0
END DESCRIPTION:
XS GIS Cut Line= 4
      2194742.67     13230171.53      2195005.47      13229844.8
      2194984.16     13229187.76      2194749.78     13228903.66
#Sta/Elev= 30
    4197  388.64  4225.6  387.79    4232  388.29  4254.3  386.74  4331.3  385.09
  4339.2  385.59  4353.6  384.24    4368   384.5  4374.4  383.54  4403.2  383.69
  4409.6  382.66    4432  382.57  4438.4  381.76  4467.2  381.65  4595.2   377.9
  4694.3  375.86  4713.9  376.13  4874.4  374.53  4914.4  375.01  4974.4  373.15
  4991.4  371.76  4994.2  371.26  4997.4  371.76  5044.5  374.29  5141.1  374.25
  5244.6  375.75  5371.2  379.73    5392  381.25  5501.8  385.08    5642  391.17
#Mann= 6 ,-1 , 0
    4197     .05       0  4713.9      .1       0  4991.4     .07       0
  4997.4      .1       0  5141.1     .05       0  5501.8      .1       0
Bank Sta=4991.4,4997.4
XS Rating Curve= 0 ,0
Exp/Cntr=0.3,0.1

Type RM Length L Ch R = 1 ,1004    ,365,365,365
BEGIN DESCRIPTION:
UNT 007 IN RACR 2.0
END DESCRIPTION:
XS GIS Cut Line= 5
       2195158.2     13230068.55      2195360.63     13229670.77
      2195307.36     13229003.08      2195119.12     13228658.57
      2195033.86     13228587.52
#Sta/Elev= 30
  4085.6  381.91  4205.6  379.78  4390.5  375.39    4517  373.39    4596  373.43
  4616.1  373.99  4631.3  373.53  4636.3  372.61  4647.9  372.94  4696.4  372.05
  4726.5  372.51  4754.3  371.85  4816.7  372.46  4876.9  372.02  4927.1  372.91
  5014.4  371.83  5017.1  371.33  5020.4  371.83  5047.5  372.88  5087.6  373.28
  5222.5  376.82  5322.8  379.48  5435.9  380.99  5516.5   384.5    5545  385.15
  5550.7  385.97  5565.1  385.85  5589.1  386.23  5624.6  388.46  5705.3  391.28
#Mann= 7 ,-1 , 0
  4085.6     .05       0  4647.9      .1       0  5014.4     .07       0
  5020.4      .1       0  5222.5     .05       0  5565.1      .1       0
  5589.1     .05       0
Bank Sta=5014.4,5020.4
XS Rating Curve= 0 ,0
Exp/Cntr=0.3,0.1

Type RM Length L Ch R = 1 ,639     ,288,288,288
BEGIN DESCRIPTION:
Mapping XS 3bf920b0
END DESCRIPTION:
XS GIS Cut Line= 4
      2195321.56     13230025.95        2195627.     13229525.16
      2195637.66       13229067.      2195587.94     13228562.72
#Sta/Elev= 30
  4168.8  377.94  4220.4  376.71  4325.3  374.09    4362  374.03    4426  372.63
  4435.6  373.13  4441.4  372.37  4530.5  371.26  4594.4   370.8  4631.2  371.52
  4710.6  370.57  4741.5   371.1  4747.4  370.42  4755.4  371.14  4929.4  369.89
  5002.1  369.45  5004.8  368.95  5008.1  369.45  5073.8   371.1  5163.8  371.59
  5314.3  374.61  5394.7  377.45  5414.8     379  5468.9   380.3  5545.4  383.76
  5555.5  384.76  5605.7  386.23  5686.1  390.24  5706.2  390.83  5720.4  390.39
#Mann= 5 ,-1 , 0
  4168.8      .1       0  4220.4     .05       0  4929.4      .1       0
  5002.1     .07       0  5008.1      .1       0
Bank Sta=5002.1,5008.1
XS Rating Curve= 0 ,0
Exp/Cntr=0.3,0.1

Type RM Length L Ch R = 1 ,351     ,0,0,0
BEGIN DESCRIPTION:
UNT 007 IN RACR 1.0
END DESCRIPTION:
XS GIS Cut Line= 3
      2195346.95     13230087.62      2195906.82     13229497.37
      2195837.37     13228542.53
#Sta/Elev= 30
  4026.9  378.07  4084.4  375.73  4150.7  374.75    4226  372.98  4388.6  370.78
    4707  369.63  4834.4  368.46  4911.1  368.44  4941.2  369.19  4988.4  368.24
  4991.1  367.74  4994.4  368.24  5051.5  369.02  5087.3  368.55  5101.6  368.51
  5111.7  369.49  5136.2  368.81  5211.9  369.25  5296.5  371.23  5412.5  375.28
  5432.5  376.42  5442.5  377.88  5462.6  377.87  5512.7  381.25  5522.8  381.03
  5562.9  382.89    5613  386.05  5673.1  388.34  5703.2  390.54  5797.8  395.02
#Mann= 7 ,-1 , 0
  4026.9      .1       0  4150.7     .05       0  4988.4     .03       0
  4994.4     .05       0  5087.3      .1       0  5136.2     .05       0
  5296.5      .1       0
Bank Sta=4988.4,4994.4
XS Rating Curve= 0 ,0
Exp/Cntr=0.3,0.1
Stream Node=UNT 007 IN RACR ,Reach-1         , 0 , 0 ,Upstream end
Stream Node=UNT 007 IN RACR ,Reach-1         , 0 , 1 ,Downstream end

Chan Stop Cuts=-1
Use User Specified Reach Order=0
Composite Channel Slope=5