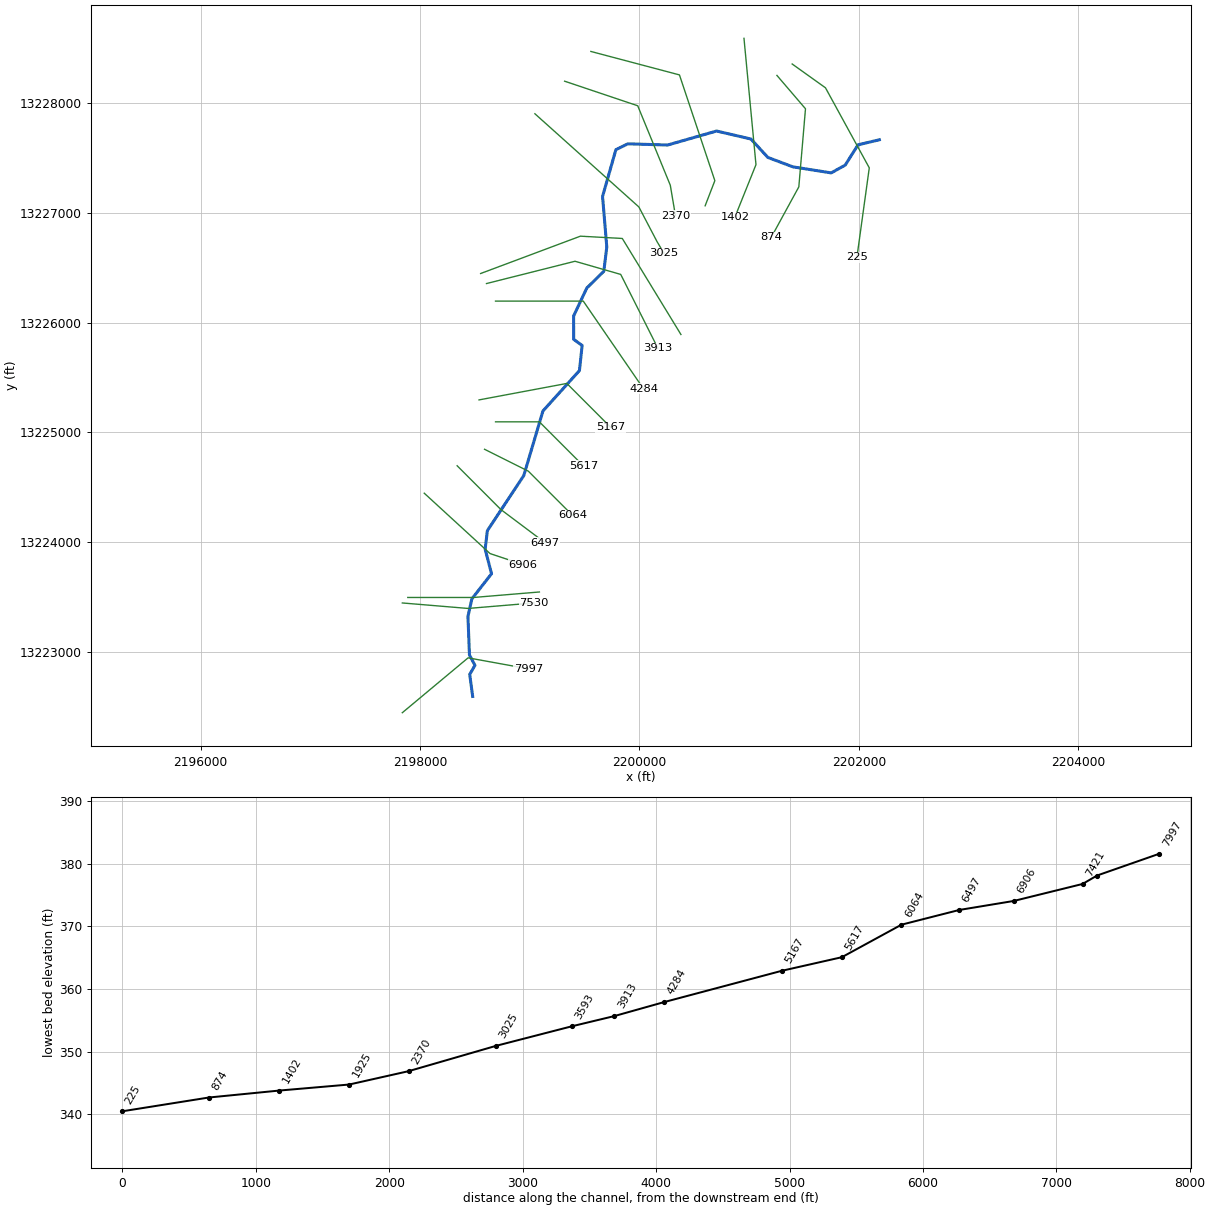
--- UNT 008 IN RACR.prj (project) ---

Proj Title=UNT 008 IN RACR Base Level Engineering
Current Plan=p01
Default Exp/Contr=0.3,0.1
English Units
Geom File=g01
Flow File=f01
Plan File=p01
BEGIN DESCRIPTION:
UNT 008 IN RACR
END DESCRIPTION:

--- UNT 008 IN RACR.p01 (plan) ---

Plan Title=Multiple Run
Short Identifier=Multiple
Geom File=g01
Flow File=f01
Subcritical Flow
K Sum by GR= 0
Std Step Tol= 0.01
Critical Tol= 0.01
Num of Std Step Trials= 20
Max Error Tol= 0.3
Flow Tol Ratio= 0.001
Split Flow NTrial= 30
Split Flow Tol= 0.02
Split Flow Ratio= 0.02
Log Output Level= 0
Friction Slope Method= 1
Unsteady Friction Slope Method= 2
Unsteady Bridges Friction Slope Method= 1
Parabolic Critical Depth
Global Vel Dist=  1 , 1 , 1
Global Log Level= 0
CheckData=True
Encroach Param= -1, 0, 0, 0
BEGIN DESCRIPTION:
Multiple Run
END DESCRIPTION:

--- UNT 008 IN RACR.f01 (steady flow) ---

Flow Title=Multiple
Number of Profiles=7
Profile Names=10-year,25-year,50-year,1pct_min,100-year,1pct_plu,500-year
River Rch & RM= UNT 008 IN RACR,Reach-1,7997
     190     263     322     292     395     534     599
River Rch & RM= UNT 008 IN RACR,Reach-1,6497
     311     440     549     503     680     920    1063
Boundary for River Rch & Prof#=UNT 008 IN RACR,Reach-1,1
Up Type=0
Dn Type=3
Dn Slope=0.005
Boundary for River Rch & Prof#=UNT 008 IN RACR,Reach-1,2
Up Type=0
Dn Type=3
Dn Slope=0.005
Boundary for River Rch & Prof#=UNT 008 IN RACR,Reach-1,3
Up Type=0
Dn Type=3
Dn Slope=0.005
Boundary for River Rch & Prof#=UNT 008 IN RACR,Reach-1,4
Up Type=0
Dn Type=3
Dn Slope=0.005
Boundary for River Rch & Prof#=UNT 008 IN RACR,Reach-1,5
Up Type=0
Dn Type=3
Dn Slope=0.005
Boundary for River Rch & Prof#=UNT 008 IN RACR,Reach-1,6
Up Type=0
Dn Type=3
Dn Slope=0.005
Boundary for River Rch & Prof#=UNT 008 IN RACR,Reach-1,7
Up Type=0
Dn Type=3
Dn Slope=0.005

--- UNT 008 IN RACR.g01 (geometry) ---

Geom Title=Existing Conditions

River Reach=UNT 008 IN RACR,Reach-1
Reach XY= 30
      2198479.32     13222595.58      2198452.23     13222795.58
      2198500.15     13222878.91      2198449.95     13222973.31
      2198436.26     13223324.05      2198472.08     13223484.29
      2198651.21     13223713.18      2198593.00     13223937.47
      2198613.60     13224106.19      2198945.29     13224607.38
      2199119.94     13225195.93      2199452.62     13225563.65
      2199477.39     13225792.54      2199400.14     13225848.67
      2199399.67     13226061.37      2199519.87     13226316.17
      2199674.89     13226468.04      2199702.12     13226690.11
      2199663.43     13227149.64      2199784.91     13227576.22
      2199893.83     13227629.86      2200256.97     13227618.90
      2200703.20     13227746.36      2201016.38     13227673.59
      2201170.86     13227505.70      2201398.99     13227419.95
      2201748.07     13227365.02      2201875.84     13227435.86
      2201992.97     13227620.72      2202187.72     13227666.85

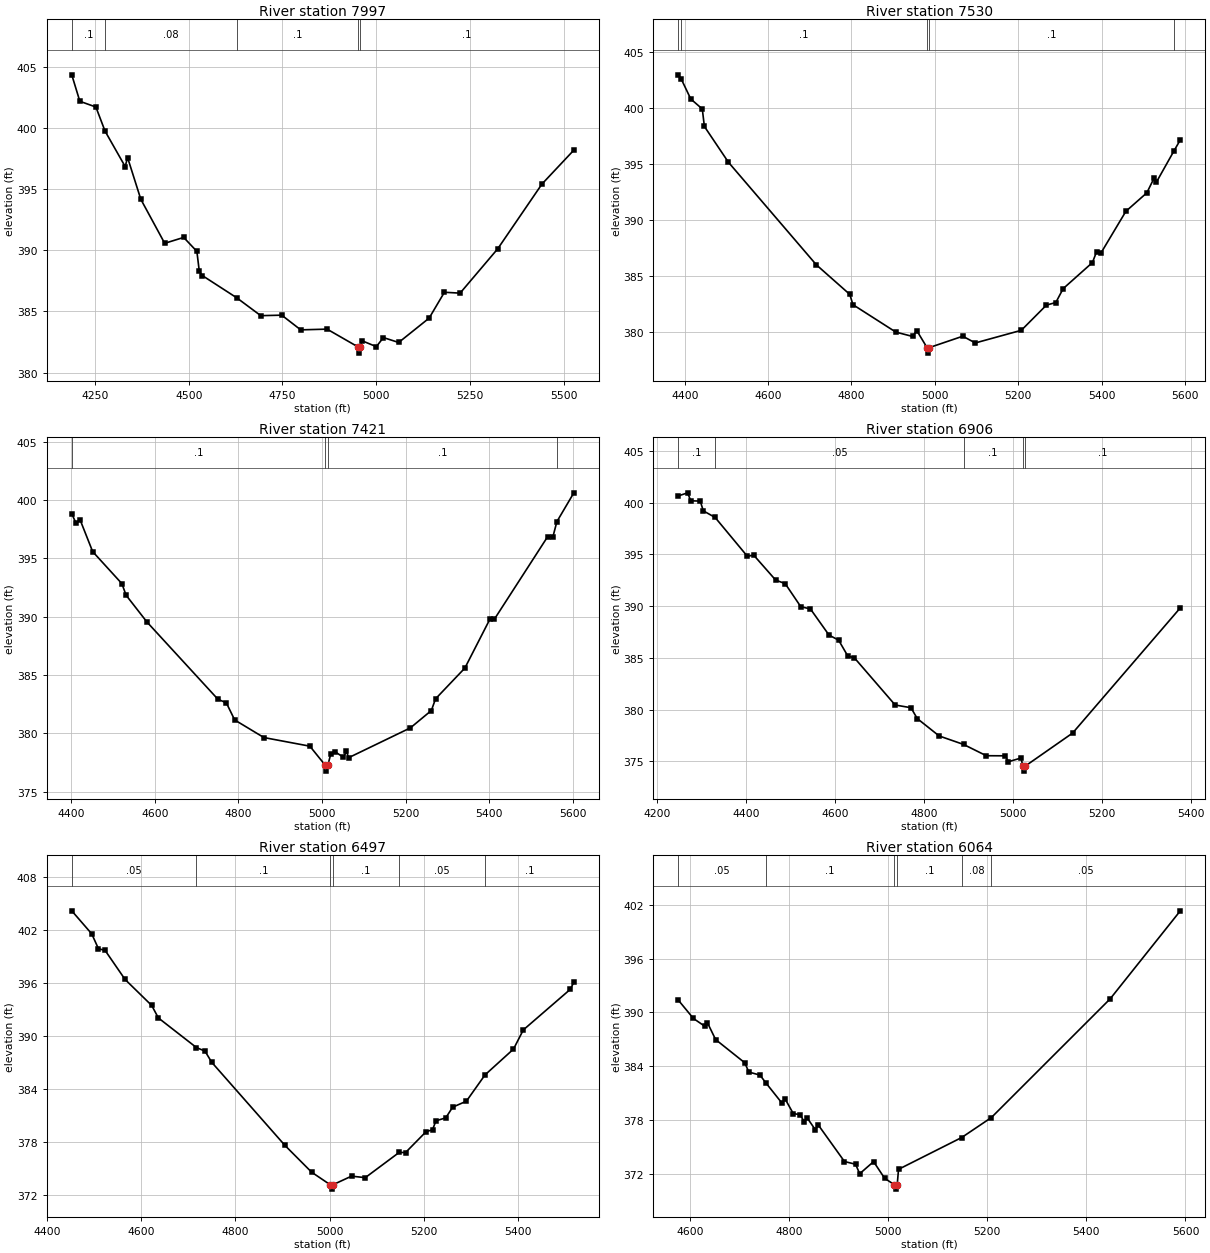
Type RM Length L Ch R = 1,7997,467,467,467
BEGIN DESCRIPTION:
UNT 008 IN RACR 15.0
END DESCRIPTION:
XS GIS Cut Line= 3
      2197837.73     13222446.86      2198437.72     13222946.85
      2198987.69     13222846.86
#Sta/Elev= 30
  4187.6  404.32  4209.1  402.16  4252.0  401.69  4276.3  399.73  4330.1  396.83
  4336.6  397.56  4371.8  394.16  4435.6  390.56  4486.3  391.04  4521.5  389.90
  4528.0  388.26  4535.8  387.93  4628.3  386.10  4692.0  384.65  4748.0  384.69
  4798.7  383.49  4869.0  383.55  4952.0  382.09  4954.7  381.59  4958.0  382.09
  4961.5  382.61  5000.4  382.12  5019.4  382.86  5060.1  382.46  5141.4  384.45
  5182.1  386.56  5224.0  386.49  5324.4  390.11  5442.5  395.40  5527.6  398.17
#Mann=5,-1,0
  4187.6     0.1       0  4276.3    0.08       0  4628.3     0.1       0
  4952.0    0.07       0  4958.0     0.1       0
Bank Sta=4952,4958
Exp/Cntr=0.3,0.1

Type RM Length L Ch R = 1,7530,109,109,109
BEGIN DESCRIPTION:
UNT 008 IN RACR 14.0
END DESCRIPTION:
XS GIS Cut Line= 3
      2197837.71     13223446.86      2198437.72     13223396.85
      2199037.75     13223446.86
#Sta/Elev= 30
  4384.5  402.97  4391.9  402.58  4414.6  400.81  4442.2  399.92  4447.2  398.36
  4504.9  395.16  4715.7  386.00  4795.9  383.36  4803.5  382.44  4906.3  379.99
  4946.5  379.60  4956.5  380.13  4981.1  378.61  4983.8  378.11  4987.1  378.61
  5066.9  379.62  5097.0  379.02  5207.4  380.15  5267.6  382.40  5290.1  382.63
  5307.7  383.87  5377.9  386.20  5388.0  387.18  5398.0  387.03  5458.2  390.78
  5508.4  392.43  5526.0  393.76  5531.0  393.36  5573.1  396.15  5588.7  397.16
#Mann=5,-1,0
  4384.5    0.08       0  4391.9     0.1       0  4981.1    0.07       0
  4987.1     0.1       0  5573.1    0.05       0
Bank Sta=4981.1,4987.1
Exp/Cntr=0.3,0.1

Type RM Length L Ch R = 1,7421,515,515,515
BEGIN DESCRIPTION:
UNT 008 IN RACR 13.0
END DESCRIPTION:
XS GIS Cut Line= 3
      2197887.75     13223496.85      2198487.72     13223496.85
      2199087.67     13223546.85
#Sta/Elev= 30
  4401.0  398.84  4411.0  398.03  4421.0  398.31  4451.0  395.59  4521.0  392.84
  4531.0  391.85  4581.0  389.55  4751.0  382.92  4771.0  382.62  4791.0  381.15
  4861.0  379.64  4971.0  378.90  5008.0  377.26  5010.8  376.76  5014.0  377.26
  5021.0  378.22  5031.1  378.43  5051.1  377.95  5058.7  378.45  5063.7  377.91
  5211.7  380.47  5261.9  381.96  5271.9  382.96  5342.1  385.60  5402.4  389.82
  5412.4  389.77  5540.3  396.87  5552.9  396.86  5562.4  398.16  5603.0  400.63
#Mann=4,-1,0
  4401.0     0.1       0  5008.0    0.07       0  5014.0     0.1       0
  5562.4    0.05       0
Bank Sta=5008,5014
Exp/Cntr=0.3,0.1

Type RM Length L Ch R = 1,6906,409,409,409
BEGIN DESCRIPTION:
UNT 008 IN RACR 12.0
END DESCRIPTION:
XS GIS Cut Line= 3
      2198037.75     13224446.83      2198637.72     13223896.85
      2198937.69     13223796.87
#Sta/Elev= 30
  4246.7  400.65  4267.9  400.95  4274.7  400.18  4296.3  400.15  4303.1  399.21
  4329.7  398.57  4402.4  394.81  4416.5  394.93  4465.9  392.52  4487.5  392.17
  4522.6  389.94  4544.2  389.73  4586.1  387.20  4607.7  386.71  4628.7  385.15
  4642.8  385.02  4735.0  380.44  4770.5  380.18  4784.7  379.13  4834.0  377.45
  4888.9  376.63  4940.1  375.54  4982.6  375.53  4990.0  374.96  5018.4  375.32
  5022.2  374.55  5024.9  374.05  5028.2  374.55  5134.4  377.73  5376.8  389.83
#Mann=5,-1,0
  4246.7     0.1       0  4329.7    0.05       0  4888.9     0.1       0
  5022.2    0.07       0  5028.2     0.1       0
Bank Sta=5022.2,5028.2
Exp/Cntr=0.3,0.1

Type RM Length L Ch R = 1,6497,433,433,433
BEGIN DESCRIPTION:
UNT 008 IN RACR 11.0
END DESCRIPTION:
XS GIS Cut Line= 3
      2198337.72     13224696.85      2198737.72     13224296.85
      2199137.73     13223996.84
#Sta/Elev= 30
  4452.8  404.13  4495.2  401.52  4509.4  399.84  4523.5  399.65  4565.9  396.36
  4622.5  393.41  4636.6  392.00  4717.5  388.64  4735.6  388.24  4749.8  386.98
  4905.3  377.56  4961.9  374.53  5001.3  373.11  5004.1  372.61  5007.3  373.11
  5046.6  374.08  5075.8  373.91  5147.8  376.77  5161.2  376.75  5204.9  379.12
  5218.5  379.33  5225.8  380.35  5246.6  380.68  5261.2  381.89  5290.4  382.57
  5330.0  385.55  5390.4  388.47  5411.2  390.64  5511.2  395.25  5518.5  396.06
#Mann=6,-1,0
  4452.8    0.05       0  4717.5     0.1       0  5001.3    0.07       0
  5007.3     0.1       0  5147.8    0.05       0  5330.0     0.1       0
Bank Sta=5001.3,5007.3
Exp/Cntr=0.3,0.1

Type RM Length L Ch R = 1,6064,447,447,447
BEGIN DESCRIPTION:
UNT 008 IN RACR 10.0
END DESCRIPTION:
XS GIS Cut Line= 3
      2198587.74     13224846.85      2198987.72     13224646.85
      2199387.74     13224246.84
#Sta/Elev= 30
  4576.7  391.37  4607.4  389.31  4629.8  388.46  4635.4  388.86  4652.1  386.96
  4710.8  384.37  4719.2  383.33  4741.6  382.99  4753.7  382.11  4786.3  379.84
  4791.9  380.37  4808.7  378.70  4822.6  378.57  4831.0  377.76  4836.6  378.23
  4853.4  376.88  4859.0  377.44  4912.1  373.34  4934.4  373.04  4942.8  371.98
  4970.8  373.33  4993.1  371.47  5012.5  370.76  5015.3  370.26  5018.5  370.76
  5021.1  372.47  5148.5  376.02  5208.4  378.25  5448.2  391.51  5589.6  401.33
#Mann=6,-1,0
  4576.7    0.05       0  4753.7     0.1       0  5012.5    0.07       0
  5018.5     0.1       0  5148.5    0.08       0  5208.4    0.05       0
Bank Sta=5012.5,5018.5
Exp/Cntr=0.3,0.1

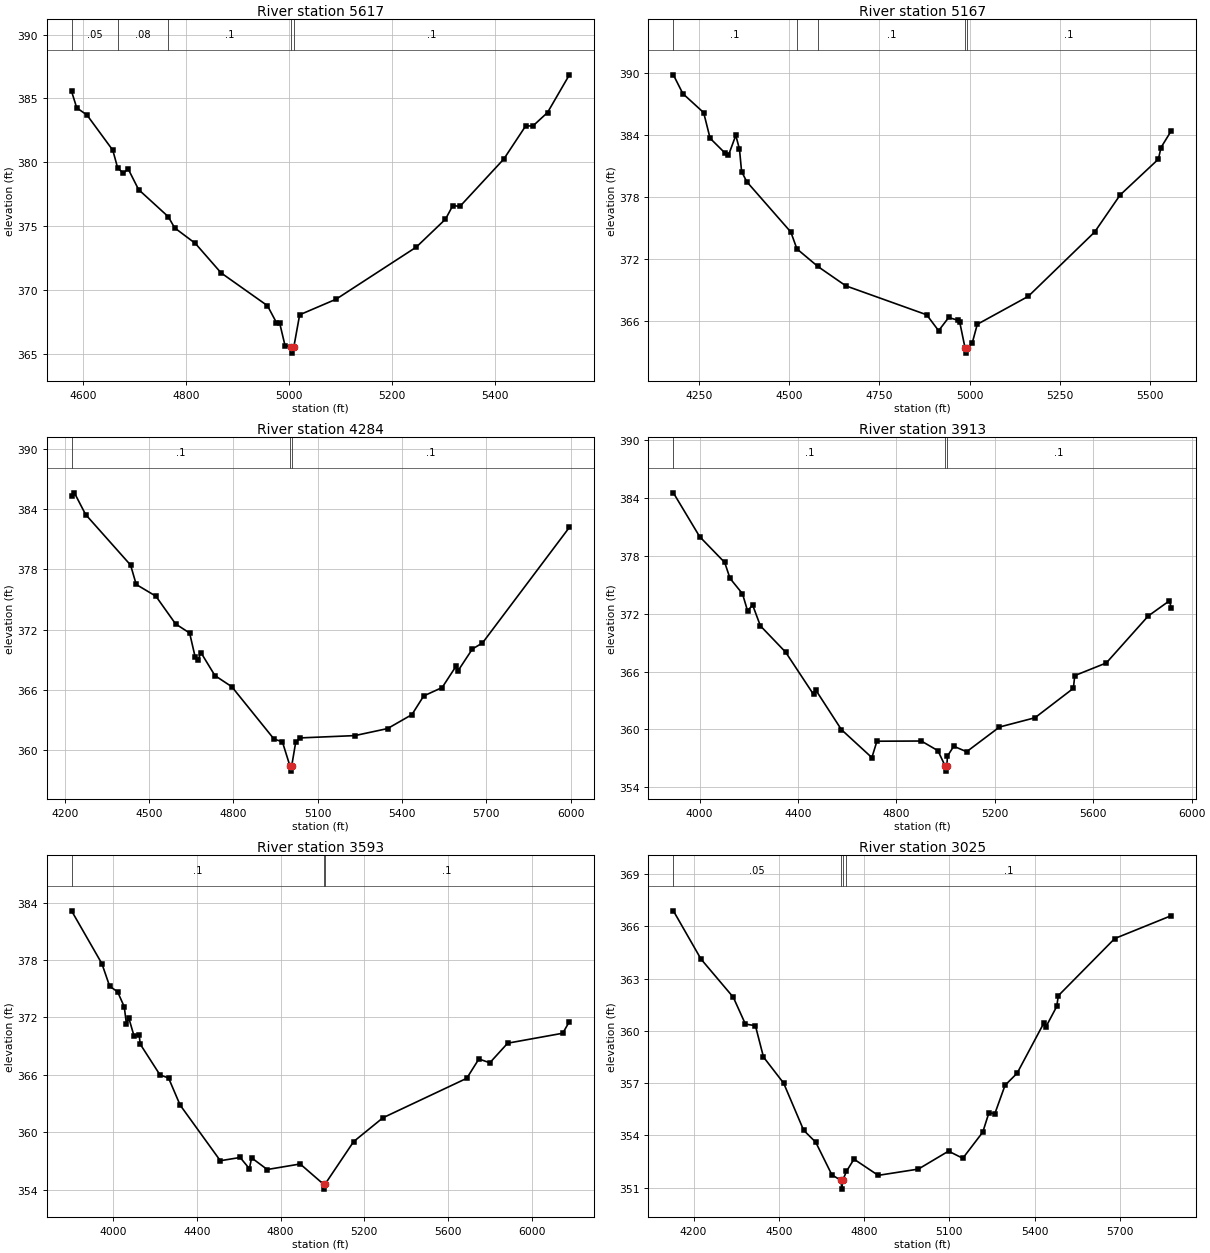
Type RM Length L Ch R = 1,5617,450,450,450
BEGIN DESCRIPTION:
UNT 008 IN RACR 9.0
END DESCRIPTION:
XS GIS Cut Line= 3
      2198687.76     13225096.85      2199087.72     13225096.85
      2199487.69     13224696.89
#Sta/Elev= 30
  4578.0  385.56  4588.0  384.27  4608.0  383.70  4658.0  380.95  4667.3  379.58
  4678.0  379.16  4688.0  379.47  4708.0  377.87  4765.5  375.75  4778.0  374.87
  4818.0  373.66  4868.0  371.35  4958.0  368.78  4975.5  367.45  4981.5  367.45
  4992.1  365.65  5003.2  365.57  5006.0  365.07  5009.2  365.57  5020.4  368.07
  5091.1  369.29  5246.7  373.37  5303.2  375.55  5317.4  376.61  5331.5  376.56
  5416.4  380.26  5458.8  382.85  5472.9  382.85  5501.2  383.90  5543.6  386.85
#Mann=5,-1,0
  4578.0    0.05       0  4667.3    0.08       0  4765.5     0.1       0
  5003.2    0.07       0  5009.2     0.1       0
Bank Sta=5003.2,5009.2
Exp/Cntr=0.3,0.1

Type RM Length L Ch R = 1,5167,883,883,883
BEGIN DESCRIPTION:
UNT 008 IN RACR 8.0
END DESCRIPTION:
XS GIS Cut Line= 3
      2198537.68     13225296.85      2199337.72     13225446.85
      2199737.75     13225046.83
#Sta/Elev= 30
  4178.9  389.84  4205.2  388.02  4262.9  386.18  4280.7  383.70  4321.4  382.29
  4331.6  382.05  4351.9  383.98  4362.1  382.65  4368.0  380.48  4382.4  379.49
  4504.5  374.62  4521.3  372.99  4579.3  371.29  4657.1  369.41  4881.0  366.61
  4914.0  365.07  4942.0  366.35  4966.6  366.09  4972.5  365.91  4987.3  363.40
  4990.1  362.90  4993.3  363.40  5007.0  363.85  5021.2  365.69  5162.6  368.40
  5346.4  374.62  5417.1  378.21  5523.2  381.68  5530.3  382.80  5558.6  384.41
#Mann=5,-1,0
  4178.9     0.1       0  4521.3    0.05       0  4579.3     0.1       0
  4987.3    0.07       0  4993.3     0.1       0
Bank Sta=4987.3,4993.3
Exp/Cntr=0.3,0.1

Type RM Length L Ch R = 1,4284,371,371,371
BEGIN DESCRIPTION:
UNT 008 IN RACR 7.0
END DESCRIPTION:
XS GIS Cut Line= 3
      2198687.68     13226196.85      2199487.72     13226196.85
      2200037.74     13225396.83
#Sta/Elev= 30
  4224.5  385.36  4234.5  385.63  4274.5  383.47  4434.5  378.43  4454.5  376.50
  4524.5  375.33  4594.5  372.57  4644.5  371.66  4664.5  369.23  4674.5  368.96
  4684.5  369.72  4734.5  367.42  4794.5  366.31  4944.5  361.10  4974.5  360.82
  5001.5  358.40  5004.3  357.90  5007.5  358.40  5022.0  360.81  5038.1  361.21
  5232.2  361.44  5348.6  362.14  5435.2  363.53  5477.1  365.39  5542.8  366.23
  5593.5  368.41  5599.6  367.91  5650.3  370.07  5686.2  370.67  5995.4  382.19
#Mann=3,-1,0
  4224.5     0.1       0  5001.5    0.07       0  5007.5     0.1       0
Bank Sta=5001.5,5007.5
Exp/Cntr=0.3,0.1

Type RM Length L Ch R = 1,3913,320,320,320
BEGIN DESCRIPTION:
UNT 008 IN RACR 6.0
END DESCRIPTION:
XS GIS Cut Line= 5
      2198605.25     13226356.74      2199412.55     13226559.87
      2199829.22     13226440.08      2200167.76     13225768.20
      2200162.61     13225768.20
#Sta/Elev= 30
  3893.3  384.52  4000.2  379.98  4102.1  377.30  4123.5  375.66  4174.3  374.06
  4194.9  372.29  4215.5  372.90  4246.9  370.74  4349.6  368.01  4463.0  363.63
  4473.3  364.04  4576.4  359.98  4700.2  357.08  4720.7  358.78  4901.2  358.80
  4968.6  357.80  4998.7  356.18  5001.4  355.68  5004.7  356.18  5007.5  357.24
  5032.9  358.26  5085.3  357.69  5218.9  360.25  5363.0  361.21  5519.2  364.26
  5524.8  365.58  5653.0  366.89  5823.6  371.76  5909.6  373.33  5916.8  372.62
#Mann=3,-1,0
  3893.3     0.1       0  4998.7    0.07       0  5004.7     0.1       0
Bank Sta=4998.7,5004.7
Exp/Cntr=0.3,0.1

Type RM Length L Ch R = 1,3593,568,568,568
BEGIN DESCRIPTION:
UNT 008 IN RACR 5.0
END DESCRIPTION:
XS GIS Cut Line= 4
      2198551.77     13226448.20      2199461.45     13226788.46
      2199843.40     13226767.62      2200378.12     13225892.62
#Sta/Elev= 30
  3801.1  383.14  3946.2  377.61  3983.2  375.25  4021.0  374.68  4053.0  373.10
  4063.4  371.29  4074.4  371.95  4099.0  370.10  4124.0  370.20  4129.3  369.20
  4223.8  365.98  4264.7  365.66  4319.9  362.83  4512.1  357.01  4606.8  357.35
  4650.9  356.18  4661.6  357.31  4736.3  356.09  4893.7  356.67  5006.0  354.54
  5008.7  354.04  5012.0  354.54  5149.2  359.01  5289.2  361.50  5689.8  365.63
  5747.8  367.65  5800.0  367.25  5885.3  369.30  6148.4  370.34  6180.3  371.56
#Mann=3,-1,0
  3801.1     0.1       0  5006.0    0.07       0  5012.0     0.1       0
Bank Sta=5006,5012
Exp/Cntr=0.3,0.1

Type RM Length L Ch R = 1,3025,655,655,655
BEGIN DESCRIPTION:
Mapping XS 152f1d86
END DESCRIPTION:
XS GIS Cut Line= 4
      2199046.75     13227903.61      2199994.66     13227054.66
      2200161.33     13226736.95      2200223.29     13226633.69
#Sta/Elev= 30
  4128.7  366.89  4226.0  364.12  4339.6  361.93  4382.2  360.39  4417.4  360.30
  4445.8  358.50  4516.8  357.00  4587.1  354.30  4629.7  353.61  4686.5  351.74
  4718.6  351.42  4721.4  350.92  4724.6  351.42  4737.7  351.94  4764.3  352.64
  4849.5  351.71  4990.8  352.07  5096.9  353.10  5147.1  352.69  5217.4  354.19
  5239.0  355.30  5259.9  355.25  5295.8  356.88  5338.2  357.57  5432.6  360.46
  5439.2  360.22  5477.6  361.40  5483.3  362.02  5681.8  365.30  5880.4  366.61
#Mann=4,-1,0
  4128.7    0.05       0  4718.6    0.07       0  4724.6    0.05       0
  4737.7     0.1       0
Bank Sta=4718.6,4724.6
Exp/Cntr=0.3,0.1

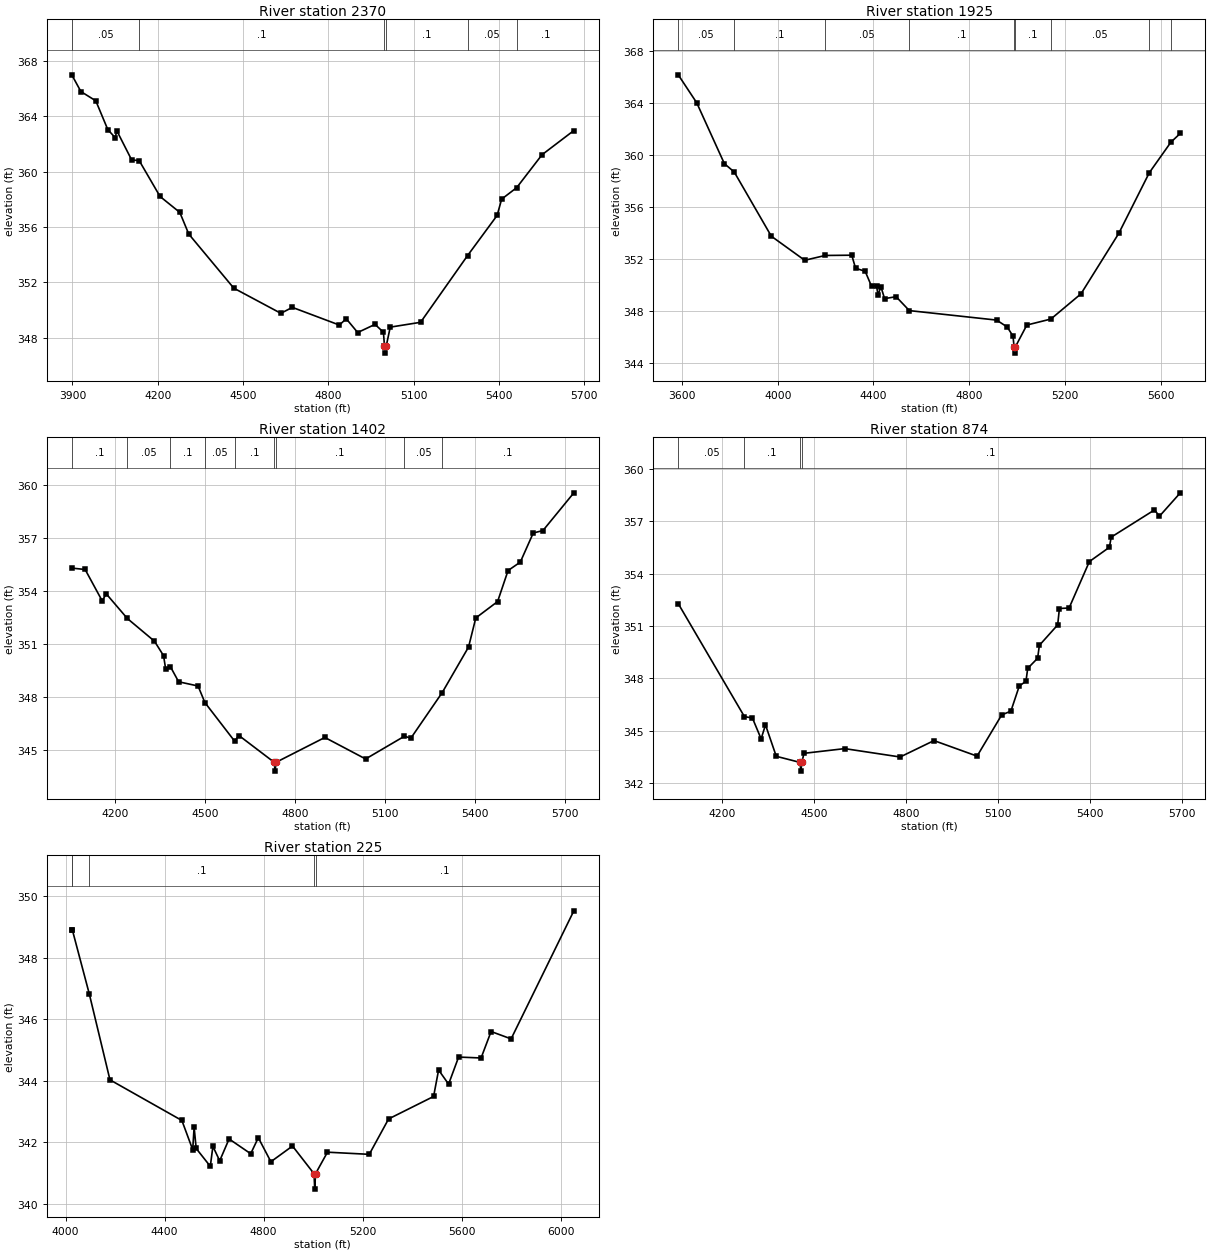
Type RM Length L Ch R = 1,2370,445,445,445
BEGIN DESCRIPTION:
Mapping XS 8eff8cd1
END DESCRIPTION:
XS GIS Cut Line= 4
      2199317.62     13228200.48      2199984.25     13227976.54
      2200281.12     13227252.58      2200328.00     13226976.53
#Sta/Elev= 30
  3897.6  367.01  3929.7  365.80  3982.1  365.13  4024.3  363.05  4050.5  362.46
  4055.9  362.97  4108.3  360.85  4134.6  360.81  4208.1  358.21  4277.5  357.06
  4309.1  355.49  4467.4  351.58  4632.9  349.76  4673.3  350.19  4838.8  348.91
  4862.8  349.37  4903.1  348.37  4964.2  348.96  4993.6  348.39  4997.4  347.38
  5000.1  346.88  5003.4  347.38  5017.6  348.76  5124.3  349.11  5289.7  353.94
  5393.5  356.84  5409.4  358.02  5462.3  358.85  5551.4  361.23  5663.3  362.98
#Mann=6,-1,0
  3897.6    0.05       0  4134.6     0.1       0  4997.4    0.07       0
  5003.4     0.1       0  5289.7    0.05       0  5462.3     0.1       0
Bank Sta=4997.4,5003.4
Exp/Cntr=0.3,0.1

Type RM Length L Ch R = 1,1925,523,523,523
BEGIN DESCRIPTION:
Mapping XS b8c3abd6
END DESCRIPTION:
XS GIS Cut Line= 4
      2199557.12     13228471.34      2200364.46     13228257.79
      2200687.37     13227294.24      2200598.83     13227065.07
#Sta/Elev= 30
  3584.5  366.15  3661.7  364.00  3777.2  359.32  3818.3  358.68  3973.3  353.74
  4112.7  351.89  4198.5  352.26  4309.2  352.28  4325.1  351.28  4365.3  351.04
  4391.9  349.89  4412.6  349.94  4418.7  349.23  4431.1  349.85  4446.3  348.94
  4494.4  349.09  4549.7  348.02  4914.3  347.29  4958.5  346.76  4982.7  346.06
  4987.1  345.25  4989.9  344.75  4993.1  345.25  5040.5  346.91  5140.8  347.37
  5266.7  349.31  5424.5  353.96  5551.9  358.62  5642.2  360.97  5681.5  361.65
#Mann=9,-1,0
  3584.5    0.05       0  3818.3     0.1       0  4198.5    0.05       0
  4549.7     0.1       0  4987.1    0.07       0  4993.1     0.1       0
  5140.8    0.05       0  5551.9     0.1       0  5642.2    0.05       0
Bank Sta=4987.1,4993.1
Exp/Cntr=0.3,0.1

Type RM Length L Ch R = 1,1402,528,528,528
BEGIN DESCRIPTION:
Mapping XS fac55f55
END DESCRIPTION:
XS GIS Cut Line= 3
      2200952.99     13228591.16      2201062.37     13227440.08
      2200869.86     13226961.40
#Sta/Elev= 30
  4056.9  355.31  4101.4  355.23  4158.2  353.45  4171.7  353.85  4242.0  352.45
  4332.4  351.16  4362.6  350.34  4369.4  349.61  4385.6  349.71  4412.8  348.86
  4477.5  348.62  4500.3  347.68  4599.3  345.49  4613.7  345.81  4731.2  344.29
  4734.0  343.79  4737.2  344.29  4899.8  345.70  5035.6  344.48  5164.8  345.77
  5186.3  345.66  5290.8  348.25  5378.4  350.83  5402.5  352.48  5475.1  353.41
  5510.0  355.17  5550.8  355.65  5593.9  357.30  5626.2  357.44  5729.1  359.58
#Mann=9,-1,0
  4056.9     0.1       0  4242.0    0.05       0  4385.6     0.1       0
  4500.3    0.05       0  4599.3     0.1       0  4731.2    0.07       0
  4737.2     0.1       0  5164.8    0.05       0  5290.8     0.1       0
Bank Sta=4731.2,4737.2
Exp/Cntr=0.3,0.1

Type RM Length L Ch R = 1,874,649,649,649
BEGIN DESCRIPTION:
Mapping XS 0c1605b0
END DESCRIPTION:
XS GIS Cut Line= 4
      2201253.33     13228253.03      2201513.76     13227949.19
      2201453.00     13227237.39      2201201.99     13226778.64
#Sta/Elev= 30
  4057.1  352.28  4273.1  345.80  4298.9  345.73  4327.4  344.53  4341.7  345.33
  4376.8  343.53  4454.3  343.18  4457.0  342.68  4460.3  343.18  4467.1  343.70
  4600.1  343.97  4780.8  343.49  4891.2  344.43  5031.7  343.54  5112.0  345.90
  5142.1  346.12  5169.4  347.56  5191.2  347.83  5196.9  348.57  5229.2  349.15
  5234.9  349.89  5294.6  351.06  5300.3  352.00  5331.9  352.03  5398.0  354.69
  5463.4  355.51  5469.1  356.09  5610.4  357.65  5626.6  357.29  5694.6  358.63
#Mann=4,-1,0
  4057.1    0.05       0  4273.1     0.1       0  4454.3    0.07       0
  4460.3     0.1       0
Bank Sta=4454.3,4460.3
Exp/Cntr=0.3,0.1

Type RM Length L Ch R = 1,225,0,0,0
BEGIN DESCRIPTION:
UNT 008 IN RACR 1.0
END DESCRIPTION:
XS GIS Cut Line= 4
      2201392.27     13228357.15      2201696.05     13228140.16
      2202095.36     13227411.00      2201982.62     13226595.82
#Sta/Elev= 30
  4025.1  348.91  4027.1  348.91  4095.9  346.82  4179.3  344.03  4469.8  342.71
  4513.5  341.76  4519.2  342.49  4527.6  341.80  4584.6  341.22  4595.0  341.87
  4622.5  341.40  4660.4  342.11  4747.7  341.63  4778.4  342.15  4829.2  341.37
  4916.5  341.88  5003.5  340.98  5006.2  340.48  5009.5  340.98  5057.7  341.68
  5226.5  341.61  5304.6  342.76  5486.3  343.49  5506.5  344.35  5546.9  343.89
  5587.3  344.77  5678.1  344.74  5718.5  345.60  5799.3  345.36  6052.7  349.52
#Mann=5,-1,0
  4025.1     0.1       0  4027.1    0.05       0  4095.9     0.1       0
  5003.5    0.07       0  5009.5     0.1       0
Bank Sta=5003.5,5009.5
Exp/Cntr=0.3,0.1

Chan Stop Cuts=-1