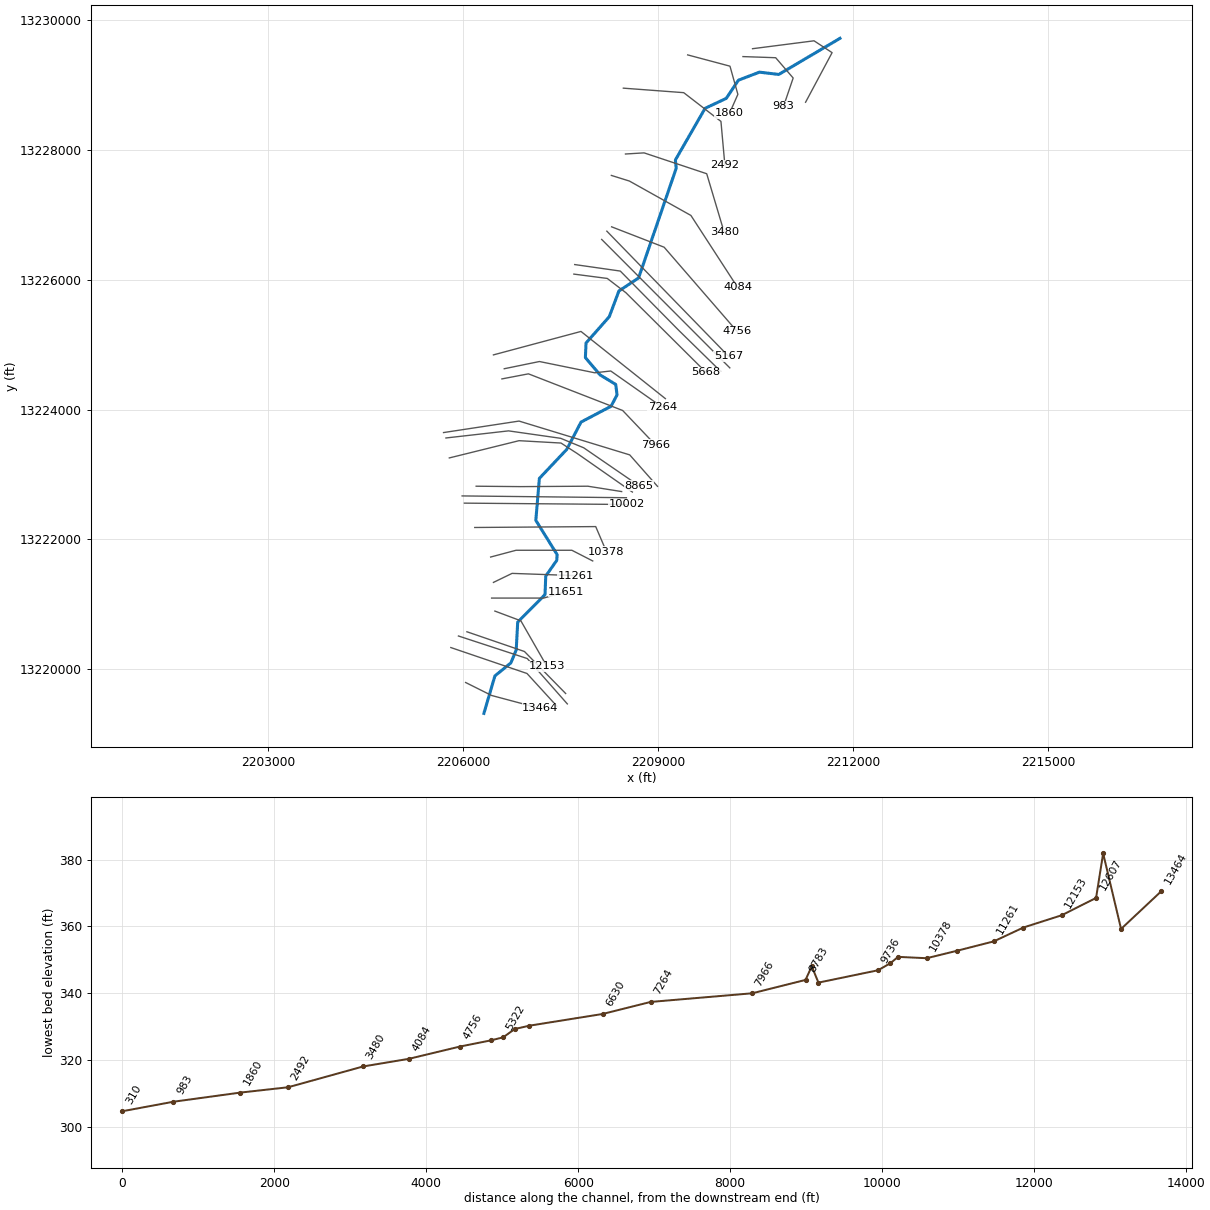
--- UNT 009 IN RACR.prj (project) ---

Proj Title=UNT 009 IN RACR Base Level Engineering
Current Plan=p01
Default Exp/Contr=0.3,0.1
English Units
Geom File=g01
Flow File=f01
Plan File=p01
Y Axis Title=Elevation
X Axis Title(PF)=Main Channel Distance
X Axis Title(XS)=Station
BEGIN DESCRIPTION:
UNT 009 IN RACR
END DESCRIPTION:
DSS Export Rating Curves= 0
DSS Export Rating Curve Sorted= 0
DSS Export Volume Flow Curves= 0
DXF OffsetX= 0
DXF OffsetY= 0
DXF ScaleX= 1
DXF ScaleY= 10

--- UNT 009 IN RACR.p01 (plan) ---

Plan Title=Multiple Run
Short Identifier=Multiple
Geom File=g01
Flow File=f01
Subcritical Flow
K Sum by GR= 0
Std Step Tol= 0.01
Critical Tol= 0.01
Num of Std Step Trials= 20
Max Error Tol= 0.3
Flow Tol Ratio= 0.001
Split Flow NTrial= 30
Split Flow Tol= 0.02
Split Flow Ratio= 0.02
Log Output Level= 0
Friction Slope Method= 1
Unsteady Friction Slope Method= 2
Unsteady Bridges Friction Slope Method= 1
Parabolic Critical Depth
Global Vel Dist=  1 , 1 , 1
Global Log Level= 0
CheckData=True
Encroach Param= -1, 0, 0, 0
BEGIN DESCRIPTION:
Multiple Run
END DESCRIPTION:

--- UNT 009 IN RACR.f01 (steady flow) ---

Flow Title=Multiple
Number of Profiles=7
Profile Names=10-year,25-year,50-year,1pct_min,100-year,1pct_plu,500-year
River Rch & RM= UNT 009 IN RACR,Reach-1,13464
     400     576     727     675     913    1235    1463
River Rch & RM= UNT 009 IN RACR,Reach-1,5167
     468     677     858     798    1079    1459    1737
Boundary for River Rch & Prof#=UNT 009 IN RACR,Reach-1,1
Up Type=0
Dn Type=3
Dn Slope=0.005
Boundary for River Rch & Prof#=UNT 009 IN RACR,Reach-1,2
Up Type=0
Dn Type=3
Dn Slope=0.005
Boundary for River Rch & Prof#=UNT 009 IN RACR,Reach-1,3
Up Type=0
Dn Type=3
Dn Slope=0.005
Boundary for River Rch & Prof#=UNT 009 IN RACR,Reach-1,4
Up Type=0
Dn Type=3
Dn Slope=0.005
Boundary for River Rch & Prof#=UNT 009 IN RACR,Reach-1,5
Up Type=0
Dn Type=3
Dn Slope=0.005
Boundary for River Rch & Prof#=UNT 009 IN RACR,Reach-1,6
Up Type=0
Dn Type=3
Dn Slope=0.005
Boundary for River Rch & Prof#=UNT 009 IN RACR,Reach-1,7
Up Type=0
Dn Type=3
Dn Slope=0.005

--- UNT 009 IN RACR.g01 (geometry) ---

Geom Title=Existing Conditions
Program Version=4.10

River Reach=UNT 009 IN RACR ,Reach-1
Reach XY= 30
      2206318.78     13219321.37      2206488.69     13219899.06
      2206733.83     13220098.37      2206816.12     13220298.15
       2206839.1     13220726.76      2207259.38     13221150.43
      2207270.56      13221435.5      2207440.09     13221677.83
      2207445.65     13221766.72      2207117.87     13222293.81
      2207172.73     13222940.33      2207594.82     13223387.75
      2207813.63     13223807.44      2208274.64     13224050.36
      2208367.74     13224225.25      2208347.11     13224386.67
      2208104.83     13224535.47      2207880.37      13224800.2
      2207890.64     13225025.51      2208248.28     13225430.15
      2208396.51     13225826.34      2208699.44     13226027.44
      2209278.31     13227716.92      2209265.44     13227843.58
      2209722.63     13228639.39      2210049.18     13228792.78
      2210234.85     13229072.05      2210558.24     13229195.99
      2210856.21     13229160.83      2211797.72     13229716.86

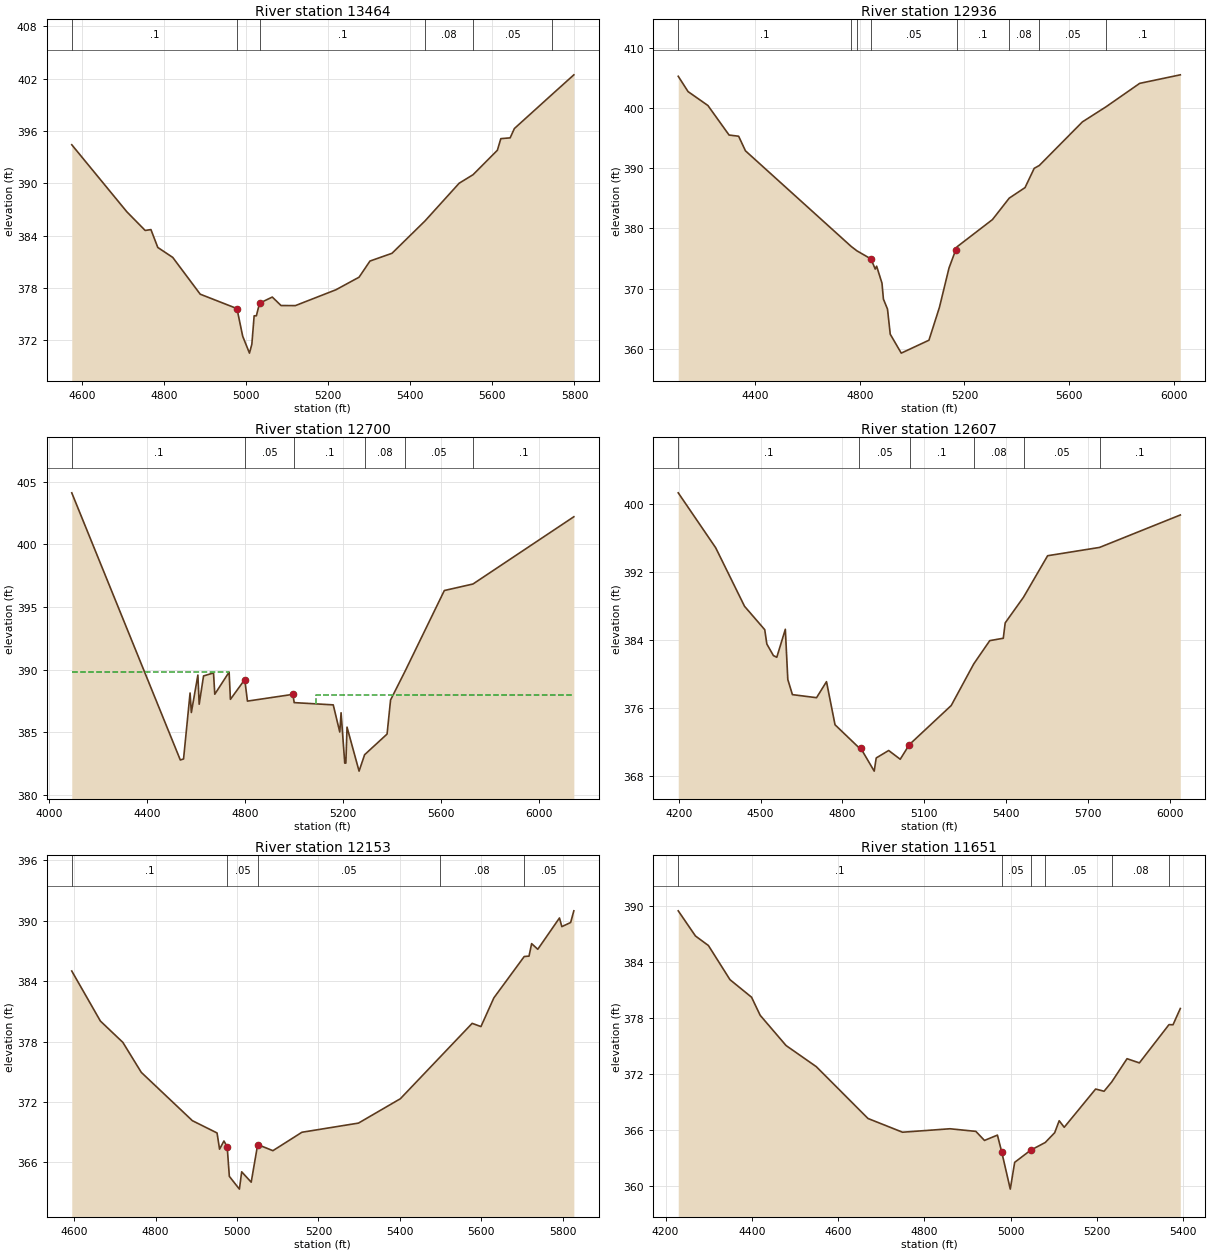
Type RM Length L Ch R = 1 ,13464   ,528,528,528
BEGIN DESCRIPTION:
UNT 009 IN RACR 17.0
END DESCRIPTION:
XS GIS Cut Line= 3
      2206037.73     13219796.85      2206437.72     13219596.85
      2207187.71     13219396.86
#Sta/Elev= 30
  4575.1  394.43  4709.3  386.74    4754   384.6    4768   384.7  4784.7  382.65
  4821.1  381.51  4888.1  377.29  4977.6  375.64  4991.6  372.47  5008.1  370.53
  5013.9  371.55  5019.5  374.81  5024.9  374.81  5032.7  376.26  5063.7  376.96
    5085  375.99    5120  375.98  5218.9   377.8  5275.2  379.24  5301.7  381.09
  5355.4  381.98  5435.8  385.69  5519.1  390.02  5552.8  390.99  5612.2   393.8
  5620.6  395.13  5643.3  395.22  5653.6  396.29  5745.4   400.2  5798.5  402.45
#Mann= 6 ,-1 , 0
  4575.1      .1       0  4977.6     .05       0  5032.7      .1       0
  5435.8     .08       0  5552.8     .05       0  5745.4      .1       0
Bank Sta=4977.6,5032.7
XS Rating Curve= 0 ,0
Exp/Cntr=0.3,0.1

Type RM Length L Ch R = 1 ,12936   ,236,236,236
BEGIN DESCRIPTION:
Mapping XS 174edab7
END DESCRIPTION:
XS GIS Cut Line= 3
      2205810.14     13220335.04      2206982.03     13219935.73
      2207442.12     13219432.23
#Sta/Elev= 30
  4105.3  405.33  4142.9  402.78  4218.9  400.46  4299.7  395.55  4336.3  395.35
  4362.4  392.92  4767.2  376.99  4788.5  376.28  4842.3  374.93  4858.7  373.24
    4864  373.72  4884.5   370.9    4890  368.24  4905.6  366.58  4916.1   362.4
  4958.2  359.25  5064.1   361.4  5104.2  366.87  5140.8  373.41  5166.9  376.48
  5172.2  376.97  5307.1  381.48  5371.2  385.05  5431.6   386.8  5466.7  390.01
  5486.1  390.48  5651.1  397.74    5741  400.24  5870.1  404.15  6025.4  405.57
#Mann= 8 ,-1 , 0
  4105.3      .1       0  4767.2     .12       0  4788.5      .1       0
  4842.3     .05       0  5172.2      .1       0  5371.2     .08       0
  5486.1     .05       0    5741      .1       0
Bank Sta=4842.3,5166.9
XS Rating Curve= 0 ,0
Exp/Cntr=0.3,0.1

Type RM Length L Ch R = 1 ,12700   ,93,93,93
BEGIN DESCRIPTION:
Mapping XS 6dc9a8a8
END DESCRIPTION:
XS GIS Cut Line= 3
      2205927.33     13220512.99      2206986.37     13220165.77
      2207602.72     13219466.95
#Sta/Elev= 30
  4093.9  404.12  4536.3  382.79  4549.5  382.87  4576.1  388.14  4581.3  386.58
  4607.9  389.57  4613.2  387.24    4631   389.5  4671.6  389.74  4676.8  388.04
  4735.2  389.81  4740.5  387.63  4798.9  389.21  4809.9  387.49  4995.2  388.03
  5000.4  387.37  5159.6  387.19  5186.2  385.02  5191.5  386.56  5206.5  382.54
    5211  382.54  5215.8  385.41  5264.9   381.9  5287.4  383.21    5379  384.86
  5393.2  387.58  5453.4  389.92  5612.4  396.32  5729.1  396.84  6140.2  402.21
#Mann= 6 ,-1 , 0
  4093.9      .1       0  4798.9     .05       0  5000.4      .1       0
  5287.4     .08       0  5453.4     .05       0  5729.1      .1       0
#XS Ineff= 2 , 0
       0 4734.38  389.81 5090.28       0  387.96
Permanent Ineff=
       T       T
Bank Sta=4798.9,4995.2
XS Rating Curve= 0 ,0
Exp/Cntr=0.3,0.1

Type RM Length L Ch R = 1 ,12607   ,454,454,454
BEGIN DESCRIPTION:
UNT 009 IN RACR 15.0
END DESCRIPTION:
XS GIS Cut Line= 3
      2206057.56     13220578.09      2206942.97     13220274.27
      2207576.65     13219627.57
#Sta/Elev= 30
  4197.9  401.33  4335.3  394.86  4441.2  387.96  4515.2  385.21  4522.9  383.52
    4547  382.16  4559.4  381.96  4590.7  385.26  4599.8  379.34  4616.7  377.56
  4705.2   377.2  4741.7  379.09    4773  374.01  4861.5  371.29  4866.8  371.28
  4916.7  368.55    4924   370.1  4969.8  370.98  5012.1  369.95  5043.8  371.58
  5049.1  371.78  5199.2  376.28  5281.8  381.18  5340.5  383.92  5390.1   384.2
  5397.1  386.01  5464.6  389.05  5552.7  393.92  5743.3   394.9  6039.4  398.72
#Mann= 6 ,-1 , 0
  4197.9      .1       0  4861.5     .05       0  5049.1      .1       0
  5281.8     .08       0  5464.6     .05       0  5743.3      .1       0
Bank Sta=4866.8,5043.8
XS Rating Curve= 0 ,0
Exp/Cntr=0.3,0.1

Type RM Length L Ch R = 1 ,12153   ,502,502,502
BEGIN DESCRIPTION:
UNT 009 IN RACR 14.0
END DESCRIPTION:
XS GIS Cut Line= 3
      2206487.76     13220896.84      2206887.72     13220746.85
      2207287.73     13220046.84
#Sta/Elev= 30
  4593.9  385.01  4664.2  380.04  4719.4  377.92  4764.7  374.94  4890.2  370.14
  4950.8  368.92    4957  367.31  4967.7  368.12  4975.7  367.55    4981  364.61
  5005.7  363.34  5011.3  365.06  5034.7  364.03  5050.6  367.77    5088  367.16
  5159.3  368.99  5298.2   369.9  5401.1  372.32  5498.4  376.45  5577.5  379.81
  5599.1  379.49  5630.8  382.34  5705.4  386.45  5717.2  386.49  5723.6  387.73
  5738.7  387.17    5792  390.28  5797.8  389.42  5819.4  389.83  5827.3  390.99
#Mann= 5 ,-1 , 0
  4593.9      .1       0  4975.7     .05       0  5050.6     .05       0
  5498.4     .08       0  5705.4     .05       0
Bank Sta=4975.7,5050.6
XS Rating Curve= 0 ,0
Exp/Cntr=0.3,0.1

Type RM Length L Ch R = 1 ,11651   ,390,390,390
BEGIN DESCRIPTION:
UNT 009 IN RACR 13.0
END DESCRIPTION:
XS GIS Cut Line= 3
      2206437.71     13221096.85      2207237.72     13221096.85
       2207587.7     13221196.85
#Sta/Elev= 30
  4229.4  389.51  4269.4  386.81  4299.4  385.79  4349.4  382.13  4399.4  380.25
  4419.4  378.31  4479.4  375.07  4549.4  372.81  4669.4  367.25  4749.4  365.78
  4859.4  366.15  4919.4  365.87  4939.4   364.9  4969.4  365.47  4979.4  363.66
  4999.2  359.68  5009.4  362.55  5046.3  363.85  5080.3  364.68  5102.2  365.73
  5112.6  367.01  5124.3  366.31  5197.1  370.41  5216.6  370.17  5234.4  371.17
  5269.9  373.66  5298.5  373.21  5367.1  377.31  5376.5   377.3  5393.4  379.04
#Mann= 6 ,-1 , 0
  4229.4      .1       0  4979.4     .05       0  5046.3      .1       0
  5080.3     .05       0  5234.4     .08       0  5367.1     .05       0
Bank Sta=4979.4,5046.3
XS Rating Curve= 0 ,0
Exp/Cntr=0.3,0.1

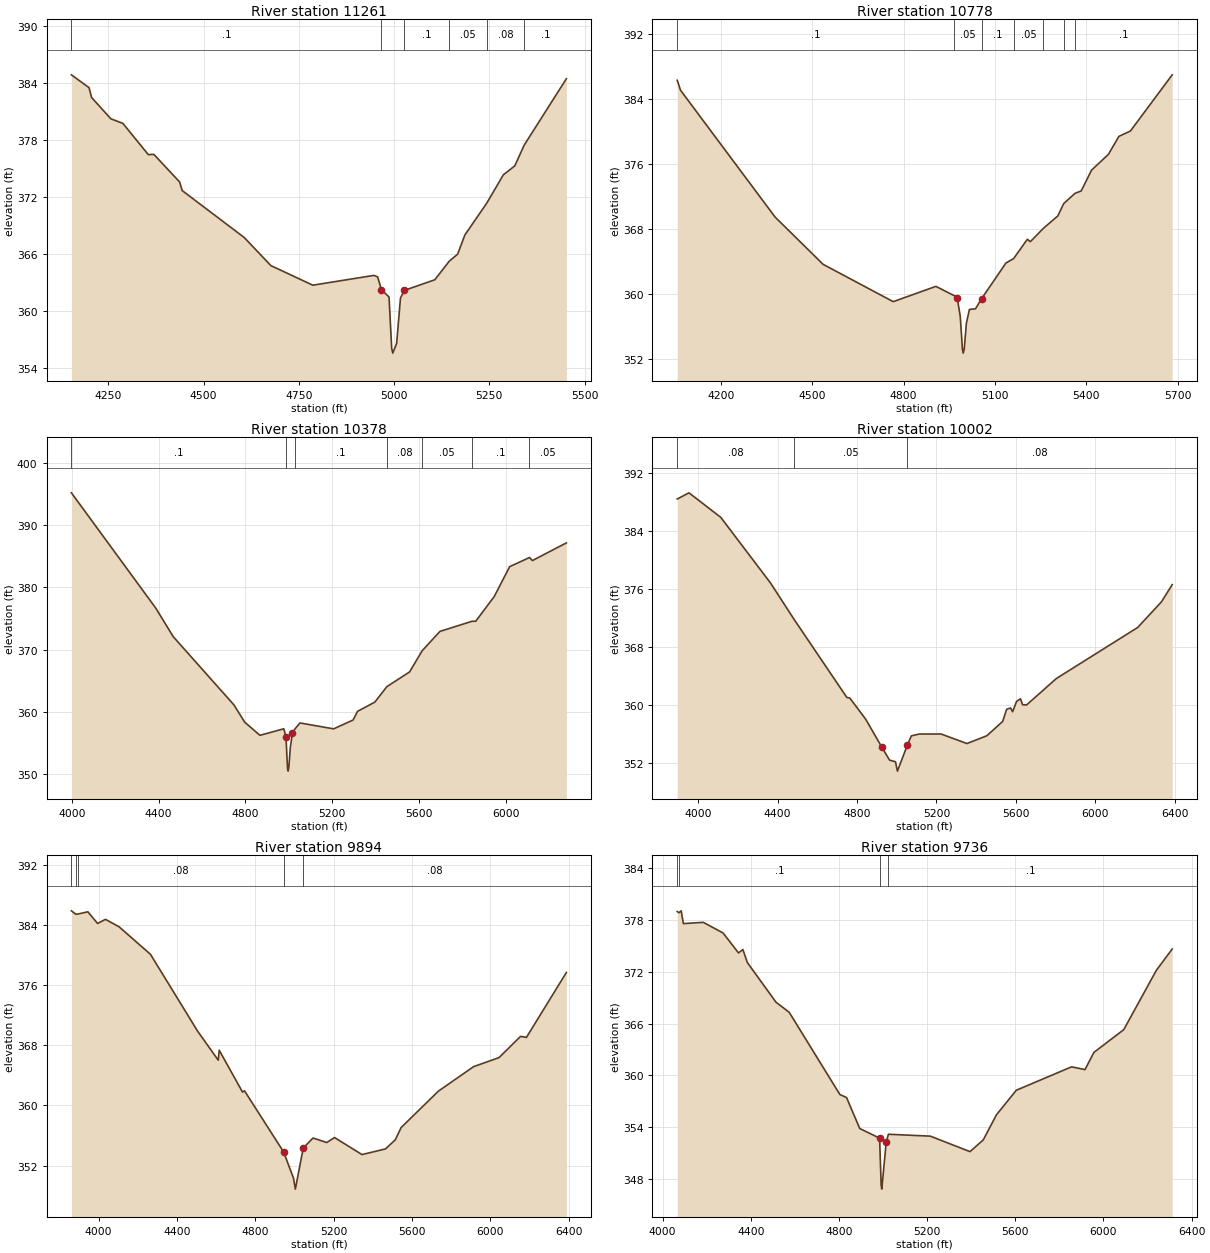
Type RM Length L Ch R = 1 ,11261   ,483,483,483
BEGIN DESCRIPTION:
UNT 009 IN RACR 12.0
END DESCRIPTION:
XS GIS Cut Line= 3
      2206466.04     13221338.37      2206752.51     13221477.27
      2207733.03     13221442.56
#Sta/Elev= 30
  4152.8  384.81  4199.1  383.46  4205.7  382.43  4256.4  380.18    4288   379.7
  4354.7  376.41  4369.2  376.44    4437  373.53  4443.6  372.63  4606.5  367.69
  4676.5  364.73  4786.6  362.67  4946.7   363.7  4956.7  363.55  4966.7  362.21
  4986.7  361.42  4993.7  356.02  4996.5  355.52  5006.7  356.55  5016.7  361.31
  5026.7  362.12  5106.8  363.24  5144.9   365.2  5166.8  365.93  5185.7  367.95
  5243.2   371.3  5286.9  374.29  5316.9  375.23  5341.5  377.41  5452.3   384.4
#Mann= 6 ,-1 , 0
  4152.8      .1       0  4966.7     .05       0  5026.7      .1       0
  5144.9     .05       0  5243.2     .08       0  5341.5      .1       0
Bank Sta=4966.7,5026.7
XS Rating Curve= 0 ,0
Exp/Cntr=0.3,0.1

Type RM Length L Ch R = 1 ,10778   ,400,400,400
BEGIN DESCRIPTION:
UNT 009 IN RACR 11.0
END DESCRIPTION:
XS GIS Cut Line= 4
      2206422.68     13221729.01      2206813.28     13221833.17
      2207672.65     13221833.17      2207993.32     13221668.51
#Sta/Elev= 30
  4057.5  386.27  4068.2  385.05  4378.7  369.44  4536.2  363.63  4766.2  359.04
  4906.2  360.92  4966.2  359.78  4976.2   359.5  4986.2  357.21  4993.2  353.21
  4995.9  352.71  4999.2  353.21  5006.2  356.38  5016.2  358.08  5036.2  358.16
  5056.2  359.41  5136.2   363.8  5161.1  364.33  5206.2  366.71  5216.2  366.42
  5259.2  368.07  5306.2  369.58  5325.5   371.1  5362.5  372.36    5383  372.66
    5417  375.22  5472.3  377.16  5506.7  379.37  5544.5  380.03  5681.6  386.94
#Mann= 7 ,-1 , 0
  4057.5      .1       0  4966.2     .05       0  5056.2      .1       0
  5161.1     .05       0  5259.2      .1       0  5325.5     .08       0
  5362.5      .1       0
Bank Sta=4976.2,5056.2
XS Rating Curve= 0 ,0
Exp/Cntr=0.3,0.1

Type RM Length L Ch R = 1 ,10378   ,376,376,376
BEGIN DESCRIPTION:
UNT 009 IN RACR 10.0
END DESCRIPTION:
XS GIS Cut Line= 3
      2206178.22     13222183.99      2208039.32     13222197.88
      2208205.38     13221810.42
#Sta/Elev= 30
  3997.6  395.17  4387.1  376.63  4467.1  372.07  4747.1  361.11  4797.1  358.32
  4867.1  356.22  4977.1  357.27  4987.1  355.99  4994.1  350.97  4996.9  350.47
  5000.1  350.97  5007.1  354.26  5017.1  356.58  5027.1  357.18  5051.6  358.21
  5207.1  357.26  5297.1  358.69  5317.1  360.07  5397.1  361.56  5452.4  364.04
  5557.1   366.4  5615.6  369.82  5697.1  372.91  5846.2  374.55    5862  374.53
  5947.9  378.53  6018.7  383.31  6110.2  384.78  6123.8  384.29  6280.3  387.13
#Mann= 7 ,-1 , 0
  3997.6      .1       0  4987.1     .05       0  5027.1      .1       0
  5452.4     .08       0  5615.6     .05       0  5846.2      .1       0
  6110.2     .05       0
Bank Sta=4987.1,5017.1
XS Rating Curve= 0 ,0
Exp/Cntr=0.3,0.1

Type RM Length L Ch R = 1 ,10002   ,108,108,108
BEGIN DESCRIPTION:
Mapping XS 31ef51d9
END DESCRIPTION:
XS GIS Cut Line= 2
      2206018.48     13222558.99      2208511.59     13222538.16
#Sta/Elev= 30
  3894.2  388.36  3953.4  389.21  4113.5  385.83  4363.5  376.81  4483.4  371.75
  4748.5  361.02  4763.5  360.94  4843.5  358.02  4923.5  354.23  4963.5  352.39
  4993.5  352.16  5003.2  350.87  5053.5  354.46  5073.5  355.73  5113.5  355.98
  5223.5  355.98  5353.5  354.67  5453.5  355.74  5533.5  357.72  5553.5   359.4
  5573.5  359.57  5583.5  359.05  5603.5  360.48  5623.5  360.83  5633.5  360.02
  5653.5  359.98  5803.5  363.62  6213.5  370.66  6333.5   374.2  6387.4  376.56
#Mann= 3 ,-1 , 0
  3894.2     .08       0  4483.4     .05       0  5053.5     .08       0
Bank Sta=4923.5,5053.5
XS Rating Curve= 0 ,0
Exp/Cntr=0.3,0.1

Type RM Length L Ch R = 1 ,9894    ,158,158,158
BEGIN DESCRIPTION:
UNT 009 IN RACR 9.0
END DESCRIPTION:
XS GIS Cut Line= 2
      2205983.82      13222670.1      2208511.56     13222642.33
#Sta/Elev= 30
  3860.8  385.86  3883.2  385.42  3892.2  385.42  3944.7  385.73  3994.7  384.18
  4034.7  384.73  4104.7  383.73  4264.7  380.08  4504.7   369.9  4610.7  366.02
  4615.7  367.34  4734.8  361.78  4744.8  361.95  4944.8  353.82  4994.8  350.37
  5004.5  348.89  5044.8  354.35  5094.8  355.68  5164.8  355.08  5204.8  355.74
  5344.8  353.48  5464.8  354.23  5514.8  355.44  5544.8  357.07  5734.8   361.9
  5914.8  365.16  6044.8  366.36  6154.8  369.18  6184.8  369.05  6388.7  377.67
#Mann= 5 ,-1 , 0
  3860.8     .05       0  3883.2      .1       0  3892.2     .08       0
  4944.8     .05       0  5044.8     .08       0
Bank Sta=4944.8,5044.8
XS Rating Curve= 0 ,0
Exp/Cntr=0.3,0.1

Type RM Length L Ch R = 1 ,9736    ,783,783,783
BEGIN DESCRIPTION:
Mapping XS 48bb4e3a
END DESCRIPTION:
XS GIS Cut Line= 4
      2206199.81     13222819.67      2206884.74     13222813.33
      2207918.42     13222819.67      2208438.46     13222737.23
#Sta/Elev= 30
  4066.6  378.97  4074.2  378.83  4084.5  379.05  4094.5  377.57  4184.5  377.72
  4274.5  376.49  4344.5  374.18  4364.5  374.57  4384.5  373.07  4514.5  368.48
  4574.5  367.31  4804.5  357.79  4834.5  357.45  4894.5  353.86  4984.5  352.75
  4991.5  347.35  4994.3  346.85  5014.5  352.28  5024.5   353.2  5214.6  352.98
  5394.6  351.19  5454.6  352.54  5514.6  355.45  5604.6  358.29  5855.4     361
  5916.2  360.68  5956.7  362.67    6092   365.3  6240.2  372.18  6311.8  374.63
#Mann= 4 ,-1 , 0
  4066.6     .05       0  4074.2      .1       0  4984.5     .05       0
  5024.5      .1       0
Bank Sta=4984.5,5014.5
XS Rating Curve= 0 ,0
Exp/Cntr=0.3,0.1

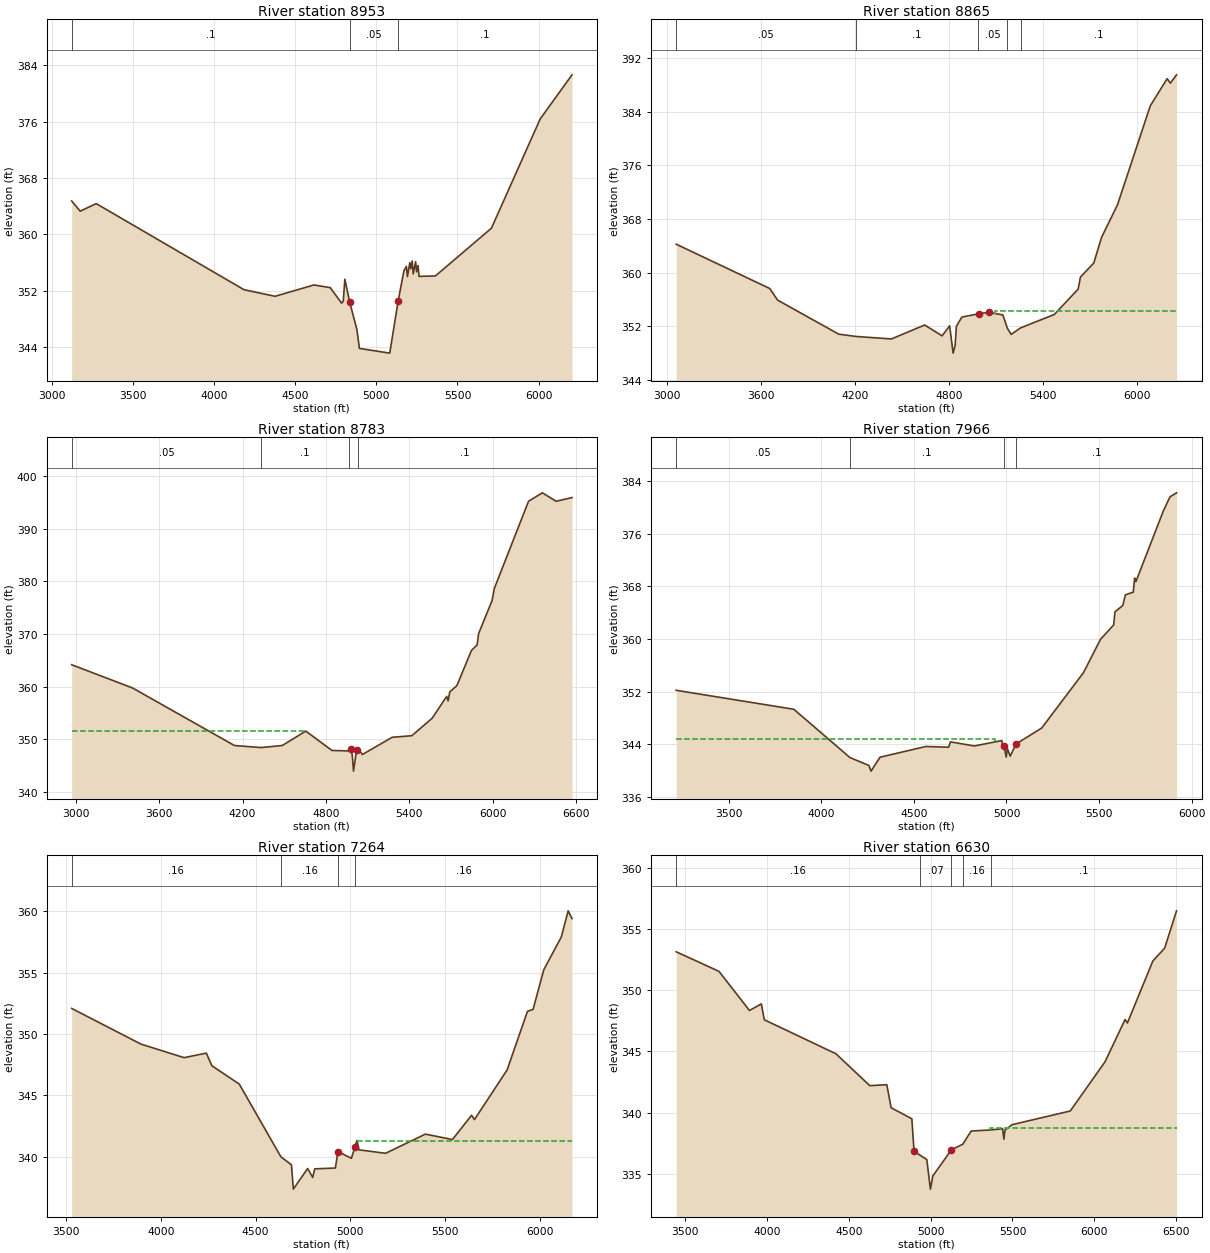
Type RM Length L Ch R = 1 ,8953    ,88,88,88
BEGIN DESCRIPTION:
Mapping XS ada05af9
END DESCRIPTION:
XS GIS Cut Line= 5
      2205786.69     13223255.17      2206859.63      13223520.8
      2207505.47     13223484.34      2207755.47     13223322.88
      2208603.54     13222729.76
#Sta/Elev= 30
  3121.6  364.75  3174.2  363.31  3273.1  364.38  4183.8  352.16  4375.3  351.22
  4615.6  352.83  4715.8  352.45  4785.9  350.24  4795.9  350.51  4805.9  353.64
    4836  350.36  4880.4  346.48  4895.6  343.82  5082.7  343.15  5134.4  350.54
  5169.8  354.83  5185.4  355.48  5191.5  354.01  5206.4  356.01  5212.5  355.14
  5221.2  356.24  5227.3  354.41  5242.1  356.13  5248.2   354.7    5257   355.6
  5263.1  354.05  5364.2  354.11  5709.5  360.89  6010.4  376.41  6206.3  382.67
#Mann= 3 , 0 , 0
  3121.6      .1       0    4836     .05       0  5134.4      .1       0
Bank Sta=4836,5134.4
XS Rating Curve= 0 ,0
Exp/Cntr=0.3,0.1

Type RM Length L Ch R = 1 ,8865    ,82,82,82
BEGIN DESCRIPTION:
Mapping XS c9c2babb
END DESCRIPTION:
XS GIS Cut Line= 5
      2205734.66     13223562.47      2206698.18     13223671.84
      2207500.26     13223557.26      2207854.43     13223411.42
      2208703.06     13222828.32
#Sta/Elev= 30
    3060  364.25  3656.9  357.65  3707.2  355.92  4097.6  350.85  4208.3  350.51
  4433.3  350.14  4645.4  352.22  4756.6   350.6  4804.7  352.09    4827  348.03
  4839.9  349.18    4848  352.04  4883.1   353.4  4984.3  353.86  4989.7   353.9
  5053.5  354.09  5144.2  353.72  5173.6  351.71  5197.5  350.82  5257.4  351.79
  5472.5  353.78  5624.8  357.56  5639.5  359.36  5724.4  361.44  5774.3  365.27
  5875.8  370.11  6084.9  384.84  6192.5   388.9  6213.4  388.23  6252.6  389.47
#Mann= 5 ,-1 , 0
    3060     .05       0  4208.3      .1       0  4984.3     .05       0
  5173.6      .1       0  5257.4      .1       0
#XS Ineff= 2 , 0
       0 4938.54  353.43 5093.23       0  354.29
Permanent Ineff=
       T       T
Bank Sta=4989.7,5053.5
XS Rating Curve= 0 ,0
Exp/Cntr=0.3,0.1

Type RM Length L Ch R = 1 ,8783    ,702,702,702
BEGIN DESCRIPTION:
Mapping XS 429b63b3
END DESCRIPTION:
XS GIS Cut Line= 4
      2205698.18      13223645.8      2206859.63     13223822.88
      2208562.76     13223302.05      2208989.82      13222817.7
#Sta/Elev= 30
  2969.7  364.15  3408.6  359.73  4141.2  348.82  4334.5  348.43  4486.2  348.83
    4655  351.56  4843.2  347.88  4966.1  347.79  4979.1  348.07  4989.6  346.97
  4998.6  343.96    5021  348.03  5031.4  348.18  5062.8  347.12  5276.8  350.38
  5418.4  350.68  5564.7     354  5669.3  358.14  5679.8  357.28  5691.2  358.99
  5742.5  360.18  5847.1  366.84  5887.9   367.9  5899.4  370.08  5996.8  376.38
    6011  378.54  6258.6  395.18  6358.2  396.77  6456.9  395.17  6571.3  395.87
#Mann= 4 ,-1 , 0
  2969.7     .05       0  4334.5      .1       0  4966.1     .05       0
  5031.4      .1       0
#XS Ineff= 2 , 0
         4644.34  351.66
Permanent Ineff=
       F       F
Bank Sta=4979.1,5021
XS Rating Curve= 0 ,0
Exp/Cntr=0.3,0.1

Type RM Length L Ch R = 1 ,7966    ,1336,1336,1336
BEGIN DESCRIPTION:
UNT 009 IN RACR 8.0
END DESCRIPTION:
XS GIS Cut Line= 4
      2206596.28     13224472.07      2207004.25     13224550.19
       2208453.9     13223985.95      2208957.35     13223456.46
#Sta/Elev= 30
  3216.8  352.22    3852  349.34  4154.9  342.01  4257.3  340.81  4268.8  339.95
  4317.1  342.06  4564.5  343.69  4687.5  343.58  4697.8  344.39    4827  343.77
  4975.2  344.59  4980.6  343.59    4988  343.69  4998.7  342.08  5005.1  343.37
  5020.2  342.23  5052.4  344.08  5190.6   346.5  5416.2  354.91  5508.1  359.97
  5578.8  362.14  5586.1  364.13  5628.2   365.1  5642.4  366.72  5684.8  367.12
  5692.1  369.25    5699  368.72  5847.8  379.49    5883  381.59  5918.4   382.2
#Mann= 4 ,-1 , 0
  3216.8     .05       0  4154.9      .1       0    4988     .05       0
  5052.4      .1       0
#XS Ineff= 2 , 0
       0 4936.61  344.79               0
Permanent Ineff=
       T       F
Bank Sta=4988,5052.4
XS Rating Curve= 0 ,0
Exp/Cntr=0.3,0.1

Type RM Length L Ch R = 1 ,7264    ,634,634,634
BEGIN DESCRIPTION:
Mapping XS 2cce9ed0
END DESCRIPTION:
XS GIS Cut Line= 5
      2206631.83     13224628.78       2207173.5     13224739.89
       2208024.2     13224566.28      2208270.72     13224594.06
      2209064.26     13224036.16
#Sta/Elev= 30
    3530  352.08    3896  349.17  4123.1  348.07  4240.4  348.44  4269.5  347.41
  4413.9  345.92  4633.8  339.99  4689.4  339.34  4699.4  337.36  4774.7  339.04
  4801.7  338.31  4811.9  339.01  4921.2  339.08  4934.4  340.42  5005.5  339.87
  5025.2  340.82  5035.2  341.33  5045.3  340.56  5186.2  340.28  5395.8  341.84
  5538.7   341.4  5639.8  343.38  5654.6  343.02  5827.1  347.07  5934.3  351.84
  5963.9     352  6020.5  355.23  6112.9   357.9  6149.1  360.03  6169.3   359.4
#Mann= 4 ,-1 , 0
    3530     .16       0  4633.8     .16       0  4934.4     .07       0
  5025.2     .16       0
#XS Ineff= 2 , 0
       0 4933.95  340.35 5034.77       0  341.31
Permanent Ineff=
       T       T
Bank Sta=4934.4,5025.2
XS Rating Curve= 0 ,0
Exp/Cntr=0.3,0.1

Type RM Length L Ch R = 1 ,6630    ,962,962,962
BEGIN DESCRIPTION:
UNT 009 IN RACR 7.0
END DESCRIPTION:
XS GIS Cut Line= 3
      2206465.55     13224841.98      2207812.76     13225203.09
      2209111.37     13224168.37
#Sta/Elev= 30
  3446.8  353.15  3707.9  351.55  3894.2  348.35  3966.7  348.89  3984.6  347.59
  4422.2  344.81  4629.3   342.2  4732.8  342.28  4759.1   340.4  4885.8  339.49
  4899.1  336.83  4935.4  336.52    4977  336.16  4999.2  333.74  5013.9  334.82
  5127.6  336.96  5196.5  337.41  5247.7  338.49  5368.4  338.58  5439.9  338.68
  5447.9  337.82  5454.3  338.56  5497.5  339.01  5853.1  340.13  6066.1  344.17
  6187.8  347.61  6202.2  347.33  6357.5   352.4  6429.6  353.45    6502   356.5
#Mann= 5 ,-1 , 0
  3446.8     .16       0  4935.4     .07       0  5127.6     .16       0
  5196.5     .16       0  5368.4      .1       0
#XS Ineff= 2 , 0
                         5360.41          338.76
Permanent Ineff=
       F       F
Bank Sta=4899.1,5127.6
XS Rating Curve= 0 ,0
Exp/Cntr=0.3,0.1

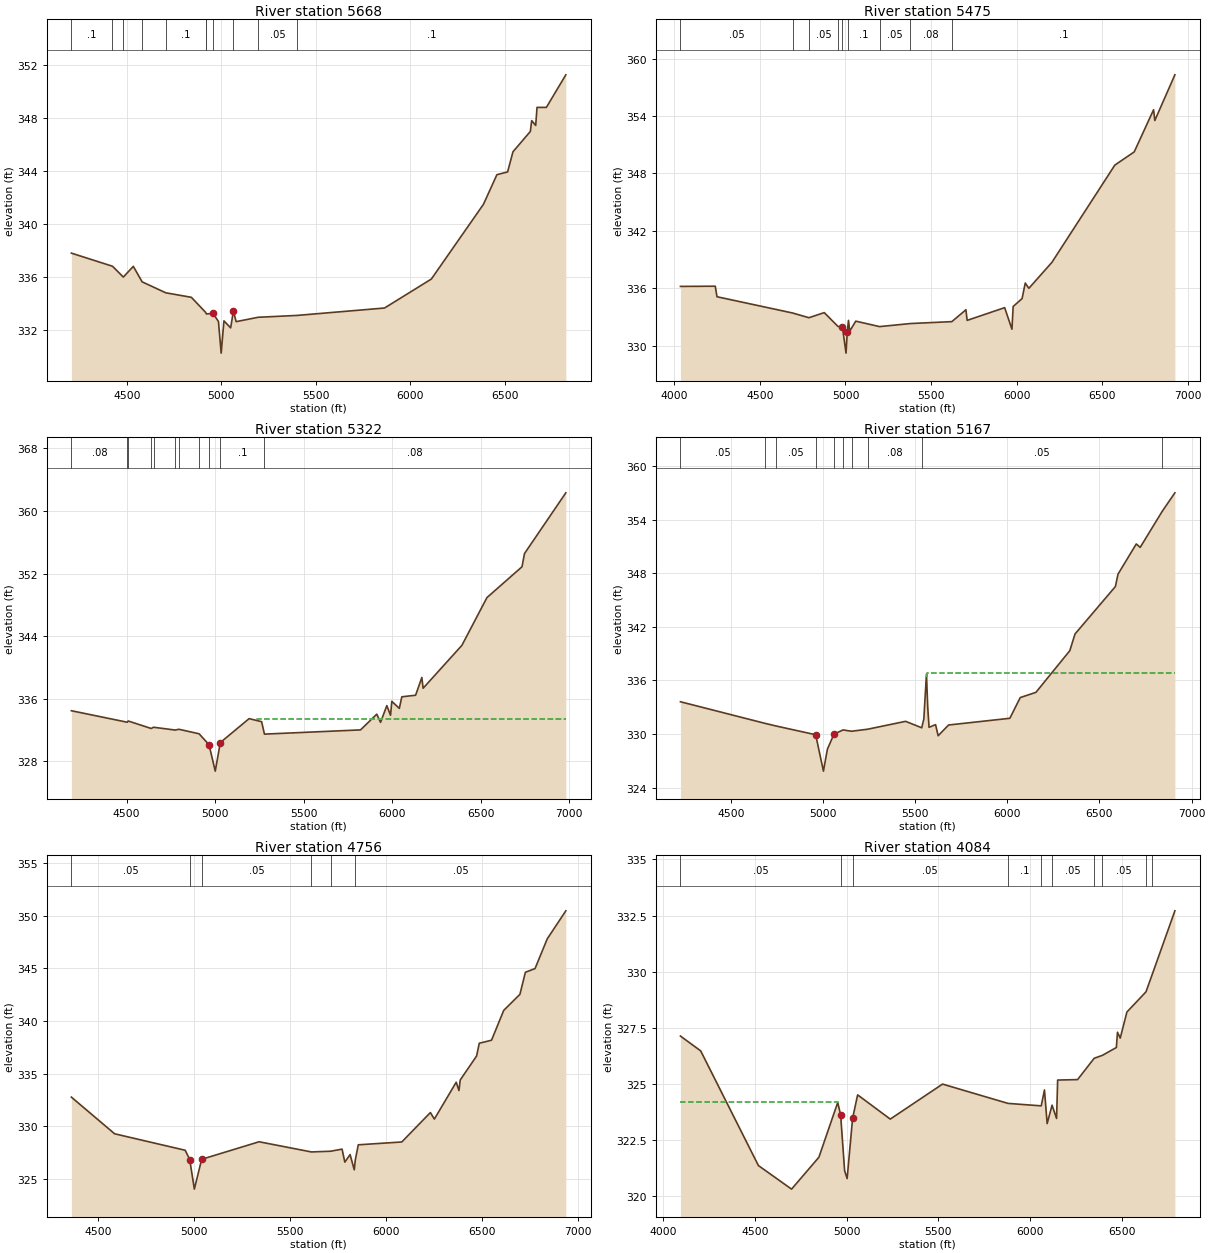
Type RM Length L Ch R = 1 ,5668    ,193,193,193
BEGIN DESCRIPTION:
UNT 009 IN RACR 6.0
END DESCRIPTION:
XS GIS Cut Line= 4
      2207703.01     13226086.12       2208217.3     13226019.33
      2208504.51     13225798.91      2209733.08     13224577.02
#Sta/Elev= 30
  4207.7   337.8  4424.8  336.81  4482.2  335.99  4535.1   336.8  4581.5  335.63
  4706.8   334.8  4841.9  334.46  4917.3  333.32  4921.7   333.2  4956.1  333.25
  4985.1  332.63  4999.4  330.24  5014.1  332.68  5049.5  332.15    5064  333.42
  5078.5  332.62    5195  332.95  5399.8  333.09  5862.8  333.65  6110.3  335.84
  6386.1   341.5  6456.8  343.73  6513.4  343.94  6541.7  345.46  6633.6     347
  6640.7  347.82  6661.9  347.45  6668.9  348.82  6718.4  348.82  6821.1  351.28
#Mann= 11 ,-1 , 0
  4207.7      .1       0  4424.8     .05       0  4482.2      .1       0
  4581.5     .05       0  4706.8      .1       0  4917.3     .05       0
  4921.7      .1       0  4956.1    .035       0    5064      .1       0
    5195     .05       0  5399.8      .1       0
Bank Sta=4956.1,5064
XS Rating Curve= 0 ,0
Exp/Cntr=0.3,0.1

Type RM Length L Ch R = 1 ,5475    ,153,153,153
BEGIN DESCRIPTION:
Mapping XS 06982f86
END DESCRIPTION:
XS GIS Cut Line= 4
      2207716.39     13226233.06      2208417.68     13226132.88
      2209319.38     13225217.82      2209958.62     13224591.96
#Sta/Elev= 30
  4036.3   336.2  4239.7  336.22  4249.8  335.12  4691.6  333.42  4786.6  332.93
  4876.3  333.46  4956.3  332.02  4982.3  331.97  5003.4  329.23  5010.6  331.42
  5017.7  332.65  5024.8  331.52  5060.2  332.57  5199.3     332  5379.6  332.32
  5621.5  332.52  5703.6  333.76  5710.7  332.65  5929.9  333.98  5972.4  331.73
  5979.4   334.1  6031.7  334.93  6050.1  336.55  6071.3     336  6205.7  338.71
  6573.3  348.87  6686.5  350.25  6799.6  354.65  6806.8  353.53    6924   358.3
#Mann= 9 ,-1 , 0
  4036.3     .05       0  4691.6      .1       0  4786.6     .05       0
  4956.3      .1       0  4982.3    .035       0  5017.7      .1       0
  5199.3     .05       0  5379.6     .08       0  5621.5      .1       0
Bank Sta=4982.3,5010.6
XS Rating Curve= 0 ,0
Exp/Cntr=0.3,0.1

Type RM Length L Ch R = 1 ,5322    ,155,155,155
BEGIN DESCRIPTION:
Mapping XS ec75b47e
END DESCRIPTION:
XS GIS Cut Line= 2
      2208131.24     13226620.06      2210102.98     13224642.04
#Sta/Elev= 30
  4188.1  334.47  4503.6     333  4508.7  333.16    4639   332.2    4652  332.36
  4774.4     332  4795.4   332.1  4909.8  331.52  4965.7  330.12  5000.8  326.75
  5029.3   330.4    5192  333.46  5262.7  333.07  5278.6  331.48  5821.3  332.02
  5913.2  334.03  5934.4  332.98  5969.8  335.12    5991  333.89  5998.1  335.67
  6040.5  334.77  6054.6  336.25  6132.4  336.45  6167.8  338.72  6174.8  337.34
  6394.1  342.83  6535.5  348.93  6733.5  352.87  6747.6  354.56    6981  362.32
#Mann= 11 ,-1 , 0
  4188.1     .08       0  4503.6      .1       0  4508.7     .08       0
    4639      .1       0    4652     .08       0  4774.4      .1       0
  4795.4     .08       0  4909.8      .1       0  4965.7    .035       0
  5029.3      .1       0  5278.6     .08       0
#XS Ineff= 2 , 0
                         5234.82          333.38
Permanent Ineff=
       F       F
Bank Sta=4965.7,5029.3
XS Rating Curve= 0 ,0
Exp/Cntr=0.3,0.1

Type RM Length L Ch R = 1 ,5167    ,411,411,411
BEGIN DESCRIPTION:
UNT 009 IN RACR 5.0
END DESCRIPTION:
XS GIS Cut Line= 2
      2208210.65     13226747.35      2210080.84     13224823.72
#Sta/Elev= 30
  4226.2  333.62  4683.9  331.21  4744.9  330.91    4960  329.93  5002.1  325.86
  5023.5  328.31    5059  329.99  5108.8  330.47  5154.4  330.32  5242.7  330.55
  5447.9  331.43  5535.4  330.71  5546.9  331.69  5561.1  336.71  5568.1  332.98
  5575.2  330.76  5610.5  331.06  5624.6  329.82  5681.2  331.02  6013.6  331.77
  6070.1  334.09    6155  334.67  6338.9  339.33  6367.2   341.2  6586.4  346.51
  6600.5  347.89  6699.6  351.27  6720.9  350.89    6841  354.94  6909.1  356.99
#Mann= 10 ,-1 , 0
  4226.2     .05       0  4683.9     .08       0  4744.9     .05       0
    4960    .035       0    5059     .05       0  5108.8     .08       0
  5154.4     .05       0  5242.7     .08       0  5535.4     .05       0
    6841     .08       0
#XS Ineff= 2 , 0
                         5561.61           336.8
Permanent Ineff=
       F       F
Bank Sta=4960,5059
XS Rating Curve= 0 ,0
Exp/Cntr=0.3,0.1

Type RM Length L Ch R = 1 ,4756    ,672,672,672
BEGIN DESCRIPTION:
UNT 009 IN RACR 4.0
END DESCRIPTION:
XS GIS Cut Line= 3
       2208284.1     13226814.16      2209092.29     13226500.24
      2210213.53     13225205.47
#Sta/Elev= 30
  4358.7  332.75  4584.3  329.26  4952.6  327.69  4976.1  326.81  5000.3  323.99
  5038.4  326.83    5338   328.5  5611.2  327.53  5712.6   327.6  5771.1   327.8
  5785.4  326.56  5812.9  327.28  5834.7  325.83  5839.9  326.75  5855.6  328.21
  6082.6  328.48  6231.8  331.28  6252.6  330.66  6366.6  334.17  6380.9  333.38
  6387.5  334.38    6473  336.67  6486.9  337.88  6550.9  338.17  6614.5  341.01
    6699  342.54  6727.5  344.64  6777.9  344.99  6841.5  347.82  6938.5  350.49
#Mann= 6 ,-1 , 0
  4358.7     .05       0  4976.1    .035       0  5038.4     .05       0
  5611.2      .1       0  5712.6     .08       0  5839.9     .05       0
#XS Ineff= 2 , 0
                          5341.8          328.45
Permanent Ineff=
       F       F
Bank Sta=4976.1,5038.4
XS Rating Curve= 0 ,0
Exp/Cntr=0.3,0.1

Type RM Length L Ch R = 1 ,4084    ,604,604,604
BEGIN DESCRIPTION:
UNT 009 IN RACR 3.0
END DESCRIPTION:
XS GIS Cut Line= 4
      2208280.25     13227605.76      2208558.07     13227518.94
      2209504.25     13226989.42       2210223.7     13225879.91
#Sta/Elev= 30
  4092.9  327.13  4203.4  326.47  4518.3  321.36  4699.2  320.31  4848.3  321.73
  4951.1  324.17    4967  323.61  4988.7  321.13  5002.4  320.78  5032.1  323.46
  5059.7  324.51  5237.7  323.43  5522.8  324.99  5880.1  324.13  6061.4  324.02
  6079.1  324.73  6093.7  323.23  6120.5  324.05  6145.1  323.46    6151  325.17
  6259.8  325.19  6350.3  326.14  6394.9  326.27  6471.4  326.62  6477.4   327.3
  6492.5  327.04  6528.8   328.2  6632.9   329.1  6667.6  329.89  6790.6  332.71
#Mann= 10 ,-1 , 0
  4092.9     .05       0    4967    .035       0  5032.1     .05       0
  5880.1      .1       0  6061.4     .08       0  6120.5     .05       0
  6350.3      .1       0  6394.9     .05       0  6632.9      .1       0
  6667.6     .05       0
#XS Ineff= 2 , 0
       0 4951.21   324.2               0
Permanent Ineff=
       T       F
Bank Sta=4967,5032.1
XS Rating Curve= 0 ,0
Exp/Cntr=0.3,0.1

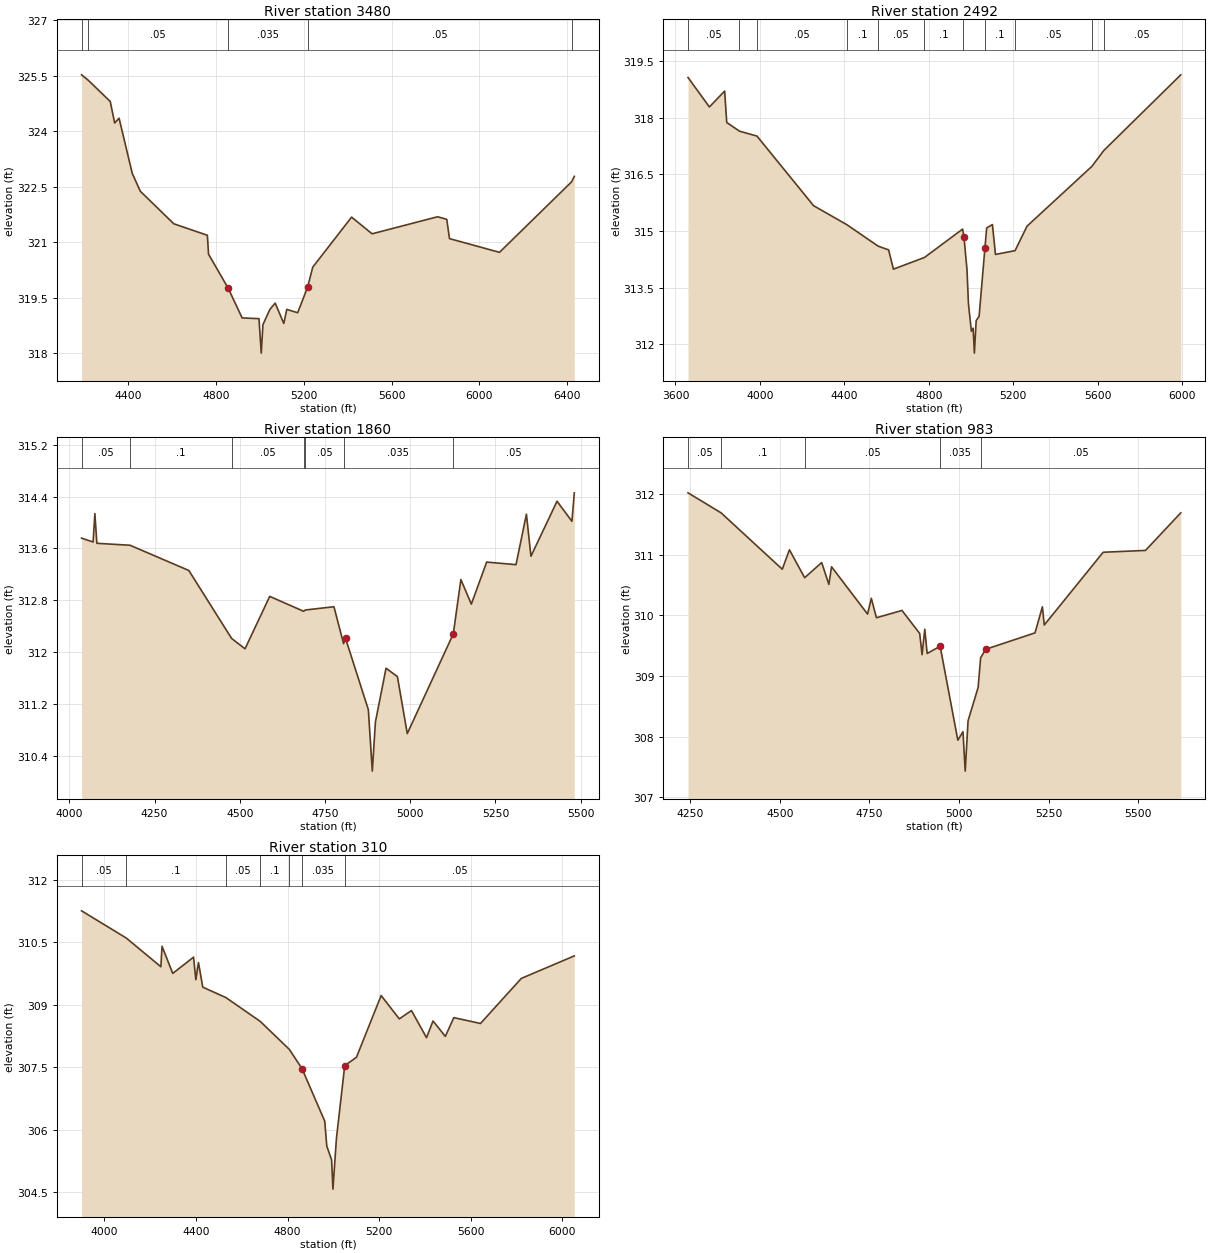
Type RM Length L Ch R = 1 ,3480    ,988,988,988
BEGIN DESCRIPTION:
Mapping XS bf1e147a
END DESCRIPTION:
XS GIS Cut Line= 4
      2208497.26      13227935.6      2208783.76     13227952.96
       2209747.3     13227631.78      2210015.97     13226730.46
#Sta/Elev= 30
    4189  325.52  4216.6  325.39  4319.7   324.8  4339.7  324.22  4359.8  324.35
  4419.9  322.86  4456.3  322.38    4609   321.5  4761.8  321.19  4767.1  320.68
  4856.7  319.76    4920  318.96  4996.7  318.94    5007  318.01  5014.8  318.78
  5046.4  319.19  5070.5  319.36  5109.7  318.81  5123.2  319.19  5172.9   319.1
  5218.1  319.79  5241.5  320.33  5418.3  321.68  5511.6  321.23  5809.9  321.69
  5851.6  321.62    5864   321.1  6091.6  320.73  6419.4  322.63  6432.2  322.78
#Mann= 5 ,-1 , 0
    4189      .1       0  4216.6     .05       0  4856.7    .035       0
  5218.1     .05       0  6419.4      .1       0
Bank Sta=4856.7,5218.1
XS Rating Curve= 0 ,0
Exp/Cntr=0.3,0.1

Type RM Length L Ch R = 1 ,2492    ,632,632,632
BEGIN DESCRIPTION:
Mapping XS 41f27107
END DESCRIPTION:
XS GIS Cut Line= 4
       2208464.7     13228949.63      2209393.54     13228880.18
      2209966.45     13228437.47      2210027.15     13227761.16
#Sta/Elev= 30
  3659.4  319.06  3760.7  318.28  3832.9   318.7  3842.9  317.87  3903.1  317.64
  3986.1  317.51  4254.1  315.67    4411  315.17  4559.9   314.6  4609.8   314.5
  4632.4  313.99  4779.6   314.3  4960.3  315.05  4966.6  314.85  4981.1  313.98
  4987.9  313.08  5001.9  312.35  5010.1  312.43  5016.1  311.77  5024.6  312.63
  5038.4  312.74  5066.2  314.56  5074.4  315.08  5101.6  315.17    5116  314.38
  5208.7  314.48  5265.9  315.13  5572.9  316.71  5629.4  317.13  5993.9  319.13
#Mann= 11 ,-1 , 0
  3659.4     .05       0  3903.1      .1       0  3986.1     .05       0
    4411      .1       0  4559.9     .05       0  4779.6      .1       0
  4960.3    .035       0  5066.2      .1       0  5208.7     .05       0
  5572.9      .1       0  5629.4     .05       0
Bank Sta=4966.6,5066.2
XS Rating Curve= 0 ,0
Exp/Cntr=0.3,0.1

Type RM Length L Ch R = 1 ,1860    ,877,877,877
BEGIN DESCRIPTION:
Mapping XS ef0df86d
END DESCRIPTION:
XS GIS Cut Line= 4
      2209454.32     13229461.77      2210105.34     13229288.17
      2210226.87     13228854.14       2210097.3     13228560.44
#Sta/Elev= 30
    4036  313.76  4069.9   313.7  4075.1  314.14  4080.9  313.68  4178.2  313.65
  4350.7  313.26  4476.2  312.21  4515.6  312.05    4588  312.86  4687.3  312.63
  4692.8  312.65  4776.4   312.7  4804.6  312.13  4810.5  312.21  4877.3  311.11
  4888.9  310.16  4898.1  310.92  4929.2  311.75  4962.6  311.62  4991.5  310.74
  5126.5  312.28  5148.8  313.12  5179.4  312.74  5224.4  313.39  5310.5  313.35
    5341  314.13  5354.3  313.48  5430.8  314.33  5474.5  314.02  5481.5  314.46
#Mann= 7 ,-1 , 0
    4036     .05       0  4178.2      .1       0  4476.2     .05       0
  4687.3      .1       0  4692.8     .05       0  4804.6    .035       0
  5126.5     .05       0
Bank Sta=4810.5,5126.5
XS Rating Curve= 0 ,0
Exp/Cntr=0.3,0.1

Type RM Length L Ch R = 1 ,983     ,673,673,673
BEGIN DESCRIPTION:
Mapping XS 0c0842c7
END DESCRIPTION:
XS GIS Cut Line= 4
        2210305.     13229435.74      2210808.47     13229418.38
      2211077.56     13229105.88      2210929.99     13228671.83
#Sta/Elev= 30
  4243.9  312.02  4336.1  311.69  4506.8  310.76  4526.8  311.08  4569.3  310.62
  4616.8  310.87  4636.8  310.51  4644.3   310.8  4744.8  310.02  4755.2  310.28
  4769.5  309.96  4840.8  310.08  4890.2   309.7  4896.8  309.35  4904.4  309.77
    4911  309.37  4947.2  309.49  4996.6  307.94  5010.9  308.08  5017.2  307.43
  5025.1  308.26  5053.2  308.81  5060.2   309.3  5074.5  309.44  5211.8  309.71
  5232.5  310.14  5237.7  309.84    5402  311.04  5520.1  311.07  5618.5  311.69
#Mann= 5 ,-1 , 0
  4243.9     .05       0  4336.1      .1       0  4569.3     .05       0
  4947.2    .035       0  5060.2     .05       0
Bank Sta=4947.2,5074.5
XS Rating Curve= 0 ,0
Exp/Cntr=0.3,0.1

Type RM Length L Ch R = 1 ,310     ,0,0,0
BEGIN DESCRIPTION:
UNT 009 IN RACR 1.0
END DESCRIPTION:
XS GIS Cut Line= 4
      2210452.55     13229557.26      2211398.74     13229678.79
      2211676.52      13229496.5      2211268.55     13228732.64
#Sta/Elev= 30
  3899.9  311.25  4094.6   310.6  4246.4  309.91  4251.4   310.4  4298.3  309.75
  4389.1  310.14  4399.1   309.6  4410.6  310.01  4429.4  309.42  4530.7  309.17
  4680.4   308.6  4807.3  307.93  4862.6  307.47    4962  306.21  4971.1  305.61
  4992.1  305.28  4997.9  304.58  5013.2   305.8  5049.4  307.54  5100.6  307.74
  5208.4  309.22  5287.7  308.66  5340.8  308.86  5406.6  308.21  5435.1  308.61
  5488.8  308.24  5525.8  308.69  5642.4  308.55  5820.6  309.63  6052.1  310.17
#Mann= 7 ,-1 , 0
  3899.9     .05       0  4094.6      .1       0  4530.7     .05       0
  4680.4      .1       0  4807.3     .05       0  4862.6    .035       0
  5049.4     .05       0
Bank Sta=4862.6,5049.4
XS Rating Curve= 0 ,0
Exp/Cntr=0.3,0.1

Chan Stop Cuts=-1
Use User Specified Reach Order=0
Composite Channel Slope=5