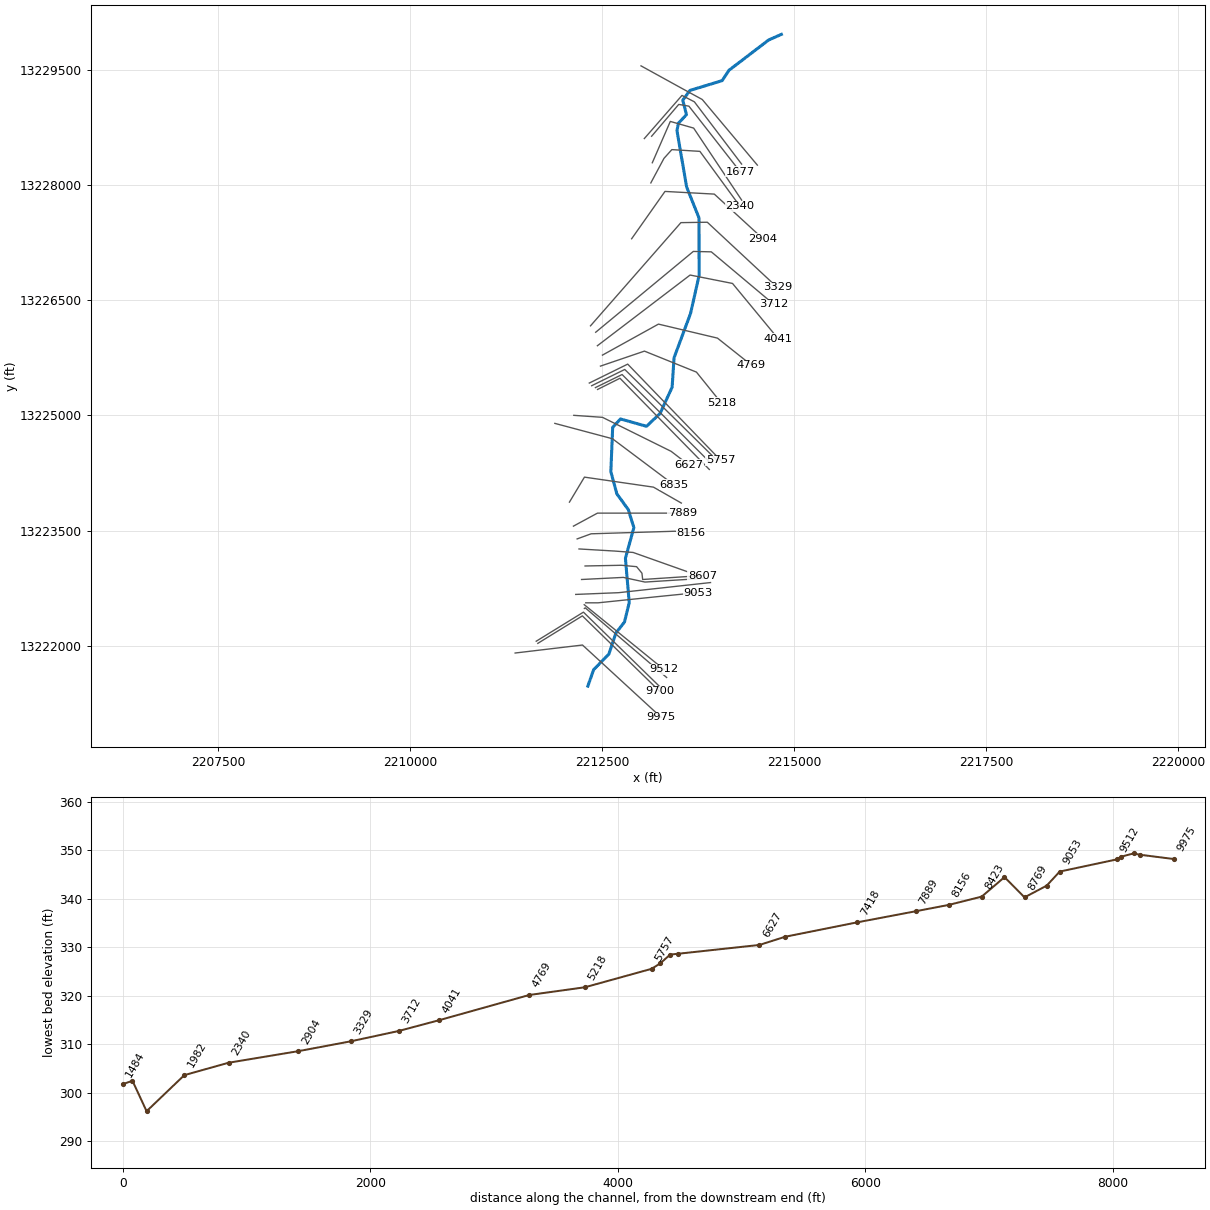
--- UNT 010 IN RACR.prj (project) ---

Proj Title=UNT 010 IN RACR Base Level Engineering
Current Plan=p01
Default Exp/Contr=0.3,0.1
English Units
Geom File=g01
Flow File=f01
Plan File=p01
Y Axis Title=Elevation
X Axis Title(PF)=Main Channel Distance
X Axis Title(XS)=Station
BEGIN DESCRIPTION:
UNT 010 IN RACR
END DESCRIPTION:
DSS Export Rating Curves= 0
DSS Export Rating Curve Sorted= 0
DSS Export Volume Flow Curves= 0
DXF OffsetX= 0
DXF OffsetY= 0
DXF ScaleX= 1
DXF ScaleY= 10

--- UNT 010 IN RACR.p01 (plan) ---

Plan Title=Multiple Run
Short Identifier=Multiple
Geom File=g01
Flow File=f01
Subcritical Flow
K Sum by GR= 0
Std Step Tol= 0.01
Critical Tol= 0.01
Num of Std Step Trials= 20
Max Error Tol= 0.3
Flow Tol Ratio= 0.001
Split Flow NTrial= 30
Split Flow Tol= 0.02
Split Flow Ratio= 0.02
Log Output Level= 0
Friction Slope Method= 1
Unsteady Friction Slope Method= 2
Unsteady Bridges Friction Slope Method= 1
Parabolic Critical Depth
Global Vel Dist=  1 , 1 , 1
Global Log Level= 0
CheckData=True
Encroach Param= -1, 0, 0, 0
BEGIN DESCRIPTION:
Multiple Run
END DESCRIPTION:

--- UNT 010 IN RACR.f01 (steady flow) ---

Flow Title=Multiple
Program Version=4.10
Number of Profiles= 7
Profile Names=10-year,25-year,50-year,1pct_min,100-year,1pct_plu,500-year
River Rch & RM=UNT 010 IN RACR,Reach-1         ,9975
     224     313     388     354     479     647     741
River Rch & RM=UNT 010 IN RACR,Reach-1         ,9550
     263     370     460     421     570     771     887
River Rch & RM=UNT 010 IN RACR,Reach-1         ,5907
     347     495     620     572     773    1046    1221
Boundary for River Rch & Prof#=UNT 010 IN RACR,Reach-1         , 1
Up Type= 0
Dn Type= 3
Dn Slope=0.003
Boundary for River Rch & Prof#=UNT 010 IN RACR,Reach-1         , 2
Up Type= 0
Dn Type= 3
Dn Slope=0.003
Boundary for River Rch & Prof#=UNT 010 IN RACR,Reach-1         , 3
Up Type= 0
Dn Type= 3
Dn Slope=0.003
Boundary for River Rch & Prof#=UNT 010 IN RACR,Reach-1         , 4
Up Type= 0
Dn Type= 3
Dn Slope=0.003
Boundary for River Rch & Prof#=UNT 010 IN RACR,Reach-1         , 5
Up Type= 0
Dn Type= 3
Dn Slope=0.003
Boundary for River Rch & Prof#=UNT 010 IN RACR,Reach-1         , 6
Up Type= 0
Dn Type= 3
Dn Slope=0.003
Boundary for River Rch & Prof#=UNT 010 IN RACR,Reach-1         , 7
Up Type= 0
Dn Type= 3
Dn Slope=0.003
DSS Import GetInterval= 0
DSS Import GetPeak= 0
DSS Import FillOption= 0

--- UNT 010 IN RACR.g01 (geometry) ---

Geom Title=Existing Conditions
Program Version=4.10

River Reach=UNT 010 IN RACR ,Reach-1
Reach XY= 30
      2212317.41      13221476.5      2212392.44     13221689.76
      2212590.39     13221891.81      2212683.63     13222168.38
      2212794.05     13222310.57      2212856.03     13222562.65
      2212806.55     13223140.26      2212916.62     13223539.73
      2212843.72     13223774.62      2212695.12      13223979.3
      2212616.71     13224268.03      2212640.55     13224845.68
      2212742.62     13224954.39      2213081.66     13224858.87
      2213258.08     13225026.87       2213414.6     13225368.14
      2213439.79     13225751.46      2213654.49     13226328.19
      2213765.77     13226822.37      2213764.71     13227571.32
      2213603.75     13227973.39      2213477.82     13228705.74
      2213495.24     13228803.18      2213601.42     13228916.82
      2213552.72     13229103.55      2213645.77     13229231.33
      2214066.31     13229359.25       2214154.1     13229493.42
      2214671.64     13229888.71      2214837.19     13229961.73

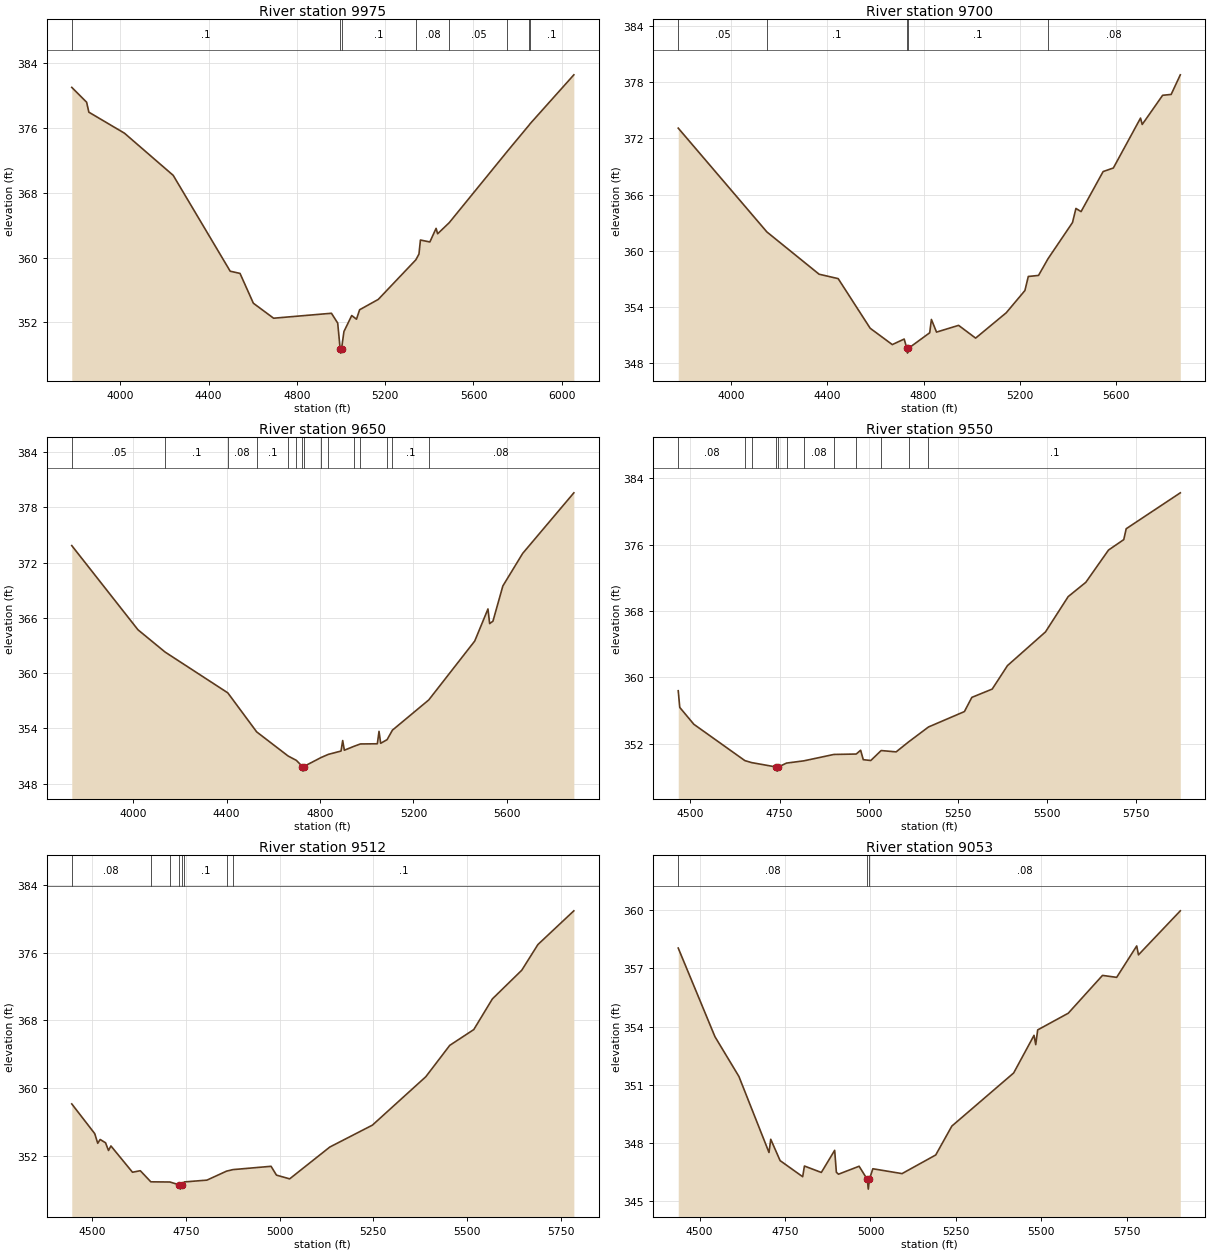
Type RM Length L Ch R = 1 ,9975    ,275,275,275
BEGIN DESCRIPTION:
UNT 010 IN RACR 17.0
END DESCRIPTION:
XS GIS Cut Line= 3
      2211370.88     13221907.08      2212247.66     13222011.25
      2213271.93     13221069.44
#Sta/Elev= 30
  3780.4  381.01  3847.7  379.18  3857.8  377.95  4018.9  375.36    4240  370.15
  4498.1  358.32  4542.6  358.05    4603  354.37  4694.7  352.52  4956.7  353.13
  4985.1  351.92  4996.3  348.71    4999  348.21  5002.3  348.71  5013.4  350.88
  5048.6  352.85  5070.2   352.4  5084.3  353.56  5168.8  354.84  5339.2  359.73
  5353.2  360.44  5359.9  362.17  5402.5  361.93  5430.8  363.61  5437.8  362.94
  5490.3  364.31  5753.8  373.13  5851.6  376.34  5856.3  376.51  6054.8  382.56
#Mann= 8 ,-1 , 0
  3780.4      .1       0  4996.3     .07       0  5002.3      .1       0
  5339.2     .08       0  5490.3     .05       0  5753.8      .1       0
  5851.6     .05       0  5856.3      .1       0
Bank Sta=4996.3,5002.3
XS Rating Curve= 0 ,0
Exp/Cntr=0.3,0.1

Type RM Length L Ch R = 1 ,9700    ,50,50,50
BEGIN DESCRIPTION:
Mapping XS 8e7be33e
END DESCRIPTION:
XS GIS Cut Line= 3
      2211666.09     13222032.97      2212245.92     13222390.59
       2213252.8     13221408.02
#Sta/Elev= 30
  3779.8  373.08  4148.7  362.01  4365.7  357.51    4445  357.04  4578.1  351.75
  4670.1  350.01  4719.5   350.6  4730.6   349.6  4733.4   349.1  4736.6   349.6
  4825.7  351.27  4832.7  352.69    4854  351.34  4945.8  352.06  5016.6   350.7
  5143.9   353.4  5221.6  355.77  5235.7  357.27  5278.2  357.38    5318  359.17
  5419.6  363.02  5433.8  364.52  5455.1  364.18  5546.9  368.45  5589.4  368.83
  5702.5  374.15  5709.5  373.47  5794.4  376.58  5829.8  376.67  5867.9  378.76
#Mann= 5 ,-1 , 0
  3779.8     .05       0  4148.7      .1       0  4730.6     .07       0
  4736.6      .1       0    5318     .08       0
Bank Sta=4730.6,4736.6
XS Rating Curve= 0 ,0
Exp/Cntr=0.3,0.1

Type RM Length L Ch R = 1 ,9650    ,100,100,100
BEGIN DESCRIPTION:
Mapping XS af47f03e
END DESCRIPTION:
XS GIS Cut Line= 3
      2211645.23     13222060.74      2212259.81      13222439.2
      2213282.06      13221441.2
#Sta/Elev= 30
  3736.6  373.86  4020.1  364.72  4136.3   362.3  4404.9  357.87  4528.6  353.63
  4663.3  351.01  4698.5  350.54  4724.3  349.87    4727  349.37  4730.3  349.87
  4804.6  350.85  4835.6  351.19  4889.8  351.55    4897  352.69    4904  351.64
  4945.9  352.07  4972.8  352.32  5045.4  352.34  5052.6  353.69  5059.6  352.39
  5087.2  352.79    5110  353.82  5265.6   357.1  5462.6   363.5  5519.2  366.98
  5526.4  365.39  5540.5  365.65    5583  369.48  5667.8  373.01    5887  379.59
#Mann= 15 ,-1 , 0
  3736.6     .05       0  4136.3      .1       0  4404.9     .08       0
  4528.6      .1       0  4663.3     .08       0  4698.5      .1       0
  4724.3     .07       0  4730.3      .1       0  4804.6     .08       0
  4835.6      .1       0  4945.9     .08       0  4972.8      .1       0
  5087.2     .08       0    5110      .1       0  5265.6     .08       0
Bank Sta=4724.3,4730.3
XS Rating Curve= 0 ,0
Exp/Cntr=0.3,0.1

Type RM Length L Ch R = 1 ,9550    ,38,38,38
BEGIN DESCRIPTION:
Mapping XS ca6101c1
END DESCRIPTION:
XS GIS Cut Line= 3
      2212272.23     13222487.74      2212284.11     13222494.76
      2213342.94     13221588.68
#Sta/Elev= 30
  4465.7  358.39    4470  356.38  4509.4  354.35  4652.4  349.97  4671.1  349.73
  4740.2   349.2  4742.9   348.7  4746.2   349.2  4769.3  349.67  4817.8  349.94
  4901.9  350.71  4964.6  350.76    4977  351.22  4984.4  350.08  5005.5  349.98
  5034.5  351.18  5076.5  351.02  5111.4  352.22  5167.1  354.02  5267.9  355.88
  5288.7  357.59  5345.8  358.59  5388.6  361.42  5495.1  365.48  5558.8  369.74
  5608.2  371.46  5671.8  375.35  5714.6  376.61  5721.4  377.92  5873.1  382.25
#Mann= 12 ,-1 , 0
  4465.7     .08       0  4652.4      .1       0  4671.1     .08       0
  4740.2     .07       0  4746.2     .08       0  4769.3      .1       0
  4817.8     .08       0  4901.9      .1       0  4964.6     .08       0
  5034.5      .1       0  5111.4     .08       0  5167.1      .1       0
Bank Sta=4740.2,4746.2
XS Rating Curve= 0 ,0
Exp/Cntr=0.3,0.1

Type RM Length L Ch R = 1 ,9512    ,459,459,459
BEGIN DESCRIPTION:
UNT 010 IN RACR 16.0
END DESCRIPTION:
XS GIS Cut Line= 2
      2212270.22     13222536.43       2213308.4     13221692.69
#Sta/Elev= 30
  4446.4  358.16  4507.6  354.66  4515.6  353.52    4522  353.97  4536.4  353.58
  4544.3  352.67  4550.7  353.21  4608.2  350.11    4629  350.29  4657.1  348.98
  4707.8  348.96  4733.1  348.62  4735.8  348.12  4739.1  348.62  4746.5  348.97
  4806.5  349.18  4858.9  350.24  4876.1  350.42  4977.4  350.81  4991.8  349.77
    5027  349.33    5134  353.08  5247.5  355.66  5389.7  361.36  5453.6  365.06
  5517.6  366.92  5567.1  370.53  5645.4  373.91  5688.5  376.94  5784.2  380.91
#Mann= 8 ,-1 , 0
  4446.4     .08       0  4657.1      .1       0  4707.8     .08       0
  4733.1     .07       0  4739.1     .08       0  4746.5      .1       0
  4858.9     .08       0  4876.1      .1       0
Bank Sta=4733.1,4739.1
XS Rating Curve= 0 ,0
Exp/Cntr=0.3,0.1

Type RM Length L Ch R = 1 ,9053    ,105,105,105
BEGIN DESCRIPTION:
Mapping XS 5285980d
END DESCRIPTION:
XS GIS Cut Line= 4
      2212290.22     13222560.73      2212451.11     13222560.73
      2213210.04     13222639.66      2213753.09     13222694.27
#Sta/Elev= 30
  4437.3  358.05  4544.8  353.48  4614.9  351.43    4703  347.51  4708.1  348.19
  4735.5  347.09  4801.6  346.26  4806.7  346.81  4856.2  346.48  4895.2  347.62
  4900.2  346.49  4906.5  346.39  4966.8   346.8  4990.8  346.12  4993.6  345.62
  4996.8  346.12    5007  346.67  5092.4  346.42    5191  347.38  5238.2  348.87
  5419.2  351.61  5478.8  353.55  5483.8  353.07  5489.5  353.83    5579  354.69
  5679.2  356.64  5720.7  356.54  5779.4  358.16  5784.5   357.7    5907  359.97
#Mann= 3 ,-1 , 0
  4437.3     .08       0  4990.8     .07       0  4996.8     .08       0
Bank Sta=4990.8,4996.8
XS Rating Curve= 0 ,0
Exp/Cntr=0.3,0.1

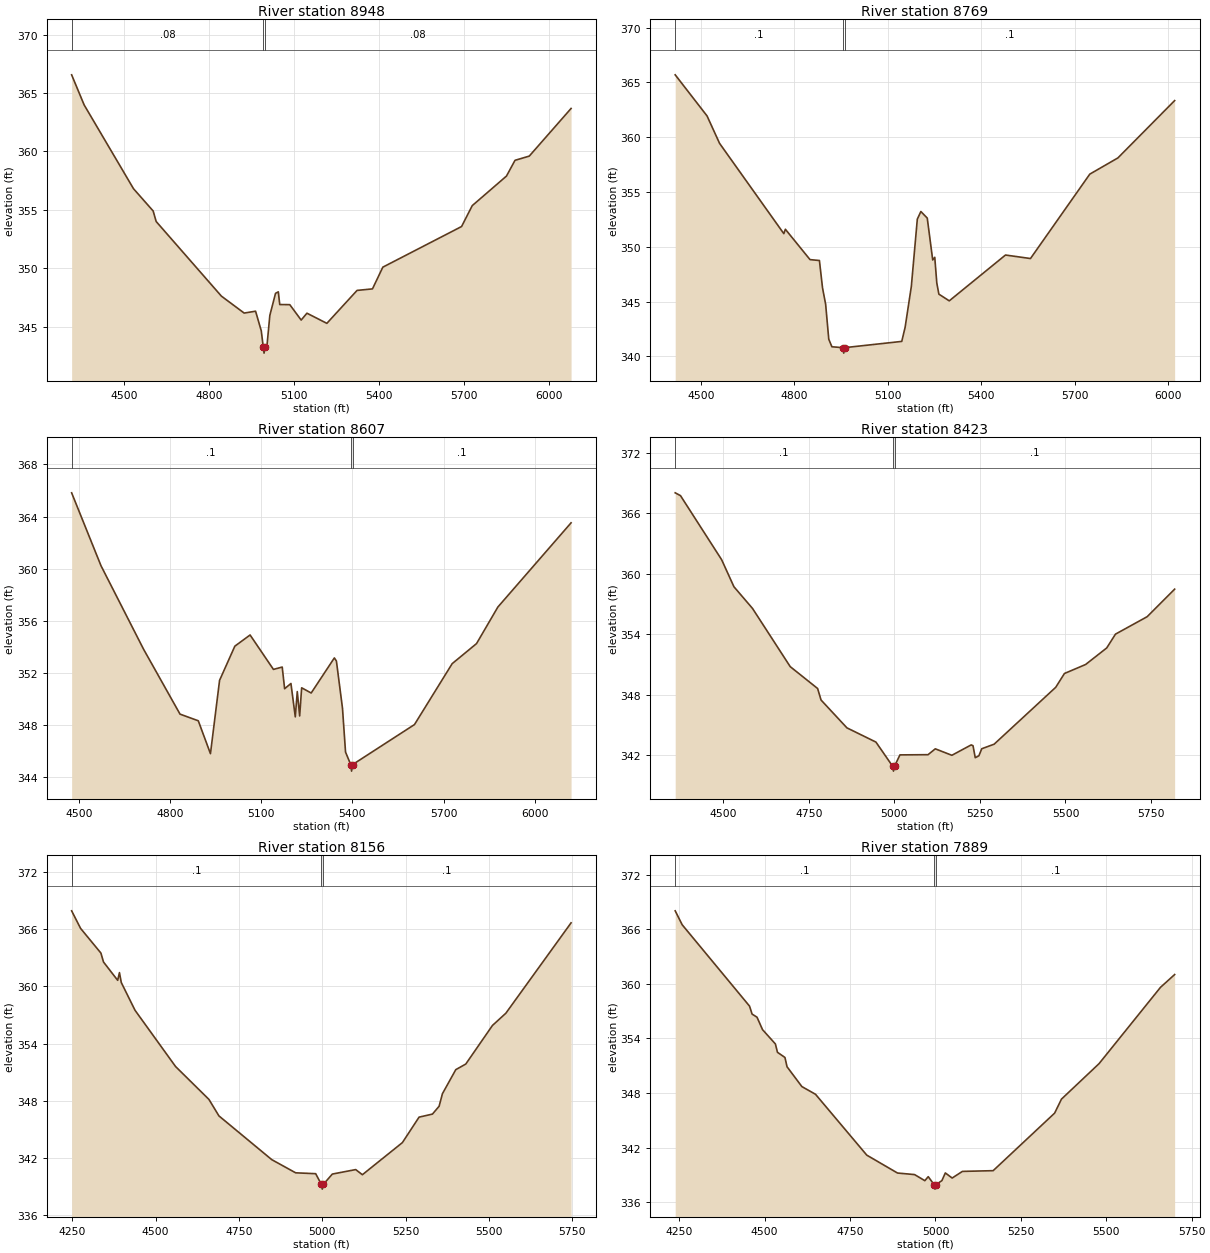
Type RM Length L Ch R = 1 ,8948    ,179,179,179
BEGIN DESCRIPTION:
UNT 010 IN RACR 15.0
END DESCRIPTION:
XS GIS Cut Line= 3
      2212159.64     13222670.02      2212718.14     13222692.67
      2213914.35     13222824.43
#Sta/Elev= 30
  4315.9  366.55  4360.1  363.97  4534.2   356.8  4603.6  354.89  4614.2  353.99
  4844.4   347.6  4924.7  346.15    4965  346.31  4985.1  344.63  4992.2  343.22
  4994.9  342.72  4998.2  343.22  5005.2  343.35  5015.3  345.95  5035.4  347.84
  5045.2  347.97  5050.3  346.88  5085.7  346.87  5125.9  345.55  5146.2  346.14
  5216.5  345.27  5323.1  348.09  5377.5  348.22    5414  350.08  5691.9  353.56
  5729.6  355.35  5850.3  357.88  5880.5  359.23  5930.8  359.59  6078.3  363.67
#Mann= 3 ,-1 , 0
  4315.9     .08       0  4992.2     .07       0  4998.2     .08       0
Bank Sta=4992.2,4998.2
XS Rating Curve= 0 ,0
Exp/Cntr=0.3,0.1

Type RM Length L Ch R = 1 ,8769    ,162,162,162
BEGIN DESCRIPTION:
UNT 010 IN RACR 14.0
END DESCRIPTION:
XS GIS Cut Line= 4
      2212235.62     13222864.31      2212778.97     13222891.63
      2213061.29     13222830.91      2213829.34     13222879.48
#Sta/Elev= 30
    4418  365.69  4520.2  361.94  4560.3  359.44  4766.5   351.2  4771.5   351.6
  4850.6  348.83  4880.7  348.75  4890.7  346.25  4900.7  344.75  4910.7  341.57
  4920.7  340.88  4955.9   340.8  4958.7   340.3  4961.9   340.8  5144.9  341.37
  5155.7  342.66  5175.6  346.38  5194.8  352.52  5206.2  353.22  5226.7  352.62
  5244.2   348.8  5250.8  349.04  5257.3   346.7    5264  345.68  5297.3  345.07
  5477.7  349.25  5557.9  348.93  5748.2  356.63  5838.4  358.11  6020.4  363.34
#Mann= 3 ,-1 , 0
    4418      .1       0  4955.9     .07       0  4961.9      .1       0
Bank Sta=4955.9,4961.9
XS Rating Curve= 0 ,0
Exp/Cntr=0.3,0.1

Type RM Length L Ch R = 1 ,8607    ,184,184,184
BEGIN DESCRIPTION:
Mapping XS 0c545d0d
END DESCRIPTION:
XS GIS Cut Line= 6
      2212281.14     13223040.38      2212754.68     13223049.48
      2212952.01     13223031.27      2213021.83     13222946.27
      2213030.93      13222864.3      2213808.06     13222915.91
#Sta/Elev= 30
  4476.3  365.82  4572.9  360.23  4712.9  353.83  4832.9  348.85    4893  348.34
    4933  345.82    4963  351.44  5013.2  354.06  5063.4  354.92  5140.2  352.28
  5169.1  352.46    5177   350.8  5197.8   351.2  5212.1  348.64  5218.6  350.58
  5226.5  348.71    5233  350.87  5264.4  350.47  5340.6  353.16  5347.4  352.92
  5367.4   349.3  5377.4  345.94  5394.5  344.98  5397.2  344.48  5400.5  344.98
  5604.2  348.05  5728.2  352.72  5808.4  354.26  5878.5  357.06  6119.4  363.52
#Mann= 3 ,-1 , 0
  4476.3      .1       0  5394.5     .07       0  5400.5      .1       0
Bank Sta=5394.5,5400.5
XS Rating Curve= 0 ,0
Exp/Cntr=0.3,0.1

Type RM Length L Ch R = 1 ,8423    ,267,267,267
BEGIN DESCRIPTION:
Mapping XS fcec8847
END DESCRIPTION:
XS GIS Cut Line= 4
      2212202.23     13223261.98      2212666.65     13223234.66
      2212906.47     13223216.45      2213616.87     13222964.47
#Sta/Elev= 30
  4359.5  368.04    4375  367.76  4495.2  361.41  4531.1  358.73  4585.4  356.58
  4695.6  350.81  4775.7  348.64  4785.7   347.5  4861.3  344.74  4946.1  343.33
  4994.6  340.95  4997.3  340.45  5000.6  340.95  5016.3  342.06  5098.4  342.08
  5119.6  342.66    5168  342.02  5224.5  343.05  5229.8  342.97  5236.3  341.78
  5246.9  341.97  5255.4  342.67  5291.5  343.12  5471.5  348.76    5497  350.13
  5558.8  351.02  5620.5  352.66  5646.1  354.03  5738.7  355.76    5819  358.49
#Mann= 3 ,-1 , 0
  4359.5      .1       0  4994.6     .07       0  5000.6      .1       0
Bank Sta=4994.6,5000.6
XS Rating Curve= 0 ,0
Exp/Cntr=0.3,0.1

Type RM Length L Ch R = 1 ,8156    ,267,267,267
BEGIN DESCRIPTION:
UNT 010 IN RACR 13.0
END DESCRIPTION:
XS GIS Cut Line= 4
      2212177.93     13223392.53      2212360.04      13223459.3
      2213449.86      13223492.7       2213662.4     13223471.44
#Sta/Elev= 30
  4248.2  367.93    4275  366.09    4336   363.5  4343.8  362.56  4386.3  360.64
  4391.6  361.45  4397.1  360.41  4438.3   357.5  4559.9   351.6    4660  348.15
    4690  346.42  4848.5  341.83  4920.1  340.45  4980.1  340.36  4997.1  339.24
  4999.9  338.74  5003.1  339.24  5030.1  340.32  5100.2  340.79  5120.2  340.25
  5240.2  343.62  5290.2  346.29  5330.3  346.61  5350.3  347.43  5360.3  348.75
  5400.3  351.27  5430.3  351.86  5510.4  355.91  5550.5  357.19  5746.1  366.67
#Mann= 3 ,-1 , 0
  4248.2      .1       0  4997.1     .07       0  5003.1      .1       0
Bank Sta=4997.1,5003.1
XS Rating Curve= 0 ,0
Exp/Cntr=0.3,0.1

Type RM Length L Ch R = 1 ,7889    ,471,471,471
BEGIN DESCRIPTION:
UNT 010 IN RACR 12.0
END DESCRIPTION:
XS GIS Cut Line= 4
      2212129.82     13223559.05      2212442.27      13223728.3
       2213210.5      13223728.3      2213549.02      13223728.3
#Sta/Elev= 30
  4238.1  368.04  4258.5  366.51  4455.7  357.56  4463.2  356.68  4477.6  356.34
  4493.8  354.97  4531.4   353.4  4537.5  352.48  4559.4  351.91  4565.5  350.89
  4608.9  348.71  4648.9  347.86  4798.9  341.17  4888.9   339.2  4938.9  339.03
  4968.9  338.36  4978.9   338.8  4995.9  337.93  4998.6  337.43  5001.9  337.93
  5018.9  338.37  5028.9  339.21  5048.9  338.65  5078.9  339.38  5168.9  339.46
  5348.9  345.79  5368.9  347.33  5478.9  351.23  5658.9  359.63  5700.2  361.03
#Mann= 3 ,-1 , 0
  4238.1      .1       0  4995.9     .07       0  5001.9      .1       0
Bank Sta=4995.9,5001.9
XS Rating Curve= 0 ,0
Exp/Cntr=0.3,0.1

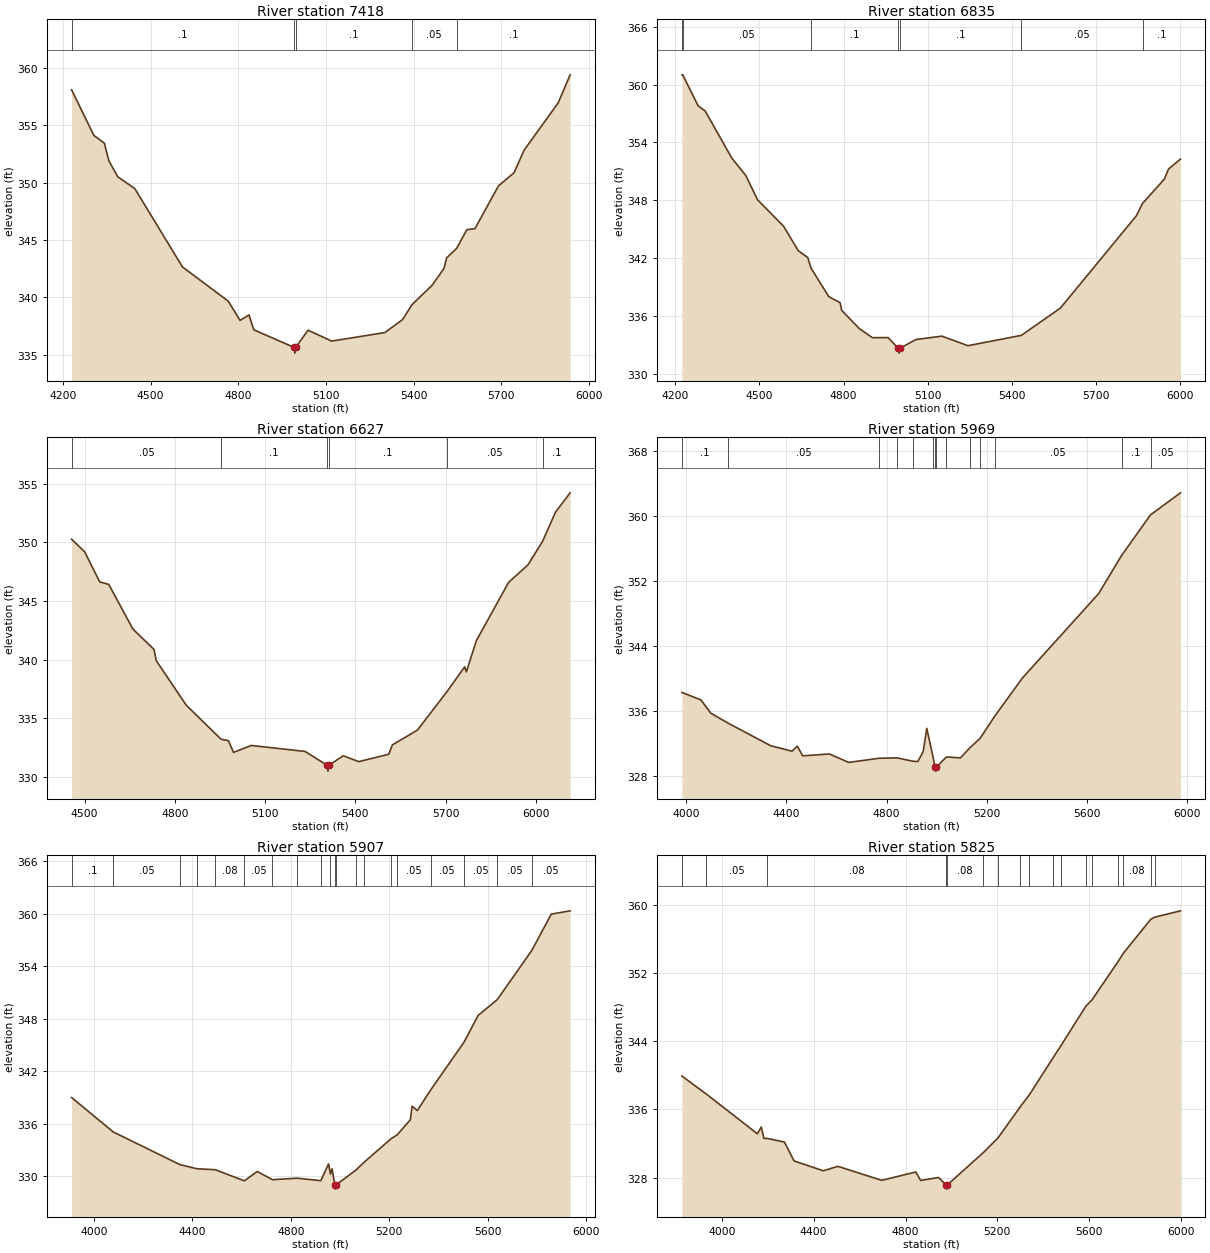
Type RM Length L Ch R = 1 ,7418    ,583,583,583
BEGIN DESCRIPTION:
UNT 010 IN RACR 11.0
END DESCRIPTION:
XS GIS Cut Line= 4
      2212077.69     13223871.53        2212273.     13224197.05
      2213171.44     13224066.84      2213534.33     13223859.47
#Sta/Elev= 30
  4229.8   358.1    4306  354.12  4341.8  353.45  4357.3  351.91  4387.6  350.52
  4445.9  349.49  4609.1  342.66  4765.7  339.68  4806.2     338  4836.5  338.48
  4853.2  337.18  4990.7  335.65  4993.4  335.15  4996.7  335.65  5038.6  337.15
  5119.4   336.2  5301.3  336.94  5361.9  338.07  5394.1  339.37    5463  341.06
  5503.4  342.52  5512.8  343.45  5546.8  344.27    5582  345.91  5609.4  345.99
    5690  349.72  5743.3  350.87  5777.9  352.84  5894.4  356.96  5935.2   359.4
#Mann= 5 ,-1 , 0
  4229.8      .1       0  4990.7     .07       0  4996.7      .1       0
  5394.1     .05       0  5546.8      .1       0
Bank Sta=4990.7,4996.7
XS Rating Curve= 0 ,0
Exp/Cntr=0.3,0.1

Type RM Length L Ch R = 1 ,6835    ,208,208,208
BEGIN DESCRIPTION:
UNT 010 IN RACR 10.0
END DESCRIPTION:
XS GIS Cut Line= 3
      2211887.72     13224896.85      2212637.72     13224696.85
      2213437.71     13224096.86
#Sta/Elev= 30
  4224.1  361.01  4226.9  361.01  4281.7   357.8  4306.9  357.26    4402  352.37
  4451.8  350.57  4493.2  348.07  4586.3  345.32  4638.1   342.8  4672.4  342.07
  4684.1  340.97  4747.4  338.02  4787.5   337.4  4793.3   336.6  4855.4  334.73
  4902.6  333.77  4958.9  333.78  4994.7  332.67  4997.5  332.17  5000.7  332.67
  5057.6  333.58  5150.3  333.93    5243  332.94  5433.1  334.01  5572.2  336.83
    5843   346.4    5865  347.68    5943  350.21  5957.6  351.25  6000.3  352.28
#Mann= 7 ,-1 , 0
  4224.1      .1       0  4226.9     .05       0  4684.1      .1       0
  4994.7     .07       0  5000.7      .1       0  5433.1     .05       0
    5865      .1       0
Bank Sta=4994.7,5000.7
XS Rating Curve= 0 ,0
Exp/Cntr=0.3,0.1

Type RM Length L Ch R = 1 ,6627    ,658,658,658
BEGIN DESCRIPTION:
Mapping XS d5336167
END DESCRIPTION:
XS GIS Cut Line= 4
      2212134.48     13225001.57      2212507.72     13224975.53
      2213401.82     13224532.83      2213627.52     13224359.21
#Sta/Elev= 30
  4456.9  350.26  4500.2   349.2  4550.4  346.62  4580.4  346.41  4660.6   342.6
  4730.8  340.86    4738  339.91    4838   336.1  4954.1  333.19  4978.1  333.08
    4995  332.08  5054.2  332.67  5232.8  332.16    5306  330.98  5308.7  330.48
    5312  330.98  5359.4  331.79  5411.3  331.29  5510.8  331.92  5522.9  332.72
  5606.1  333.98  5705.1  337.29  5763.1  339.38  5768.6  338.95  5801.9  341.61
    5909  346.58  5973.3  348.07  6022.3   350.1  6064.8  352.57  6113.5  354.22
#Mann= 6 ,-1 , 0
  4456.9     .05       0  4954.1      .1       0    5306     .07       0
    5312      .1       0  5705.1     .05       0  6022.3      .1       0
Bank Sta=5306,5312
XS Rating Curve= 0 ,0
Exp/Cntr=0.3,0.1

Type RM Length L Ch R = 1 ,5969    ,62,62,62
BEGIN DESCRIPTION:
Mapping XS 41328c08
END DESCRIPTION:
XS GIS Cut Line= 3
      2212443.87     13225338.52       2212735.5     13225484.34
      2213898.67     13224296.87
#Sta/Elev= 30
  3983.9  338.33  4059.7  337.41  4098.8  335.79  4166.7  334.58    4338  331.78
  4422.9  331.11  4444.2  331.73  4465.3  330.54  4571.5  330.77  4649.2  329.73
    4770  330.24  4841.8  330.29  4904.3  329.88  4924.9  329.84  4946.2  331.08
  4960.4  333.91  4986.5  330.23  4992.6  329.16  4995.4  328.66  4998.6  329.16
  5038.7   330.4  5094.7  330.29  5131.2  331.49    5173  332.69    5232  335.44
  5342.3  340.12  5646.3  350.49  5737.1  355.15  5852.6  360.15  5972.2  362.86
#Mann= 14 ,-1 , 0
  3983.9      .1       0  4166.7     .05       0    4770      .1       0
  4841.8     .05       0  4904.3      .1       0  4986.5     .05       0
  4992.6     .03       0  4998.6     .05       0  5038.7      .1       0
  5131.2     .05       0    5173      .1       0    5232     .05       0
  5737.1      .1       0  5852.6     .05       0
Bank Sta=4992.6,4998.6
XS Rating Curve= 0 ,0
Exp/Cntr=0.3,0.1

Type RM Length L Ch R = 1 ,5907    ,82,82,82
BEGIN DESCRIPTION:
Mapping XS 80b9c06c
END DESCRIPTION:
XS GIS Cut Line= 3
      2212416.04     13225362.81      2212763.28     13225532.95
      2213922.88     13224373.36
#Sta/Elev= 30
    3909  338.98  4078.3  335.04  4349.7   331.3  4418.9  330.83  4492.8  330.72
  4611.3  329.45  4663.8  330.52  4725.5  329.58  4825.8  329.75  4922.1  329.47
  4953.7  331.39  4961.4  330.22  4967.8  330.83    4979     329  4981.7   328.5
    4985     329  5065.2  330.69    5097  331.55  5208.3  334.28  5232.6  334.71
    5286  336.43  5293.1  337.99  5314.3  337.48  5368.3  339.83  5503.9  345.29
  5561.8  348.37  5639.5  350.18  5780.7  355.84  5858.8  359.95  5935.6  360.33
#Mann= 20 ,-1 , 0
    3909      .1       0  4078.3     .05       0  4349.7     .08       0
  4418.9     .05       0  4492.8     .08       0  4611.3     .05       0
  4725.5     .08       0  4825.8     .05       0  4922.1     .08       0
  4961.4     .05       0    4979     .03       0    4985     .05       0
  5065.2     .08       0    5097     .05       0  5208.3     .08       0
  5232.6     .05       0  5368.3     .05       0  5503.9     .05       0
  5639.5     .05       0  5780.7     .05       0
Bank Sta=4979,4985
XS Rating Curve= 0 ,0
Exp/Cntr=0.3,0.1

Type RM Length L Ch R = 1 ,5825    ,68,68,68
BEGIN DESCRIPTION:
Mapping XS 7973ebed
END DESCRIPTION:
XS GIS Cut Line= 3
      2212367.41      13225387.1        2212798.     13225598.92
       2214002.6     13224411.68
#Sta/Elev= 30
  3826.3  339.92  3932.8   337.8  4154.8  333.15  4171.7  333.94  4183.3  332.61
  4198.8   332.6  4272.7  332.18  4314.5  329.97  4441.8  328.81  4505.4  329.33
  4696.4  327.69  4844.8  328.67  4866.1  327.67  4943.8  328.03  4976.3  327.16
    4979  326.66  4982.3  327.16  5137.9  330.92  5202.8  332.67  5300.7  336.35
  5339.3  337.72  5442.8  342.07  5475.9  343.44  5584.8  348.09  5612.5  348.86
  5726.8  353.39    5749  354.33  5868.8  358.32  5885.6  358.55  5997.5  359.29
#Mann= 17 ,-1 , 0
  3826.3      .1       0  3932.8     .05       0  4198.8     .08       0
  4976.3     .07       0  4982.3     .08       0  5137.9     .05       0
  5202.8     .08       0  5300.7     .05       0  5339.3     .08       0
  5442.8     .05       0  5475.9     .08       0  5584.8     .05       0
  5612.5     .08       0  5726.8     .05       0    5749     .08       0
  5868.8     .05       0  5885.6     .08       0
Bank Sta=4976.3,4982.3
XS Rating Curve= 0 ,0
Exp/Cntr=0.3,0.1

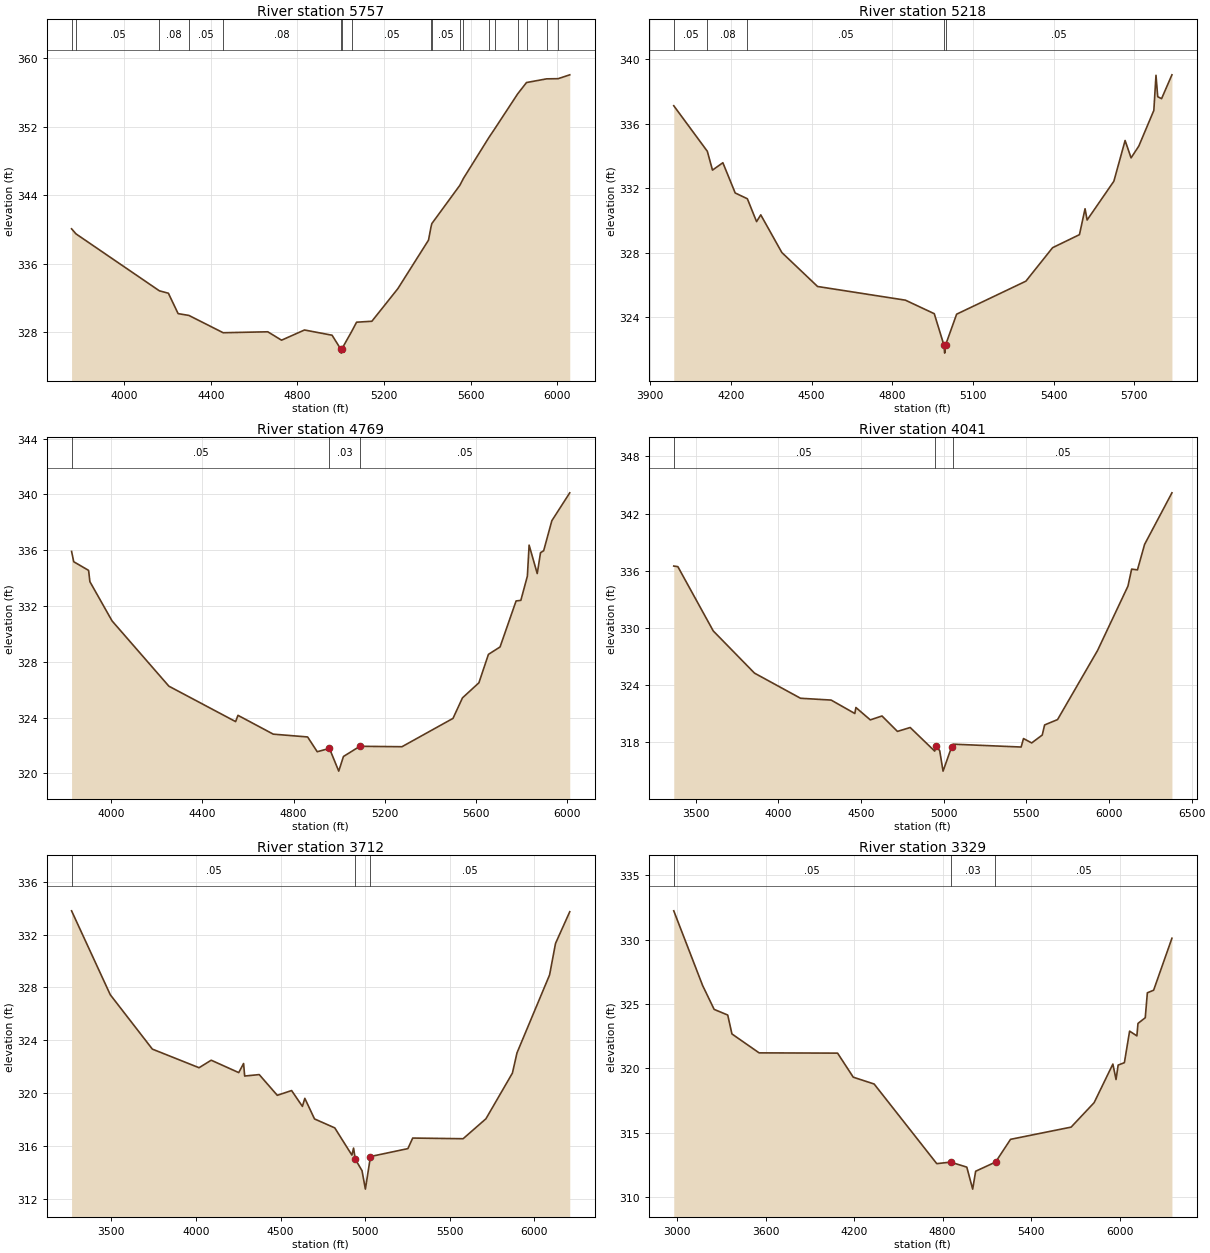
Type RM Length L Ch R = 1 ,5757    ,539,539,539
BEGIN DESCRIPTION:
UNT 010 IN RACR 9.0
END DESCRIPTION:
XS GIS Cut Line= 3
      2212336.24     13225421.86       2212836.2     13225668.37
      2214048.01     13224414.89
#Sta/Elev= 30
  3757.3  340.07  3777.6  339.48    4163  332.83  4204.5  332.55  4249.4  330.17
  4299.2  329.96  4457.5  327.94  4663.5  328.05  4727.1  327.07    4833  328.26
  4960.4  327.65  4999.8  326.06  5002.6  325.56  5005.8  326.06  5051.7  328.12
  5073.6  329.17  5144.3  329.28  5264.4  333.09  5405.9  338.75  5417.2  340.26
  5421.3  340.68  5550.7  345.15  5567.1  345.95  5684.2   350.7  5712.8  351.78
  5817.7  355.82  5858.5  357.14  5951.3  357.57  6004.3  357.59  6058.2  358.04
#Mann= 18 ,-1 , 0
  3757.3      .1       0  3777.6     .05       0    4163     .08       0
  4299.2     .05       0  4457.5     .08       0  4999.8     .07       0
  5005.8     .08       0  5051.7     .05       0  5417.2     .08       0
  5421.3     .05       0  5550.7     .08       0  5567.1     .05       0
  5684.2     .08       0  5712.8     .05       0  5817.7     .08       0
  5858.5     .05       0  5951.3     .08       0  6004.3     .05       0
Bank Sta=4999.8,5005.8
XS Rating Curve= 0 ,0
Exp/Cntr=0.3,0.1

Type RM Length L Ch R = 1 ,5218    ,449,449,449
BEGIN DESCRIPTION:
UNT 010 IN RACR 8.0
END DESCRIPTION:
XS GIS Cut Line= 4
      2212481.36     13225642.37      2213054.25     13225837.67
      2213731.34     13225564.24      2214056.34     13225161.24
#Sta/Elev= 30
  3987.2  337.12  4112.1  334.29  4131.3  333.12  4169.9  333.58  4215.8   331.7
    4261  331.34  4295.3  329.92  4310.9  330.34  4389.3     328  4522.2  325.89
    4849  325.04  4956.3   324.2  4992.2  322.25    4995  321.75  4998.2  322.25
  5039.5  324.17  5297.1  326.22  5396.4   328.3  5496.4  329.11  5517.2  330.72
  5524.9  330.02  5624.4  332.43  5666.2  334.96  5688.4  333.88  5717.1  334.61
  5773.1  336.83  5781.1  339.01  5787.5  337.68  5801.9  337.56  5840.4  339.04
#Mann= 5 ,-1 , 0
  3987.2     .05       0  4112.1     .08       0    4261     .05       0
  4992.2     .03       0  4998.2     .05       0
Bank Sta=4992.2,4998.2
XS Rating Curve= 0 ,0
Exp/Cntr=0.3,0.1

Type RM Length L Ch R = 1 ,4769    ,728,728,728
BEGIN DESCRIPTION:
UNT 010 IN RACR 7.0
END DESCRIPTION:
XS GIS Cut Line= 4
      2212507.39      13225785.6      2213236.54     13226189.24
      2214004.77     13226006.95      2214447.48     13225655.38
#Sta/Elev= 30
    3825  335.91  3834.5  335.17  3899.8  334.55  3905.5  333.74  4002.8  330.93
  4252.4  326.25  4545.6  323.71  4555.9  324.16    4711  322.81  4861.8  322.61
  4904.1  321.55  4957.7  321.79  4998.5  320.16  5019.3  321.21  5091.3  321.94
  5276.3  321.91  5500.4  323.94    5542  325.41  5614.2  326.49  5656.1  328.53
  5707.1  329.06  5777.6  332.36  5798.4   332.4  5827.2  334.14  5834.8  336.36
  5870.5  334.32  5884.9  335.82  5898.7  335.96  5934.6  338.11  6013.3  340.11
#Mann= 3 , 0 , 0
    3825     .05       0  4957.7     .03       0  5091.3     .05       0
Bank Sta=4957.7,5091.3
XS Rating Curve= 0 ,0
Exp/Cntr=0.3,0.1

Type RM Length L Ch R = 1 ,4041    ,329,329,329
BEGIN DESCRIPTION:
UNT 010 IN RACR 6.0
END DESCRIPTION:
XS GIS Cut Line= 4
      2212441.77     13225907.78       2213648.7     13226828.09
      2214200.78     13226718.72      2214794.55     13225999.94
#Sta/Elev= 30
  3367.8  336.49  3392.6  336.43  3606.7  329.68  3856.1  325.25  4134.6  322.61
  4319.7  322.42    4463  321.01  4469.4  321.64  4556.5  320.34  4627.2  320.75
  4720.7  319.13  4797.7  319.54  4945.8  317.06  4955.9  317.59  4976.3   317.1
  4996.5  314.96  5047.7  317.47  5057.9  317.79  5468.7  317.49    5483  318.38
  5532.5  317.92  5596.4  318.75  5610.7  319.81  5688.9  320.37  5930.7  327.62
  6114.9  334.39    6137  336.17  6172.2  336.09  6215.2  338.76  6380.7  344.18
#Mann= 3 ,-1 , 0
  3367.8     .05       0  4945.8     .03       0  5057.9     .05       0
Bank Sta=4955.9,5047.7
XS Rating Curve= 0 ,0
Exp/Cntr=0.3,0.1

Type RM Length L Ch R = 1 ,3712    ,383,383,383
BEGIN DESCRIPTION:
UNT 010 IN RACR 5.0
END DESCRIPTION:
XS GIS Cut Line= 4
      2212419.51     13226083.28      2213690.36     13227135.38
      2213924.74     13227130.17      2214737.27     13226447.86
#Sta/Elev= 30
  3264.8  333.81  3493.7  327.45  3742.5  323.33  4018.6  321.92  4090.3  322.49
  4253.1  321.55  4281.7  322.24  4288.2  321.29  4374.2   321.4    4481  319.83
  4565.7  320.19  4629.5  318.99  4643.8   319.6  4701.1  318.04  4820.9  317.36
    4922   315.3    4932  315.83    4942  314.99    4982  314.12  5001.8  312.72
    5032  315.19  5253.1  315.79  5281.7  316.59  5579.6  316.54  5714.5  318.05
    5871  321.51  5898.3  323.05  6090.8  328.95    6126  331.34  6210.1  333.74
#Mann= 3 , 0 , 0
  3264.8     .05       0    4942     .03       0    5032     .05       0
Bank Sta=4942,5032
XS Rating Curve= 0 ,0
Exp/Cntr=0.3,0.1

Type RM Length L Ch R = 1 ,3329    ,425,425,425
BEGIN DESCRIPTION:
UNT 010 IN RACR 4.0
END DESCRIPTION:
XS GIS Cut Line= 4
      2212351.84     13226166.65      2213528.91     13227510.38
      2213872.66     13227515.59      2214783.42     13226667.28
#Sta/Elev= 30
  2978.2  332.24    3174  326.43  3251.9  324.58  3343.9  324.14  3372.4  322.67
  3556.5   321.2    4088  321.18  4194.3  319.31  4335.7  318.78  4759.9  312.59
  4853.4  312.71  4963.4  312.32  5003.2  310.61  5023.4     312  5153.6  312.69
  5160.5  312.75  5259.7  314.48  5670.1  315.43  5825.9  317.33  5952.9  320.33
  5974.4  319.13  5988.6  320.25  6030.9  320.44  6066.3  322.89  6115.6  322.52
    6123  323.49  6172.3  323.93  6186.5  325.87    6229  326.07    6353  330.11
#Mann= 3 ,-1 , 0
  2978.2     .05       0  4853.4     .03       0  5153.6     .05       0
Bank Sta=4853.4,5160.5
XS Rating Curve= 0 ,0
Exp/Cntr=0.3,0.1

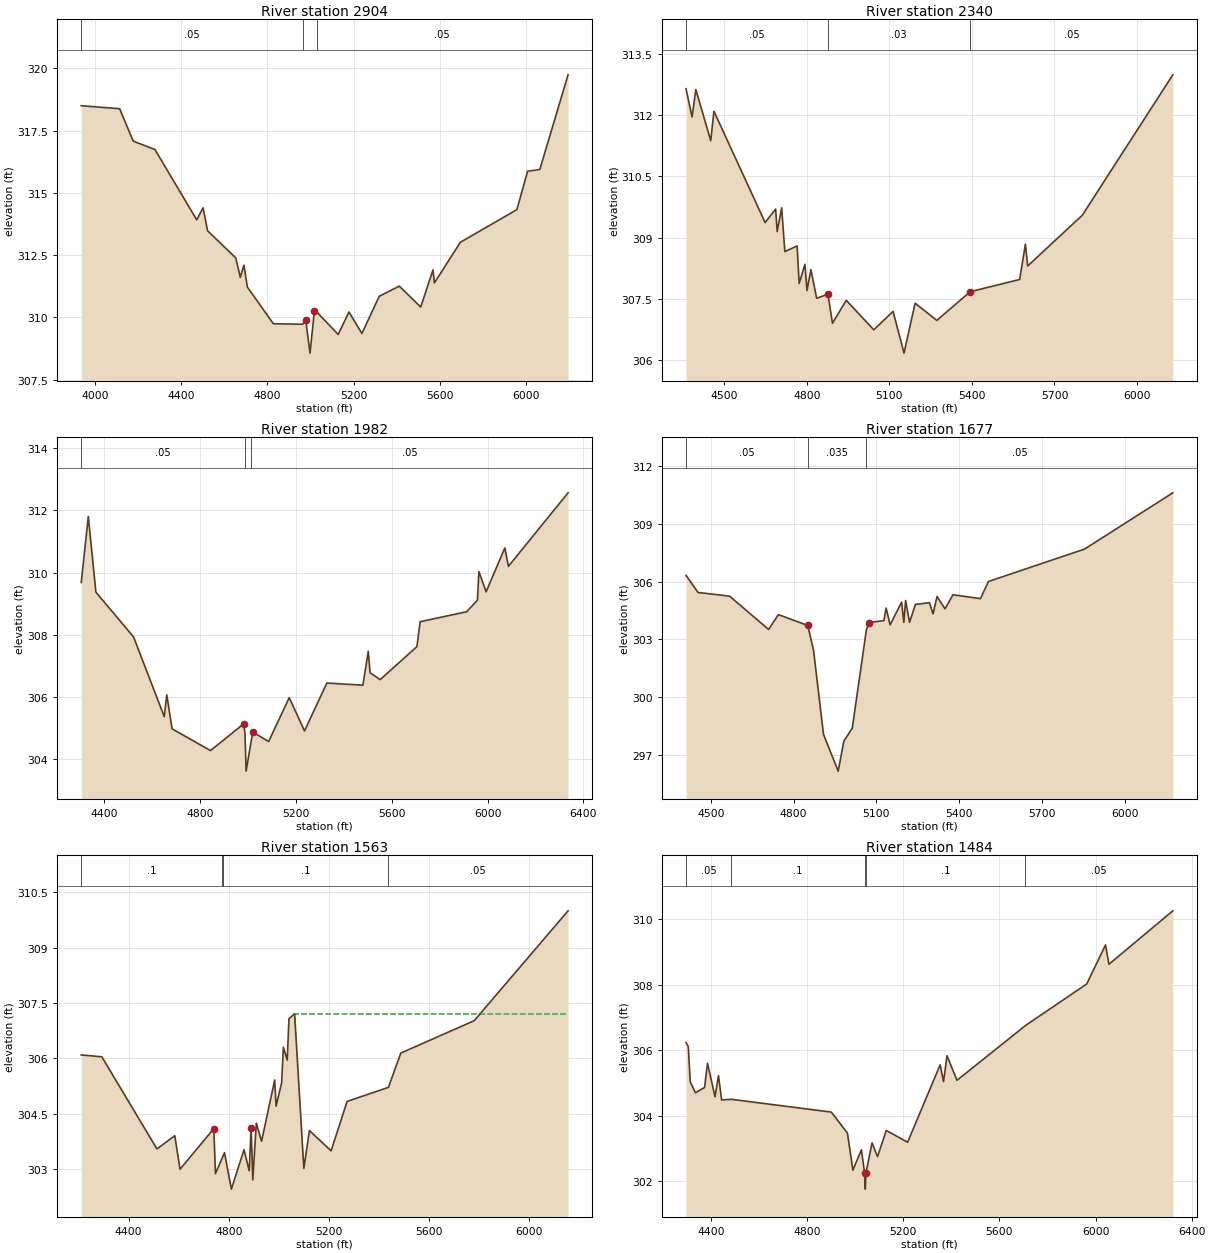
Type RM Length L Ch R = 1 ,2904    ,564,564,564
BEGIN DESCRIPTION:
Mapping XS 3eb04bbb
END DESCRIPTION:
XS GIS Cut Line= 4
      2212887.47     13227300.34      2213321.49     13227916.64
      2213963.85     13227881.92      2214596.71     13227301.07
#Sta/Elev= 30
  3936.9   318.5  4114.8  318.38  4177.6  317.08  4278.6  316.74    4472  313.92
  4501.6   314.4  4522.5  313.48  4653.1  312.39    4674  311.61  4690.7   312.1
  4706.9  311.22  4827.1  309.75  4963.5  309.73  4977.3   309.9  4997.1  308.57
  5017.4  310.26  5027.4  310.23  5127.6  309.32  5177.6  310.22  5237.7  309.36
  5317.8  310.85    5411  311.26  5510.2  310.42    5567  311.91  5573.7  311.39
    5694  313.02    5956  314.33  6005.4  315.87  6062.1  315.94    6193  319.74
#Mann= 3 ,-1 , 0
  3936.9     .05       0  4963.5     .03       0  5027.4     .05       0
Bank Sta=4977.3,5017.4
XS Rating Curve= 0 ,0
Exp/Cntr=0.3,0.1

Type RM Length L Ch R = 1 ,2340    ,358,358,358
BEGIN DESCRIPTION:
Mapping XS db819920
END DESCRIPTION:
XS GIS Cut Line= 5
      2213137.34     13228027.58      2213308.45     13228346.99
      2213411.13     13228461.07      2213776.21     13228438.26
      2214300.13      13227720.7
#Sta/Elev= 30
  4360.4  312.64  4382.3  311.95  4396.1  312.62  4450.3  311.37  4461.9  312.09
    4648  309.37  4686.2   309.7  4691.8  309.15  4708.1  309.73  4719.8  308.66
  4764.3   308.8  4771.8  307.88  4792.7  308.35  4800.2  307.71  4814.4  308.22
  4835.4  307.52  4876.2  307.62  4892.9  306.91    4943  307.47  5043.2  306.75
  5113.3   307.2  5153.1  306.18  5193.4   307.4  5272.4  306.98  5393.6  307.68
  5573.6  307.98  5594.4  308.84  5602.8  308.31  5801.4  309.55  6130.5  312.98
#Mann= 3 , 0 , 0
  4360.4     .05       0  4876.2     .03       0  5393.6     .05       0
Bank Sta=4876.2,5393.6
XS Rating Curve= 0 ,0
Exp/Cntr=0.3,0.1

Type RM Length L Ch R = 1 ,1982    ,305,305,305
BEGIN DESCRIPTION:
UNT 010 IN RACR 3.0
END DESCRIPTION:
XS GIS Cut Line= 4
      2213156.54     13228289.86      2213390.93      13228828.1
      2213694.75     13228741.29      2214319.77     13227803.77
#Sta/Elev= 30
  4305.9  309.68  4335.3   311.8    4367  309.37    4524  307.93    4652  305.37
  4662.6  306.07  4684.4  304.98  4844.9  304.28  4983.2  305.14  4988.5  304.84
  4993.4  303.62  5014.4  304.59  5022.3  304.87  5087.2  304.57  5173.1  305.98
  5236.8  304.91    5330  306.45  5480.2  306.38  5502.7  307.47  5510.2  306.78
  5552.3  306.56  5705.5  307.62    5719  308.42  5912.9  308.74  5957.9  309.11
  5963.9  310.03    5994  309.38  6072.1  310.79  6087.1   310.2  6335.7  312.56
#Mann= 3 ,-1 , 0
  4305.9     .05       0  4988.5    .035       0  5014.4     .05       0
Bank Sta=4983.2,5022.3
XS Rating Curve= 0 ,0
Exp/Cntr=0.3,0.1

Type RM Length L Ch R = 1 ,1677    ,114,114,114
BEGIN DESCRIPTION:
Mapping XS 4f30239d
END DESCRIPTION:
XS GIS Cut Line= 4
      2213147.64     13228635.13      2213500.66     13229049.59
      2213633.17     13229026.74      2214301.51     13228172.14
#Sta/Elev= 30
  4410.6  306.33  4454.1  305.44  4568.3  305.25  4709.9  303.52  4745.1  304.29
  4851.6  303.73  4872.6  302.44  4908.7  298.08  4961.9  296.17  4982.5  297.73
  5012.9   298.4  5064.1   303.5  5073.8  303.88  5127.5  303.98  5135.6  304.63
  5150.1  303.76  5191.7  304.94  5199.8  303.89  5206.2  305.02  5220.6  303.89
  5241.7  304.82  5292.5  304.91  5305.6  304.33  5320.1  305.23    5349  304.59
    5378  305.32  5477.4  305.12  5506.4  306.01  5854.5  307.69  6174.4  310.61
#Mann= 3 ,-1 , 0
  4410.6     .05       0  4851.6    .035       0  5064.1     .05       0
Bank Sta=4851.6,5073.8
XS Rating Curve= 0 ,0
Exp/Cntr=0.3,0.1

Type RM Length L Ch R = 1 ,1563    ,79,79,79
BEGIN DESCRIPTION:
Mapping XS 1f509ab4
END DESCRIPTION:
XS GIS Cut Line= 4
      2213052.89     13228605.24      2213542.79     13229166.63
      2213704.25      13229083.3      2214318.98      13228273.1
#Sta/Elev= 30
  4211.1  306.09  4293.2  306.04  4513.4  303.54  4584.6   303.9  4605.5  302.99
  4740.3  304.09    4747  302.87    4783  303.44  4810.6  302.45  4860.9  303.52
  4881.8  302.95  4889.4  304.11    4896   302.7  4910.2  304.24  4931.1  303.75
  4983.5  305.41  4989.1   304.7  5011.3  305.34    5018   306.3  5033.5  305.95
  5040.5  307.07    5063  307.21  5099.9  303.01  5122.1  304.04  5208.7  303.49
  5272.7  304.83  5437.6  305.21    5487  306.14  5780.2  307.02  6154.9     310
#Mann= 4 ,-1 , 0
  4211.1      .1       0  4772.4     .07       0  4778.4      .1       0
  5437.6     .05       0
#XS Ineff= 2 , 0
                         5065.51          307.21
Permanent Ineff=
       F       F
Bank Sta=4740.3,4889.4
XS Rating Curve= 0 ,0
Exp/Cntr=0.3,0.1

Type RM Length L Ch R = 1 ,1484    ,455,455,455
BEGIN DESCRIPTION:
UNT 010 IN RACR 2.0
END DESCRIPTION:
XS GIS Cut Line= 4
       2213009.5     13229551.46      2213555.49     13229250.64
      2213806.81     13229113.56      2214524.24     13228259.05
#Sta/Elev= 30
  4296.3  306.23  4305.7  306.11  4313.8  305.03  4335.6   304.7  4373.4  304.86
  4385.6   305.6    4417  304.58  4431.3  305.22  4444.5  304.48  4485.1   304.5
  4900.8  304.11  4967.8  303.47  4990.6  302.34    5026  302.96  5039.1  302.26
  5041.9  301.76  5045.1  302.26  5070.3  303.17  5093.1  302.75  5129.5  303.55
  5218.2  303.19  5353.5  305.55  5367.8  305.04  5382.1  305.83  5423.7  305.08
  5708.5  306.75  5963.6  308.02  6041.6  309.21  6055.9  308.62  6321.7  310.25
#Mann= 5 ,-1 , 0
  4296.3     .05       0  4485.1      .1       0  5039.1     .07       0
  5045.1      .1       0  5708.5     .05       0
Bank Sta=5039.1,5045.1
XS Rating Curve= 0 ,0
Exp/Cntr=0.3,0.1