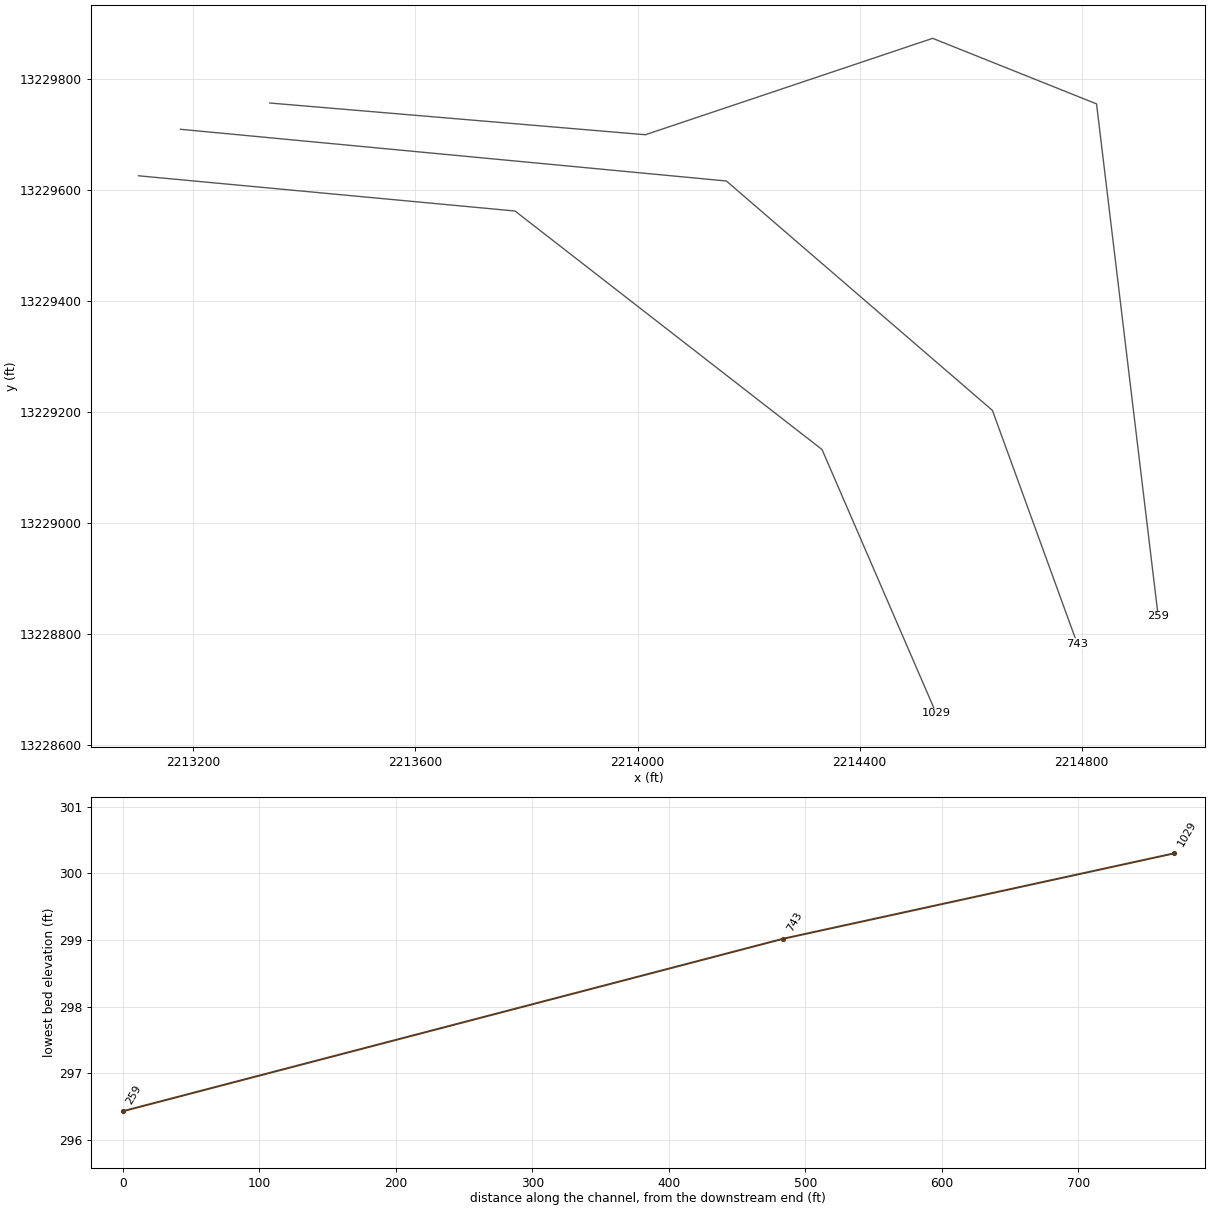
HEC-RAS study UNT 010 IN RACR.prj: UNT 010 IN RACR Base Level Engineering

--- UNT 010 IN RACR.g01 (geometry) --- (continued)

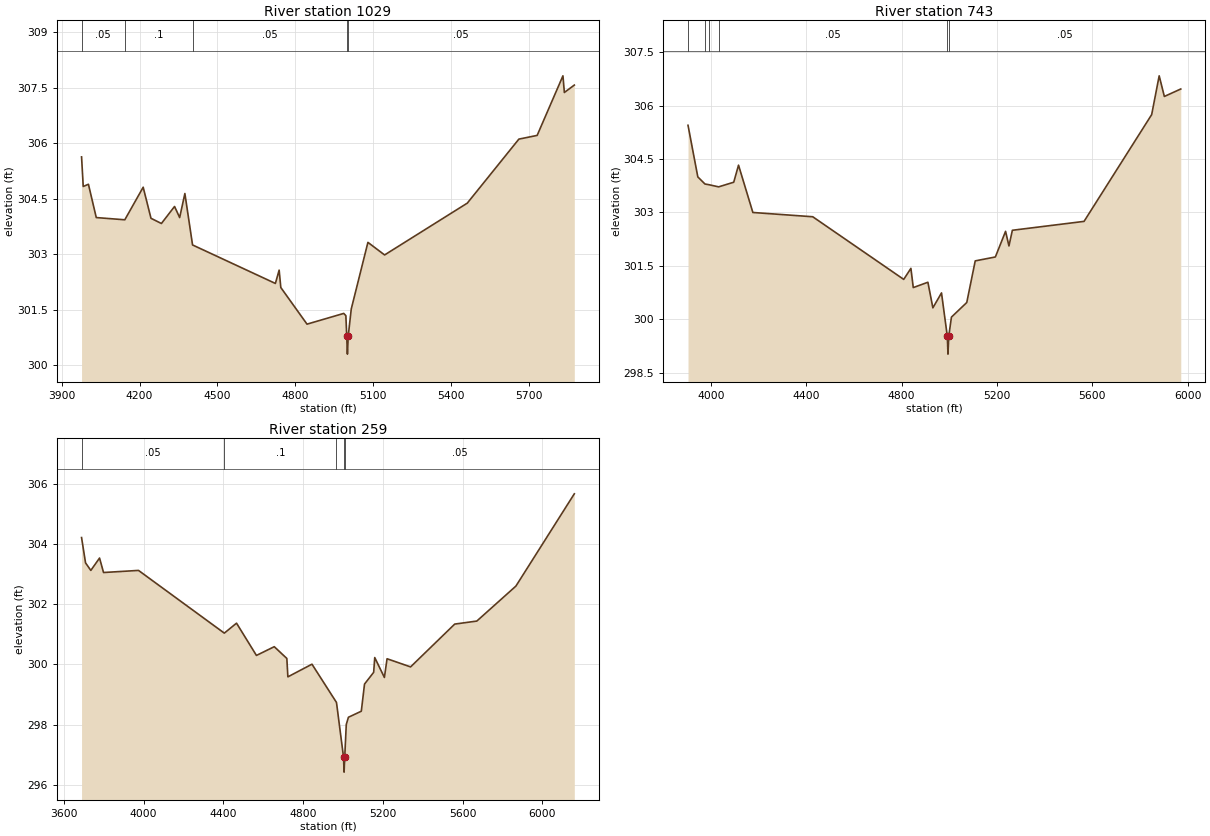
Type RM Length L Ch R = 1 ,1029    ,286,286,286
BEGIN DESCRIPTION:
Mapping XS a41bdebc
END DESCRIPTION:
XS GIS Cut Line= 4
      2213101.29      13229624.8       2213779.4     13229561.37
       2214332.3     13229131.84      2214537.92     13228656.63
#Sta/Elev= 30
  3976.5  305.63    3983  304.83    4003  304.89  4033.2  303.99  4143.2  303.93
    4214  304.81  4244.1  303.97  4284.3  303.83  4334.9  304.29  4354.6  303.99
  4374.7  304.64  4404.3  303.25  4723.5  302.21    4738  302.57  4744.4   302.1
  4845.4  301.11  4986.9   301.4  4995.1  301.34  4998.4   300.8  5001.1   300.3
  5004.4   300.8  5015.9  301.52  5080.1  303.32  5144.4  302.98  5463.1  304.38
  5661.9  306.11  5732.3  306.21  5831.7  307.82  5837.2  307.37  5875.5  307.57
#Mann= 5 ,-1 , 0
  3976.5     .05       0  4143.2      .1       0  4404.3     .05       0
  4998.4    .035       0  5004.4     .05       0
Bank Sta=4998.4,5004.4
XS Rating Curve= 0 ,0
Exp/Cntr=0.3,0.1

Type RM Length L Ch R = 1 ,743     ,484,484,484
BEGIN DESCRIPTION:
Mapping XS 0290c3a5
END DESCRIPTION:
XS GIS Cut Line= 4
      2213176.79     13229708.57      2214160.05     13229615.42
      2214639.22     13229202.22      2214791.98     13228782.12
#Sta/Elev= 30
  3903.7  305.45  3944.8     304  3974.8   303.8  3991.9  303.78  4032.1  303.72
  4095.5  303.85  4115.6  304.33  4175.8     303    4427  302.88  4808.7  301.12
  4838.8  301.43  4848.8  300.89  4910.1  301.04    4931  300.32  4967.2  300.74
  4991.6  299.52  4994.4  299.02  4997.6  299.52  5008.9  300.06  5073.2  300.47
  5108.7  301.64  5193.2  301.75    5236  302.47  5250.2  302.06  5264.5   302.5
  5565.3  302.75    5849  305.75  5880.5  306.84  5902.2  306.26  5971.1  306.47
#Mann= 6 ,-1 , 0
  3903.7     .08       0  3974.8     .05       0  3991.9      .1       0
  4032.1     .05       0  4991.6    .035       0  4997.6     .05       0
Bank Sta=4991.6,4997.6
XS Rating Curve= 0 ,0
Exp/Cntr=0.3,0.1

Type RM Length L Ch R = 1 ,259     ,0,0,0
BEGIN DESCRIPTION:
UNT 010 IN RACR 1.0
END DESCRIPTION:
XS GIS Cut Line= 5
      2213337.79     13229755.88      2214014.22     13229698.75
      2214531.58     13229872.36      2214826.72      13229754.3
      2214937.76     13228831.29
#Sta/Elev= 30
  3688.4  304.21  3708.4  303.37  3734.9  303.12  3778.7  303.53  3798.7  303.05
  3974.1  303.12  4404.6  301.04  4465.9  301.37  4565.8   300.3  4655.2  300.59
  4718.3   300.2  4723.5  299.59  4844.4  300.01  4967.4  298.74  5002.7  296.93
  5005.5  296.43  5008.7  296.93  5016.5  298.01  5027.3  298.25  5091.9  298.45
    5108  299.35  5153.9  299.74  5159.3  300.23  5207.7  299.57  5221.1  300.19
  5339.1  299.92  5560.6  301.34  5671.4  301.44  5867.5   302.6  6160.5  305.66
#Mann= 5 ,-1 , 0
  3688.4     .05       0  4404.6      .1       0  4967.4     .05       0
  5002.7    .035       0  5008.7     .05       0
Bank Sta=5002.7,5008.7
XS Rating Curve= 0 ,0
Exp/Cntr=0.3,0.1

Chan Stop Cuts=-1
Use User Specified Reach Order=0
Composite Channel Slope=5