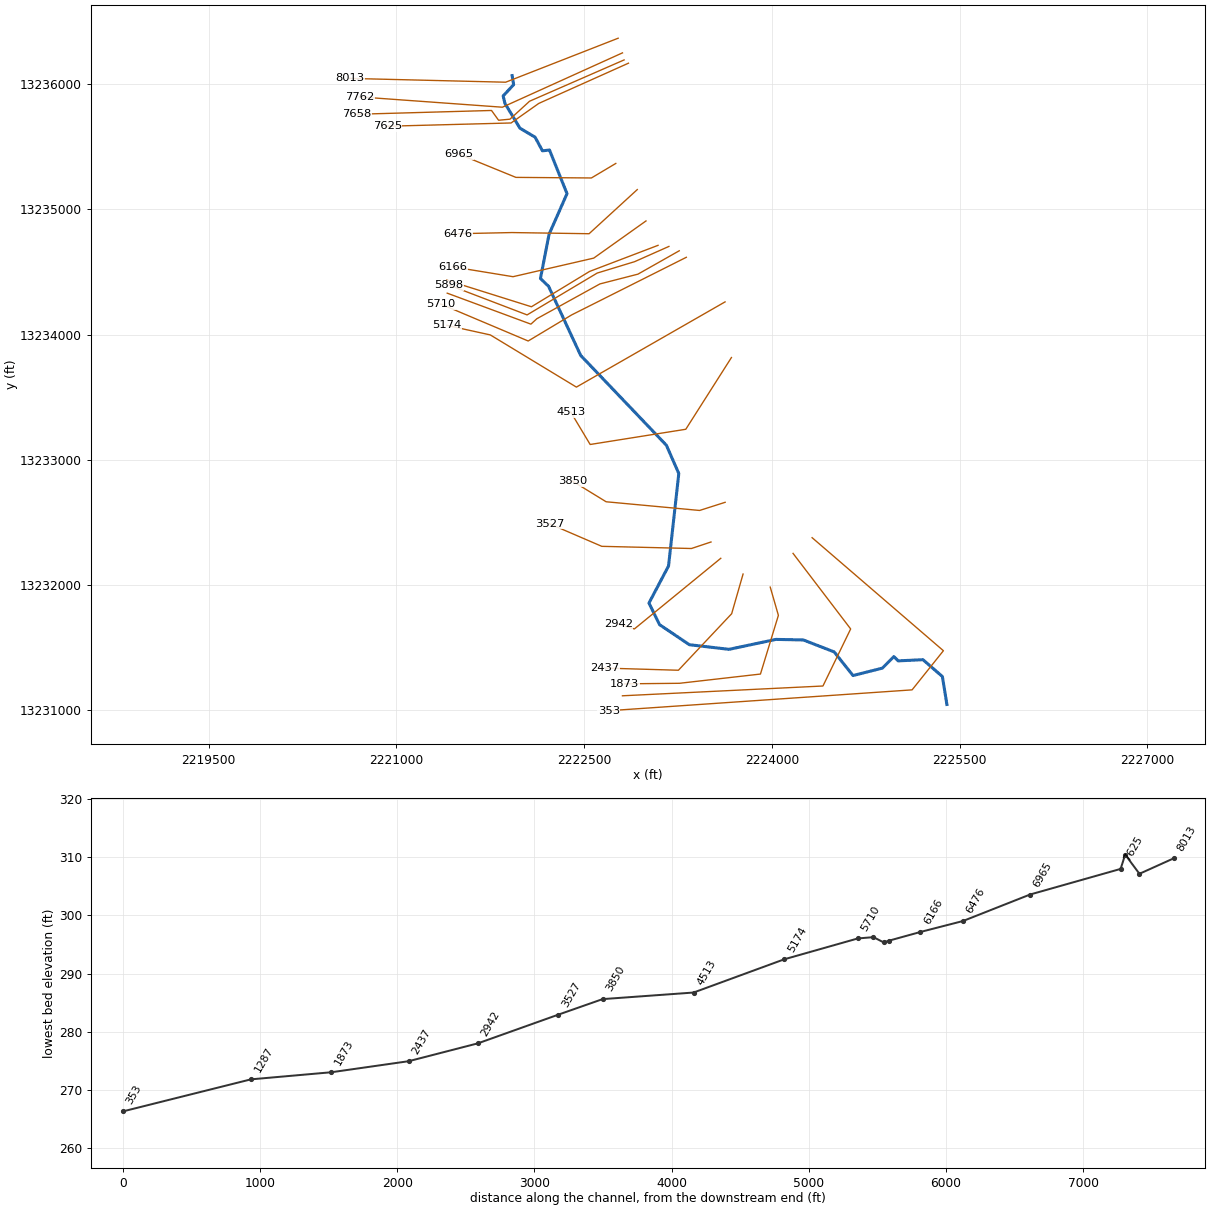
--- UNT 011 IN RACR.prj (project) ---

Proj Title=UNT 011 IN RACR Base Level Engineering
Current Plan=p01
Default Exp/Contr=0.3,0.1
English Units
Geom File=g01
Flow File=f01
Plan File=p01
Y Axis Title=Elevation
X Axis Title(PF)=Main Channel Distance
X Axis Title(XS)=Station
BEGIN DESCRIPTION:
UNT 011 IN RACR
END DESCRIPTION:
DSS Export Rating Curves= 0
DSS Export Rating Curve Sorted= 0
DSS Export Volume Flow Curves= 0
DXF OffsetX= 0
DXF OffsetY= 0
DXF ScaleX= 1
DXF ScaleY= 10

--- UNT 011 IN RACR.p01 (plan) ---

Plan Title=Multiple Run
Program Version=4.10
Short Identifier=Multiple
Geom File=g01
Flow File=f01
Subcritical Flow
K Sum by GR= 0
Std Step Tol= 0.01
Critical Tol= 0.01
Num of Std Step Trials= 20
Max Error Tol= 0.3
Flow Tol Ratio= 0.001
Split Flow NTrial= 30
Split Flow Tol= 0.02
Split Flow Ratio= 0.02
Log Output Level= 0
Friction Slope Method= 1
Unsteady Friction Slope Method= 2
Unsteady Bridges Friction Slope Method= 1
Parabolic Critical Depth
Global Vel Dist= 1 , 1 , 1
Global Log Level= 0
CheckData=True
Encroach Param=-1 ,0,0, 0
BEGIN DESCRIPTION:
Multiple Run
END DESCRIPTION:
Computation Interval=1HOUR
Output Interval=1HOUR
Run HTab= 0
Run UNet= 0
Run PostProcess= 0
Run WQNet= 0
UNET Theta= 1
UNET Theta Warmup= 1
UNET ZTol= 0.02
UNET ZSATol= 0.05
UNET MxIter= 20
UNET MaxInSteps= 0
UNET DtIC= 0
UNET DtMin= 0
UNET MaxCRTS= 20
UNET WFStab= 2
UNET SFStab= 1
UNET WFX= 1
UNET SFX= 1
UNET DSS MLevel= 4
UNET DZMax Abort= 100
UNET Convert EG Bridges= 0
UNET Use Existing IB Tables=-1
UNET Froude Reduction=False
UNET Froude Limit= 1
UNET Froude Power= 10
UNET Time Slicing=0,0, 5
UNET Junction Losses=0
Instantaneous Interval=1HOUR
Write IC File= 0
Write IC File at Sim End=0
Echo Input=False
Echo Parameters=False
Echo Output=False
Write Detailed= 0
WQ AD Non Conservative
WQ ULTIMATE=-1
WQ Max Comp Step=1HOUR
WQ Output Interval=15MIN
WQ Output Selected Increments= 0
WQ Output face flow=0
WQ Output face velocity=0
WQ Output face area=0
WQ Output face dispersion=0
WQ Output cell volume=0
WQ Output cell surface area=0
WQ Output cell continuity=0
WQ Output cumulative cell continuity=0
WQ Output face conc=0
WQ Output face dconc_dx=0
WQ Output face courant=0
WQ Output face peclet=0
WQ Output face adv mass=0
WQ Output face disp mass=0
WQ Output cell mass=0
WQ Output cell source sink temp=0
WQ Output cell source sink nsm=0
WQ Output MaxMinRange=-1
WQ Daily Max Min Mean=-1
WQ Daily Range=0
WQ Daily Time=0
WQ Create Restart=0
WQ Fixed Restart=0
WQ System Summary=0
WQ Use Fixed Temperature=0
Sorting and Armoring Iterations= 10
XS Update Threshold= 0.02
Hydraulics Update Threshold= 0.02
Energy Slope Method= 1
Volume Change Method= 0
XS Weighting Method= 0
Number of US Weighted Cross Sections= 1
Number of DS Weighted Cross Sections= 1
Upstream XS Weight=0.25
Main XS Weight=0.5
Downstream XS Weight=0.25
Number of DS XS's Weighted with US Boundary= 1
Upstream Boundary Weight= 1
Weight of XSs Associated with US Boundary= 0
Number of US XS's Weighted with DS Boundary= 1
Downstream Boundary Weight= 0.5
Weight of XSs Associated with DS Boundary= 0.5
Sediment Output Level= 4
Mass or Volume Output= 0
Output Increment Type= 1
Profile and TS Output Increment= 10
XS Output Flag= 0
XS Output Increment= 10
Disregard all LS=0
Disregard all Conn=0
Disregard all Breaches=0
Disregard all Pumps=0

--- UNT 011 IN RACR.f01 (steady flow) ---

Flow Title=Multiple
Program Version=4.10
Number of Profiles= 7
Profile Names=10-year,25-year,50-year,1pct_min,100-year,1pct_plu,500-year
River Rch & RM=UNT 011 IN RACR,Reach-1         ,8013
     206     284     349     316     427     578     650
River Rch & RM=UNT 011 IN RACR,Reach-1         ,6476
     266     372     460     419     567     766     873
Boundary for River Rch & Prof#=UNT 011 IN RACR,Reach-1         , 1
Up Type= 0
Dn Type= 3
Dn Slope=0.005
Boundary for River Rch & Prof#=UNT 011 IN RACR,Reach-1         , 2
Up Type= 0
Dn Type= 3
Dn Slope=0.005
Boundary for River Rch & Prof#=UNT 011 IN RACR,Reach-1         , 3
Up Type= 0
Dn Type= 3
Dn Slope=0.005
Boundary for River Rch & Prof#=UNT 011 IN RACR,Reach-1         , 4
Up Type= 0
Dn Type= 3
Dn Slope=0.005
Boundary for River Rch & Prof#=UNT 011 IN RACR,Reach-1         , 5
Up Type= 0
Dn Type= 3
Dn Slope=0.005
Boundary for River Rch & Prof#=UNT 011 IN RACR,Reach-1         , 6
Up Type= 0
Dn Type= 3
Dn Slope=0.005
Boundary for River Rch & Prof#=UNT 011 IN RACR,Reach-1         , 7
Up Type= 0
Dn Type= 3
Dn Slope=0.005
DSS Import GetInterval= 0
DSS Import GetPeak= 0
DSS Import FillOption= 0

--- UNT 011 IN RACR.g01 (geometry) ---

Geom Title=Existing Conditions
Program Version=4.10

River Reach=UNT 011 IN RACR ,Reach-1
Reach XY= 30
      2221925.05     13236068.56      2221937.23     13235996.45
      2221853.43     13235906.23      2221867.75     13235846.77
      2221987.55     13235648.85      2222108.82     13235576.65
      2222167.31       13235468.       2222223.5     13235474.49
      2222363.57     13235126.07      2222220.13     13234801.19
       2222151.3      13234448.4      2222216.03     13234386.27
      2222472.66     13233834.12       2223157.2     13233116.72
      2223256.38     13232891.19      2223174.42     13232152.51
      2223018.11     13231856.34      2223102.66     13231684.08
      2223340.89     13231523.74      2223657.72     13231486.86
      2224032.41     13231566.18      2224250.99     13231561.86
      2224497.71      13231466.2      2224647.98     13231277.49
      2224882.62     13231336.87      2224974.29     13231428.88
      2225008.79     13231394.81      2225206.51     13231404.14
      2225361.86     13231269.64      2225397.72     13231046.86

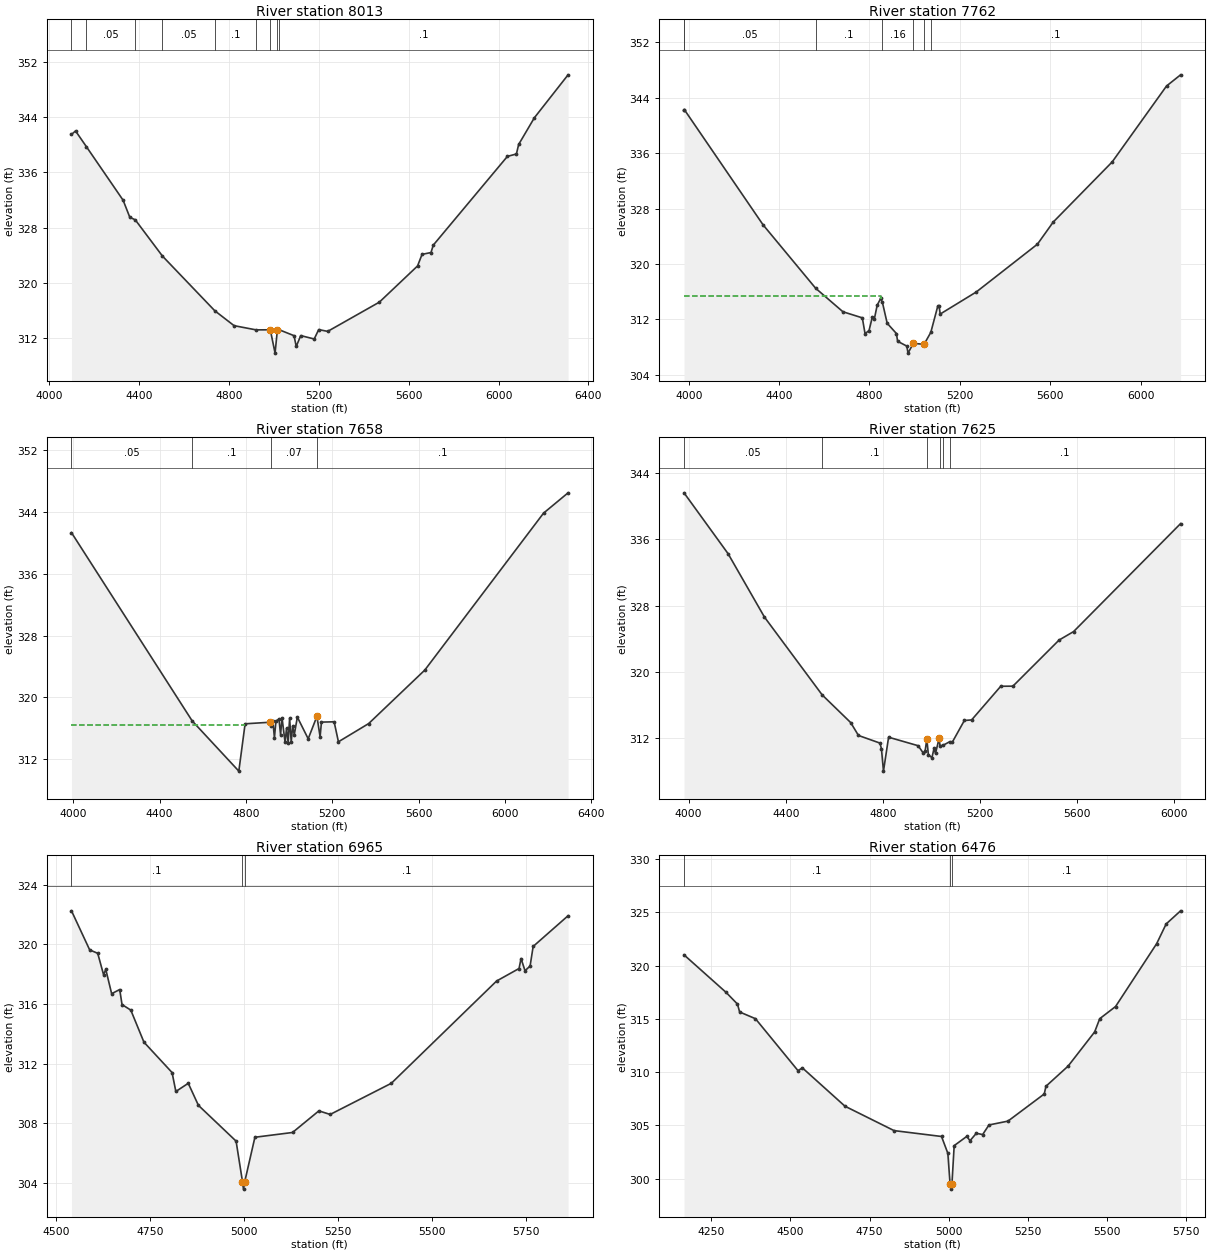
Type RM Length L Ch R = 1 ,8013    ,251,251,251
BEGIN DESCRIPTION:
UNT 011 IN RACR 10.0
END DESCRIPTION:
XS GIS Cut Line= 3
      2222772.12     13236367.35      2221873.38     13236015.97
      2220627.74     13236046.36
#Sta/Elev= 30
  4098.7   341.5  4116.7  342.01  4165.4  339.71  4328.5  331.97  4358.4  329.49
  4382.6  329.13  4503.8  323.87  4736.7  315.95  4822.6  313.79  4920.5  313.18
  4983.9  313.19  5005.1  309.81  5015.4  313.16  5024.7  313.18  5089.4  312.34
  5099.4  310.78  5119.4  312.35  5179.4  311.86  5199.4  313.22  5239.4  312.96
  5469.5   317.2  5639.5  322.44  5659.5  324.12  5699.5  324.39  5709.5  325.46
  6039.6  338.32  6079.7  338.67  6089.7  340.05  6159.7  343.92  6309.7  350.14
#Mann= 9 ,-1 , 0
  4098.7     .08       0  4165.4     .05       0  4382.6      .1       0
  4503.8     .05       0  4736.7      .1       0  4920.5     .16       0
  4983.9     .07       0  5015.4     .16       0  5024.7      .1       0
#XS Ineff= 2 , 0
                         5088.96          312.29
Permanent Ineff=
       F       F
Bank Sta=4983.9,5015.4
XS Rating Curve= 0 ,0
Exp/Cntr=0.3,0.1

Type RM Length L Ch R = 1 ,7762    ,104,104,104
BEGIN DESCRIPTION:
Mapping XS 32d13d4b
END DESCRIPTION:
XS GIS Cut Line= 3
      2222806.52     13236250.34      2221847.34     13235816.32
      2220705.83     13235898.79
#Sta/Elev= 30
  3979.3  342.25  3981.3  342.25  4329.2  325.65  4561.8   316.5  4682.5  313.11
  4768.3  312.23  4780.4  309.95    4798   310.4  4812.2  312.29  4821.1     312
  4834.1  314.06  4849.7  315.04  4857.3  314.45  4878.3  311.45  4919.1  309.97
  4924.5  308.85  4965.3  308.15  4970.5  307.14  4993.9  308.54  5041.8  308.42
  5071.4  310.14  5101.9  313.89  5107.9  313.98  5112.9  312.78  5272.4  315.96
  5543.1  322.86  5613.2  326.06  5873.9  334.73  6114.5  345.69  6176.6   347.3
#Mann= 7 ,-1 , 0
  3979.3     .08       0  3981.3     .05       0  4561.8      .1       0
  4857.3     .16       0  4993.9     .07       0  5041.8     .16       0
  5071.4      .1       0
#XS Ineff= 2 , 0
         4849.28  315.35
Permanent Ineff=
       F       F
Bank Sta=4993.9,5041.8
XS Rating Curve= 0 ,0
Exp/Cntr=0.3,0.1

Type RM Length L Ch R = 1 ,7658    ,33,33,33
BEGIN DESCRIPTION:
Mapping XS 8c023f42
END DESCRIPTION:
XS GIS Cut Line= 6
      2222819.57     13236193.93      2222064.35     13235864.06
       2221908.1     13235720.84      2221816.96     13235712.15
      2221760.53     13235790.28      2220684.17      13235759.9
#Sta/Elev= 30
  3991.8  341.33  4550.9  316.95  4767.1  310.44  4796.2  316.57  4910.5  316.77
  4917.9  316.32  4924.7  316.94  4932.1  314.76  4938.9  316.89  4953.1   317.2
  4960.5  315.18  4967.3  317.35  4981.4  314.16  4988.2  315.99  4995.6  314.14
  5002.4  317.27  5009.8  314.25  5016.6  316.28    5024  315.15  5038.3  317.44
  5088.5  314.63    5129  317.54  5143.7  314.88  5149.9  316.79  5208.7  316.83
  5228.6  314.24  5368.7   316.6  5628.8  323.53    6179  343.86  6292.6  346.49
#Mann= 4 ,-1 , 0
  3991.8     .05       0  4550.9      .1       0  4917.9     .07       0
    5129      .1       0
#XS Ineff= 2 , 0
         4795.36  316.46
Permanent Ineff=
       F       F
Bank Sta=4910.5,5129
XS Rating Curve= 0 ,0
Exp/Cntr=0.3,0.1

Type RM Length L Ch R = 1 ,7625    ,660,660,660
BEGIN DESCRIPTION:
Mapping XS 613f6101
END DESCRIPTION:
XS GIS Cut Line= 4
      2222854.24     13236167.87      2222138.14      13235846.7
      2221916.78     13235690.45       2220927.2     13235664.41
#Sta/Elev= 30
    3981  341.62  4162.4  334.27  4312.4   326.6  4550.3  317.19  4667.6  313.85
  4699.7  312.29  4788.1  311.37  4794.3   310.7  4802.7  307.98  4823.8  312.08
  4945.7  311.05  4966.6  310.16  4974.4  310.44  4981.4  311.85  4987.6  309.98
  5002.3   309.6    5011  310.72  5017.1  310.13  5031.9  311.93  5035.6  311.04
  5047.4  311.09  5075.8  311.54  5085.9  311.46  5135.9   314.1  5165.9  314.17
  5285.9  318.24  5335.9  318.25    5526  323.82    5586  324.85  6026.7   337.9
#Mann= 6 ,-1 , 0
    3981     .05       0  4550.3      .1       0  4981.4     .07       0
  5035.6      .1       0  5047.4     .16       0  5075.8      .1       0
#XS Ineff= 2 , 0
         4824.21  312.04
Permanent Ineff=
       F       F
Bank Sta=4981.4,5031.9
XS Rating Curve= 0 ,0
Exp/Cntr=0.3,0.1

Type RM Length L Ch R = 1 ,6965    ,489,489,489
BEGIN DESCRIPTION:
UNT 011 IN RACR 9.0
END DESCRIPTION:
XS GIS Cut Line= 4
      2222753.16      13235367.2      2222558.34     13235251.23
       2221955.4     13235255.87      2221501.81       13235441.
#Sta/Elev= 30
  4541.6  322.25  4589.9  319.63  4611.3   319.4  4626.9  317.96  4632.7  318.32
  4648.3  316.69  4669.7  316.97  4675.9  315.96  4699.2  315.59  4734.1  313.44
  4808.9   311.4  4818.9  310.13  4851.9  310.68  4878.9   309.2    4979   306.8
    4996  304.08  4998.7  303.58    5002  304.08    5029  307.06    5129  307.38
    5199  308.83    5229  308.59  5391.5  310.68  5671.2  317.54  5730.9  318.38
  5736.3  319.05  5746.8  318.23  5760.3  318.55  5768.4  319.86  5861.2  321.92
#Mann= 3 ,-1 , 0
  4541.6      .1       0    4996     .07       0    5002      .1       0
Bank Sta=4996,5002
XS Rating Curve= 0 ,0
Exp/Cntr=0.3,0.1

Type RM Length L Ch R = 1 ,6476    ,310,310,310
BEGIN DESCRIPTION:
UNT 011 IN RACR 8.0
END DESCRIPTION:
XS GIS Cut Line= 4
      2222924.71     13235158.44      2222539.79     13234805.98
      2221922.93     13234815.26      2221492.17     13234805.99
#Sta/Elev= 30
  4163.4  321.01  4296.7  317.48  4332.4  316.39  4339.2  315.65  4389.2  315.02
  4523.6  310.15  4537.8   310.4  4672.2  306.81  4827.4  304.52  4977.4  303.97
  4997.4  302.39  5004.4  299.53  5007.2  299.03  5010.4  299.53  5017.4  303.11
  5057.4  303.98  5067.4  303.57  5087.4  304.27  5107.4  304.15  5127.4  305.05
  5187.4  305.41  5302.2  307.96  5307.5  308.68  5377.5  310.57  5461.5  313.78
  5477.5  315.02  5527.5  316.16  5657.5  322.06  5687.5  323.91  5733.1  325.14
#Mann= 3 ,-1 , 0
  4163.4      .1       0  5004.4     .07       0  5010.4      .1       0
Bank Sta=5004.4,5010.4
XS Rating Curve= 0 ,0
Exp/Cntr=0.3,0.1

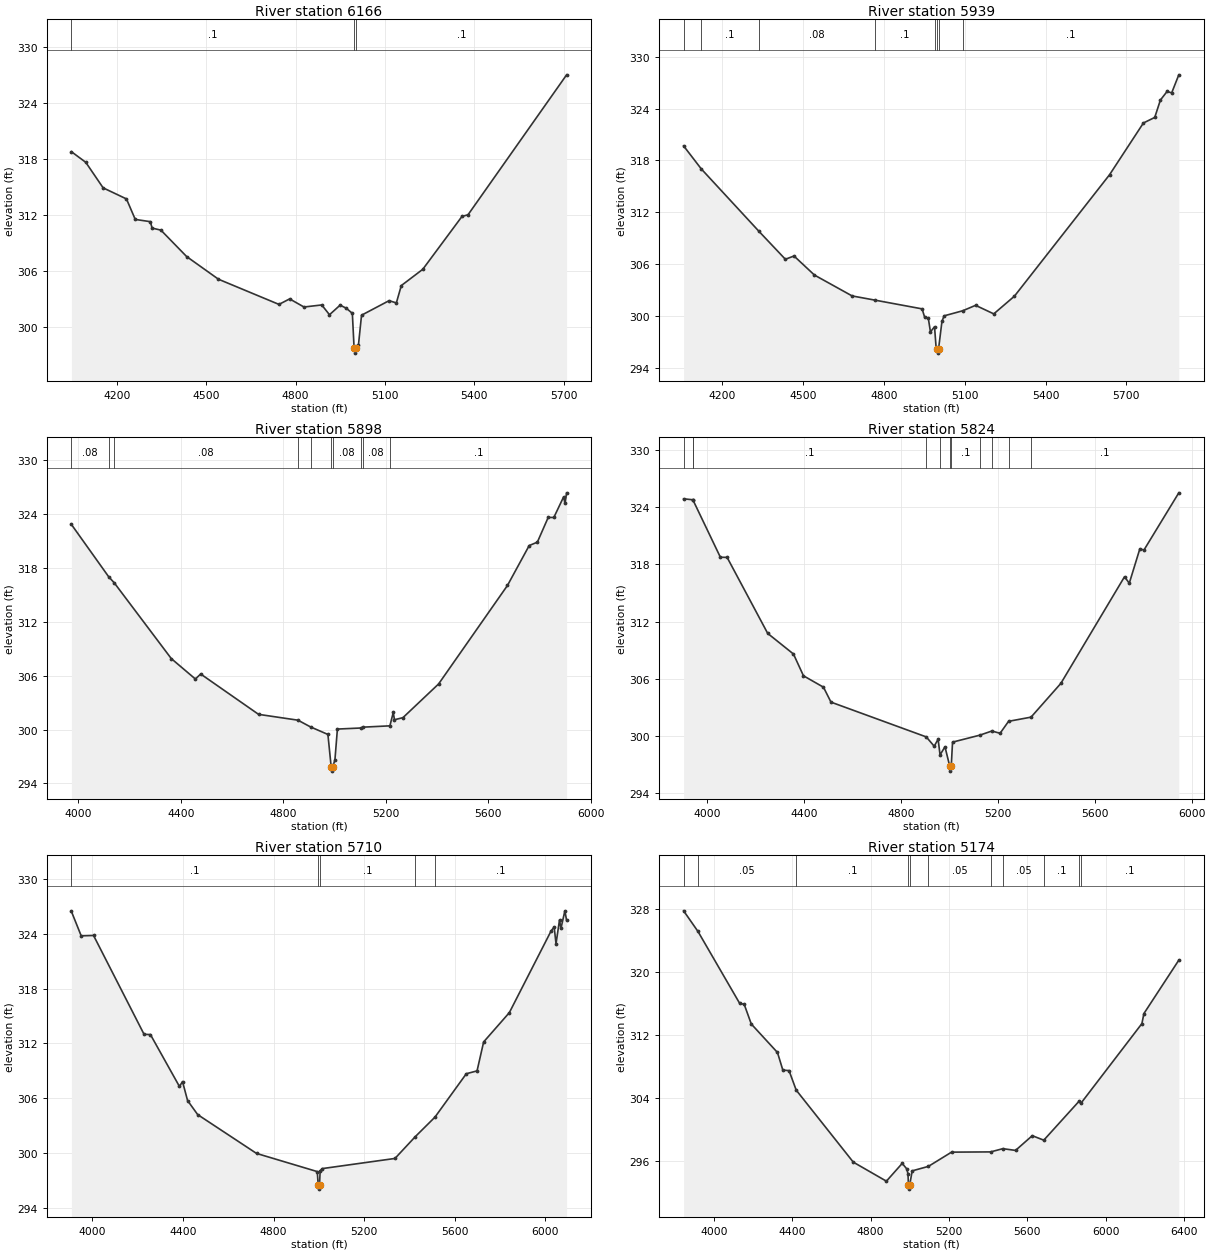
Type RM Length L Ch R = 1 ,6166    ,227,227,227
BEGIN DESCRIPTION:
UNT 011 IN RACR 7.0
END DESCRIPTION:
XS GIS Cut Line= 4
      2222994.31     13234908.02      2222576.89     13234611.19
      2221932.21     13234462.77      2221451.34     13234541.37
#Sta/Elev= 30
  4048.3  318.77  4096.4  317.63  4154.6  314.89  4232.9   313.7  4262.4   311.5
  4312.9  311.26    4319  310.57  4348.5  310.35  4434.6  307.52  4541.6  305.08
  4744.4  302.38  4780.3  302.97  4828.3   302.1    4888  302.32  4913.9  301.27
  4949.6   302.3  4970.1  301.97  4990.6  301.42  4996.5  297.65  4999.3  297.15
  5002.5  297.65  5011.2  298.06  5021.4  301.22  5113.8  302.78  5138.2  302.54
  5154.8   304.4  5226.9  306.15  5358.3  311.82  5378.6     312  5709.3  327.02
#Mann= 3 ,-1 , 0
  4048.3      .1       0  4996.5     .07       0  5002.5      .1       0
Bank Sta=4996.5,5002.5
XS Rating Curve= 0 ,0
Exp/Cntr=0.3,0.1

Type RM Length L Ch R = 1 ,5939    ,41,41,41
BEGIN DESCRIPTION:
Mapping XS d070309b
END DESCRIPTION:
XS GIS Cut Line= 4
      2223090.68     13234713.17       2222543.8     13234504.83
      2222079.39     13234222.72       2221402.5     13234435.33
#Sta/Elev= 30
  4056.7  319.69  4122.1  317.03  4336.6  309.78  4434.4  306.55  4466.5  306.93
  4542.3  304.72  4682.2   302.3  4767.5  301.81    4942   300.8  4951.6  299.81
  4964.9  299.74  4972.9  298.13  4988.1  298.73  4994.3  296.18  4997.1  296.17
  4999.9  295.67  5003.1  296.17  5015.6  299.34  5023.5  299.99  5092.6  300.58
  5140.5  301.21    5208  300.22  5284.6  302.27  5637.8  316.35  5763.5  322.35
  5805.5  322.99  5826.4     325  5851.2     326  5868.4  325.84  5894.8  327.93
#Mann= 8 ,-1 , 0
  4056.7     .08       0  4122.1      .1       0  4336.6     .08       0
  4767.5      .1       0  4988.1     .08       0  4997.1     .07       0
  5003.1     .08       0  5092.6      .1       0
Bank Sta=4997.1,5003.1
XS Rating Curve= 0 ,0
Exp/Cntr=0.3,0.1

Type RM Length L Ch R = 1 ,5898    ,74,74,74
BEGIN DESCRIPTION:
Mapping XS 1f3dfa7b
END DESCRIPTION:
XS GIS Cut Line= 5
      2223177.51      13234704.5      2222904.05     13234582.96
      2222604.57     13234491.81      2222044.67     13234157.61
      2221421.15     13234395.76
#Sta/Elev= 30
  3973.4  322.86  4118.5  317.04  4140.6  316.35  4362.9  307.91    4457  305.63
  4477.6  306.19  4703.5  301.69  4857.2  301.04  4906.1  300.29    4974  299.45
  4986.6  295.86  4989.3  295.36  4992.6  295.86  5001.3  296.59    5011  300.05
  5103.5  300.17  5109.1  300.26  5215.8  300.41  5228.9   301.9  5233.6  301.09
  5266.6  301.32  5405.8  305.08  5674.4  316.06  5759.2  320.51  5791.1  320.89
  5833.4  323.65  5855.3  323.64  5893.5  325.94  5898.9  325.21  5905.2  326.39
#Mann= 10 ,-1 , 0
  3973.4     .08       0  4118.5      .1       0  4140.6     .08       0
  4857.2      .1       0  4906.1     .08       0  4986.6     .07       0
  4992.6     .08       0  5103.5      .1       0  5109.1     .08       0
  5215.8      .1       0
Bank Sta=4986.6,4992.6
XS Rating Curve= 0 ,0
Exp/Cntr=0.3,0.1

Type RM Length L Ch R = 1 ,5824    ,114,114,114
BEGIN DESCRIPTION:
Mapping XS b9cd3007
END DESCRIPTION:
XS GIS Cut Line= 6
      2223259.97     13234669.78      2222930.09     13234483.13
      2222626.27     13234405.01       2222122.8     13234127.23
      2222075.05     13234083.83      2221406.63     13234331.23
#Sta/Elev= 30
    3902  324.91  3939.9  324.81    3940  324.82  4053.9  318.76  4081.6  318.75
  4249.3  310.75  4355.7  308.58    4397  306.29  4479.6  305.09  4510.6  303.52
  4904.1  299.86  4936.9  298.88    4953  299.62    4961  297.97  4981.4  298.82
  5001.2  296.76    5004  296.26  5007.2  296.76  5012.6  299.31  5124.7  300.04
  5175.1  300.48  5208.9  300.24    5244   301.5  5336.8  301.94  5459.9  305.49
  5722.8  316.71  5742.5  316.03  5785.9  319.63  5803.3  319.53    5947  325.54
#Mann= 11 ,-1 , 0
    3902      .1       0  3939.9     .08       0    3940      .1       0
  4904.1     .08       0    4961      .1       0  5001.2     .07       0
  5007.2      .1       0  5124.7     .08       0  5175.1      .1       0
    5244     .08       0  5336.8      .1       0
Bank Sta=5001.2,5007.2
XS Rating Curve= 0 ,0
Exp/Cntr=0.3,0.1

Type RM Length L Ch R = 1 ,5710    ,536,536,536
BEGIN DESCRIPTION:
UNT 011 IN RACR 6.0
END DESCRIPTION:
XS GIS Cut Line= 4
      2223316.37     13234617.68      2222400.57     13234157.61
      2222053.35     13233949.28      2221354.61      13234244.4
#Sta/Elev= 30
    3907  326.45  3950.2  323.78  4004.8  323.82  4228.1  312.99  4256.1  312.97
  4384.4  307.28  4397.9  307.82  4420.3  305.74    4465   304.2    4725  299.95
  4993.5  297.96  4997.3  296.54  5000.1  296.04  5003.3  296.54  5006.2  298.04
  5015.9  298.29  5336.8   299.4  5426.3  301.78  5513.3  303.92  5652.1  308.68
  5699.5  308.99  5728.6  312.16  5842.2  315.37  6026.8  324.32  6040.2  324.75
  6048.5  322.92  6063.9  325.52  6070.2  324.59  6087.6  326.52  6095.3  325.47
#Mann= 5 ,-1 , 0
    3907      .1       0  4997.3     .07       0  5003.3      .1       0
  5426.3     .08       0  5513.3      .1       0
Bank Sta=4997.3,5003.3
XS Rating Curve= 0 ,0
Exp/Cntr=0.3,0.1

Type RM Length L Ch R = 1 ,5174    ,661,661,661
BEGIN DESCRIPTION:
UNT 011 IN RACR 4.0
END DESCRIPTION:
XS GIS Cut Line= 4
      2223625.96     13234261.62      2222438.48     13233581.08
      2221750.98     13233997.74      2221403.75     13234074.14
#Sta/Elev= 30
  3845.1  327.82  3918.4   325.2  4131.6  316.05  4154.3  315.95  4190.6  313.44
  4324.3  309.82  4351.7  307.58  4383.3  307.52  4419.9  305.04  4711.3  295.89
  4880.4  293.47  4961.1  295.73  4984.1  295.04  4990.4  294.43  4993.2  292.96
  4995.9  292.46  4999.2  292.96    5012  294.78  5094.8  295.35    5213  297.16
  5412.4  297.19  5474.9   297.6  5539.7  297.38  5625.1  299.25  5683.9  298.68
  5865.5  303.67  5873.2  303.36  6184.8  313.49  6195.1  314.77  6373.2  321.55
#Mann= 11 ,-1 , 0
  3845.1      .1       0  3918.4     .05       0  4419.9      .1       0
  4993.2     .07       0  4999.2      .1       0  5094.8     .05       0
  5412.4      .1       0  5474.9     .05       0  5683.9      .1       0
  5865.5     .08       0  5873.2      .1       0
Bank Sta=4993.2,4999.2
XS Rating Curve= 0 ,0
Exp/Cntr=0.3,0.1

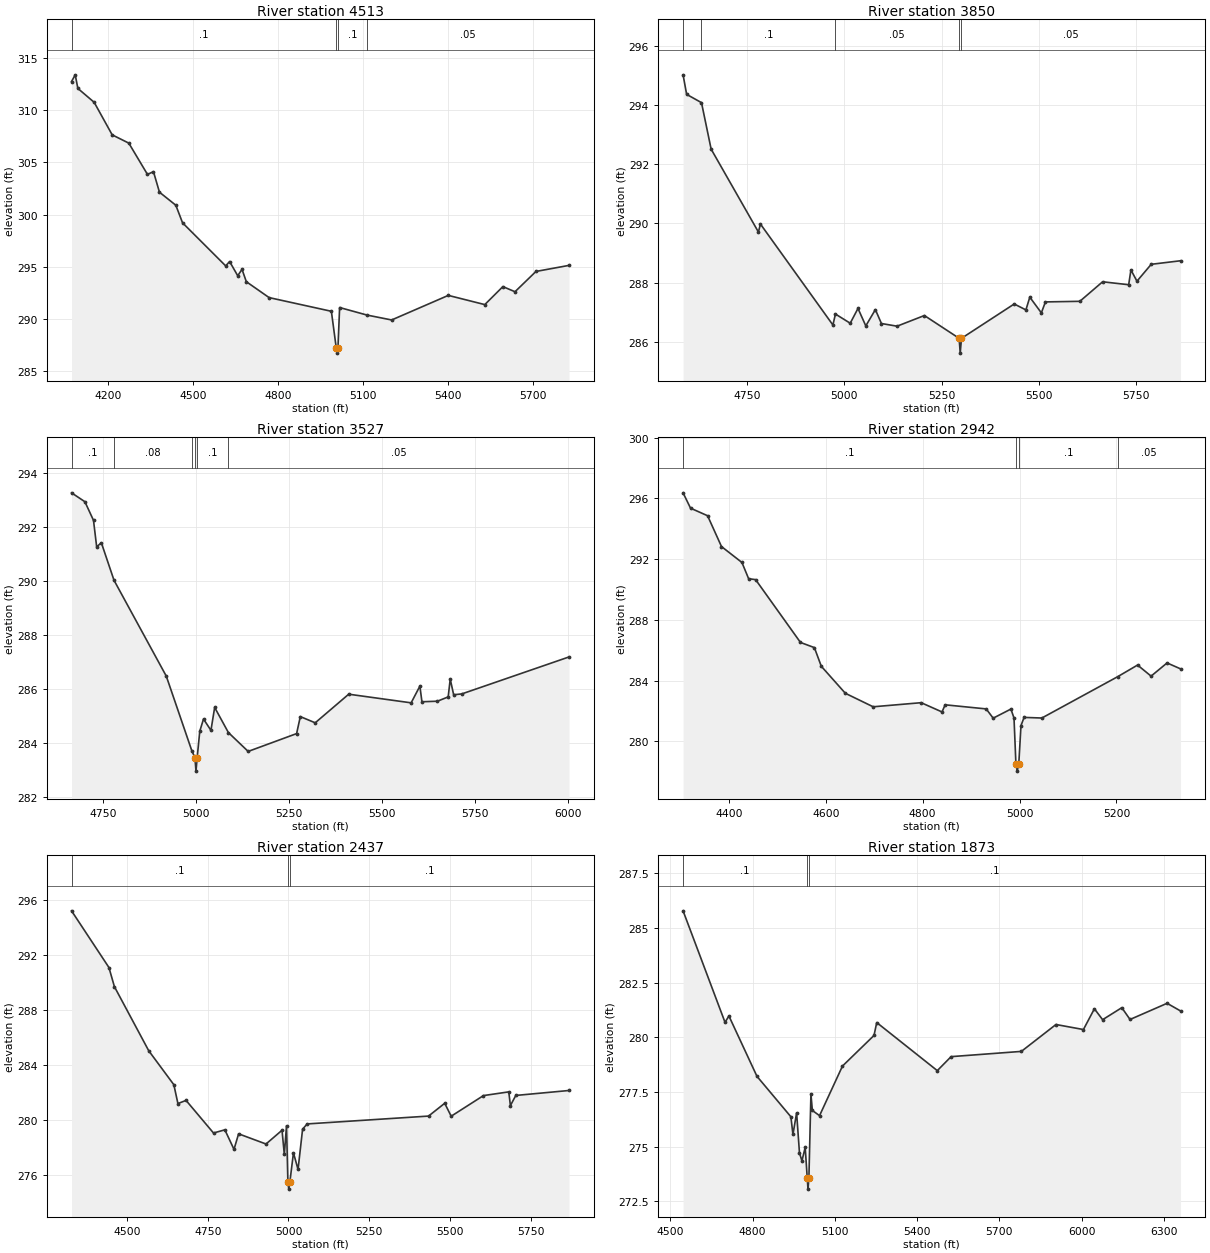
Type RM Length L Ch R = 1 ,4513    ,663,663,663
BEGIN DESCRIPTION:
Mapping XS 8980aa31
END DESCRIPTION:
XS GIS Cut Line= 4
      2223676.86     13233817.25      2223312.29     13233244.36
       2222548.4     13233122.83      2222392.84      13233382.1
#Sta/Elev= 30
  4071.2  312.72  4084.2  313.36  4093.5  312.06  4151.1  310.73  4214.6  307.62
  4273.2  306.83    4339  303.84  4360.2   304.1  4381.3  302.14  4439.1  300.89
  4462.8  299.21    4615  295.09  4628.8  295.51  4657.4  294.15  4672.6  294.76
  4687.8  293.58  4768.1  292.06  4987.8  290.75    5005  287.25  5007.8  286.75
    5011  287.25  5016.9  291.11  5113.4  290.39  5200.4  289.92  5400.3  292.27
    5529  291.39  5592.8  293.11  5635.6  292.62  5709.5  294.56  5826.1  295.14
#Mann= 4 ,-1 , 0
  4071.2      .1       0    5005     .07       0    5011      .1       0
  5113.4     .05       0
Bank Sta=5005,5011
XS Rating Curve= 0 ,0
Exp/Cntr=0.3,0.1

Type RM Length L Ch R = 1 ,3850    ,323,323,323
BEGIN DESCRIPTION:
UNT 011 IN RACR 5.0
END DESCRIPTION:
XS GIS Cut Line= 4
      2223626.51     13232661.02      2223422.54     13232595.92
      2222676.01     13232665.37      2222406.89     13232830.31
#Sta/Elev= 30
  4585.3  295.02  4594.5  294.36  4632.7  294.08  4657.5  292.51  4779.1  289.71
  4784.3  289.98  4970.7  286.57  4977.2  286.94  5015.2  286.63  5035.2  287.13
  5055.3  286.54  5079.9  287.09  5095.5  286.62  5135.7  286.53    5206  286.89
  5295.4  286.12  5298.1  285.62  5301.4  286.12    5437  287.28  5467.1  287.08
  5477.1  287.51  5506.8  286.98  5517.3  287.35  5605.8  287.37  5664.4  288.03
  5731.4  287.93  5737.2  288.43  5752.7  288.05  5789.4  288.62  5864.8  288.74
#Mann= 5 ,-1 , 0
  4585.3     .08       0  4632.7      .1       0  4977.2     .05       0
  5295.4    .035       0  5301.4     .05       0
Bank Sta=5295.4,5301.4
XS Rating Curve= 0 ,0
Exp/Cntr=0.3,0.1

Type RM Length L Ch R = 1 ,3527    ,585,585,585
BEGIN DESCRIPTION:
Mapping XS 4fb322fd
END DESCRIPTION:
XS GIS Cut Line= 4
      2223513.72      13232344.2      2223357.43      13232292.1
      2222641.29     13232309.46      2222223.18     13232489.71
#Sta/Elev= 30
  4665.3  293.26  4701.2  292.93  4724.3  292.24  4732.8  291.26  4745.4  291.41
  4779.4  290.02  4919.8  286.47  4988.3  283.71  4996.8  283.45  4999.6  282.95
  5002.8  283.45  5009.8  284.43  5019.8  284.88  5039.8  284.46  5049.8  285.31
  5086.6  284.38  5139.8  283.68  5269.9  284.34  5279.9  284.97  5319.9  284.74
  5409.9   285.8  5577.6  285.48  5601.1   286.1  5606.6  285.52  5648.2  285.54
  5677.1   285.7  5682.6  286.36  5691.8  285.78  5713.6  285.81  6001.7  287.18
#Mann= 6 ,-1 , 0
  4665.3      .1       0  4779.4     .08       0  4988.3      .1       0
  4996.8     .07       0  5002.8      .1       0  5086.6     .05       0
Bank Sta=4996.8,5002.8
XS Rating Curve= 0 ,0
Exp/Cntr=0.3,0.1

Type RM Length L Ch R = 1 ,2942    ,505,505,505
BEGIN DESCRIPTION:
UNT 011 IN RACR 3.0
END DESCRIPTION:
XS GIS Cut Line= 3
      2223591.79     13232213.96       2222901.7     13231649.74
      2222772.09     13231688.62
#Sta/Elev= 30
  4305.6  296.37    4321  295.36  4356.2  294.86  4384.9  292.83  4427.1  291.78
  4440.9  290.71  4455.3  290.65  4547.9  286.51  4576.6  286.17  4590.9  284.94
  4640.5  283.16  4697.9  282.27    4797  282.54    4840  281.93  4846.5   282.4
  4931.2  282.13  4945.6  281.52  4982.2  282.12  4988.6  281.53  4992.5  278.53
  4995.2  278.03  4998.5  278.53    5003  281.03  5009.4  281.57  5046.1  281.53
  5202.9  284.26  5243.6  285.02  5271.5  284.29  5304.5  285.16  5332.3  284.77
#Mann= 4 ,-1 , 0
  4305.6      .1       0  4992.5     .07       0  4998.5      .1       0
  5202.9     .05       0
Bank Sta=4992.5,4998.5
XS Rating Curve= 0 ,0
Exp/Cntr=0.3,0.1

Type RM Length L Ch R = 1 ,2437    ,564,564,564
BEGIN DESCRIPTION:
Mapping XS 53fbddc6
END DESCRIPTION:
XS GIS Cut Line= 4
      2223769.76     13232088.12      2223678.61     13231771.27
      2223253.26     13231319.88      2222662.94     13231337.24
#Sta/Elev= 30
  4328.2  295.19    4444  291.07  4460.9  289.68  4567.2  285.02    4645  282.55
  4657.6  281.18  4682.8  281.41  4767.8  279.04    4803  279.27  4831.3  277.85
  4845.5  278.98  4930.4  278.24    4980  279.24  4987.1  277.48  4993.9  279.57
  4998.2  275.46    5001  274.96  5004.2  275.46  5015.4   277.6  5029.6  276.39
  5043.7  279.32  5057.9   279.7  5433.7  280.27  5483.8   281.2  5503.8  280.26
  5603.8  281.76  5682.2  282.03  5687.2  281.03  5703.9  281.77  5868.7  282.13
#Mann= 3 ,-1 , 0
  4328.2      .1       0  4998.2     .07       0  5004.2      .1       0
Bank Sta=4998.2,5004.2
XS Rating Curve= 0 ,0
Exp/Cntr=0.3,0.1

Type RM Length L Ch R = 1 ,1873    ,586,586,586
BEGIN DESCRIPTION:
UNT 011 IN RACR 2.0
END DESCRIPTION:
XS GIS Cut Line= 5
      2223986.78      13231983.9      2224051.88     13231758.25
      2223908.65      13231289.5      2223261.94     13231215.71
      2222823.56     13231211.37
#Sta/Elev= 30
  4546.4  285.79  4699.4  280.69  4713.6  280.98  4815.9  278.22  4939.6  276.37
  4947.1  275.56  4960.5  276.55  4970.9  274.72  4979.9  274.35  4991.8  274.97
  4999.3  273.56    5002  273.06  5005.3  273.56  5012.7  277.41  5017.9  276.66
  5044.1  276.42  5127.8  278.69  5242.8  280.09  5252.7  280.68  5473.6  278.48
  5523.9  279.12  5780.2  279.36  5906.4  280.59  6006.5  280.36  6046.5  281.31
  6076.5  280.81  6146.5  281.36  6176.5  280.82  6311.7  281.56  6360.7  281.21
#Mann= 3 ,-1 , 0
  4546.4      .1       0  4999.3     .07       0  5005.3      .1       0
Bank Sta=4999.3,5005.3
XS Rating Curve= 0 ,0
Exp/Cntr=0.3,0.1

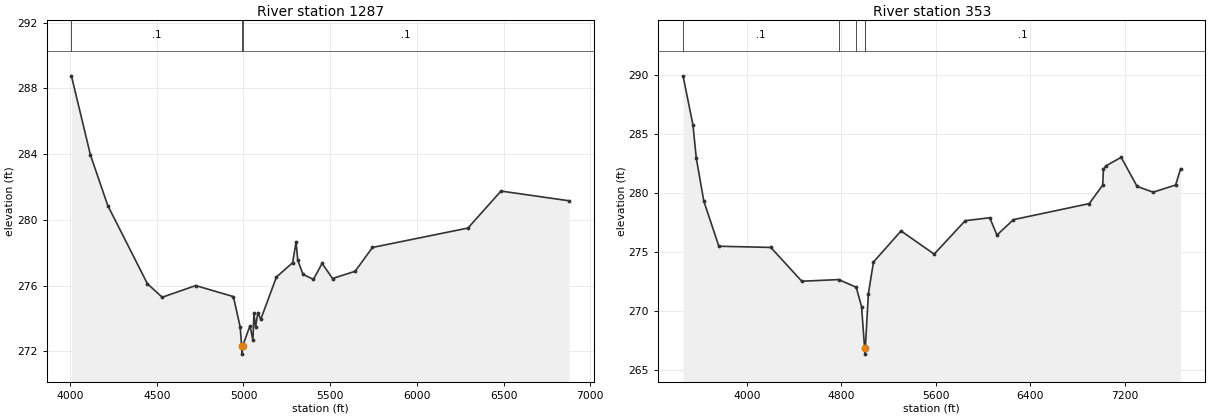
Type RM Length L Ch R = 1 ,1287    ,934,934,934
BEGIN DESCRIPTION:
Mapping XS 9fd2fd0c
END DESCRIPTION:
XS GIS Cut Line= 4
      2224169.05     13232253.05      2224629.13     13231649.74
      2224407.78     13231194.01      2222806.25     13231115.89
#Sta/Elev= 30
  4007.8  288.77  4117.6  283.95  4217.4  280.88    4446  276.12  4531.3   275.3
  4724.6  276.01  4941.7  275.34    4981  273.49  4989.4  272.34  4992.2  271.84
  4995.4  272.34  5037.5  273.57  5054.5  272.67  5060.1  274.33  5069.9   273.5
  5082.7  274.36  5099.7  273.96  5189.9  276.53  5283.2   277.4  5303.3  278.66
  5312.8  277.56  5343.3  276.69  5403.4  276.39  5453.4  277.36  5513.5  276.44
  5643.7  276.88  5743.8  278.33  6294.4  279.51  6484.7  281.76  6876.6  281.17
#Mann= 3 ,-1 , 0
  4007.8      .1       0  4989.4     .07       0  4995.4      .1       0
Bank Sta=4989.4,4995.4
XS Rating Curve= 0 ,0
Exp/Cntr=0.3,0.1

Type RM Length L Ch R = 1 ,353     ,0,0,0
BEGIN DESCRIPTION:
UNT 011 IN RACR 1.0
END DESCRIPTION:
XS GIS Cut Line= 4
      2224321.25     13232378.55       2225369.9     13231475.74
       2225119.9     13231163.24      2222696.25     13230996.58
#Sta/Elev= 30
  3459.5  289.96  3543.5   285.8    3572  282.96  3635.7  279.32    3763  275.49
  4202.9  275.39  4465.2  272.52  4777.5  272.66  4926.1  272.01  4971.5  270.37
  4997.3  266.83  5000.1  266.33  5003.3  266.83  5029.2  271.46  5072.3  274.15
  5305.8  276.79  5586.4  274.82  5849.4  277.66  6057.5  277.91  6117.7  276.44
    6258  277.75  6899.5  279.11  7013.8  280.68  7019.8  282.01  7039.8  282.31
  7170.1  283.04  7304.9  280.57  7440.8  280.08  7631.2  280.69  7672.8  282.07
#Mann= 5 ,-1 , 0
  3459.5      .1       0  4777.5     .05       0  4926.1      .1       0
  4997.3     .07       0  5003.3      .1       0
Bank Sta=4997.3,5003.3
XS Rating Curve= 0 ,0
Exp/Cntr=0.3,0.1

Chan Stop Cuts=-1
Use User Specified Reach Order=0
Composite Channel Slope=5