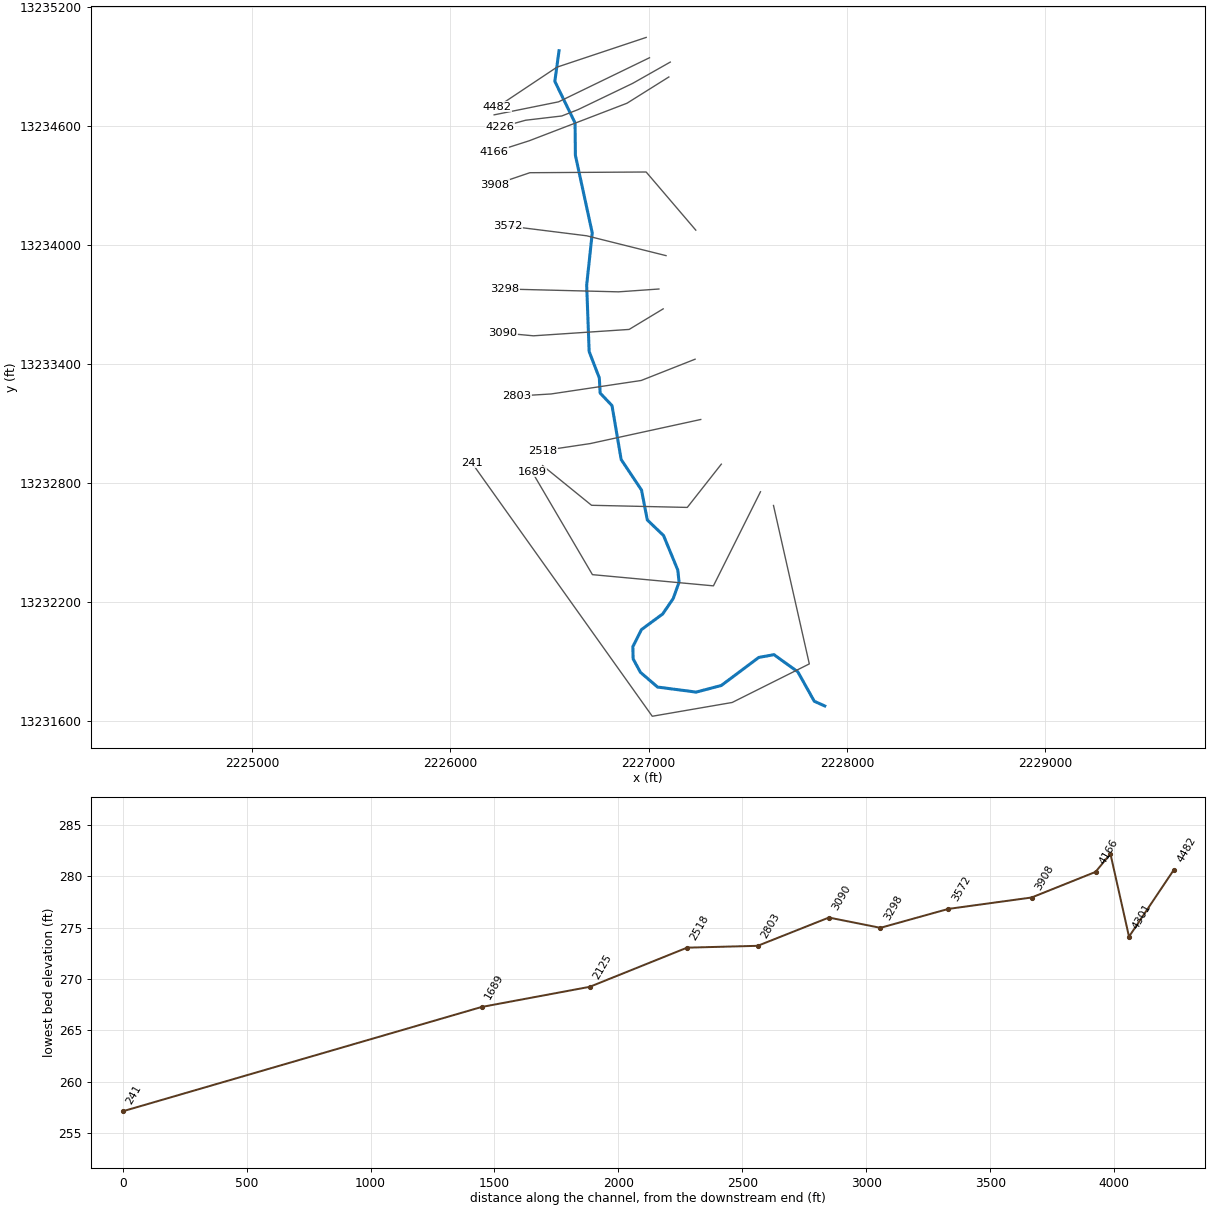
--- UNT 012 IN RACR.prj (project) ---

Proj Title=UNT 012 IN RACR Base Level Engineering
Current Plan=p01
Default Exp/Contr=0.3,0.1
English Units
Geom File=g01
Flow File=f01
Plan File=p01
BEGIN DESCRIPTION:
UNT 012 IN RACR
END DESCRIPTION:

--- UNT 012 IN RACR.p01 (plan) ---

Plan Title=Multiple Run
Short Identifier=Multiple
Geom File=g01
Flow File=f01
Subcritical Flow
K Sum by GR= 0
Std Step Tol= 0.01
Critical Tol= 0.01
Num of Std Step Trials= 20
Max Error Tol= 0.3
Flow Tol Ratio= 0.001
Split Flow NTrial= 30
Split Flow Tol= 0.02
Split Flow Ratio= 0.02
Log Output Level= 0
Friction Slope Method= 1
Unsteady Friction Slope Method= 2
Unsteady Bridges Friction Slope Method= 1
Parabolic Critical Depth
Global Vel Dist=  1 , 1 , 1
Global Log Level= 0
CheckData=True
Encroach Param= -1, 0, 0, 0
BEGIN DESCRIPTION:
Multiple Run
END DESCRIPTION:

--- UNT 012 IN RACR.f01 (steady flow) ---

Flow Title=Multiple
Number of Profiles=7
Profile Names=10-year,25-year,50-year,1pct_min,100-year,1pct_plu,500-year
River Rch & RM= UNT 012 IN RACR,Reach-1,4482
     241     337     418     382     517     699     802
River Rch & RM= UNT 012 IN RACR,Reach-1,3572
     276     389     483     443     598     809     932
Boundary for River Rch & Prof#=UNT 012 IN RACR,Reach-1,1
Up Type=0
Dn Type=3
Dn Slope=0.005
Boundary for River Rch & Prof#=UNT 012 IN RACR,Reach-1,2
Up Type=0
Dn Type=3
Dn Slope=0.005
Boundary for River Rch & Prof#=UNT 012 IN RACR,Reach-1,3
Up Type=0
Dn Type=3
Dn Slope=0.005
Boundary for River Rch & Prof#=UNT 012 IN RACR,Reach-1,4
Up Type=0
Dn Type=3
Dn Slope=0.005
Boundary for River Rch & Prof#=UNT 012 IN RACR,Reach-1,5
Up Type=0
Dn Type=3
Dn Slope=0.005
Boundary for River Rch & Prof#=UNT 012 IN RACR,Reach-1,6
Up Type=0
Dn Type=3
Dn Slope=0.005
Boundary for River Rch & Prof#=UNT 012 IN RACR,Reach-1,7
Up Type=0
Dn Type=3
Dn Slope=0.005

--- UNT 012 IN RACR.g01 (geometry) ---

Geom Title=Existing Conditions

River Reach=UNT 012 IN RACR,Reach-1
Reach XY= 30
      2226548.46     13234979.72      2226527.10     13234825.51
      2226629.18     13234615.79      2226630.85     13234452.67
      2226715.82     13234061.18      2226687.72     13233797.94
      2226700.22     13233463.28      2226751.40     13233330.60
      2226755.61     13233253.95      2226815.41     13233191.00
      2226861.65     13232918.65      2226964.20     13232765.10
      2226993.32     13232614.46      2227075.22     13232535.90
      2227147.14     13232361.45      2227153.37     13232300.64
      2227123.93     13232218.44      2227070.88     13232140.48
      2226963.75     13232061.63      2226920.39     13231975.53
      2226921.92     13231914.04      2226958.60     13231846.45
      2227045.16     13231772.08      2227239.63     13231746.63
      2227366.39     13231780.06      2227555.17     13231921.32
      2227631.91     13231935.36      2227752.39     13231848.46
      2227835.11     13231700.39      2227887.72     13231676.86

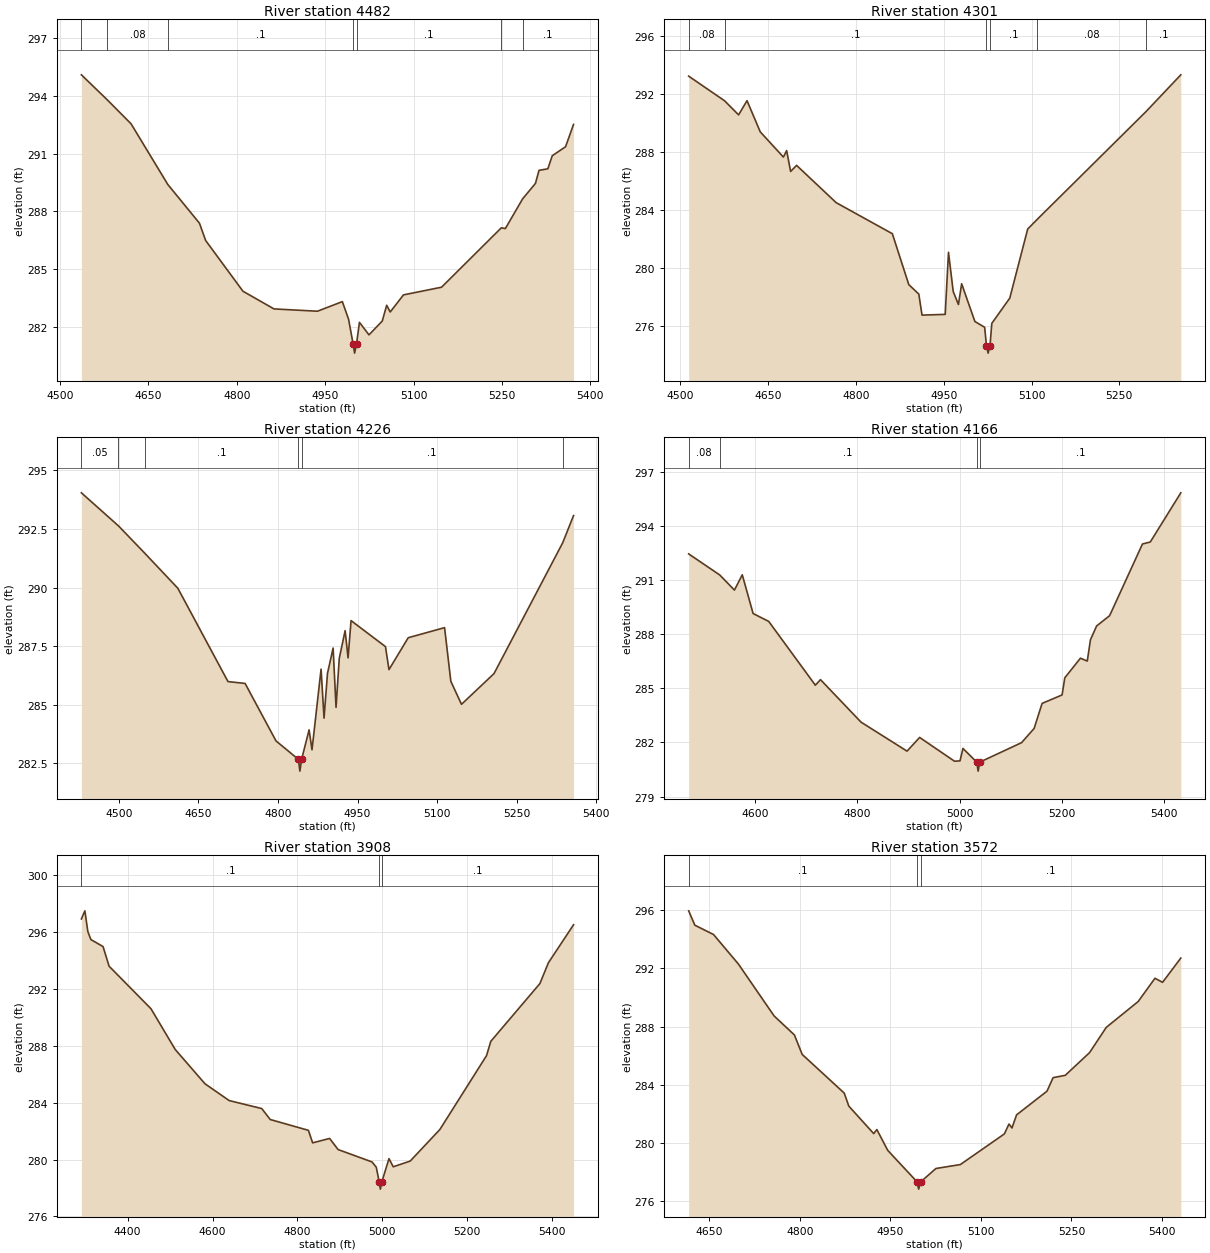
Type RM Length L Ch R = 1,4482,181,181,181
BEGIN DESCRIPTION:
UNT 012 IN RACR 8.0
END DESCRIPTION:
XS GIS Cut Line= 3
      2226987.72     13235046.85      2226537.72     13234896.85
      2226237.71     13234696.85
#Sta/Elev= 30
  4536.5  295.10  4580.7  293.79  4620.8  292.55  4683.2  289.39  4736.8  287.38
  4747.3  286.48  4810.6  283.84  4863.3  282.92  4937.0  282.80  4979.2  283.30
  4989.8  282.38  4997.3  281.12  5000.0  280.62  5003.3  281.12  5008.2  282.22
  5024.4  281.57  5046.9  282.29  5054.4  283.11  5060.4  282.76  5082.9  283.65
  5147.5  284.05  5248.9  287.14  5255.7  287.10  5285.1  288.65  5306.8  289.45
  5312.8  290.13  5327.8  290.21  5335.3  290.89  5357.9  291.36  5371.4  292.52
#Mann=7,-1,0
  4536.5    0.05       0  4580.7    0.08       0  4683.2     0.1       0
  4997.3    0.07       0  5003.3     0.1       0  5248.9    0.08       0
  5285.1     0.1       0
Bank Sta=4997.3,5003.3
Exp/Cntr=0.3,0.1

Type RM Length L Ch R = 1,4301,75,75,75
BEGIN DESCRIPTION:
Mapping XS 9e3e7b9b
END DESCRIPTION:
XS GIS Cut Line= 3
      2227004.46     13234944.36      2226546.12     13234722.14
      2226221.26     13234656.47
#Sta/Elev= 30
  4514.2  293.20  4575.6  291.50  4599.5  290.53  4613.9  291.51  4636.5  289.36
  4676.1  287.62  4681.6  288.07  4688.4  286.63  4698.6  287.05  4766.2  284.48
  4862.2  282.34  4890.3  278.83  4907.4  278.18  4912.9  276.73  4952.5  276.78
  4958.1  281.06  4966.2  278.35  4975.1  277.46  4980.6  278.89  5003.2  276.29
  5019.9  275.89  5023.0  274.61  5025.8  274.11  5029.0  274.61  5032.1  276.16
  5062.8  277.90  5093.4  282.66  5109.7  283.33  5295.4  290.75  5355.0  293.29
#Mann=6,-1,0
  4514.2    0.08       0  4575.6     0.1       0  5023.0    0.07       0
  5029.0     0.1       0  5109.7    0.08       0  5295.4     0.1       0
Bank Sta=5023,5029
Exp/Cntr=0.3,0.1

Type RM Length L Ch R = 1,4226,60,60,60
BEGIN DESCRIPTION:
Mapping XS 0a730dc4
END DESCRIPTION:
XS GIS Cut Line= 6
      2227109.09     13234922.48      2226919.62     13234815.23
      2226644.37     13234682.97      2226562.16     13234650.80
      2226379.85     13234629.35      2226251.94     13234593.82
#Sta/Elev= 30
  4429.5  294.04  4499.4  292.63  4548.7  291.47  4611.3  289.97  4705.8  285.99
  4738.1  285.91  4796.3  283.46  4838.6  282.67  4841.4  282.17  4844.6  282.67
  4858.7  283.93  4864.2  283.08  4881.3  286.52  4886.9  284.43  4893.4  286.34
  4904.0  287.42  4909.5  284.89  4915.6  286.98  4926.6  288.16  4932.2  287.00
  4937.8  288.59  5002.7  287.48  5009.3  286.50  5045.6  287.86  5114.1  288.29
  5125.9  286.00  5146.0  285.02  5207.3  286.33  5336.8  291.91  5357.2  293.07
#Mann=6,-1,0
  4429.5    0.05       0  4499.4    0.08       0  4548.7     0.1       0
  4838.6    0.07       0  4844.6     0.1       0  5336.8    0.08       0
Bank Sta=4838.6,4844.6
Exp/Cntr=0.3,0.1

Type RM Length L Ch R = 1,4166,258,258,258
BEGIN DESCRIPTION:
Mapping XS f5f0d07a
END DESCRIPTION:
XS GIS Cut Line= 4
      2227101.89     13234847.38      2226891.02     13234715.14
      2226397.73     13234525.69      2226220.89     13234469.10
#Sta/Elev= 30
  4470.0  292.47  4530.8  291.30  4559.6  290.46  4574.9  291.31  4596.1  289.16
  4626.7  288.72  4717.9  285.18  4727.9  285.49  4807.3  283.13  4897.3  281.52
  4922.0  282.28  4990.2  280.96  5001.0  280.98  5006.7  281.67  5033.7  280.91
  5036.4  280.41  5039.7  280.91  5121.4  281.99  5146.0  282.78  5161.6  284.17
  5200.7  284.64  5206.0  285.59  5236.6  286.68  5250.0  286.52  5256.2  287.70
  5268.3  288.47  5293.7  289.04  5358.0  293.02  5373.3  293.13  5433.0  295.86
#Mann=4,-1,0
  4470.0    0.08       0  4530.8     0.1       0  5033.7    0.07       0
  5039.7     0.1       0
Bank Sta=5033.7,5039.7
Exp/Cntr=0.3,0.1

Type RM Length L Ch R = 1,3908,336,336,336
BEGIN DESCRIPTION:
UNT 012 IN RACR 7.0
END DESCRIPTION:
XS GIS Cut Line= 4
      2227237.74     13234075.31      2226987.53     13234368.41
      2226401.30     13234364.83      2226222.65     13234304.09
#Sta/Elev= 30
  4290.9  296.90  4299.1  297.47  4306.1  296.01  4313.3  295.45  4341.9  294.96
  4356.2  293.58  4455.0  290.59  4512.1  287.73  4582.3  285.32  4639.4  284.14
  4716.1  283.58  4736.1  282.81  4826.1  282.05  4836.1  281.17  4876.1  281.48
  4896.1  280.70  4976.1  279.83  4986.1  279.46  4993.1  278.42  4995.8  277.92
  4999.1  278.42  5016.1  280.06  5026.1  279.49  5066.1  279.89  5136.1  282.11
  5246.1  287.30  5256.1  288.30  5371.9  292.36  5391.9  293.82  5451.2  296.49
#Mann=3,-1,0
  4290.9     0.1       0  4993.1    0.07       0  4999.1     0.1       0
Bank Sta=4993.1,4999.1
Exp/Cntr=0.3,0.1

Type RM Length L Ch R = 1,3572,274,274,274
BEGIN DESCRIPTION:
UNT 012 IN RACR 6.0
END DESCRIPTION:
XS GIS Cut Line= 3
      2227087.69     13233946.86      2226687.72     13234046.85
      2226287.71     13234096.86
#Sta/Elev= 30
  4615.9  295.96  4626.2  294.97  4657.1  294.33  4698.3  292.30  4757.6  288.72
  4791.1  287.42  4804.0  286.08  4873.6  283.42  4881.3  282.52  4922.5  280.63
  4927.7  280.91  4945.7  279.48  4994.3  277.31  4997.0  276.81  5000.3  277.31
  5025.6  278.23  5066.0  278.50  5139.0  280.61  5146.6  281.29  5151.6  281.02
  5159.2  281.92  5209.6  283.55  5219.7  284.48  5239.8  284.64  5280.1  286.20
  5307.8  287.94  5360.7  289.72  5388.5  291.32  5401.1  291.04  5431.3  292.71
#Mann=3,-1,0
  4615.9     0.1       0  4994.3    0.07       0  5000.3     0.1       0
Bank Sta=4994.3,5000.3
Exp/Cntr=0.3,0.1

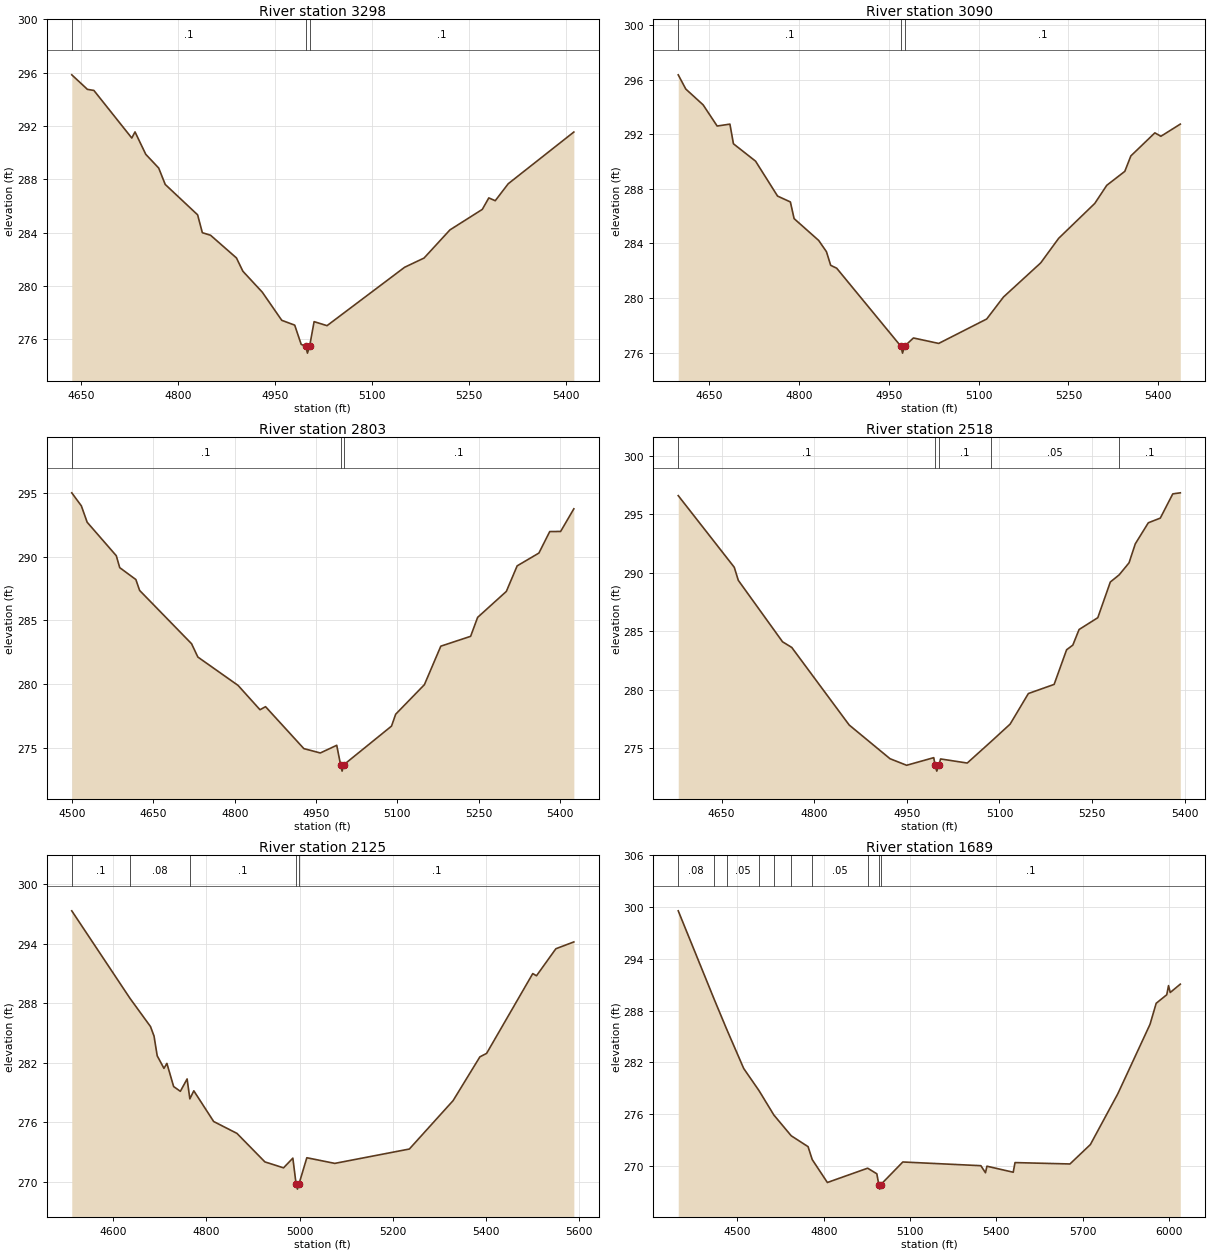
Type RM Length L Ch R = 1,3298,208,208,208
BEGIN DESCRIPTION:
Mapping XS 547f8a79
END DESCRIPTION:
XS GIS Cut Line= 3
      2227051.84     13233778.60      2226848.12     13233764.30
      2226276.21     13233778.60
#Sta/Elev= 30
  4635.5  295.84  4659.7  294.75  4669.7  294.67  4728.3  291.10  4733.3  291.56
  4749.9  289.88  4769.9  288.85  4780.0  287.62  4830.1  285.34  4837.4  284.00
  4850.1  283.81  4890.1  282.11  4900.1  281.11  4930.1  279.54  4960.2  277.43
  4980.2  277.07  4990.2  275.63  4997.2  275.47  4999.9  274.97  5003.2  275.47
  5010.2  277.33  5030.2  277.03  5150.2  281.41  5180.2  282.10  5220.2  284.21
  5270.3  285.75  5280.3  286.61  5290.3  286.40  5310.3  287.67  5411.8  291.55
#Mann=3,-1,0
  4635.5     0.1       0  4997.2    0.07       0  5003.2     0.1       0
Bank Sta=4997.2,5003.2
Exp/Cntr=0.3,0.1

Type RM Length L Ch R = 1,3090,287,287,287
BEGIN DESCRIPTION:
UNT 012 IN RACR 5.0
END DESCRIPTION:
XS GIS Cut Line= 4
      2227073.32     13233678.50      2226901.74     13233574.85
      2226419.17     13233542.67      2226265.43     13233556.98
#Sta/Elev= 30
  4598.4  296.35  4611.0  295.31  4640.0  294.15  4663.4  292.60  4684.7  292.74
  4690.6  291.30  4727.5  290.03  4764.3  287.47  4785.7  287.04  4791.9  285.82
  4833.0  284.22  4845.9  283.40  4853.0  282.40  4863.0  282.19  4970.3  276.47
  4973.0  275.97  4976.3  276.47  4991.2  277.08  5033.4  276.68  5113.6  278.47
  5141.6  280.08  5203.8  282.58  5233.8  284.38  5294.0  286.93  5314.1  288.26
  5344.2  289.28  5354.3  290.41  5394.4  292.10  5404.5  291.85  5436.9  292.74
#Mann=3,-1,0
  4598.4     0.1       0  4970.3    0.07       0  4976.3     0.1       0
Bank Sta=4970.3,4976.3
Exp/Cntr=0.3,0.1

Type RM Length L Ch R = 1,2803,285,285,285
BEGIN DESCRIPTION:
Mapping XS c2e86c9f
END DESCRIPTION:
XS GIS Cut Line= 4
      2227234.16     13233424.70      2226962.51     13233317.47
      2226508.54     13233249.56      2226333.34     13233238.83
#Sta/Elev= 30
  4499.3  294.98  4517.0  293.96  4527.7  292.68  4581.5  290.06  4587.8  289.13
  4617.6  288.20  4624.5  287.35  4720.4  283.18  4732.0  282.14  4806.3  279.92
  4846.7  278.02  4856.9  278.26  4927.6  274.98  4958.0  274.64  4988.3  275.24
  4995.4  273.72  4998.2  273.22  5001.4  273.72  5089.4  276.74  5097.1  277.67
  5150.1  279.98  5180.4  282.99  5235.4  283.76  5248.3  285.24  5301.3  287.27
  5321.3  289.27  5361.4  290.27  5381.4  291.95  5401.5  291.96  5425.9  293.73
#Mann=3,-1,0
  4499.3     0.1       0  4995.4    0.07       0  5001.4     0.1       0
Bank Sta=4995.4,5001.4
Exp/Cntr=0.3,0.1

Type RM Length L Ch R = 1,2518,393,393,393
BEGIN DESCRIPTION:
UNT 012 IN RACR 4.0
END DESCRIPTION:
XS GIS Cut Line= 3
      2227262.78     13233120.87      2226705.14     13232999.34
      2226465.63     13232963.59
#Sta/Elev= 30
  4579.9  296.58  4670.6  290.46  4677.2  289.34  4748.8  284.09  4763.7  283.61
  4856.7  276.98  4922.8  274.10  4949.7  273.54  4993.6  274.19  4995.8  273.54
  4998.5  273.04  5001.8  273.54  5004.7  274.08  5047.8  273.73  5086.3  275.56
  5117.3  277.06  5146.8  279.67  5188.5  280.45  5208.7  283.41  5218.8  283.81
  5228.9  285.14  5259.2  286.15  5279.5  289.20  5293.8  289.81  5309.8  290.84
  5319.9  292.46  5341.0  294.26  5360.4  294.66  5380.6  296.73  5392.8  296.82
#Mann=5,-1,0
  4579.9     0.1       0  4995.8    0.07       0  5001.8     0.1       0
  5086.3    0.05       0  5293.8     0.1       0
Bank Sta=4995.8,5001.8
Exp/Cntr=0.3,0.1

Type RM Length L Ch R = 1,2125,436,436,436
BEGIN DESCRIPTION:
UNT 012 IN RACR 3.0
END DESCRIPTION:
XS GIS Cut Line= 4
      2227366.42     13232895.65      2227194.86     13232677.62
      2226712.29     13232688.35      2226465.63     13232888.54
#Sta/Elev= 30
  4511.0  297.34  4635.7  288.52  4680.0  285.65  4687.6  284.69  4694.4  282.70
  4708.9  281.43  4715.2  281.93  4729.7  279.59  4744.1  279.11  4758.6  280.36
  4764.5  278.35  4773.0  279.16  4815.6  276.06  4865.6  274.86  4925.6  271.98
  4965.6  271.38  4985.6  272.36  4992.6  269.73  4995.4  269.23  4998.6  269.73
  5015.6  272.40  5075.6  271.83  5235.7  273.28  5329.6  278.17  5387.1  282.59
  5401.5  282.94  5500.6  291.00  5508.6  290.78  5550.2  293.51  5588.8  294.20
#Mann=5,-1,0
  4511.0     0.1       0  4635.7    0.08       0  4764.5     0.1       0
  4992.6    0.07       0  4998.6     0.1       0
Bank Sta=4992.6,4998.6
Exp/Cntr=0.3,0.1

Type RM Length L Ch R = 1,1689,1448,1448,1448
BEGIN DESCRIPTION:
UNT 012 IN RACR 2.0
END DESCRIPTION:
XS GIS Cut Line= 4
      2227563.82     13232756.63      2227326.63     13232282.25
      2226716.72     13232338.73      2226412.23     13232857.48
#Sta/Elev= 30
  4294.6  299.57  4419.8  289.28  4462.9  285.83  4522.1  281.27  4575.1  278.71
  4626.9  275.87  4687.2  273.46  4745.7  272.20  4760.1  270.70  4812.8  268.04
  4952.7  269.70  4984.6  269.05  4991.6  267.77  4994.4  267.27  4997.6  267.77
  5074.9  270.42  5346.1  269.99  5362.1  269.17  5367.1  269.93  5458.5  269.23
  5464.7  270.35  5655.6  270.19  5726.5  272.44  5822.2  278.36  5933.7  286.39
  5955.2  288.84  5991.9  289.83  5998.1  290.89  6003.9  290.09  6039.0  291.06
#Mann=10,-1,0
  4294.6    0.08       0  4419.8     0.1       0  4462.9    0.05       0
  4575.1     0.1       0  4626.9    0.05       0  4687.2     0.1       0
  4760.1    0.05       0  4952.7     0.1       0  4991.6    0.07       0
  4997.6     0.1       0
Bank Sta=4991.6,4997.6
Exp/Cntr=0.3,0.1

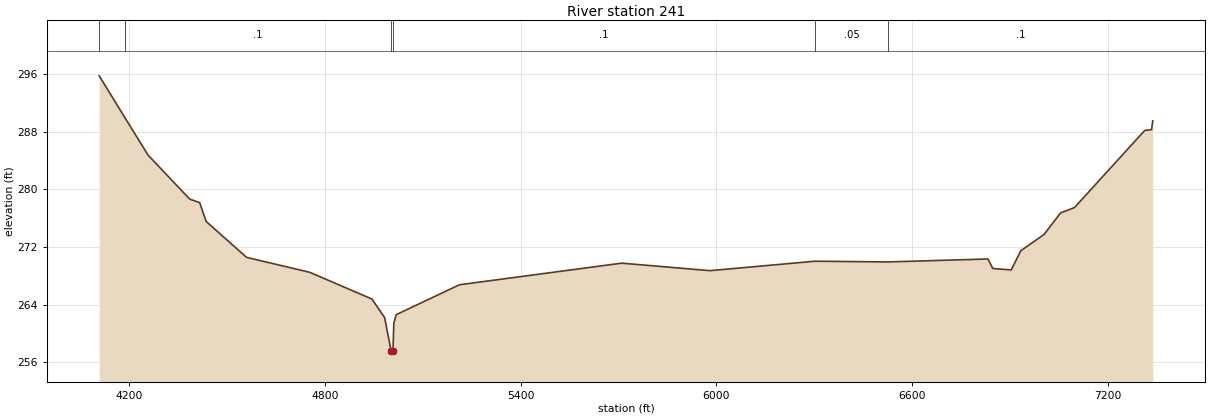
Type RM Length L Ch R = 1,241,0,0,0
BEGIN DESCRIPTION:
UNT 012 IN RACR 1.0
END DESCRIPTION:
XS GIS Cut Line= 5
      2227629.46     13232687.39      2227810.01     13231888.80
      2227421.12     13231694.36      2227018.34     13231624.91
      2226108.91     13232902.29
#Sta/Elev= 30
  4107.4  295.76  4185.9  289.97  4257.4  284.74  4384.8  278.65  4415.5  278.15
  4435.3  275.54  4559.1  270.56  4752.9  268.48  4943.6  264.77  4982.7  262.18
  5002.1  257.62  5004.8  257.12  5008.1  257.62  5010.7  261.38  5018.1  262.60
  5211.9  266.75  5709.4  269.75  5980.4  268.71  6302.0  270.02  6526.0  269.92
  6832.5  270.33  6847.2  269.01  6903.8  268.81  6933.3  271.48  7004.6  273.74
  7055.0  276.72  7097.8  277.47  7313.2  288.18  7334.1  288.29  7337.7  289.51
#Mann=6,-1,0
  4107.4    0.08       0  4185.9     0.1       0  5002.1    0.07       0
  5008.1     0.1       0  6302.0    0.05       0  6526.0     0.1       0
Bank Sta=5002.1,5008.1
Exp/Cntr=0.3,0.1

Chan Stop Cuts=-1