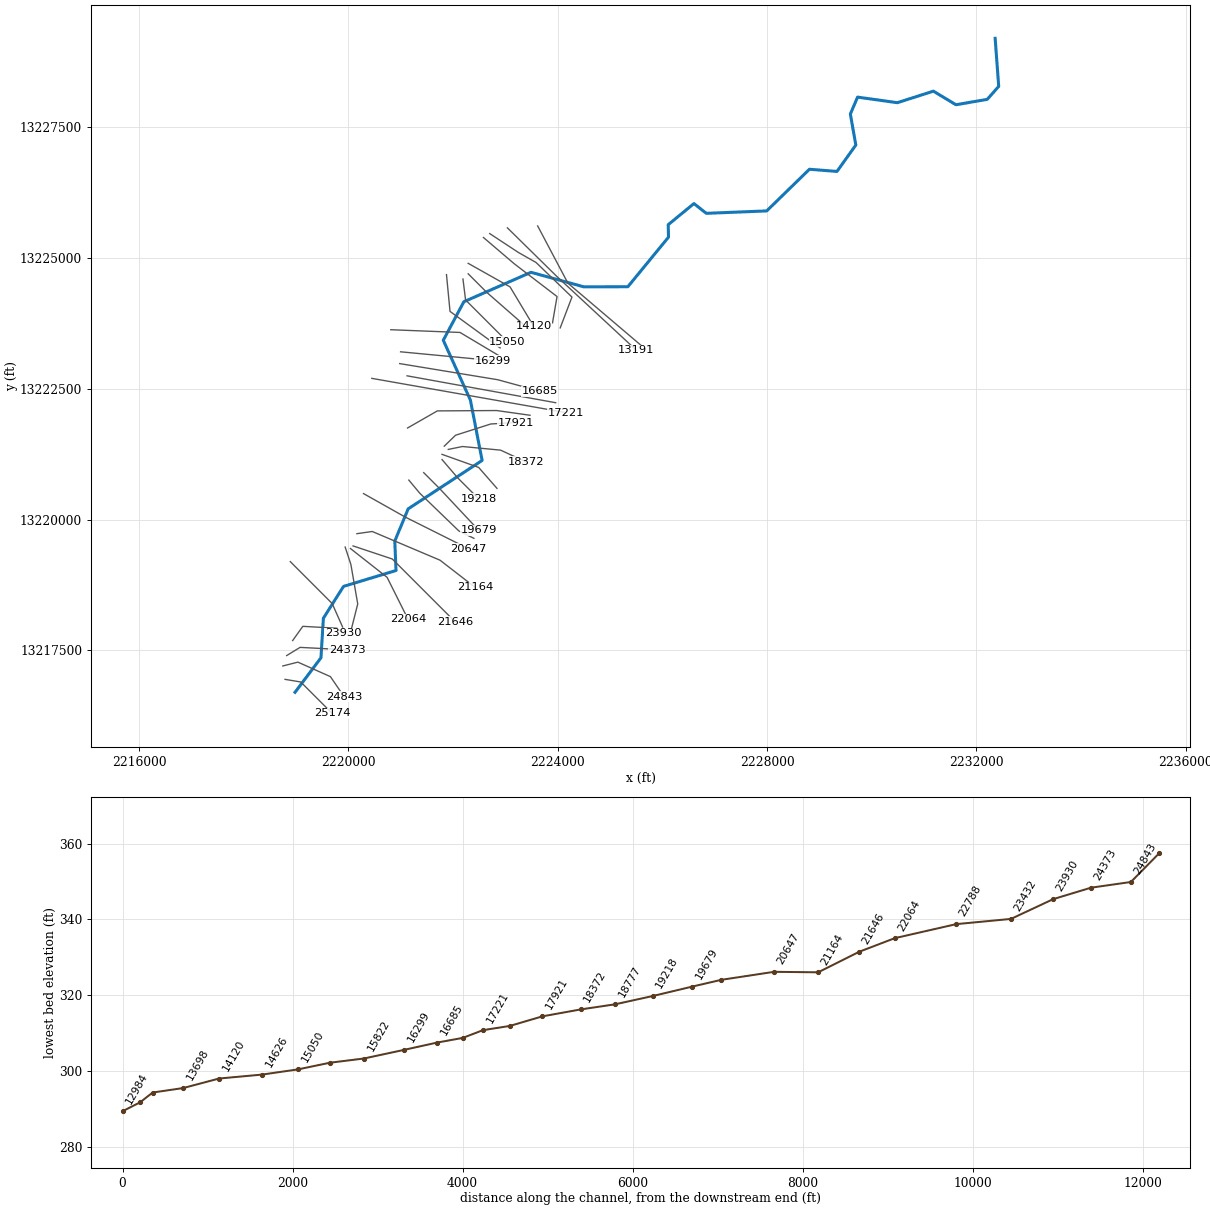
--- UNT 013 IN RACR.prj (project) ---

Proj Title=UNT 013 IN RACR Base Level Engineering
Current Plan=p01
Default Exp/Contr=0.3,0.1
English Units
Geom File=g01
Flow File=f01
Plan File=p01
Y Axis Title=Elevation
X Axis Title(PF)=Main Channel Distance
X Axis Title(XS)=Station
BEGIN DESCRIPTION:
UNT 013 IN RACR
END DESCRIPTION:
DSS Export Rating Curves= 0
DSS Export Rating Curve Sorted= 0
DSS Export Volume Flow Curves= 0
DXF OffsetX= 0
DXF OffsetY= 0
DXF ScaleX= 1
DXF ScaleY= 10

--- UNT 013 IN RACR.p01 (plan) ---

Plan Title=Multiple Run
Short Identifier=Multiple
Geom File=g01
Flow File=f01
Subcritical Flow
K Sum by GR= 0
Std Step Tol= 0.01
Critical Tol= 0.01
Num of Std Step Trials= 20
Max Error Tol= 0.3
Flow Tol Ratio= 0.001
Split Flow NTrial= 30
Split Flow Tol= 0.02
Split Flow Ratio= 0.02
Log Output Level= 0
Friction Slope Method= 1
Unsteady Friction Slope Method= 2
Unsteady Bridges Friction Slope Method= 1
Parabolic Critical Depth
Global Vel Dist=  1 , 1 , 1
Global Log Level= 0
CheckData=True
Encroach Param= -1, 0, 0, 0
BEGIN DESCRIPTION:
Multiple Run
END DESCRIPTION:

--- UNT 013 IN RACR.f01 (steady flow) ---

Flow Title=Multiple
Program Version=4.10
Number of Profiles= 7
Profile Names=10-year,25-year,50-year,1pct_min,100-year,1pct_plu,500-year
River Rch & RM=UNT 013 IN RACR,Reach-1         ,25174
     208     290     358     326     441     596     679
River Rch & RM=UNT 013 IN RACR,Reach-1         ,22788
     284     401     501     460     622     841     975
River Rch & RM=UNT 013 IN RACR,Reach-1         ,18372
     421     608     769     715     967    1308    1553
River Rch & RM=UNT 013 IN RACR,Reach-1         ,16986
     433     625     790     734     993    1343    1594
River Rch & RM=UNT 013 IN RACR,Reach-1         ,15421
     603     880    1121    1048    1417    1916    2301
River Rch & RM=UNT 013 IN RACR,Reach-1         ,15050
     603     880    1121    1048    1417    1916    2301
River Rch & RM=UNT 013 IN RACR,Reach-1         ,6065
     743    1092    1397    1311    1773    2398    2903
River Rch & RM=UNT 013 IN RACR,Reach-1         ,5471
     743    1092    1397    1311    1773    2398    2903
River Rch & RM=UNT 013 IN RACR,Reach-1         ,1287
     811    1195    1532    1440    1948    2635    3201
Boundary for River Rch & Prof#=UNT 013 IN RACR,Reach-1         , 1
Up Type= 0
Dn Type= 3
Dn Slope=0.005
Boundary for River Rch & Prof#=UNT 013 IN RACR,Reach-1         , 2
Up Type= 0
Dn Type= 3
Dn Slope=0.005
Boundary for River Rch & Prof#=UNT 013 IN RACR,Reach-1         , 3
Up Type= 0
Dn Type= 3
Dn Slope=0.005
Boundary for River Rch & Prof#=UNT 013 IN RACR,Reach-1         , 4
Up Type= 0
Dn Type= 3
Dn Slope=0.005
Boundary for River Rch & Prof#=UNT 013 IN RACR,Reach-1         , 5
Up Type= 0
Dn Type= 3
Dn Slope=0.005
Boundary for River Rch & Prof#=UNT 013 IN RACR,Reach-1         , 6
Up Type= 0
Dn Type= 3
Dn Slope=0.005
Boundary for River Rch & Prof#=UNT 013 IN RACR,Reach-1         , 7
Up Type= 0
Dn Type= 3
Dn Slope=0.005
DSS Import GetInterval= 0
DSS Import GetPeak= 0
DSS Import FillOption= 0

--- UNT 013 IN RACR.g01 (geometry) ---

Geom Title=Existing Conditions
Program Version=4.10

River Reach=UNT 013 IN RACR ,Reach-1
Reach XY= 30
      2218978.34     13216700.04      2219473.91     13217358.34
      2219520.59     13218115.67       2219905.2     13218723.37
      2220908.09     13219027.23      2220884.78     13219590.07
      2221140.54     13220205.04      2222553.63     13221130.19
      2222329.67     13222283.83      2221811.54     13223427.48
      2222204.74     13224163.09      2223488.17     13224725.69
      2224498.31     13224447.95      2225338.93     13224450.07
      2226115.64     13225397.49      2226110.02     13225635.55
      2226601.72     13226039.44      2226837.71     13225852.85
      2227991.91      13225898.8      2228808.74     13226695.04
      2229334.65     13226653.25      2229695.33     13227157.92
       2229590.6     13227750.35      2229728.74     13228073.53
      2230488.37     13227966.91       2231177.8     13228187.29
      2231607.61     13227927.86      2232206.35     13228030.47
      2232425.69     13228278.22      2232357.72     13229196.86

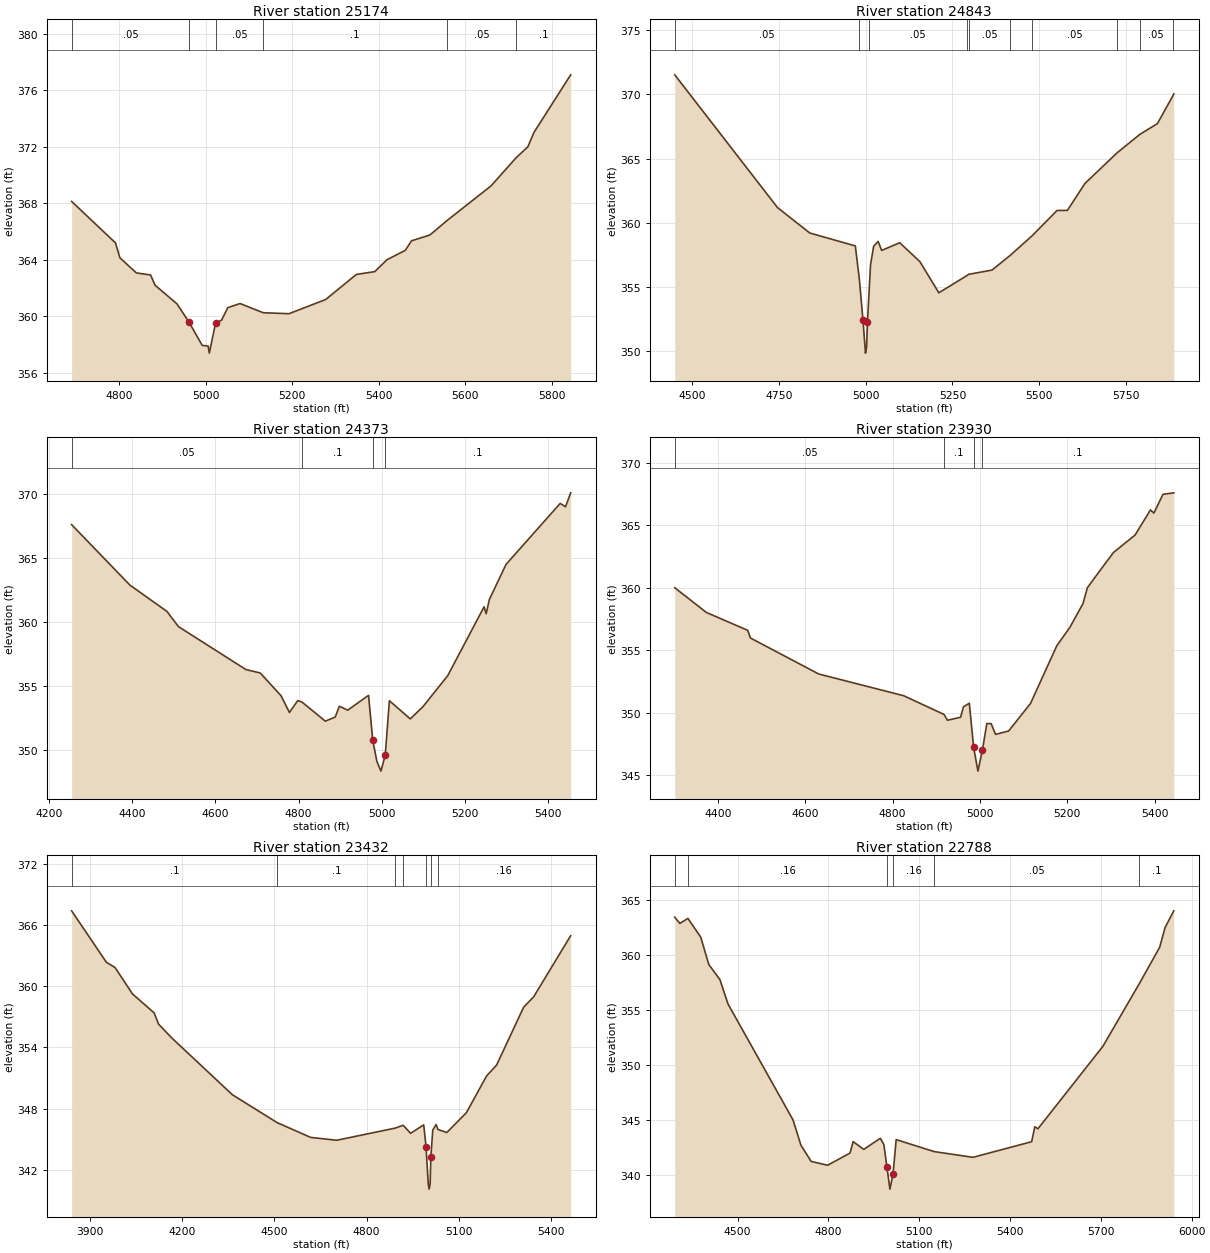
Type RM Length L Ch R = 1 ,25174   ,331,331,331
BEGIN DESCRIPTION:
UNT 013 IN RACR 42.0
END DESCRIPTION:
XS GIS Cut Line= 3
      2218787.74     13216946.85      2219087.72     13216896.85
      2219687.69     13216296.89
#Sta/Elev= 30
  4690.6  368.13    4792  365.19  4802.1  364.14  4840.1  363.07  4873.1  362.92
  4883.2   362.2  4933.9  360.88  4961.8  359.58  4992.2  357.94  5005.9  357.89
  5008.6  357.39    5023  359.51  5037.1  359.73  5051.3  360.61  5079.6   360.9
  5133.1  360.25  5192.7  360.18  5277.6  361.19  5348.3  362.96  5390.7  363.16
    5419     364  5461.4  364.67  5475.6  365.34    5518  365.75  5557.5  366.77
  5659.4  369.23  5717.8  371.24  5744.3  371.99  5758.4  373.01  5843.2  377.09
#Mann= 6 ,-1 , 0
  4690.6     .05       0  4961.8     .05       0    5023     .05       0
  5133.1      .1       0  5557.5     .05       0  5717.8      .1       0
Bank Sta=4961.8,5023
XS Rating Curve= 0 ,0
Exp/Cntr=0.3,0.1

Type RM Length L Ch R = 1 ,24843   ,470,470,470
BEGIN DESCRIPTION:
UNT 013 IN RACR 41.0
END DESCRIPTION:
XS GIS Cut Line= 4
       2218745.6     13217202.93      2219032.86     13217276.05
      2219654.42     13216999.21      2219915.58     13216617.92
#Sta/Elev= 30
  4449.2  371.53  4745.5  361.19  4838.5  359.21  4969.9   358.2  4981.7  355.56
  4991.8  352.46  4999.2  349.85  5002.5  350.35  5004.9  352.27  5008.1  353.89
  5013.7  356.72  5022.7  358.17  5035.6  358.55  5045.9  357.85  5097.9  358.45
    5156  356.98  5210.7  354.55  5292.8  355.91  5296.7  355.99    5364  356.32
  5417.2  357.48  5480.4  359.01  5551.5  360.96  5581.4  360.97  5632.1  363.07
  5724.6  365.45  5790.3  366.89    5841  367.73    5885  369.87  5888.2  370.05
#Mann= 10 ,-1 , 0
  4449.2     .05       0  4981.7     .05       0  5008.1     .05       0
  5292.8      .1       0  5296.7     .05       0  5417.2      .1       0
  5480.4     .05       0  5724.6      .1       0  5790.3     .05       0
    5885      .1       0
Bank Sta=4991.8,5004.9
XS Rating Curve= 0 ,0
Exp/Cntr=0.3,0.1

Type RM Length L Ch R = 1 ,24373   ,443,443,443
BEGIN DESCRIPTION:
UNT 013 IN RACR 40.0
END DESCRIPTION:
XS GIS Cut Line= 3
      2218818.73     13217401.41      2219074.64      13217558.1
      2219972.84      13217511.1
#Sta/Elev= 30
  4254.5  367.63  4394.6   362.9  4483.6  360.84  4511.3  359.65  4673.4  356.29
  4707.9  356.02  4757.9  354.24    4778  352.93    4798  353.86  4808.1  353.75
  4864.3  352.25  4888.1  352.57  4898.1  353.42  4918.1  353.11  4968.2  354.27
  4978.2  350.78  4988.2  349.11    4998  348.34  5008.3  349.58  5018.3  353.85
  5068.4  352.43  5098.4  353.36  5158.5  355.81  5245.9   361.2  5250.9  360.66
  5258.6  361.77  5298.7  364.52  5428.8  369.29  5441.7  369.03    5454  370.12
#Mann= 4 ,-1 , 0
  4254.5     .05       0  4808.1      .1       0  4978.2     .05       0
  5008.3      .1       0
Bank Sta=4978.2,5008.3
XS Rating Curve= 0 ,0
Exp/Cntr=0.3,0.1

Type RM Length L Ch R = 1 ,23930   ,497,497,497
BEGIN DESCRIPTION:
UNT 013 IN RACR 39.0
END DESCRIPTION:
XS GIS Cut Line= 4
      2218933.63      13217688.7      2219126.88     13217960.29
      2219779.78     13217923.72      2219899.94     13217824.46
#Sta/Elev= 30
  4300.9     360  4373.4  358.02  4468.1  356.59  4474.2  355.98  4630.6   353.1
  4825.4  351.36  4917.9  349.86  4925.5   349.4  4955.6  349.64  4962.2  350.47
  4975.6  350.76  4985.6  347.22  4995.4  345.33  5005.6     347  5015.7  349.13
  5025.7  349.13  5035.7  348.27  5065.7  348.54  5115.8  350.74  5175.9  355.35
    5206  356.83    5236  358.73    5246  359.99    5266  360.95  5305.9  362.82
  5355.3  364.21  5390.5  366.22  5398.4  365.97  5419.2  367.47    5444  367.59
#Mann= 4 ,-1 , 0
  4300.9     .05       0  4917.9      .1       0  4985.6     .05       0
  5005.6      .1       0
Bank Sta=4985.6,5005.6
XS Rating Curve= 0 ,0
Exp/Cntr=0.3,0.1

Type RM Length L Ch R = 1 ,23432   ,644,644,644
BEGIN DESCRIPTION:
UNT 013 IN RACR 38.0
END DESCRIPTION:
XS GIS Cut Line= 3
      2218887.75     13219196.82      2219687.72     13218396.85
      2219887.73     13217946.82
#Sta/Elev= 30
  3840.5  367.39  3953.6  362.35  3981.9  361.83  4038.4  359.25  4109.2  357.38
  4123.3  356.29  4165.7  354.95  4363.7  349.36  4509.8  346.62  4618.3  345.18
  4703.1   344.9  4893.4  346.09  4919.3  346.37  4943.5  345.58  4986.2  346.41
  4993.7  344.27    5001  340.61  5003.7  340.11    5007  340.61  5009.4  343.26
  5015.6   345.9  5026.5  346.44  5032.2  345.96  5061.4  345.66    5125   347.6
  5190.7   351.2  5223.5  352.28  5311.1  357.93  5343.9  358.96  5464.3  364.95
#Mann= 7 ,-1 , 0
  3840.5      .1       0  4509.8      .1       0  4893.4     .16       0
  4919.3     .16       0  4993.7     .05       0  5009.4     .16       0
  5032.2     .16       0
Bank Sta=4993.7,5009.4
XS Rating Curve= 0 ,0
Exp/Cntr=0.3,0.1

Type RM Length L Ch R = 1 ,22788   ,724,724,724
BEGIN DESCRIPTION:
UNT 013 IN RACR 37.0
END DESCRIPTION:
XS GIS Cut Line= 4
      2219936.48     13219474.99      2220046.16     13219140.73
      2220176.74     13218388.59      2220046.22      13217871.7
#Sta/Elev= 30
  4292.7  363.44  4309.6  362.88  4336.2  363.33  4378.5  361.63  4405.1  359.15
  4442.2  357.75  4468.7  355.55  4683.4  345.02  4709.3  342.73  4743.1  341.25
  4797.7   340.9  4871.7  342.01  4881.9  343.05    4917  342.34  4971.6  343.35
  4983.4  342.78  4993.5  340.74  5003.4  338.73  5013.8  340.12    5024  343.23
  5149.8  342.14  5277.7  341.62  5471.6  343.04  5481.9   344.4  5492.2  344.21
  5706.9  351.71  5827.7  357.43  5894.4  360.71  5912.2   362.5    5941  364.02
#Mann= 6 ,-1 , 0
  4292.7      .1       0  4336.2     .16       0  4993.5     .05       0
  5013.8     .16       0  5149.8     .05       0  5827.7      .1       0
Bank Sta=4993.5,5013.8
XS Rating Curve= 0 ,0
Exp/Cntr=0.3,0.1

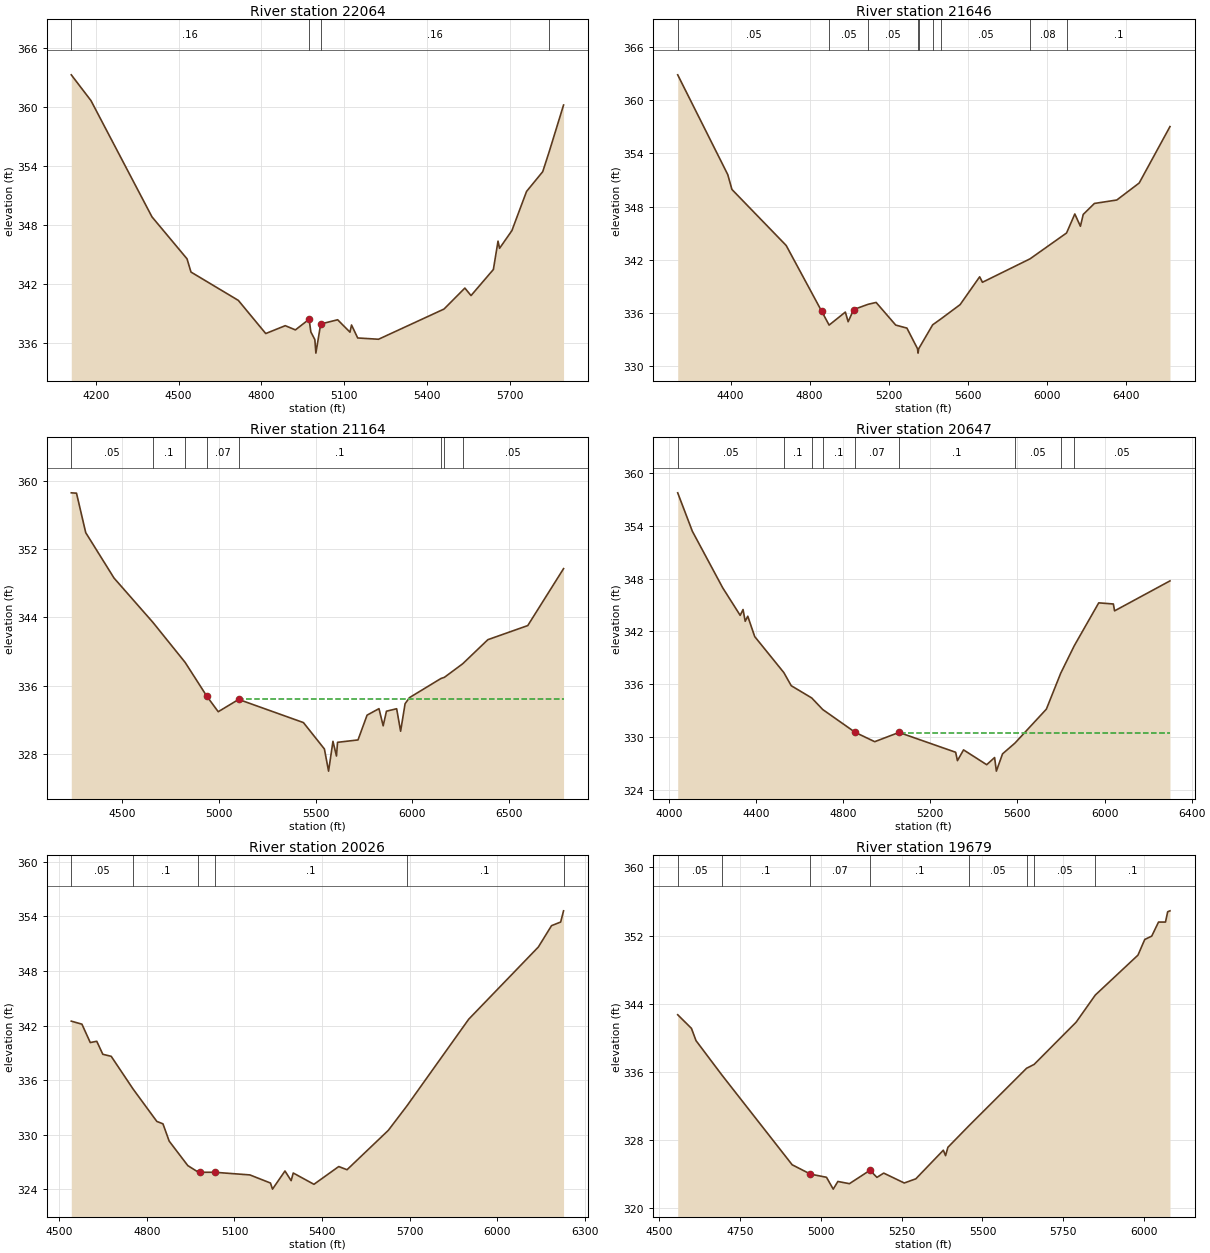
Type RM Length L Ch R = 1 ,22064   ,418,418,418
BEGIN DESCRIPTION:
UNT 013 IN RACR 36.0
END DESCRIPTION:
XS GIS Cut Line= 3
       2220037.7     13219446.87      2220737.72     13218896.85
      2221137.73     13218096.84
#Sta/Elev= 30
  4110.8   363.3  4182.2  360.68  4403.3  348.87  4530.5   344.6  4544.7  343.26
  4716.4  340.38  4815.8  337.01  4886.6  337.81  4923.3  337.38    4973  338.46
  4979.4  337.17  4993.8   336.4  4997.6  335.02    5015  337.98  5076.5  338.41
  5121.2  337.15  5126.8  337.88  5149.2  336.56  5224.7  336.43  5462.2   339.5
  5537.7  341.63  5560.1  340.87  5641.1  343.52  5657.9   346.4  5663.5  345.67
  5708.2  347.47  5761.3  351.45    5820  353.46  5843.7  355.51  5895.5  360.23
#Mann= 4 ,-1 , 0
  4110.8     .16       0    4973     .06       0    5015     .16       0
  5843.7      .1       0
Bank Sta=4973,5015
XS Rating Curve= 0 ,0
Exp/Cntr=0.3,0.1

Type RM Length L Ch R = 1 ,21646   ,482,482,482
BEGIN DESCRIPTION:
UNT 013 IN RACR 35.0
END DESCRIPTION:
XS GIS Cut Line= 3
      2220087.69     13219496.86      2220837.72     13219246.85
      2222037.75     13218046.82
#Sta/Elev= 30
  4133.2  362.89  4386.2  351.61  4407.3  349.93  4681.4   343.6  4860.6  336.17
  4898.4   334.6  4980.4  336.07  4994.5  334.98  5022.8  336.36  5095.5  336.95
  5135.9  337.16  5234.9   334.6  5291.5  334.26  5345.1  331.93  5347.8  331.43
  5351.1  331.93  5421.6  334.63  5465.9  335.34  5560.2  336.91  5659.2  340.06
  5673.3  339.44  5913.8  342.09  6098.2  345.01    6140  347.16  6168.3  345.77
  6182.5  347.11    6239  348.35  6352.2  348.74  6465.3  350.66  6620.9  357.04
#Mann= 9 ,-1 , 0
  4133.2     .05       0  4898.4     .05       0  5095.5     .05       0
  5345.1     .07       0  5351.1     .05       0  5421.6      .1       0
  5465.9     .05       0  5913.8     .08       0  6098.2      .1       0
#XS Ineff= 2 , 0
       0                 5136.27       0  337.12
Permanent Ineff=
       F       T
Bank Sta=4860.6,5022.8
XS Rating Curve= 0 ,0
Exp/Cntr=0.3,0.1

Type RM Length L Ch R = 1 ,21164   ,517,517,517
BEGIN DESCRIPTION:
UNT 013 IN RACR 34.0
END DESCRIPTION:
XS GIS Cut Line= 4
      2220161.04     13219730.95      2220453.57     13219772.74
      2221748.93      13219224.3      2222417.51      13218707.2
#Sta/Elev= 30
  4236.2  358.58  4263.2  358.54    4311  353.92  4457.4  348.61  4658.8  343.42
  4825.8  338.73    4938  334.77  4996.7  332.97  5102.3  334.41  5437.5   331.7
  5546.1  328.61  5567.6  326.02  5590.3  329.51  5608.5  327.79    5614  329.39
  5719.9  329.67  5766.9  332.57  5828.5  333.33  5850.2  331.32  5867.1  333.03
  5919.9  333.32  5940.4  330.69  5963.6  333.91  5986.3  334.62  6149.4  336.86
  6166.7  336.99  6261.7  338.58    6392   341.4  6598.4  343.05  6783.6  349.71
#Mann= 8 ,-1 , 0
  4236.2     .05       0  4658.8      .1       0  4825.8     .05       0
    4938     .07       0  5102.3      .1       0  6149.4     .05       0
  6166.7      .1       0  6261.7     .05       0
#XS Ineff= 2 , 0
       0                 5104.22       0  334.45
Permanent Ineff=
       F       T
Bank Sta=4938,5102.3
XS Rating Curve= 0 ,0
Exp/Cntr=0.3,0.1

Type RM Length L Ch R = 1 ,20647   ,621,621,621
BEGIN DESCRIPTION:
UNT 013 IN RACR 33.0
END DESCRIPTION:
XS GIS Cut Line= 3
      2220287.71     13220496.86      2221087.72     13220046.85
       2222287.7     13219446.87
#Sta/Elev= 30
    4041  357.72  4108.3  353.36  4247.5  346.95  4327.8  343.82  4340.9  344.48
  4350.8  343.15  4362.6  343.72  4394.5  341.41  4528.1  337.33  4562.1  335.84
  4656.2  334.45  4706.6  333.14  4855.6  330.55  4945.2  329.49  5056.7  330.54
  5316.7  328.29    5325  327.34    5353  328.56  5459.2  326.88  5495.5  327.69
  5503.7  326.15  5531.9  328.11  5588.5  329.32  5733.1  333.18  5799.2  337.27
  5861.3  340.38  5973.5  345.24  6040.6  345.11  6046.2  344.33  6300.5  347.73
#Mann= 9 ,-1 , 0
    4041     .05       0  4528.1      .1       0  4656.2     .05       0
  4706.6      .1       0  4855.6     .07       0  5056.7      .1       0
  5588.5     .05       0  5799.2      .1       0  5861.3     .05       0
#XS Ineff= 2 , 0
       0                    5063       0  330.52
Permanent Ineff=
       F       T
Bank Sta=4855.6,5056.7
XS Rating Curve= 0 ,0
Exp/Cntr=0.3,0.1

Type RM Length L Ch R = 1 ,20026   ,347,347,347
BEGIN DESCRIPTION:
UNT 013 IN RACR 32.0
END DESCRIPTION:
XS GIS Cut Line= 4
      2221153.49      13220754.7      2221362.41     13220503.99
      2222109.33     13219783.19      2222396.63     13219642.15
#Sta/Elev= 30
  4541.7  342.48  4578.1  342.15  4606.7  340.13  4628.9  340.27  4649.7  338.84
  4678.3  338.62  4753.4  335.02  4834.5  331.47  4855.4  331.21  4876.7  329.31
  4940.5  326.62  4975.8  325.91    4983  325.89  5032.4  325.89  5152.8   325.6
  5223.3  324.71  5230.2  324.04  5272.9  326.03    5294  324.97  5301.2  325.81
    5372  324.57  5456.9  326.52  5485.2  326.17  5626.4  330.49  5690.2  333.18
  5901.5  342.69  6139.9  350.62  6184.9  352.96  6216.2  353.36  6226.1  354.59
#Mann= 6 ,-1 , 0
  4541.7     .05       0  4753.4      .1       0  4975.8     .07       0
  5032.4      .1       0  5690.2      .1       0  6226.1     .05       0
#XS Ineff= 2 , 0
       0                 5033.39       0  325.88
Permanent Ineff=
       F       T
Bank Sta=4983,5032.4
XS Rating Curve= 0 ,0
Exp/Cntr=0.3,0.1

Type RM Length L Ch R = 1 ,19679   ,461,461,461
BEGIN DESCRIPTION:
UNT 013 IN RACR 31.0
END DESCRIPTION:
XS GIS Cut Line= 3
      2221437.69     13220896.88      2221737.72     13220596.85
      2222487.73     13219796.85
#Sta/Elev= 30
  4558.5   342.7    4601   341.1  4615.1  339.66  4694.7  335.64  4912.1  325.09
  4968.7  323.99  5018.2  323.62    5039  322.23  5053.4  323.13    5089  322.87
  5152.5  324.44    5174  323.61    5195  324.11  5258.5  322.95  5294.2  323.44
  5379.2   326.8    5386  326.16  5393.3  327.14  5459.6  329.72  5636.4  336.42
  5659.7  336.87  5789.5  341.83  5848.6  345.01  5980.5   349.7  6001.5  351.54
    6023  351.93    6044  353.58  6065.5  353.58  6072.3  354.79  6079.4   354.9
#Mann= 8 ,-1 , 0
  4558.5     .05       0  4694.7      .1       0  4968.7     .07       0
  5152.5      .1       0  5459.6     .05       0  5636.4      .1       0
  5659.7     .05       0  5848.6      .1       0
Bank Sta=4968.7,5152.5
XS Rating Curve= 0 ,0
Exp/Cntr=0.3,0.1

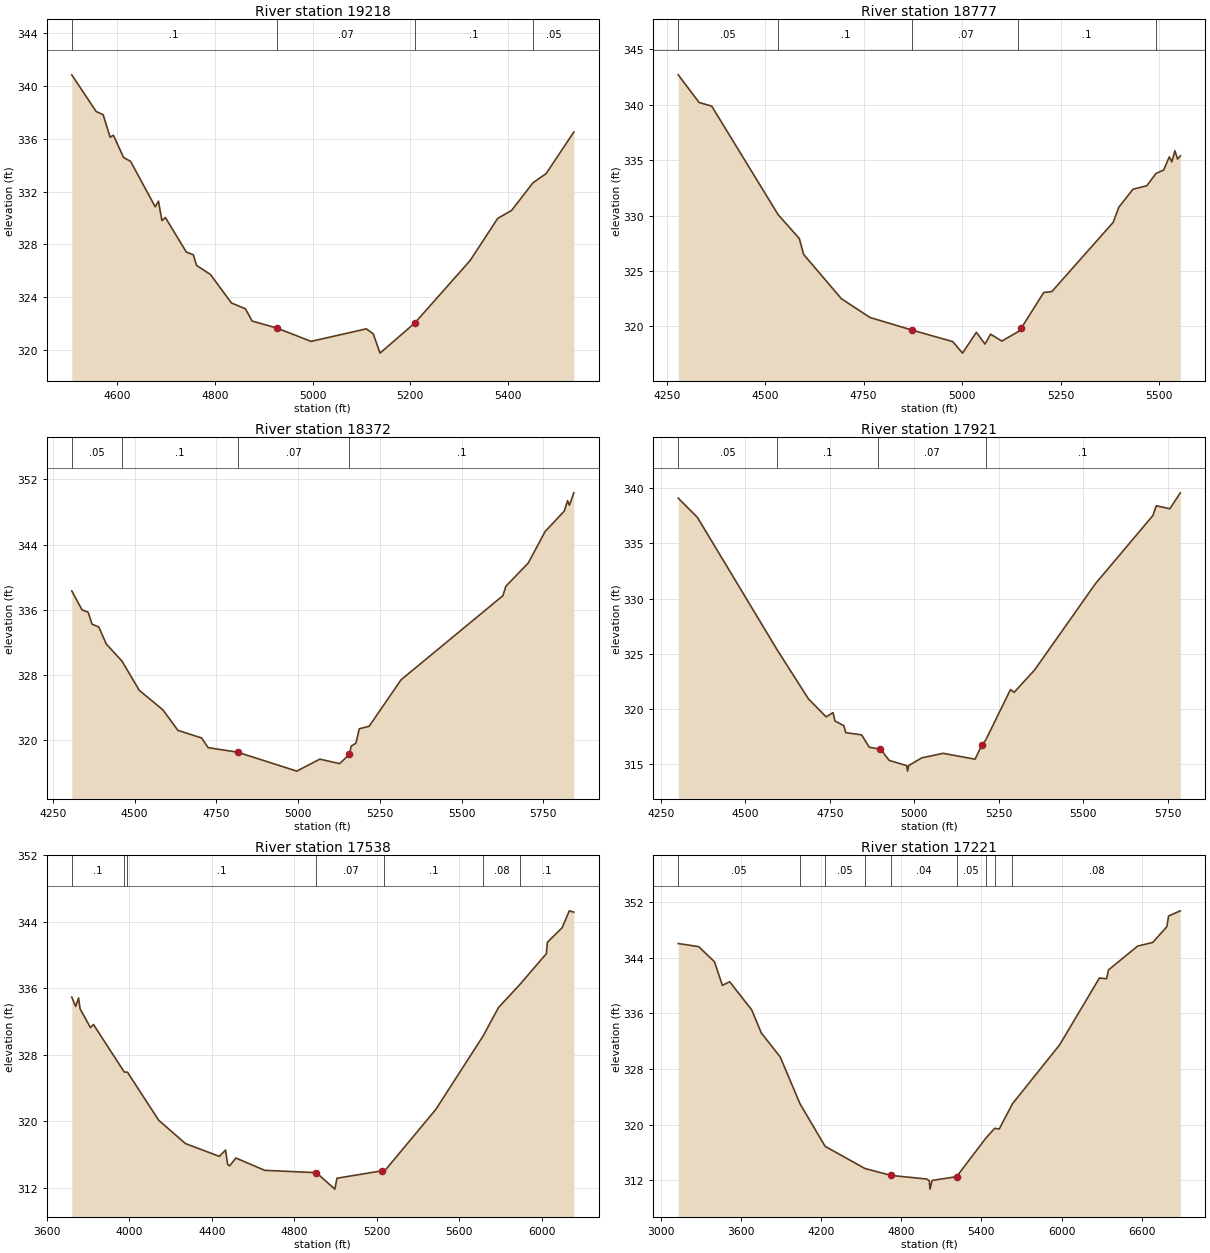
Type RM Length L Ch R = 1 ,19218   ,441,441,441
BEGIN DESCRIPTION:
UNT 013 IN RACR 30.0
END DESCRIPTION:
XS GIS Cut Line= 3
      2221787.72     13221146.85      2222087.72     13220796.85
      2222487.75     13220396.83
#Sta/Elev= 30
  4507.6  340.84  4557.5  338.06  4571.8  337.82  4586.1  336.11  4592.7  336.27
  4613.5  334.58  4627.8  334.29  4678.3  330.84  4684.9  331.27    4692   329.8
  4699.1  330.03  4741.9  327.41  4756.2  327.21  4762.8  326.41  4791.3  325.71
  4834.1  323.56  4862.7  323.12  4876.4  322.19  4926.3  321.67  4996.9  320.65
    5110   321.6  5124.1  321.22    5138  319.76    5209  322.04  5322.1  326.77
  5378.7  329.97    5407  330.57  5450.9  332.67  5477.7  333.36  5534.3  336.51
#Mann= 4 ,-1 , 0
  4507.6      .1       0  4926.3     .07       0    5209      .1       0
  5450.9     .05       0
Bank Sta=4926.3,5209
XS Rating Curve= 0 ,0
Exp/Cntr=0.3,0.1

Type RM Length L Ch R = 1 ,18777   ,405,405,405
BEGIN DESCRIPTION:
UNT 013 IN RACR 29.0
END DESCRIPTION:
XS GIS Cut Line= 3
      2221787.76     13221246.84      2222487.72     13220996.85
      2222837.74     13220596.83
#Sta/Elev= 30
  4279.3  342.71  4332.4  340.21  4364.2  339.89    4533  330.08  4586.7  327.93
  4597.8  326.49  4693.4   322.5  4766.1   320.8  4873.9  319.65  4976.4  318.62
  5001.1  317.58  5036.3  319.46  5058.2   318.4  5072.4  319.29  5100.9  318.67
  5142.6  319.52  5150.2  319.83  5207.2  323.05    5228  323.14  5383.7  329.39
  5397.9  330.75    5434  332.38  5469.1   332.7  5492.5  333.81  5511.8  334.11
  5526.1   335.3  5532.7  334.85  5540.3  335.86    5547   335.1  5554.1  335.39
#Mann= 5 ,-1 , 0
  4279.3     .05       0    4533      .1       0  4873.9     .07       0
  5142.6      .1       0  5492.5     .05       0
Bank Sta=4873.9,5150.2
XS Rating Curve= 0 ,0
Exp/Cntr=0.3,0.1

Type RM Length L Ch R = 1 ,18372   ,451,451,451
BEGIN DESCRIPTION:
UNT 013 IN RACR 28.0
END DESCRIPTION:
XS GIS Cut Line= 4
      2221906.99     13221341.12      2222177.84     13221396.68
      2222907.01     13221327.24      2223384.41     13221105.83
#Sta/Elev= 30
  4307.9  338.33  4339.3  336.01    4358  335.72  4369.9  334.25  4390.3  333.92
  4413.5  331.82  4461.3  329.73  4514.3  326.14  4586.8  323.74  4632.4  321.23
  4704.8   320.3  4724.9  319.11  4815.3  318.55  4995.9  316.23  5066.4   317.7
  5126.7  317.15  5156.9  318.27  5162.3  319.29  5176.9  319.67    5187  321.42
  5217.1  321.73  5314.7  327.43  5626.3  337.75  5635.2   338.9  5703.5  341.74
  5755.3  345.62  5813.7  348.11    5824   349.4  5829.5  348.83  5843.1  350.36
#Mann= 4 ,-1 , 0
  4307.9     .05       0  4461.3      .1       0  4815.3     .07       0
  5156.9      .1       0
Bank Sta=4815.3,5156.9
XS Rating Curve= 0 ,0
Exp/Cntr=0.3,0.1

Type RM Length L Ch R = 1 ,17921   ,383,383,383
BEGIN DESCRIPTION:
UNT 013 IN RACR 27.0
END DESCRIPTION:
XS GIS Cut Line= 4
       2221830.6      13221403.6       2222045.9     13221611.96
      2222719.51     13221827.24      2223198.72     13221855.02
#Sta/Elev= 30
  4301.1  339.09  4357.9  337.35  4594.5  325.35  4686.6  320.94  4739.1  319.31
  4759.7  319.69    4765  318.94  4791.6  318.51  4797.2  317.88  4844.1  317.68
  4866.8  316.56  4893.7  316.42  4898.9  316.44  4925.8  315.37  4977.6   314.9
  4980.3   314.4  4983.6   314.9  5022.4   315.6  5085.5  316.01    5180  315.48
    5201   316.8  5211.5   317.2    5285  321.78  5295.5  321.52  5356.2  323.54
  5536.5  331.35  5706.8  337.52  5716.8   338.4  5756.9  338.13  5787.9  339.57
#Mann= 4 ,-1 , 0
  4301.1     .05       0  4594.5      .1       0  4893.7     .07       0
  5211.5      .1       0
Bank Sta=4898.9,5201
XS Rating Curve= 0 ,0
Exp/Cntr=0.3,0.1

Type RM Length L Ch R = 1 ,17538   ,317,317,317
BEGIN DESCRIPTION:
Mapping XS 5b689292
END DESCRIPTION:
XS GIS Cut Line= 4
      2221129.21     13221750.84      2221698.68     13222077.24
      2222830.62     13222084.18      2223469.54      13221993.9
#Sta/Elev= 30
  3721.5  334.95  3740.4  333.83  3754.4  334.85  3761.9  333.54    3812  331.29
  3826.7  331.66  3976.2  325.94  3991.3  325.93  4143.2  320.14    4273  317.34
  4436.9  315.81  4466.9  316.57  4476.9  314.85  4486.9  314.67  4516.9  315.61
  4656.9  314.13  4906.9  313.85  4996.7  311.87  5006.9  313.18  5226.9  314.08
  5236.9  314.02  5486.9  321.48  5716.9  330.34  5789.7  333.69  5894.3  336.49
  6021.8  340.17  6026.9  341.54    6098  343.28  6133.1  345.32  6155.1  345.16
#Mann= 7 ,-1 , 0
  3721.5      .1       0  3976.2     .05       0  3991.3      .1       0
  4906.9     .07       0  5236.9      .1       0  5716.9     .08       0
  5894.3      .1       0
Bank Sta=4906.9,5226.9
XS Rating Curve= 0 ,0
Exp/Cntr=0.3,0.1

Type RM Length L Ch R = 1 ,17221   ,235,235,235
BEGIN DESCRIPTION:
UNT 013 IN RACR 26.0
END DESCRIPTION:
XS GIS Cut Line= 2
       2220445.6     13222699.01      2224147.08     13222046.22
#Sta/Elev= 30
  3130.6  346.03  3283.5  345.59    3402  343.41  3461.2  340.02  3515.4  340.55
  3681.1  336.49  3752.4  333.19  3894.3  329.73    4042  323.02  4230.2   316.9
  4527.7  313.72  4724.1  312.72    4991   312.2  5010.2  311.95  5015.1  310.75
  5031.6     312  5214.4  312.54  5432.5  318.05  5499.3  319.49  5533.4  319.38
  5632.9  323.02  5986.1  331.49  6283.3  341.07  6337.5  340.98  6351.7  342.24
  6569.4  345.66  6682.9  346.19  6788.3  348.45  6801.4  349.99  6889.2  350.73
#Mann= 9 ,-1 , 0
  3130.6     .05       0    4042      .1       0  4230.2     .05       0
  4527.7      .1       0  4724.1     .04       0  5214.4     .05       0
  5432.5     .08       0  5499.3      .1       0  5632.9     .08       0
Bank Sta=4724.1,5214.4
XS Rating Curve= 0 ,0
Exp/Cntr=0.3,0.1

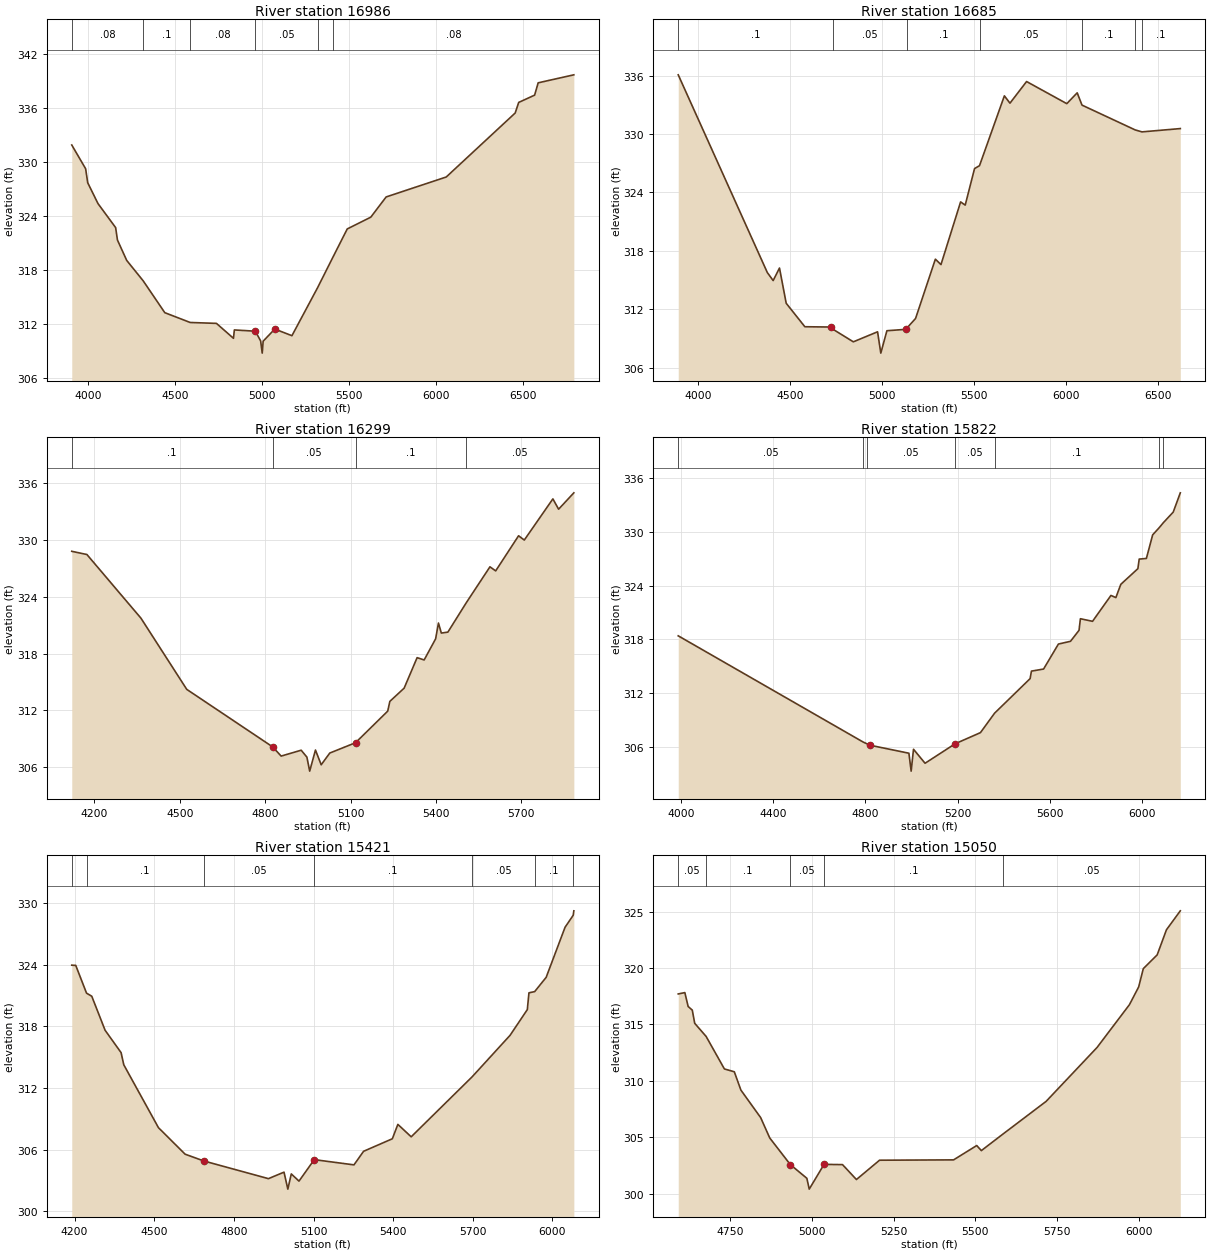
Type RM Length L Ch R = 1 ,16986   ,301,301,301
BEGIN DESCRIPTION:
UNT 013 IN RACR 25.0
END DESCRIPTION:
XS GIS Cut Line= 2
      2221119.28     13222747.61      2223959.57     13222233.72
#Sta/Elev= 30
  3904.2  331.88  3983.9  329.24  3995.9  327.68    4055  325.36  4156.4  322.69
  4166.8  321.31    4220  319.04    4315  316.76  4439.1  313.22  4585.1  312.13
  4735.9  312.03  4833.8  310.37  4838.9   311.3  4959.5  311.16    4990  310.08
  4999.1  308.72  5004.5  310.05  5071.3   311.4    5170  310.66  5317.9  316.02
  5408.3   319.5  5487.9  322.54  5623.3  323.85  5711.5   326.1    6057  328.32
  6453.4  335.44  6473.7  336.62  6565.1  337.43  6585.5   338.8  6790.6  339.69
#Mann= 6 ,-1 , 0
  3904.2     .08       0    4315      .1       0  4585.1     .08       0
  4959.5     .05       0  5317.9      .1       0  5408.3     .08       0
Bank Sta=4959.5,5071.3
XS Rating Curve= 0 ,0
Exp/Cntr=0.3,0.1

Type RM Length L Ch R = 1 ,16685   ,386,386,386
BEGIN DESCRIPTION:
UNT 013 IN RACR 24.0
END DESCRIPTION:
XS GIS Cut Line= 3
      2220978.67     13222981.02      2222850.94     13222673.03
      2223653.01     13222454.28
#Sta/Elev= 30
  3892.2  336.07  4376.3  315.77  4408.1  314.94  4442.5  316.23    4479  312.61
  4580.4   310.2  4722.3  310.17  4732.4  309.95  4843.9  308.65  4975.6  309.68
  4993.2  307.49  5026.3  309.79  5127.6  309.93  5137.8  310.12  5182.1  311.05
  5289.8  317.14  5320.2  316.58  5426.9  323.02  5451.9  322.69  5502.6  326.44
  5529.6  326.74  5664.8  333.91  5695.2  333.16  5785.5  335.38    6004  333.11
  6060.6  334.22  6086.7  332.96    6376  330.41  6412.6  330.21    6621  330.55
#Mann= 7 ,-1 , 0
  3892.2      .1       0  4732.4     .05       0  5137.8      .1       0
  5529.6     .05       0  6086.7      .1       0    6376     .05       0
  6412.6      .1       0
Bank Sta=4722.3,5127.6
XS Rating Curve= 0 ,0
Exp/Cntr=0.3,0.1

Type RM Length L Ch R = 1 ,16299   ,477,477,477
BEGIN DESCRIPTION:
UNT 013 IN RACR 23.0
END DESCRIPTION:
XS GIS Cut Line= 2
      2220995.76     13223206.51      2222750.97     13223039.85
#Sta/Elev= 30
    4121  328.81  4174.2  328.47    4364  321.74  4524.8  314.22  4826.1  308.15
  4856.3  307.17  4926.6  307.79  4946.7  307.06  4956.5  305.58  4976.8  307.81
  4996.9  306.25    5027  307.49  5117.4  308.58  5230.5  311.92    5238  312.95
  5288.2  314.35  5333.7  317.57  5358.5  317.33  5398.7  319.56  5408.7  321.23
  5418.8  320.17  5441.8  320.27  5506.9   323.4  5589.5  327.17  5609.6  326.74
    5690  330.45  5710.1     330  5810.5  334.35  5830.6  333.26  5884.1  334.99
#Mann= 4 ,-1 , 0
    4121      .1       0  4826.1     .05       0  5117.4      .1       0
  5506.9     .05       0
Bank Sta=4826.1,5117.4
XS Rating Curve= 0 ,0
Exp/Cntr=0.3,0.1

Type RM Length L Ch R = 1 ,15822   ,401,401,401
BEGIN DESCRIPTION:
UNT 013 IN RACR 22.0
END DESCRIPTION:
XS GIS Cut Line= 3
      2220808.26     13223628.39      2222131.19      13223576.3
      2222864.13     13223139.66
#Sta/Elev= 30
    3989  318.39  4790.6  306.53  4809.1  306.31  4819.1  306.18  4989.2  305.28
    4999  303.28  5009.2  305.72  5059.3  304.16  5189.4  306.33  5299.5  307.58
  5360.7  309.75  5514.8  313.61  5520.6  314.45  5573.2  314.68  5637.5  317.47
    5690  317.78    5727  319.01  5732.9   320.3  5785.5  320.01  5865.3   322.9
  5886.7  322.66  5908.1  324.14  5982.1  325.89  5987.9  326.96    6019  327.03
  6046.3  329.67    6073  330.42  6092.1  331.01  6135.4  332.21  6166.1  334.36
#Mann= 7 ,-1 , 0
    3989     .05       0  4790.6      .1       0  4809.1     .05       0
  5189.4     .05       0  5360.7      .1       0    6073     .05       0
  6092.1      .1       0
Bank Sta=4819.1,5189.4
XS Rating Curve= 0 ,0
Exp/Cntr=0.3,0.1

Type RM Length L Ch R = 1 ,15421   ,371,371,371
BEGIN DESCRIPTION:
Mapping XS 80ed987b
END DESCRIPTION:
XS GIS Cut Line= 3
      2221872.67     13224681.82      2221940.38     13223978.68
      2222897.97     13223281.31
#Sta/Elev= 30
  4189.5  323.95  4204.5  323.93  4245.1  321.23  4264.8  320.93    4315  317.62
  4375.3  315.44  4385.4  314.26    4516  308.14  4616.4  305.56  4686.8   304.9
  4930.2  303.18  4988.9  303.81  5003.3  302.16  5016.3  303.64  5045.3  302.94
  5102.9  305.03  5252.4  304.52  5288.5  305.84  5396.9  307.06  5417.7  308.46
  5467.9  307.25  5697.5  313.09  5840.4  317.13  5905.3  319.63  5911.4  321.26
    5933  321.38  5976.3  322.77  6047.4  327.64  6078.1  328.81  6080.5  329.24
#Mann= 7 ,-1 , 0
  4189.5     .05       0  4245.1      .1       0  4686.8     .05       0
  5102.9      .1       0  5697.5     .05       0    5933      .1       0
  6078.1     .05       0
Bank Sta=4686.8,5102.9
XS Rating Curve= 0 ,0
Exp/Cntr=0.3,0.1

Type RM Length L Ch R = 1 ,15050   ,424,424,424
BEGIN DESCRIPTION:
UNT 013 IN RACR 21.0
END DESCRIPTION:
XS GIS Cut Line= 3
      2222187.72     13224596.89      2222237.72     13224196.85
       2223037.7     13223396.87
#Sta/Elev= 30
    4592   317.7  4612.2  317.82  4622.3  316.59  4634.9  316.27  4642.4   315.1
  4677.2  313.94  4733.1  311.06  4763.4  310.81  4783.5  309.19    4844  306.75
  4871.7  304.95  4934.7  302.59  4985.1  301.38  4992.4  300.42  5037.6  302.61
  5094.1  302.59  5136.6  301.27  5207.3  302.98  5433.6  303.01  5504.3  304.28
  5518.4  303.83  5584.2  305.29  5716.4  308.19    5872  312.96    5971  316.75
  5999.2  318.32  6013.4  319.94  6055.8  321.16  6084.1  323.38  6126.5  325.06
#Mann= 5 ,-1 , 0
    4592     .05       0  4677.2      .1       0  4934.7     .05       0
  5037.6      .1       0  5584.2     .05       0
Bank Sta=4934.7,5037.6
XS Rating Curve= 0 ,0
Exp/Cntr=0.3,0.1

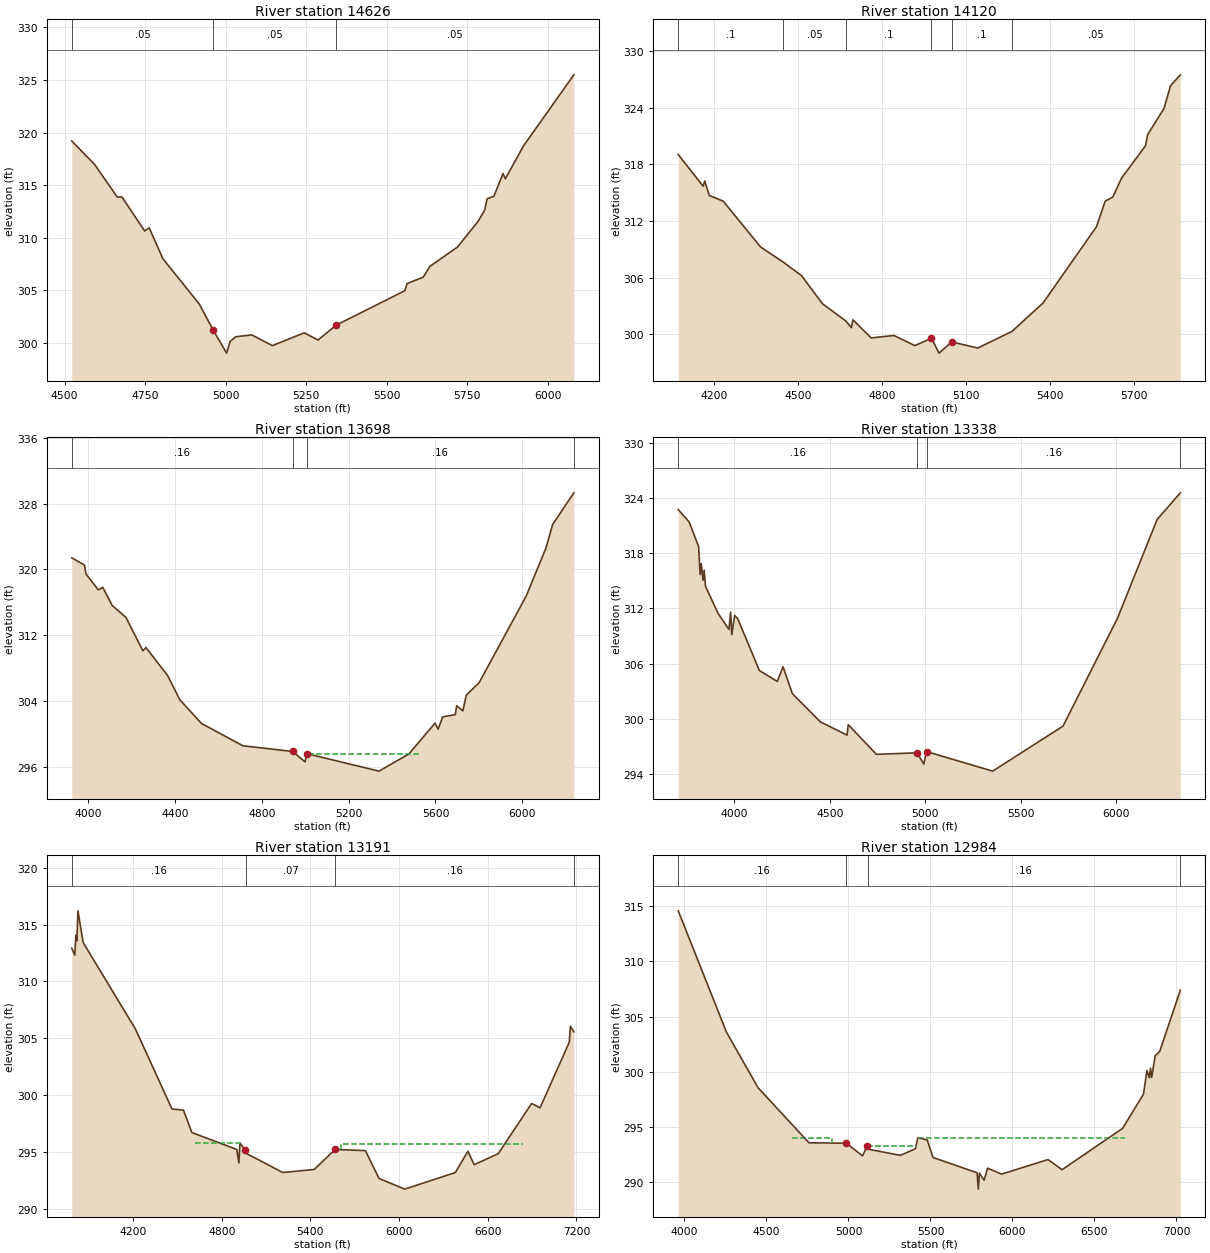
Type RM Length L Ch R = 1 ,14626   ,506,506,506
BEGIN DESCRIPTION:
UNT 013 IN RACR 20.0
END DESCRIPTION:
XS GIS Cut Line= 3
      2222287.75     13224696.82      2222637.72     13224346.85
      2223437.69     13223646.88
#Sta/Elev= 30
  4522.4   319.2  4593.1  316.98  4663.8  313.87  4677.9  313.89  4748.6  310.65
  4762.8  310.94  4805.2  308.01  4918.3   303.7  4960.8  301.25  5002.9  299.04
  5013.8  300.14  5031.1   300.6  5081.4  300.77    5145  299.75  5243.7  300.97
  5286.4  300.29  5343.4  301.71    5556  304.97  5562.6  305.65  5612.9  306.26
  5633.8  307.29  5719.2  309.12  5782.8  311.55  5803.7  312.64  5811.3  313.72
  5832.1  313.94  5860.6  316.11  5867.7  315.61  5924.2  318.74  6080.3  325.49
#Mann= 3 , 0 , 0
  4522.4     .05       0  4960.8     .05       0  5343.4     .05       0
Bank Sta=4960.8,5343.4
XS Rating Curve= 0 ,0
Exp/Cntr=0.3,0.1

Type RM Length L Ch R = 1 ,14120   ,422,422,422
BEGIN DESCRIPTION:
UNT 013 IN RACR 19.0
END DESCRIPTION:
XS GIS Cut Line= 3
      2222287.68     13224896.88      2223087.72     13224446.85
      2223537.74     13223696.82
#Sta/Elev= 30
  4071.9  319.04  4160.9  315.69  4166.6  316.24  4182.5  314.71  4232.6   314.1
  4366.1  309.24  4445.8  307.67  4512.1  306.21  4587.3  303.22  4670.6   301.4
  4689.9   300.7  4695.7  301.53  4760.7  299.61  4841.6  299.87  4916.8   298.8
  4976.1  299.57  5003.2     298  5048.1  299.19  5141.4  298.54  5263.5   300.3
  5374.7  303.32  5565.1  311.39  5596.2   314.1  5623.5  314.54  5654.5  316.53
  5740.1  319.97  5747.8  321.15  5806.2  323.92  5829.5  326.33  5864.5  327.49
#Mann= 6 ,-1 , 0
  4071.9      .1       0  4445.8     .05       0  4670.6      .1       0
  4976.1     .05       0  5048.1      .1       0  5263.5     .05       0
Bank Sta=4976.1,5048.1
XS Rating Curve= 0 ,0
Exp/Cntr=0.3,0.1

Type RM Length L Ch R = 1 ,13698   ,360,360,360
BEGIN DESCRIPTION:
UNT 013 IN RACR 18.0
END DESCRIPTION:
XS GIS Cut Line= 4
      2222579.33     13225390.83      2223169.59     13224887.38
      2223985.56     13224262.38      2223899.02     13223760.42
#Sta/Elev= 30
  3924.6  321.41  3983.1  320.54  3989.7  319.47  4046.8  317.52  4067.7  317.82
  4110.5  315.63  4174.2  314.17  4252.1  310.11  4266.4  310.51  4366.3   307.1
  4422.3  304.17  4522.3  301.28  4713.2  298.57  4941.7  297.88  4999.8  296.61
  5006.1  297.62  5340.3  295.49  5477.6  297.58  5598.1  301.32  5612.6   300.6
  5633.5  302.08  5691.5  302.36  5697.8  303.43  5726.4  302.81  5741.9  304.72
  5801.8  306.26    6018  316.76  6109.3  322.61  6139.7  325.45  6237.6  329.31
#Mann= 4 ,-1 , 0
  3924.6     .16       0  4941.7     .07       0  5006.1     .16       0
  6237.6     .05       0
#XS Ineff= 1 ,-1
 5014.55 5531.47   297.6
Permanent Ineff=
       T
Bank Sta=4941.7,5006.1
XS Rating Curve= 0 ,0
Exp/Cntr=0.3,0.1

Type RM Length L Ch R = 1 ,13338   ,147,147,147
BEGIN DESCRIPTION:
Mapping XS 3c4b4978
END DESCRIPTION:
XS GIS Cut Line= 5
      2222698.52     13225465.86      2223247.72     13225104.39
      2223583.96     13224913.76      2224270.39     13224252.33
      2224046.34     13223663.45
#Sta/Elev= 30
  3707.2  322.76  3764.6   321.4    3814  318.72  3821.8  315.69  3827.8  316.89
  3836.9  315.06  3842.9  316.17  3849.9  314.42  3915.2  311.48  3972.4  309.72
  3981.5  311.59  3987.4  309.14  4002.5  311.24  4017.5  310.93    4132  305.24
  4225.4  304.06  4255.6  305.66  4304.8  302.72  4450.9  299.66  4590.8  298.22
  4596.6  299.36    4744  296.13  4956.7  296.29  4992.3  295.07  5006.4  296.43
  5352.7   294.3  5720.8   299.2  6005.9  310.94  6213.2  321.68  6334.5  324.58
#Mann= 4 ,-1 , 0
  3707.2     .16       0  4956.7     .07       0  5006.4     .16       0
  6334.5     .05       0
#XS Ineff= 1 ,-1
 5018.75 5577.08  296.33
Permanent Ineff=
       T
Bank Sta=4956.7,5006.4
XS Rating Curve= 0 ,0
Exp/Cntr=0.3,0.1

Type RM Length L Ch R = 1 ,13191   ,207,207,207
BEGIN DESCRIPTION:
Mapping XS 86124bad
END DESCRIPTION:
XS GIS Cut Line= 3
      2223037.09     13225575.22      2223974.59     13224653.34
      2225500.66     13223236.65
#Sta/Elev= 30
  3785.4  312.92  3805.9  312.31    3813  314.07    3820  313.58  3827.2  316.21
  3862.5  313.42  4216.1  305.81  4463.5  298.77  4541.4  298.67  4597.9   296.7
    4902  295.21  4916.1  294.03  4923.1  295.77  4958.5  295.18  4965.5  294.87
  5213.4  293.18  5425.5  293.45  5567.2  295.21  5772.4  295.11  5864.2  292.66
  6038.1  291.72  6380.7  293.18  6465.7  295.05  6508.3  293.87    6671  294.84
  6897.2  299.26  6953.9  298.88  7151.7  304.65  7159.1  306.05  7182.5  305.57
#Mann= 4 ,-1 , 0
  3785.4     .16       0  4965.5     .07       0  5567.2     .16       0
  7182.5     .08       0
#XS Ineff= 2 ,-1
 4620.27 4921.61   295.8 5608.33 6836.11  295.72
Permanent Ineff=
       T       T
Bank Sta=4958.5,5567.2
XS Rating Curve= 0 ,0
Exp/Cntr=0.3,0.1

Type RM Length L Ch R = 1 ,12984   ,724,724,724
BEGIN DESCRIPTION:
Mapping XS edfdd14e
END DESCRIPTION:
XS GIS Cut Line= 3
      2223615.21     13225611.68      2224193.34     13224517.93
      2225583.33     13223336.17
#Sta/Elev= 30
  3962.1  314.59  4256.2   303.6  4448.6  298.56  4759.3  293.57  4987.6  293.53
  5086.3  292.38    5114  293.28  5121.3  292.99  5316.6  292.43  5408.9  293.03
  5423.2  294.03  5480.3  293.83  5515.4  292.24  5784.5  290.85  5791.9  289.37
  5798.7  290.82  5827.3  290.18  5848.2  291.27  5933.8  290.73  6217.2  292.05
  6302.9  291.13  6671.9  294.88  6799.3  297.98  6820.1  300.12  6834.4  299.48
  6842.1  300.33  6848.7  299.48  6870.7  301.46  6898.2  301.85  7023.7   307.4
#Mann= 4 ,-1 , 0
  3962.1     .16       0  4987.6     .07       0  5121.3     .16       0
  7023.7     .05       0
#XS Ineff= 3 ,-1
 4657.21 4897.98  294.02  5113.4 5415.95  293.28 5422.28  6686.3  294.03
Permanent Ineff=
       T       T       T
Bank Sta=4987.6,5114
XS Rating Curve= 0 ,0
Exp/Cntr=0.3,0.1