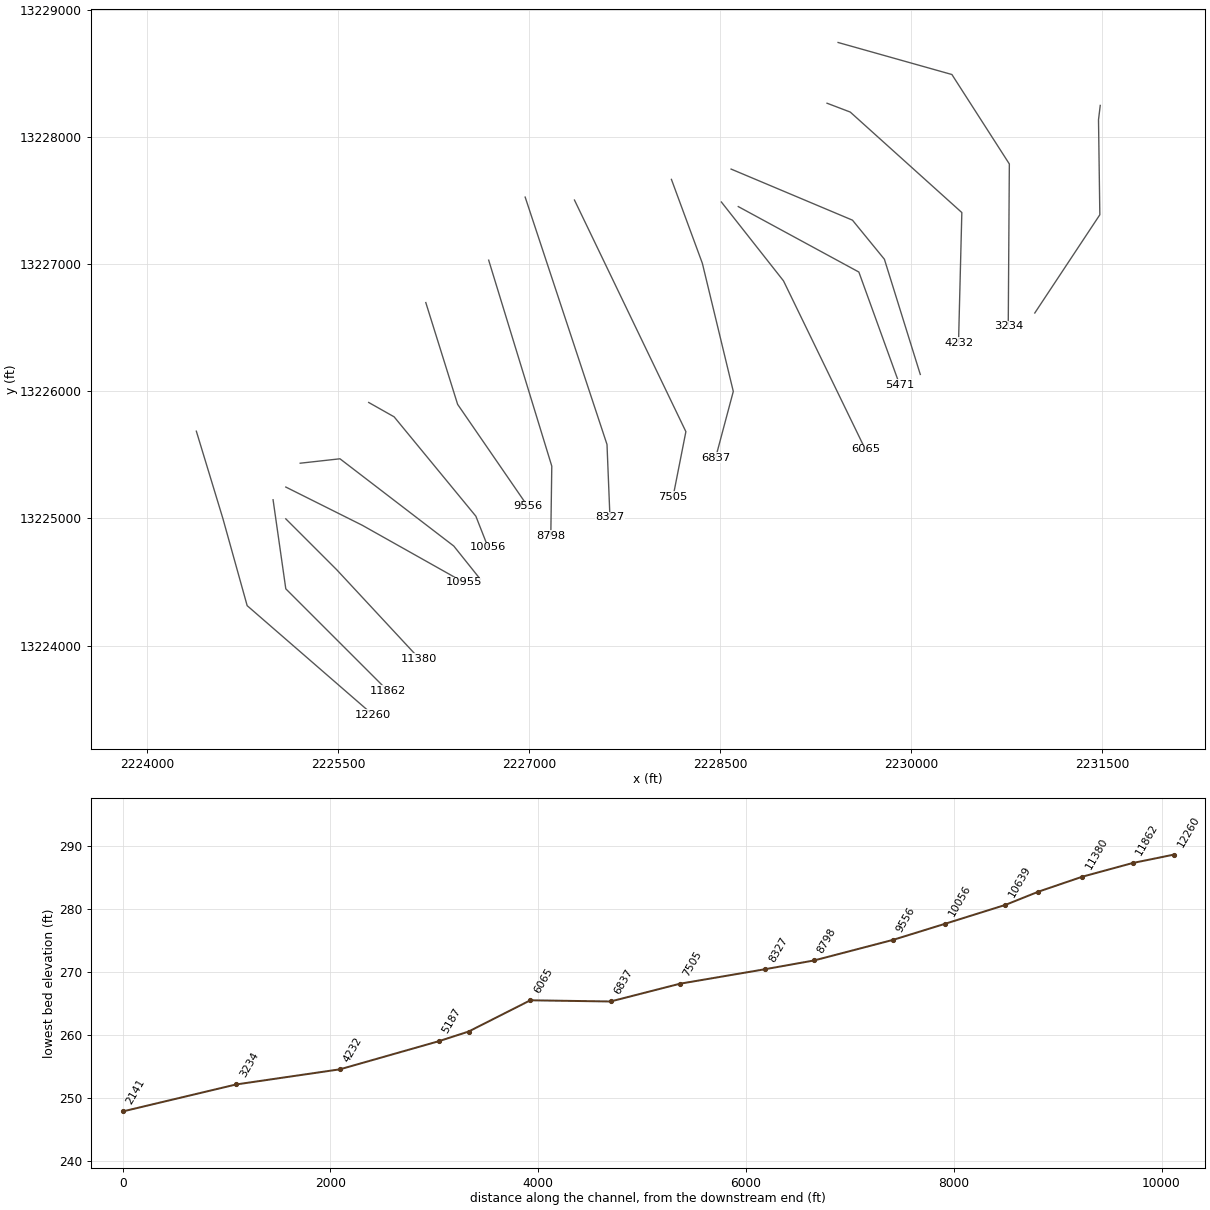
HEC-RAS study UNT 013 IN RACR.prj: UNT 013 IN RACR Base Level Engineering

--- UNT 013 IN RACR.g01 (geometry) --- (continued)

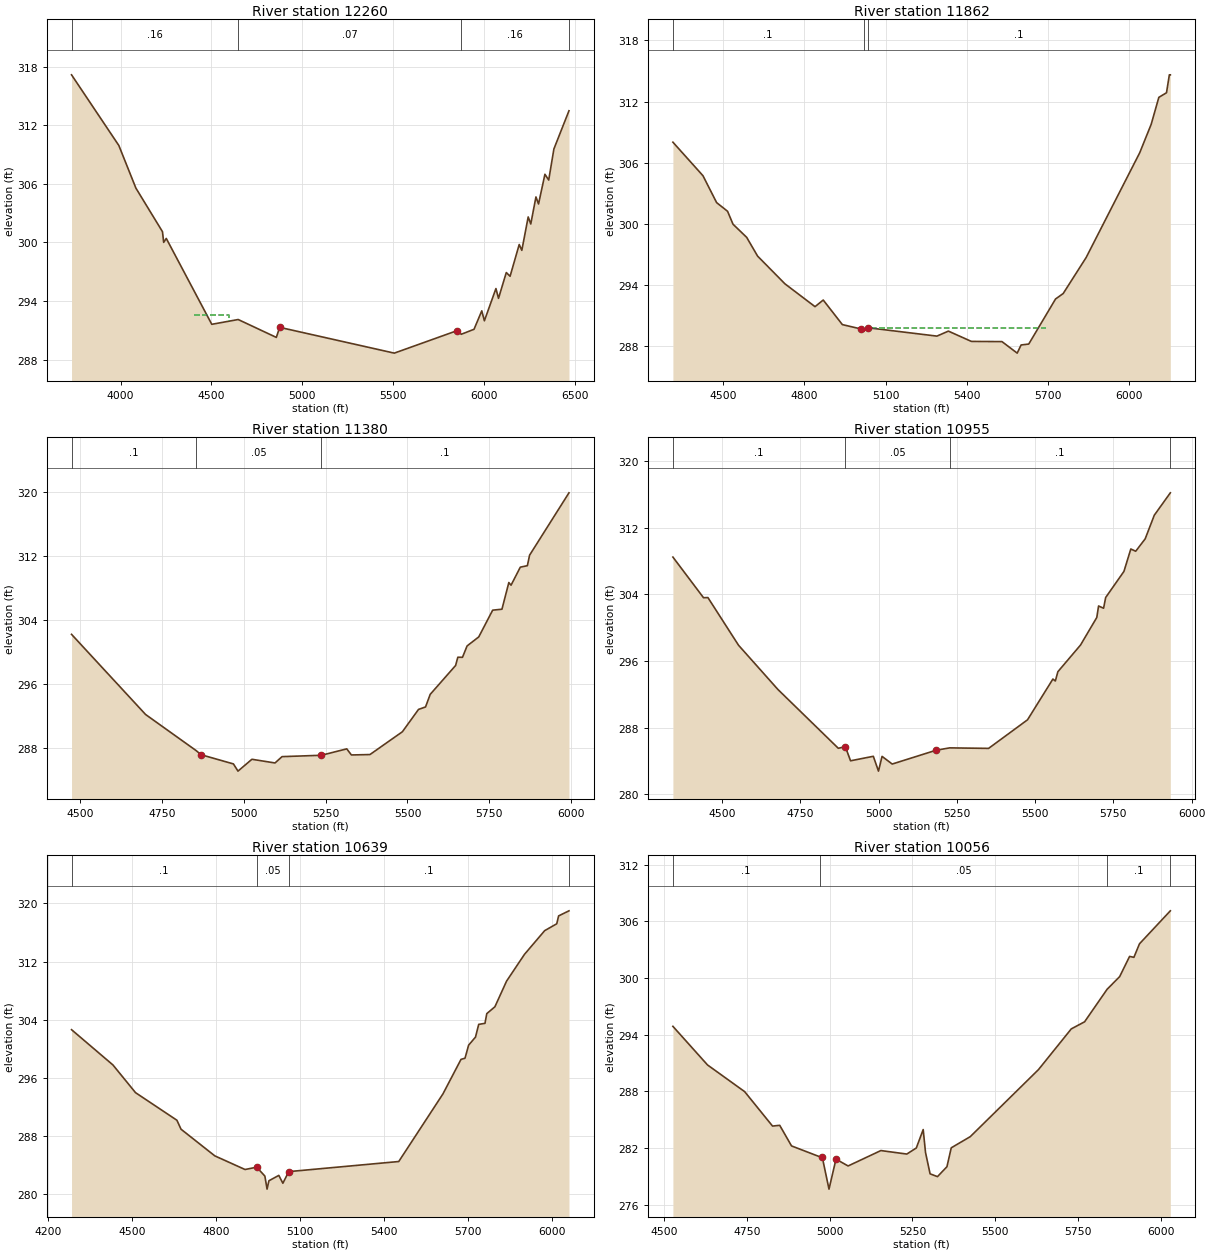
Type RM Length L Ch R = 1 ,12260   ,398,398,398
BEGIN DESCRIPTION:
UNT 013 IN RACR 15.0
END DESCRIPTION:
XS GIS Cut Line= 4
      2224384.88     13225685.94       2224593.2     13225000.23
      2224784.17     13224314.46      2225773.25     13223455.53
#Sta/Elev= 30
  3730.3  317.15  3990.6  309.92  4084.7  305.55    4231  301.09  4237.6     300
  4251.9   300.4  4502.4  291.61  4647.7   292.1  4857.8  290.27  4876.1   291.3
  5507.2  288.66    5854  290.97  5875.9  290.59  5946.1   291.1  5988.8  292.99
  6003.1  291.97  6066.7  295.27  6080.9  294.27  6123.7  296.91  6144.6  296.53
  6194.9  299.78  6209.2  299.18  6244.3   302.6  6258.5  301.88    6287  304.65
  6301.3  303.93  6336.4  306.97  6357.3  306.38  6385.8  309.56  6468.8  313.47
#Mann= 4 ,-1 , 0
  3730.3     .16       0  4647.7     .07       0  5875.9     .16       0
  6468.8      .1       0
#XS Ineff= 1 ,-1
 4404.79 4594.51  292.58
Permanent Ineff=
       T
Bank Sta=4876.1,5854
XS Rating Curve= 0 ,0
Exp/Cntr=0.3,0.1

Type RM Length L Ch R = 1 ,11862   ,482,482,482
BEGIN DESCRIPTION:
UNT 013 IN RACR 14.0
END DESCRIPTION:
XS GIS Cut Line= 3
      2224987.72     13225146.84      2225087.72     13224446.85
      2225887.75     13223646.83
#Sta/Elev= 30
  4313.8  308.02  4424.9  304.73  4475.4  302.09  4515.8  301.24    4536  299.97
  4586.5  298.68  4626.9  296.84  4727.9  294.12  4839.1  291.88  4869.4  292.53
  4940.1  290.12  5010.8  289.68  5018.4  289.48    5035  289.81  5289.6  288.99
    5332  289.48  5416.9  288.47    5530  288.45  5586.3  287.32  5600.7  288.12
    5629  288.21    5728  292.63  5756.3  293.17  5841.1   296.7  6039.1  306.98
  6081.6  309.78  6109.8  312.42  6138.1  312.87  6148.7  314.63  6152.3  314.63
#Mann= 3 ,-1 , 0
  4313.8      .1       0  5018.4     .05       0    5035      .1       0
#XS Ineff= 1 ,-1
 5046.88 5692.71   289.8
Permanent Ineff=
       T
Bank Sta=5010.8,5035
XS Rating Curve= 0 ,0
Exp/Cntr=0.3,0.1

Type RM Length L Ch R = 1 ,11380   ,425,425,425
BEGIN DESCRIPTION:
UNT 013 IN RACR 13.0
END DESCRIPTION:
XS GIS Cut Line= 3
      2225087.72     13224996.86      2225487.72     13224596.85
      2226137.69     13223896.88
#Sta/Elev= 30
    4473  302.25  4699.3  292.24  4854.8   287.7    4869  287.21    4968  286.06
  4981.9  285.16  5024.5  286.64  5095.1  286.18  5116.6  286.97  5236.8  287.14
  5314.5  287.94  5328.7  287.18  5385.4  287.23  5484.6  290.08  5533.9  292.87
  5555.4  293.18  5569.6  294.75  5647.3  298.36  5654.1  299.39  5668.3  299.38
  5682.4   300.8  5718.1  301.93  5760.6  305.27    5789  305.39    5810  308.72
  5816.8  308.39  5845.1  310.64  5866.7  310.83  5873.5  312.14  5993.9  319.93
#Mann= 3 ,-1 , 0
    4473      .1       0  4854.8     .05       0  5236.8      .1       0
Bank Sta=4869,5236.8
XS Rating Curve= 0 ,0
Exp/Cntr=0.3,0.1

Type RM Length L Ch R = 1 ,10955   ,316,316,316
BEGIN DESCRIPTION:
UNT 013 IN RACR 12.0
END DESCRIPTION:
XS GIS Cut Line= 3
      2225087.74     13225246.85      2225687.72     13224946.85
      2226487.74     13224496.84
#Sta/Elev= 30
  4343.2  308.46    4441  303.58    4455   303.6  4552.8  297.88  4678.6  292.57
  4871.5  285.51  4893.8  285.71  4910.6  284.01  4983.3  284.55  4999.8  282.77
  5011.2  284.54  5043.6  283.62  5183.9  285.28  5227.2  285.56  5351.5   285.5
  5475.8  288.93  5556.8  293.82  5564.7  293.59  5572.7   294.7    5645   297.9
    5697  301.21  5702.7  302.59  5718.7  302.32  5725.4  303.61  5783.7  306.74
  5805.7  309.43  5821.3  309.16  5851.6  310.65  5880.6  313.48  5931.9  316.17
#Mann= 4 ,-1 , 0
  4343.2      .1       0  4893.8     .05       0  5227.2      .1       0
  5931.9     .05       0
Bank Sta=4893.8,5183.9
XS Rating Curve= 0 ,0
Exp/Cntr=0.3,0.1

Type RM Length L Ch R = 1 ,10639   ,583,583,583
BEGIN DESCRIPTION:
UNT 013 IN RACR 11.0
END DESCRIPTION:
XS GIS Cut Line= 4
      2225200.84     13225434.25      2225513.34     13225468.98
      2226407.44     13224783.21      2226615.76     13224522.81
#Sta/Elev= 30
  4285.3  302.63  4433.1  297.77  4513.6  293.96  4661.3  290.16  4675.9  288.93
  4796.4  285.26  4904.3  283.38  4945.9   283.7    4975  282.48  4982.9  280.68
  4989.5  281.83  5024.8  282.57  5039.3  281.49  5060.2  283.09  5452.7  284.48
  5610.4  293.79  5674.8  298.54  5689.1   298.7  5701.9  300.49  5726.5  301.61
    5738  303.36  5760.3   303.5  5766.8  304.84  5795.7  305.78  5837.3  309.31
  5901.3     313  5973.3  316.26  6016.4  317.21    6023  318.29    6060  318.99
#Mann= 4 ,-1 , 0
  4285.3      .1       0  4945.9     .05       0  5060.2      .1       0
    6060     .05       0
Bank Sta=4945.9,5060.2
XS Rating Curve= 0 ,0
Exp/Cntr=0.3,0.1

Type RM Length L Ch R = 1 ,10056   ,500,500,500
BEGIN DESCRIPTION:
UNT 013 IN RACR 10.0
END DESCRIPTION:
XS GIS Cut Line= 4
      2225739.07     13225911.66      2225938.69     13225798.84
      2226581.05     13225017.59      2226676.55     13224774.49
#Sta/Elev= 30
  4526.9  294.89  4631.3  290.81  4743.6  287.98  4827.7  284.34  4849.4  284.42
  4885.1  282.24  4969.8   281.1  4977.7  281.08  4998.2  277.67  5019.3  280.84
  5055.9  280.12  5154.9  281.75  5233.1  281.38  5261.8  282.02  5282.6  283.97
  5289.6  281.55  5303.4  279.29  5325.7  278.99  5354.3  280.04  5367.3  282.04
  5424.7  283.22  5630.6  290.31  5729.7  294.62  5769.9  295.37  5838.1  298.82
  5875.8  300.15  5905.8  302.29  5918.8  302.19  5935.6  303.62  6028.8  307.11
#Mann= 4 ,-1 , 0
  4526.9      .1       0  4969.8     .05       0  5838.1      .1       0
  6028.8     .05       0
Bank Sta=4977.7,5019.3
XS Rating Curve= 0 ,0
Exp/Cntr=0.3,0.1

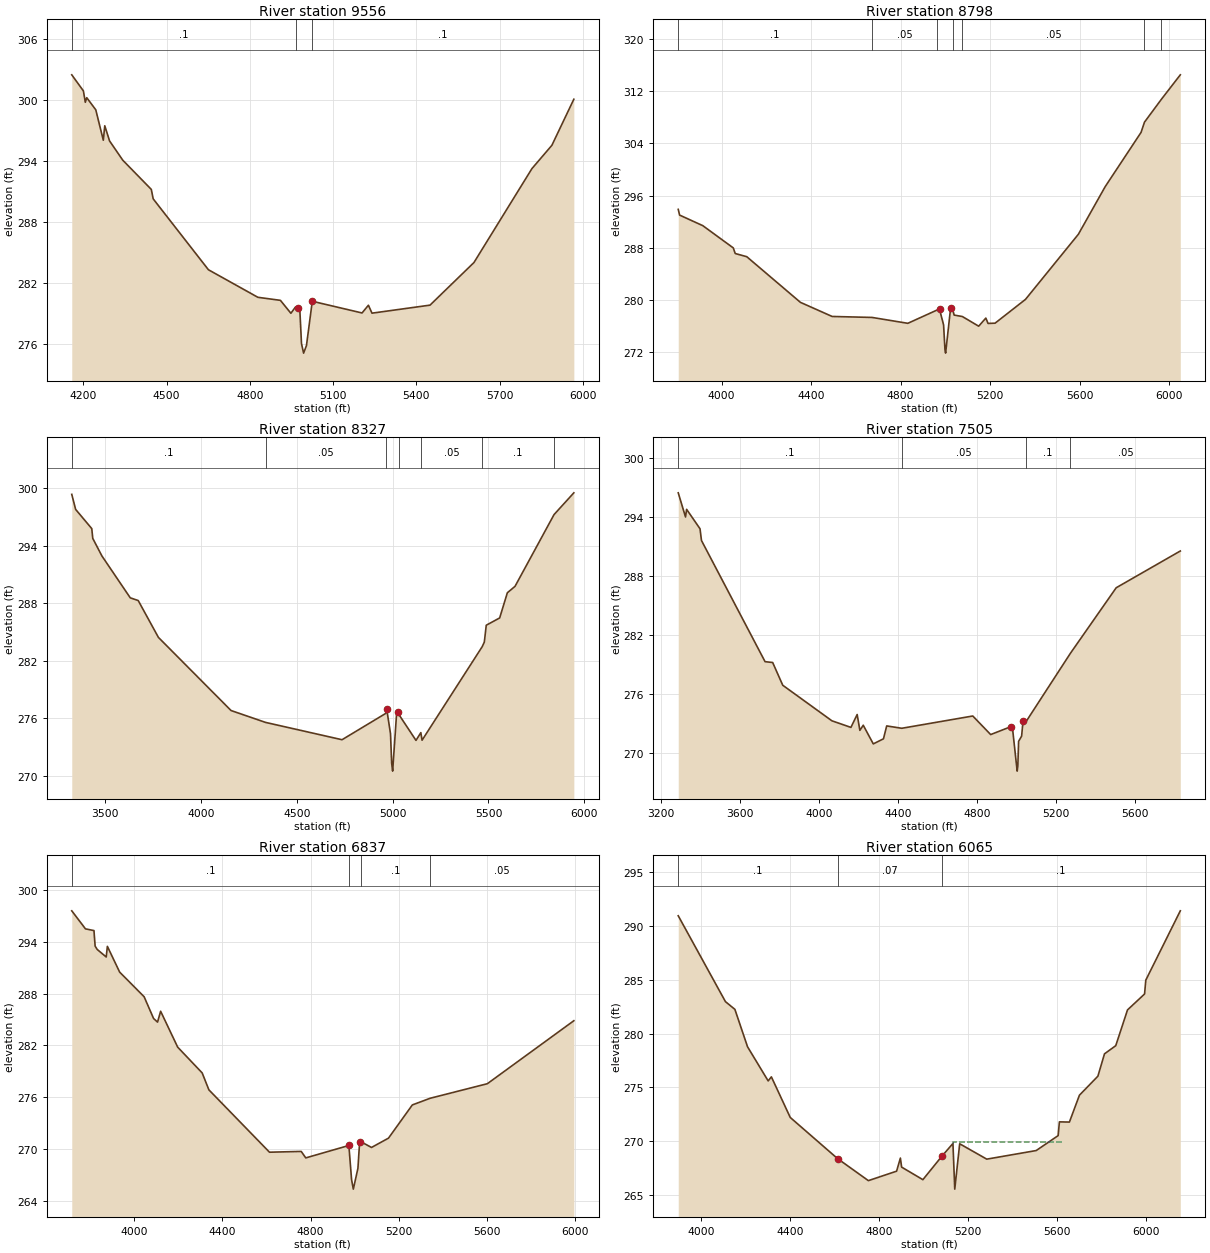
Type RM Length L Ch R = 1 ,9556    ,758,758,758
BEGIN DESCRIPTION:
UNT 013 IN RACR 9.0
END DESCRIPTION:
XS GIS Cut Line= 3
      2226187.71     13226696.89      2226437.72     13225896.85
      2226987.72     13225096.86
#Sta/Elev= 30
  4158.2  302.49  4200.1  300.91    4207  299.79  4212.2  300.24  4244.7  299.05
  4271.9  296.06  4277.1  297.48  4294.4  295.99  4342.1  294.09  4444.8  291.22
  4451.6  290.29  4650.6  283.32  4828.8  280.61    4910  280.31  4947.7  279.04
    4965  279.68  4974.9  279.52  4980.1  279.27  4985.9  276.06  4993.5  275.12
  5003.8  275.86  5024.8  280.22  5204.1  279.07    5227  279.83  5239.9  279.05
    5449  279.84  5607.3  284.03  5816.3  293.27  5888.1  295.56  5967.2  300.09
#Mann= 3 ,-1 , 0
  4158.2      .1       0    4965     .05       0  5024.8      .1       0
Bank Sta=4974.9,5024.8
XS Rating Curve= 0 ,0
Exp/Cntr=0.3,0.1

Type RM Length L Ch R = 1 ,8798    ,471,471,471
BEGIN DESCRIPTION:
UNT 013 IN RACR 7.0
END DESCRIPTION:
XS GIS Cut Line= 3
       2226681.7     13227030.26       2227177.5     13225411.16
      2227169.76     13224861.52
#Sta/Elev= 30
  3806.6   293.9  3812.7  293.02  3916.3   291.4  4052.5  287.99  4061.2  287.13
  4112.8  286.64  4352.6  279.64  4494.2  277.48  4672.7  277.33  4832.3  276.43
  4960.6  278.43  4973.8  278.59    4992   276.2  4998.3  272.36  5001.1  271.86
  5023.3  278.74  5032.6  278.55  5039.3  277.69  5075.9  277.47  5148.8  275.99
  5180.8  277.23  5190.7  276.41    5222  276.45    5358   280.1  5594.2  290.08
  5714.2  297.39  5874.3   305.7  5889.6  307.27  5965.1  310.77  6049.6  314.52
#Mann= 7 ,-1 , 0
  3806.6      .1       0  4672.7     .05       0  4960.6     .05       0
  5032.6      .1       0  5075.9     .05       0  5889.6      .1       0
  5965.1     .05       0
Bank Sta=4973.8,5023.3
XS Rating Curve= 0 ,0
Exp/Cntr=0.3,0.1

Type RM Length L Ch R = 1 ,8327    ,822,822,822
BEGIN DESCRIPTION:
UNT 013 IN RACR 6.0
END DESCRIPTION:
XS GIS Cut Line= 3
      2226968.34     13227526.07      2227611.33      13225581.6
       2227634.5      13225010.1
#Sta/Elev= 30
  3325.5  299.38  3345.7  297.81  3429.9   295.8  3435.1  294.78  3482.7  292.95
  3630.8  288.57  3672.2  288.29  3777.6  284.44  4156.7   276.8  4336.6  275.56
  4735.8  273.75  4963.2  276.49  4968.5  277.01  4988.8  274.38  4994.9  271.28
  4999.9  270.47  5020.4  276.43  5026.6  276.61  5031.9   276.4  5121.8  273.68
  5147.1  274.49  5153.5   273.7  5467.3  283.47  5478.4  283.95  5488.4  285.71
  5558.4  286.47  5598.5   289.1  5638.5  289.77  5842.3  297.27  5945.5  299.54
#Mann= 7 ,-1 , 0
  3325.5      .1       0  4336.6     .05       0  4963.2     .07       0
  5031.9      .1       0  5147.1     .05       0  5467.3      .1       0
  5842.3     .05       0
Bank Sta=4968.5,5026.6
XS Rating Curve= 0 ,0
Exp/Cntr=0.3,0.1

Type RM Length L Ch R = 1 ,7505    ,668,668,668
BEGIN DESCRIPTION:
UNT 013 IN RACR 5.0
END DESCRIPTION:
XS GIS Cut Line= 3
      2227355.66     13227502.88      2228231.09     13225682.31
      2228130.46     13225171.44
#Sta/Elev= 30
  3286.8  296.48  3323.7  294.02  3329.2   294.8  3397.1  292.82  3404.4  291.63
  3726.2   279.3  3764.8  279.21  3815.7   276.9  4064.6  273.28  4160.7  272.61
  4192.3  273.92    4206  272.31  4223.1  272.83  4273.9  270.93  4325.4  271.45
  4341.8  272.76    4418  272.52  4777.4  273.77  4867.9  271.88  4969.5  272.68
  4980.1  272.22    5002  268.16  5005.3  268.66  5009.3  271.19  5024.5  271.72
  5031.9  273.29  5046.7  273.19  5271.4  280.15  5503.2  286.82  5827.6  290.56
#Mann= 4 ,-1 , 0
  3286.8      .1       0    4418     .05       0  5046.7      .1       0
  5271.4     .05       0
Bank Sta=4969.5,5031.9
XS Rating Curve= 0 ,0
Exp/Cntr=0.3,0.1

Type RM Length L Ch R = 1 ,6837    ,772,772,772
BEGIN DESCRIPTION:
Mapping XS 6588e586
END DESCRIPTION:
XS GIS Cut Line= 4
      2228117.49      13227665.2      2228360.56     13227005.43
      2228603.62     13225998.49      2228464.73     13225477.67
#Sta/Elev= 30
  3716.2   297.6  3778.4  295.51  3816.9  295.31  3822.2  293.51  3831.7  293.12
  3872.5  292.25  3877.8  293.48  3933.4   290.5  4044.5  287.64  4087.4  285.12
  4105.4   284.7  4119.4  285.96  4196.7   281.8  4307.9  278.81  4338.3  276.85
  4613.3  269.62  4757.3  269.71  4777.9  268.96  4973.4   270.4  4985.7  266.44
  4993.7  265.34  5014.5  267.75  5022.4  270.85  5027.6  270.84  5076.2  270.17
  5153.2  271.25  5261.4   275.1    5342  275.87  5601.8  277.56  5994.2  284.86
#Mann= 4 ,-1 , 0
  3716.2      .1       0  4973.4     .07       0  5027.6      .1       0
    5342     .05       0
Bank Sta=4973.4,5022.4
XS Rating Curve= 0 ,0
Exp/Cntr=0.3,0.1

Type RM Length L Ch R = 1 ,6065    ,594,594,594
BEGIN DESCRIPTION:
Mapping XS e353ea75
END DESCRIPTION:
XS GIS Cut Line= 3
      2228509.95     13227487.38      2228998.03     13226867.59
      2229641.01      13225542.9
#Sta/Elev= 30
  3895.3  290.97  4107.9  282.98  4150.5  282.26  4207.4  278.78  4300.4   275.6
  4314.8  275.98  4399.8   272.2    4613  268.37  4751.7  266.32  4878.8   267.2
  4895.9  268.42  4901.4  267.58  4997.2  266.41  5081.9  268.57  5132.6  269.78
  5140.8  265.53    5163  269.75    5285  268.32  5507.6  269.12  5606.5  270.51
  5612.1  271.79  5657.2  271.77  5702.3  274.27  5785.5  276.04  5815.2  278.12
  5865.9  278.88  5918.9  282.21  5995.7  283.69  6001.3  284.98  6156.7  291.43
#Mann= 3 , 0 , 0
  3895.3      .1       0    4613     .07       0  5081.9      .1       0
#XS Ineff= 1 ,-1
 5131.25 5622.92  269.89
Permanent Ineff=
       T
Bank Sta=4613,5081.9
XS Rating Curve= 0 ,0
Exp/Cntr=0.3,0.1

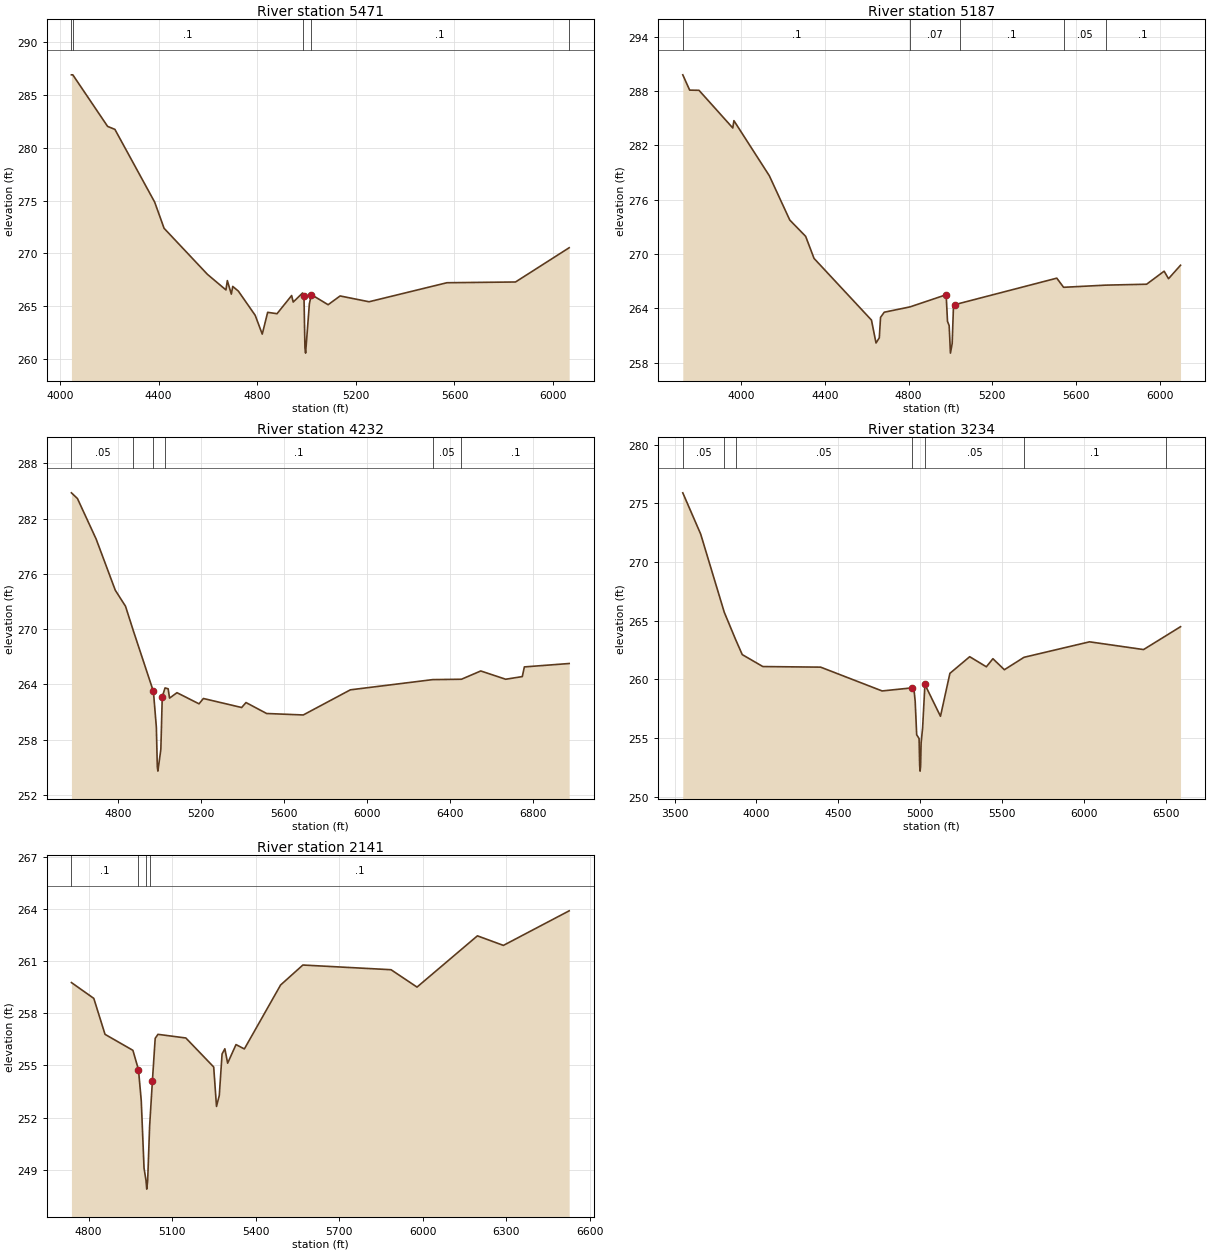
Type RM Length L Ch R = 1 ,5471    ,284,284,284
BEGIN DESCRIPTION:
UNT 013 IN RACR 4.0
END DESCRIPTION:
XS GIS Cut Line= 3
      2228642.79     13227451.38      2229590.14     13226936.92
      2229910.13     13226052.24
#Sta/Elev= 30
  4046.5   286.9  4052.1   286.9  4193.3  282.02  4222.8  281.74  4384.3  274.85
  4422.3  272.38  4598.3  268.02  4673.2  266.55  4678.9  267.43  4695.1  266.15
  4700.8  266.88  4723.5  266.44  4791.8  264.15  4820.5  262.37  4842.4  264.43
  4880.4   264.3  4939.7  266.02    4946   265.4    4984  266.26  4989.7     266
  4993.6  261.07  4996.3  260.57  5011.5  265.21  5019.4  266.11  5087.6  265.15
  5136.3  265.98  5253.6  265.43  5569.5  267.23  5847.7   267.3  6065.3  270.54
#Mann= 5 ,-1 , 0
  4046.5     .05       0  4052.1      .1       0    4984     .07       0
  5019.4      .1       0  6065.3      .1       0
Bank Sta=4989.7,5019.4
XS Rating Curve= 0 ,0
Exp/Cntr=0.3,0.1

Type RM Length L Ch R = 1 ,5187    ,955,955,955
BEGIN DESCRIPTION:
UNT 013 IN RACR 3.0
END DESCRIPTION:
XS GIS Cut Line= 4
      2228586.33     13227746.25      2229539.95     13227344.73
      2229790.91      13227037.3      2230072.77     13226132.02
#Sta/Elev= 30
  3720.8  289.79  3753.7   288.1  3798.3  288.08  3959.8  283.92  3965.2  284.73
  4134.6  278.64  4232.3  273.75  4308.2  271.95  4348.4  269.51  4622.9   262.7
  4644.6  260.17  4660.3  260.74  4666.3     263  4684.1  263.57  4807.6  264.16
    4980   265.5  4986.4  262.56  4994.3  262.09  5000.5  259.05  5008.7   260.1
  5015.1   264.3    5023  264.36  5043.9  264.54  5508.9  267.33  5541.5  266.32
  5742.5  266.56  5938.3  266.66  6022.1   268.1  6043.1  267.27  6100.5  268.76
#Mann= 5 ,-1 , 0
  3720.8      .1       0  4807.6     .07       0  5043.9      .1       0
  5541.5     .05       0  5742.5      .1       0
Bank Sta=4980,5023
XS Rating Curve= 0 ,0
Exp/Cntr=0.3,0.1

Type RM Length L Ch R = 1 ,4232    ,998,998,998
BEGIN DESCRIPTION:
UNT 013 IN RACR 2.0
END DESCRIPTION:
XS GIS Cut Line= 4
      2229340.17      13228263.9      2229522.46     13228194.46
       2230399.2     13227404.53      2230373.18     13226381.03
#Sta/Elev= 30
  4573.9   284.8  4602.9  284.18  4693.2  279.77  4785.3  274.22  4834.6  272.48
  4872.7  269.79  4969.1  263.22  4983.3  259.33  4987.8  255.07  4990.6  254.57
  5004.9  256.94  5011.7  262.63  5025.1  263.61  5040.1  263.51  5046.9   262.5
  5082.7  263.09  5188.9  261.88  5209.8  262.46  5394.4  261.48  5415.3  262.02
  5514.7  260.83  5691.3  260.67  5918.3   263.4  6315.1  264.51  6453.7  264.55
  6546.9  265.45    6667  264.55    6747  264.84    6757  265.89  6972.9  266.26
#Mann= 6 ,-1 , 0
  4573.9     .05       0  4872.7      .1       0  4969.1     .07       0
  5025.1      .1       0  6315.1     .05       0  6453.7      .1       0
Bank Sta=4969.1,5011.7
XS Rating Curve= 0 ,0
Exp/Cntr=0.3,0.1

Type RM Length L Ch R = 1 ,3234    ,1093,1093,1093
BEGIN DESCRIPTION:
Mapping XS fa2c6eee
END DESCRIPTION:
XS GIS Cut Line= 4
      2229426.98     13228741.33      2230321.07      13228489.6
      2230772.46     13227786.47      2230763.78      13226511.1
#Sta/Elev= 30
  3549.9  275.91  3659.2  272.39  3803.3  265.72  3872.7  263.39    3913  262.11
  4038.9  261.09  4391.8  261.04  4767.2  259.01    4948  259.27  4963.2  258.95
  4969.2  258.12  4978.4  255.27    4993  254.95  4996.5  252.67  4999.3  252.17
  5002.5  252.67  5005.5  254.58  5014.7  255.89  5028.6  259.56  5123.7  256.85
  5181.2  260.51  5302.1  261.93  5403.9  261.07  5443.9  261.76  5513.9  260.82
  5633.9  261.88  6033.9   263.2  6363.9  262.54  6500.8  263.72  6589.7  264.49
#Mann= 7 ,-1 , 0
  3549.9     .05       0  3803.3      .1       0  3872.7     .05       0
    4948     .03       0  5028.6     .05       0  5633.9      .1       0
  6500.8     .16       0
Bank Sta=4948,5028.6
XS Rating Curve= 0 ,0
Exp/Cntr=0.3,0.1

Type RM Length L Ch R = 1 ,2141    ,854,854,854
BEGIN DESCRIPTION:
Mapping XS ba1ba1b1
END DESCRIPTION:
XS GIS Cut Line= 4
      2231486.61     13228246.59      2231472.98     13228133.69
       2231483.4     13227387.17      2230972.42     13226615.06
#Sta/Elev= 30
  4738.7  259.77    4819  258.86  4859.3  256.79  4959.3  255.87  4979.3  254.76
  4989.3  252.97  4999.3  249.09  5006.3  248.38    5009  247.88  5012.3  248.38
  5019.3   251.5  5029.3  254.11  5039.3  256.56  5049.3  256.79  5149.3  256.58
  5249.3  254.91  5259.3  252.64  5269.3  253.27  5279.3  255.66  5289.3  255.96
  5299.3  255.13  5329.3   256.2  5359.3  255.95  5489.3  259.63  5569.3  260.78
  5885.7  260.51  5978.9  259.51  6195.6  262.46  6288.9  261.91  6524.9   263.9
#Mann= 4 ,-1 , 0
  4738.7      .1       0  4979.3     .05       0  5006.3     .05       0
  5019.3      .1       0
Bank Sta=4979.3,5029.3
XS Rating Curve= 0 ,0
Exp/Cntr=0.3,0.1