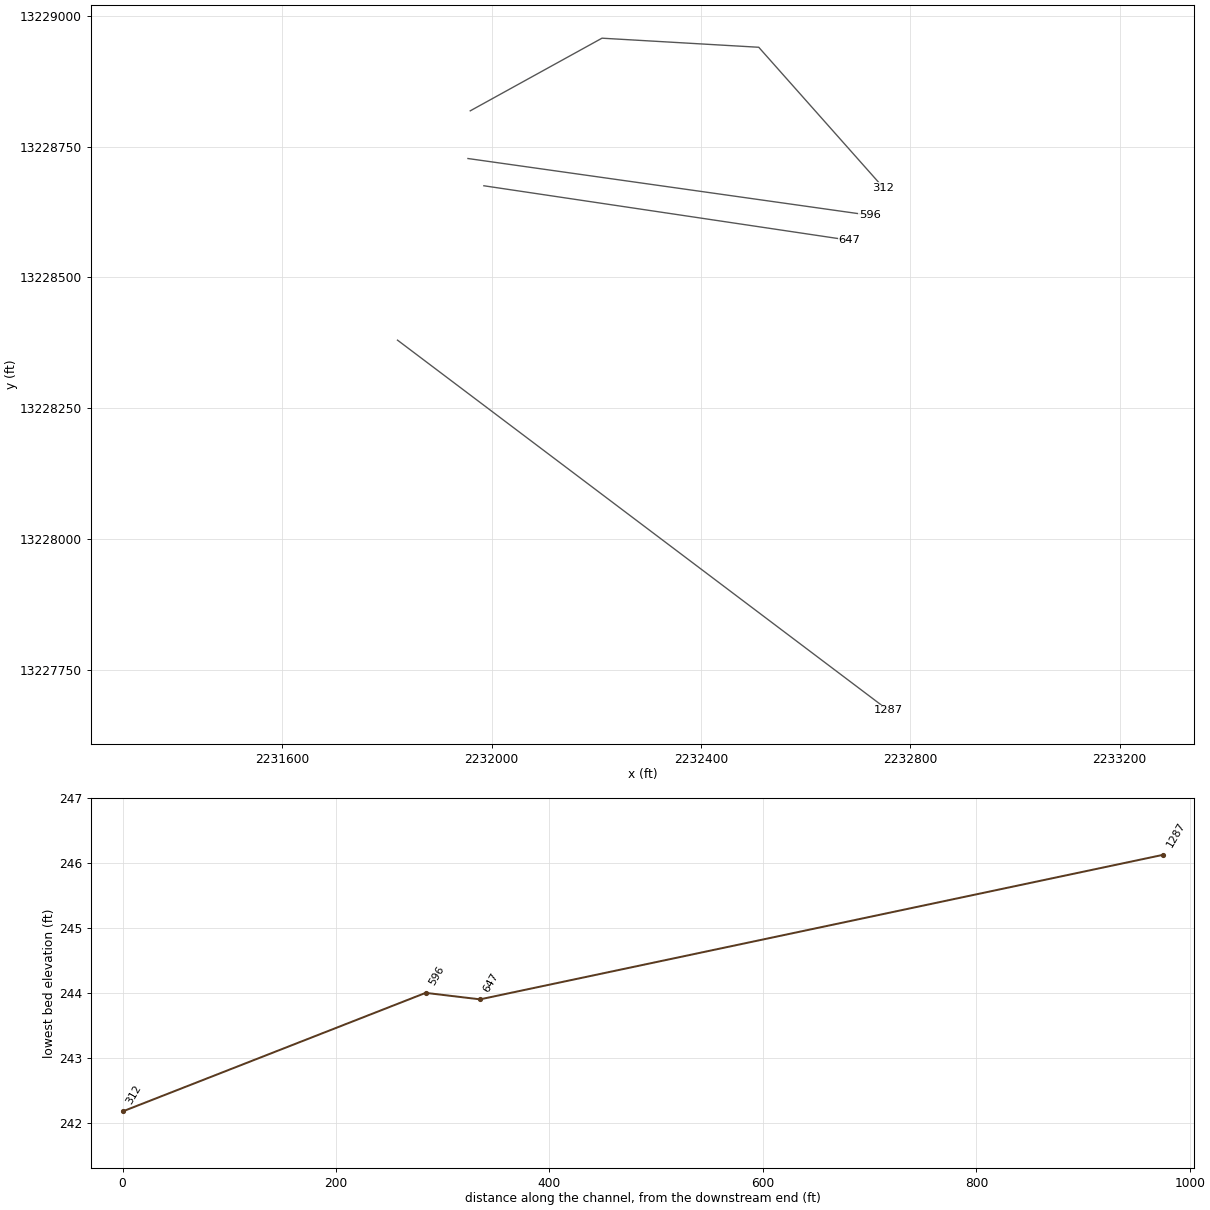
HEC-RAS study UNT 013 IN RACR.prj: UNT 013 IN RACR Base Level Engineering

--- UNT 013 IN RACR.g01 (geometry) --- (continued)

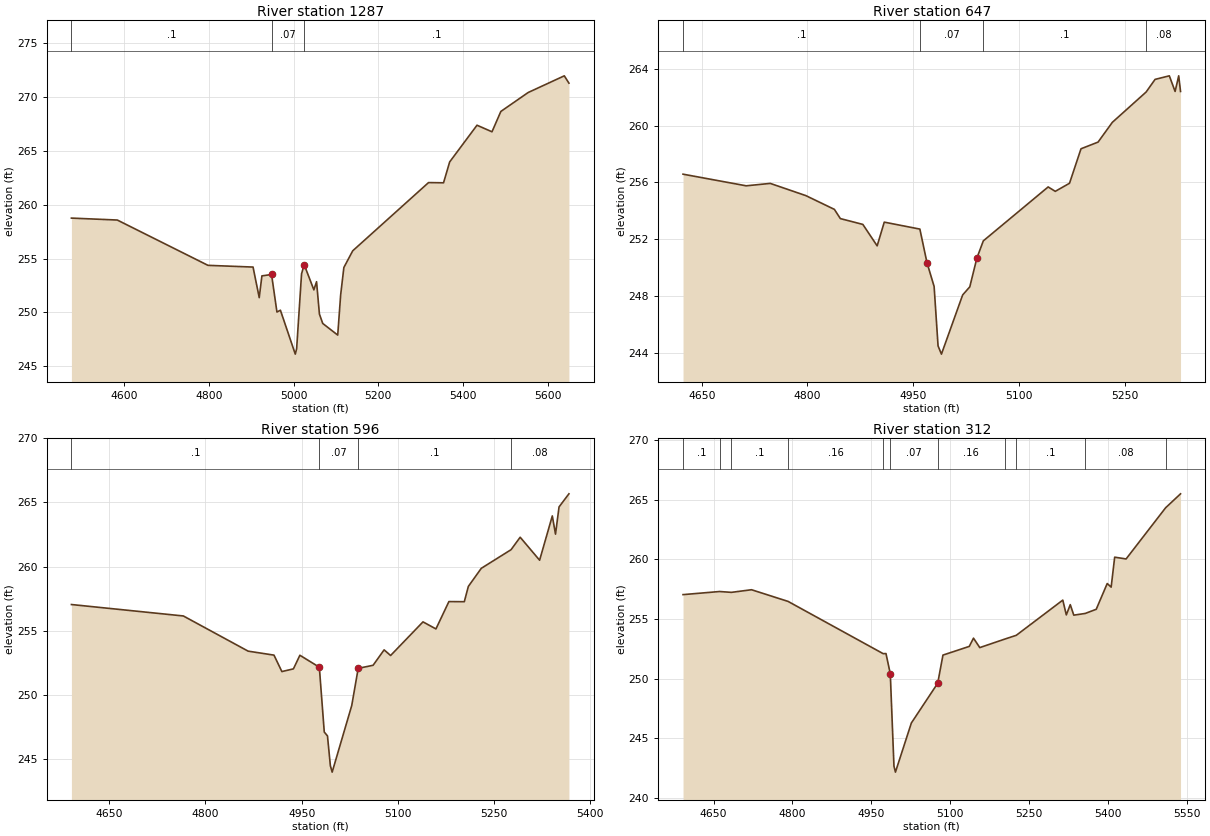
Type RM Length L Ch R = 1 ,1287    ,640,640,640
BEGIN DESCRIPTION:
Mapping XS b1b3760e
END DESCRIPTION:
XS GIS Cut Line= 2
      2231820.39     13228380.15       2232757.9     13227672.68
#Sta/Elev= 30
  4475.6  258.77  4583.9  258.59    4798  254.38  4904.4  254.22    4919  251.38
  4925.3   253.4  4948.1  253.53  4960.8  250.04    4969  250.21  5004.1  246.13
  5007.3  246.63  5018.9  253.59  5025.2  254.44    5048   252.1  5054.3  252.86
  5061.1  249.85  5068.9  248.98  5104.3   247.9  5111.2  251.63  5118.8  254.18
  5139.7  255.73  5318.7  262.07  5354.1  262.05  5368.6  263.99  5433.1   267.4
  5468.5  266.79  5489.4  268.68  5553.9  270.44  5639.2  271.99  5650.1  271.31
#Mann= 3 , 0 , 0
  4475.6      .1       0  4948.1     .07       0  5025.2      .1       0
Bank Sta=4948.1,5025.2
XS Rating Curve= 0 ,0
Exp/Cntr=0.3,0.1

Type RM Length L Ch R = 1 ,647     ,51,51,51
BEGIN DESCRIPTION:
Mapping XS 23ddcd6a
END DESCRIPTION:
XS GIS Cut Line= 2
      2231985.38     13228675.26      2232683.46      13228571.2
#Sta/Elev= 30
  4623.5  256.58  4713.1  255.76  4747.2  255.93  4797.7  255.07  4838.2   254.1
  4846.7  253.45  4878.6  253.04  4898.9  251.53    4909   253.2  4959.5  252.71
  4969.6  250.34  4979.7  248.67  4985.3  244.48  4990.1   243.9  5020.2  248.07
  5030.3  248.64  5040.4  250.67  5049.5  251.88  5141.5  255.68  5151.6  255.37
  5171.8  255.94  5188.1  258.37  5212.3  258.84  5232.5  260.23  5280.5  262.37
  5293.2  263.26  5313.4  263.51  5321.6  262.41  5326.7  263.51  5329.3  262.41
#Mann= 4 ,-1 , 0
  4623.5      .1       0  4959.5     .07       0  5049.5      .1       0
  5280.5     .08       0
Bank Sta=4969.6,5040.4
XS Rating Curve= 0 ,0
Exp/Cntr=0.3,0.1

Type RM Length L Ch R = 1 ,596     ,284,284,284
BEGIN DESCRIPTION:
Mapping XS 3c8f465e
END DESCRIPTION:
XS GIS Cut Line= 2
      2231954.98     13228727.35      2232722.95     13228618.87
#Sta/Elev= 30
    4591  257.05  4765.5  256.16  4866.5  253.42  4906.8  253.11  4919.1  251.83
  4937.1  252.04  4947.2   253.1  4977.5  252.17  4985.2  247.12  4990.2  246.82
  4994.7   244.5  4997.5     244    5028  249.18  5038.1  252.08  5061.3  252.32
  5078.5  253.52  5088.6  253.08  5139.1   255.7  5159.3  255.15  5179.5  257.28
  5203.5  257.27  5209.8  258.46    5230  259.87  5276.4  261.32  5290.6  262.29
  5320.9   260.5  5340.7  263.95  5345.7  262.53  5351.2  264.65  5366.6  265.67
#Mann= 4 ,-1 , 0
    4591      .1       0  4977.5     .07       0  5038.1      .1       0
  5276.4     .08       0
Bank Sta=4977.5,5038.1
XS Rating Curve= 0 ,0
Exp/Cntr=0.3,0.1

Type RM Length L Ch R = 1 ,312     ,0,0,0
BEGIN DESCRIPTION:
UNT 013 IN RACR 1.0
END DESCRIPTION:
XS GIS Cut Line= 4
      2231959.36     13228818.51      2232211.05     13228957.38
      2232510.53     13228940.02      2232748.81     13228671.42
#Sta/Elev= 30
    4592  257.05  4661.5  257.31    4684  257.24  4722.3  257.46  4791.9  256.48
  4972.8   252.1  4978.1  252.11  4986.3  250.42  4993.3  242.67  4996.1  242.17
  5026.4  246.29  5076.5  249.62  5086.5  251.98  5136.6  252.71  5144.6   253.4
  5156.6  252.61    5204  253.32    5226  253.64  5314.5  256.59  5321.2  255.35
  5328.7  256.21  5335.4  255.33    5357  255.47  5378.1  255.82    5399  257.98
  5406.5  257.68  5413.2  260.19  5434.9  260.04  5510.1  264.33  5538.5   265.5
#Mann= 11 ,-1 , 0
    4592      .1       0  4661.5     .16       0    4684      .1       0
  4791.9     .16       0  4972.8      .1       0  4986.3     .07       0
  5076.5     .16       0    5204     .08       0    5226      .1       0
    5357     .08       0  5510.1      .1       0
Bank Sta=4986.3,5076.5
XS Rating Curve= 0 ,0
Exp/Cntr=0.3,0.1
Stream Node=UNT 013 IN RACR ,Reach-1         , 0 , 0 ,Upstream end
Stream Node=UNT 013 IN RACR ,Reach-1         , 0 , 1 ,Downstream end

Chan Stop Cuts=-1
Use User Specified Reach Order=0
Composite Channel Slope=5