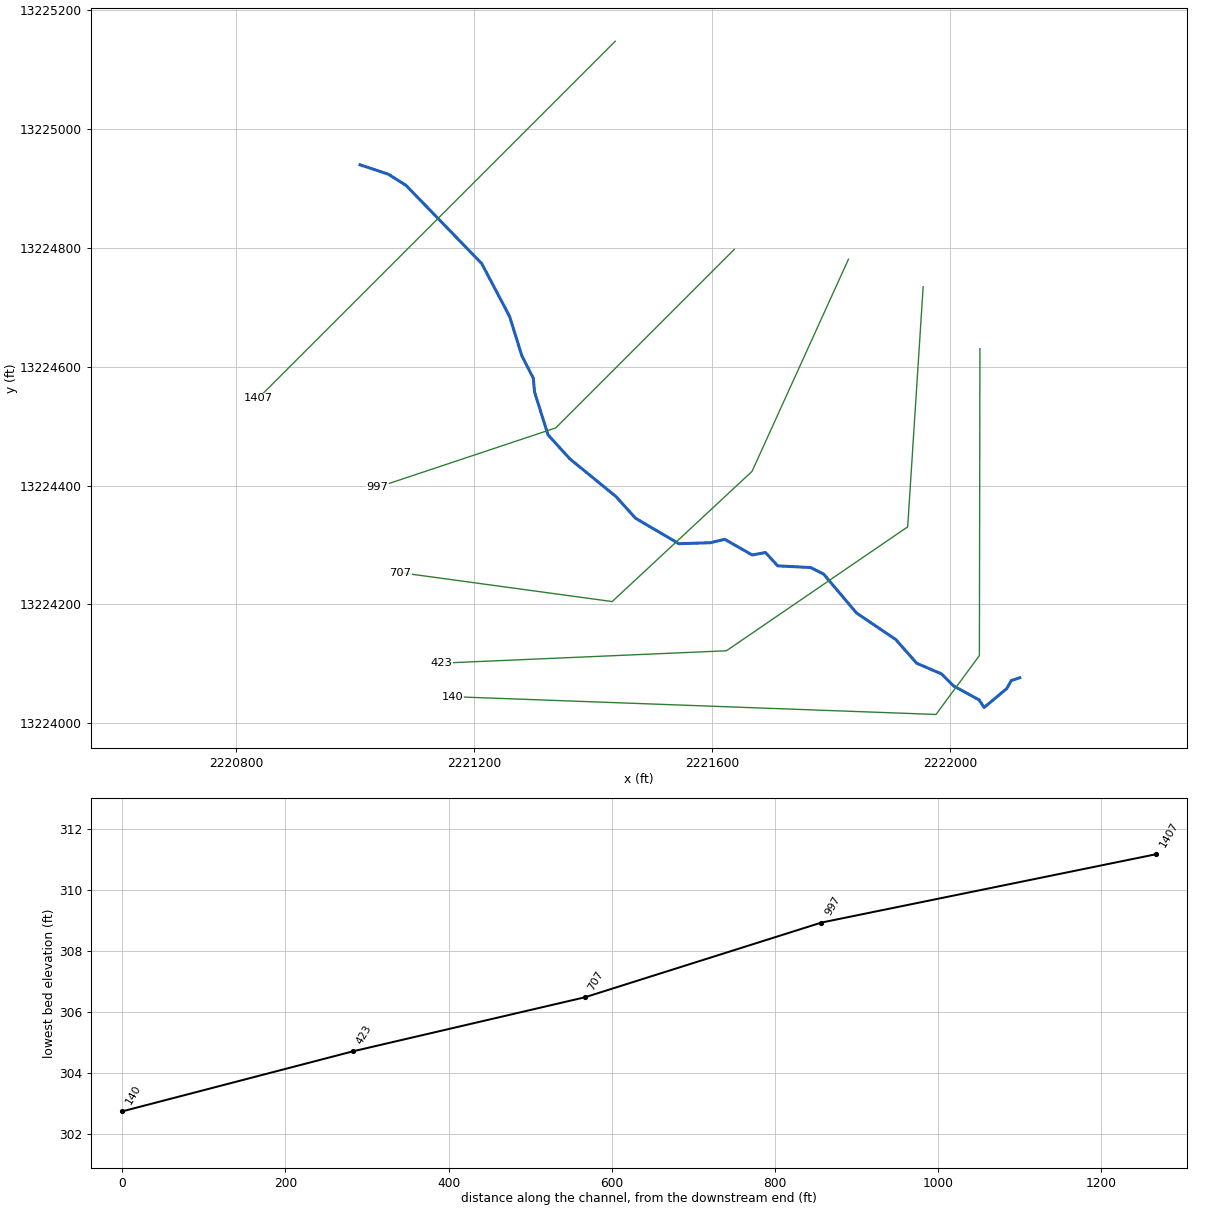
--- UNT 014 IN RACR.prj (project) ---

Proj Title=UNT 014 IN RACR Base Level Engineering
Current Plan=p01
Default Exp/Contr=0.3,0.1
English Units
Geom File=g01
Flow File=f01
Plan File=p01
Y Axis Title=Elevation
X Axis Title(PF)=Main Channel Distance
X Axis Title(XS)=Station
BEGIN DESCRIPTION:
UNT 014 IN RACR
END DESCRIPTION:
DSS Export Rating Curves= 0
DSS Export Rating Curve Sorted= 0
DSS Export Volume Flow Curves= 0
DXF OffsetX= 0
DXF OffsetY= 0
DXF ScaleX= 1
DXF ScaleY= 10

--- UNT 014 IN RACR.p01 (plan) ---

Plan Title=Multiple Run
Short Identifier=Multiple
Geom File=g01
Flow File=f01
Subcritical Flow
K Sum by GR= 0
Std Step Tol= 0.01
Critical Tol= 0.01
Num of Std Step Trials= 20
Max Error Tol= 0.3
Flow Tol Ratio= 0.001
Split Flow NTrial= 30
Split Flow Tol= 0.02
Split Flow Ratio= 0.02
Log Output Level= 0
Friction Slope Method= 1
Unsteady Friction Slope Method= 2
Unsteady Bridges Friction Slope Method= 1
Parabolic Critical Depth
Global Vel Dist=  1 , 1 , 1
Global Log Level= 0
CheckData=True
Encroach Param= -1, 0, 0, 0
BEGIN DESCRIPTION:
Multiple Run
END DESCRIPTION:

--- UNT 014 IN RACR.f01 (steady flow) ---

Flow Title=Multiple
Program Version=4.10
Number of Profiles= 7
Profile Names=10-year,25-year,50-year,1pct_min,100-year,1pct_plu,500-year
River Rch & RM=UNT 014 IN RACR,Reach-1         ,1407
     191     264     324     294     397     537     605
Boundary for River Rch & Prof#=UNT 014 IN RACR,Reach-1         , 1
Up Type= 0
Dn Type= 3
Dn Slope=0.005
Boundary for River Rch & Prof#=UNT 014 IN RACR,Reach-1         , 2
Up Type= 0
Dn Type= 3
Dn Slope=0.005
Boundary for River Rch & Prof#=UNT 014 IN RACR,Reach-1         , 3
Up Type= 0
Dn Type= 3
Dn Slope=0.005
Boundary for River Rch & Prof#=UNT 014 IN RACR,Reach-1         , 4
Up Type= 0
Dn Type= 3
Dn Slope=0.005
Boundary for River Rch & Prof#=UNT 014 IN RACR,Reach-1         , 5
Up Type= 0
Dn Type= 3
Dn Slope=0.005
Boundary for River Rch & Prof#=UNT 014 IN RACR,Reach-1         , 6
Up Type= 0
Dn Type= 3
Dn Slope=0.005
Boundary for River Rch & Prof#=UNT 014 IN RACR,Reach-1         , 7
Up Type= 0
Dn Type= 3
Dn Slope=0.005
DSS Import GetInterval= 0
DSS Import GetPeak= 0
DSS Import FillOption= 0

--- UNT 014 IN RACR.g01 (geometry) ---

Geom Title=Existing Conditions
Program Version=4.10

River Reach=UNT 014 IN RACR ,Reach-1
Reach XY= 30
      2221008.64     13224939.04      2221056.31     13224923.24
      2221086.09     13224904.36      2221213.22     13224773.03
      2221260.05     13224684.26      2221280.68     13224618.07
        2221300.     13224580.08      2221301.93     13224557.39
      2221324.61     13224485.19      2221361.41     13224444.73
      2221439.04     13224381.26       2221471.7     13224345.03
      2221544.69     13224302.17      2221597.38      13224303.8
       2221621.7     13224309.54      2221667.85     13224283.22
      2221690.27     13224287.33      2221710.68     13224264.95
       2221765.9      13224262.1      2221787.82     13224251.25
      2221843.21     13224185.68      2221909.09     13224141.15
       2221944.4      13224101.2      2221985.89     13224083.43
       2222006.4     13224063.09      2222049.28     13224039.58
      2222057.72     13224026.85      2222095.87     13224058.77
      2222103.44     13224072.17      2222117.72     13224076.85

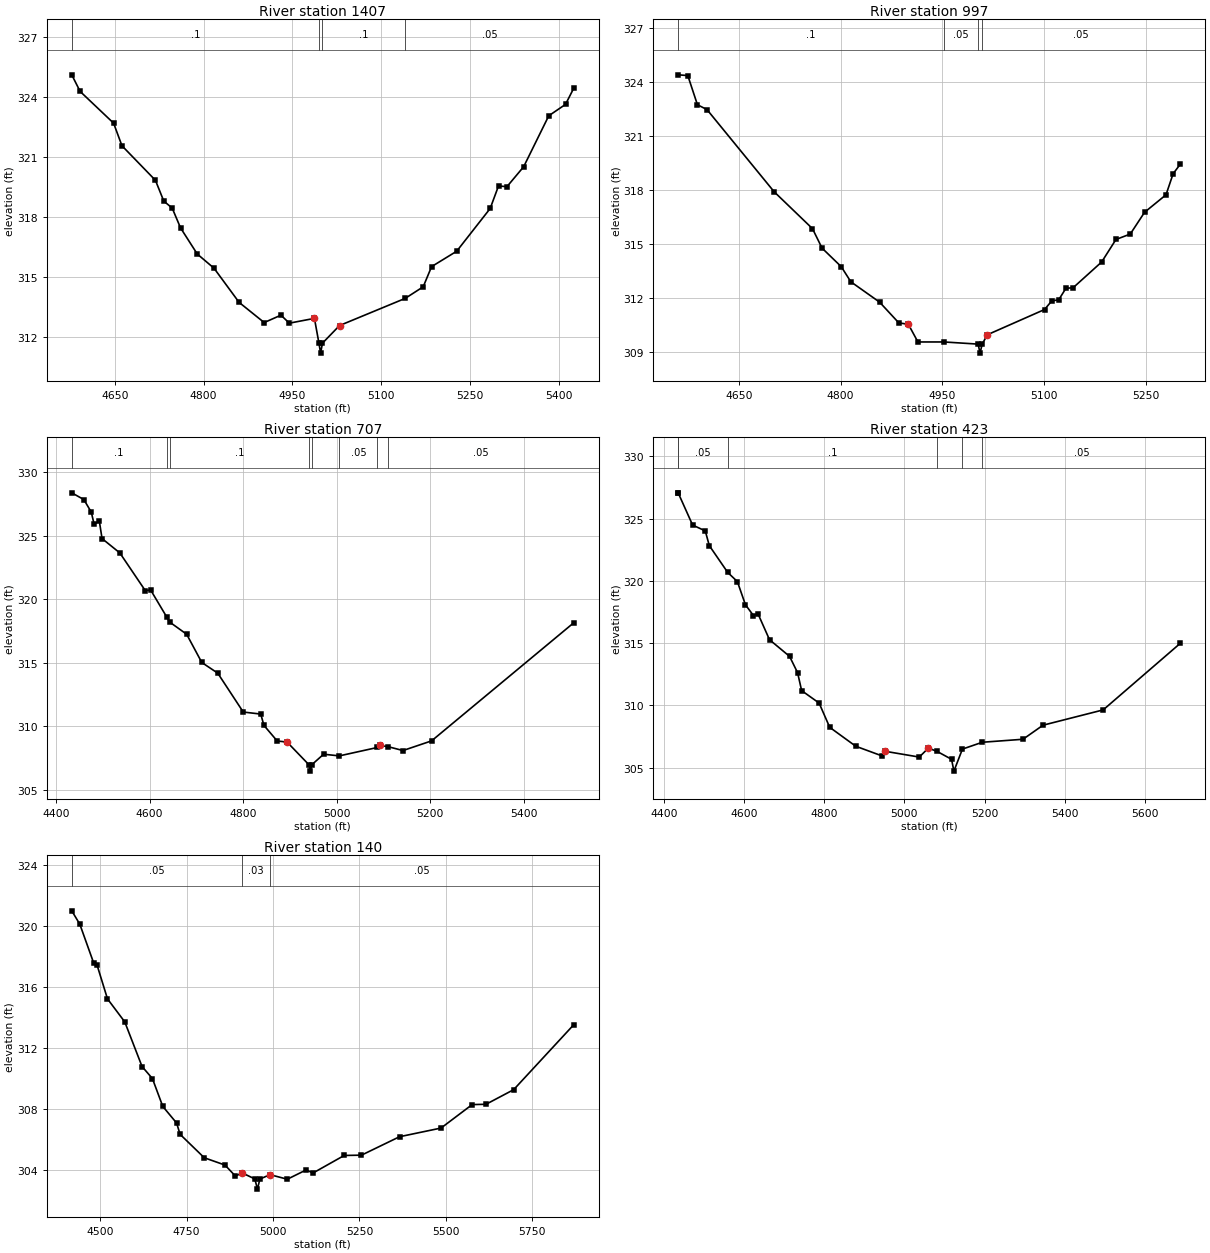
Type RM Length L Ch R = 1 ,1407    ,410,410,410
BEGIN DESCRIPTION:
UNT 014 IN RACR 3.0
END DESCRIPTION:
XS GIS Cut Line= 3
       2221437.7     13225146.84      2221137.72     13224846.85
      2220837.72     13224546.86
#Sta/Elev= 30
  4577.2   325.1  4591.3  324.27  4647.9  322.68    4662  321.55  4718.6  319.82
  4732.7  318.78  4746.9  318.43    4761  317.44  4789.3  316.13  4817.6  315.42
    4860  313.71  4902.4   312.7  4930.7  313.07  4944.9  312.67  4987.3  312.91
  4994.9  311.67  4997.7  311.17  5000.9  311.67  5029.7  312.55  5140.7  313.91
  5171.1  314.49  5185.3   315.5  5227.7  316.27  5284.3  318.41  5298.4  319.54
  5312.6   319.5  5340.9   320.5  5383.3  323.05  5411.6  323.62  5425.7  324.44
#Mann= 4 ,-1 , 0
  4577.2      .1       0  4994.9     .07       0  5000.9      .1       0
  5140.7     .05       0
Bank Sta=4987.3,5029.7
XS Rating Curve= 0 ,0
Exp/Cntr=0.3,0.1

Type RM Length L Ch R = 1 ,997     ,290,290,290
BEGIN DESCRIPTION:
UNT 014 IN RACR 2.0
END DESCRIPTION:
XS GIS Cut Line= 3
      2221637.72     13224796.85      2221337.72     13224496.85
      2221037.71     13224396.85
#Sta/Elev= 30
  4560.5  324.38  4574.6  324.34  4588.8  322.72  4602.9  322.45  4701.9  317.89
  4758.5  315.84  4772.6  314.76  4800.9  313.73  4815.1  312.89  4857.5  311.76
  4885.8  310.61  4899.9  310.53    4914  309.55  4952.6  309.55  5002.8  309.43
  5005.6  308.93  5008.8  309.43  5016.4  309.95  5100.7  311.35  5111.2  311.82
  5121.8   311.9  5132.3  312.53  5142.9  312.56    5185  313.99  5206.1  315.24
  5227.2  315.54  5248.3  316.75  5279.9  317.72  5290.4  318.89    5301  319.42
#Mann= 4 ,-1 , 0
  4560.5      .1       0  4952.6     .05       0  5002.8     .03       0
  5008.8     .05       0
Bank Sta=4899.9,5016.4
XS Rating Curve= 0 ,0
Exp/Cntr=0.3,0.1

Type RM Length L Ch R = 1 ,707     ,284,284,284
BEGIN DESCRIPTION:
Mapping XS cf09fa2a
END DESCRIPTION:
XS GIS Cut Line= 4
      2221829.69     13224780.38      2221667.58     13224423.75
      2221432.53     13224204.91      2221075.93     13224253.54
#Sta/Elev= 30
  4433.9  328.38  4459.7  327.85  4475.6  326.86  4481.7   325.9  4492.7  326.17
  4498.6  324.78  4536.6  323.65  4590.9  320.69  4602.5  320.73  4636.6  318.62
  4643.1  318.21  4679.4  317.25  4711.7  315.03  4745.8  314.19  4800.3  311.13
  4837.7  310.97  4844.5  310.08  4872.9  308.85  4893.9  308.77  4940.7  306.98
  4943.5  306.48  4946.7  306.98    4972  307.81  5005.7  307.68  5086.7  308.34
  5092.2   308.5  5109.2  308.41  5141.6   308.1  5202.7  308.86  5506.7  318.16
#Mann= 8 ,-1 , 0
  4433.9      .1       0  4636.6     .05       0  4643.1      .1       0
  4940.7     .07       0  4946.7      .1       0  5005.7     .05       0
  5086.7      .1       0  5109.2     .05       0
Bank Sta=4893.9,5092.2
XS Rating Curve= 0 ,0
Exp/Cntr=0.3,0.1

Type RM Length L Ch R = 1 ,423     ,283,283,283
BEGIN DESCRIPTION:
Mapping XS c72ad9a0
END DESCRIPTION:
XS GIS Cut Line= 4
      2221955.26     13224734.18      2221929.22     13224330.52
      2221624.53     13224122.18      2221145.39     13224101.35
#Sta/Elev= 30
  4435.5  327.07    4436  327.02  4471.4  324.48    4503  324.01    4513  322.83
  4559.1  320.67  4583.1  319.94  4603.2  318.08  4623.2  317.21  4634.3  317.37
  4663.3  315.27  4713.4  313.93  4733.4  312.62  4743.5  311.18  4787.1  310.18
  4813.6  308.23  4878.6  306.71  4944.4  305.93  4950.8  306.31  5037.1  305.84
  5059.9  306.56  5081.9  306.29  5117.7  305.66  5123.6  304.71  5144.8  306.48
  5194.5  307.03    5296  307.27    5346   308.4  5496.2  309.63  5688.7  314.98
#Mann= 6 ,-1 , 0
  4435.5      .1       0    4436     .05       0  4559.1      .1       0
  5081.9     .07       0  5144.8      .1       0  5194.5     .05       0
Bank Sta=4950.8,5059.9
XS Rating Curve= 0 ,0
Exp/Cntr=0.3,0.1

Type RM Length L Ch R = 1 ,140     ,0,0,0
BEGIN DESCRIPTION:
UNT 014 IN RACR 1.0
END DESCRIPTION:
XS GIS Cut Line= 4
       2222050.7     13224630.14      2222049.76      13224114.1
      2221976.84     13224015.14      2221163.75     13224045.04
#Sta/Elev= 30
  4417.8  321.01  4441.1  320.13  4481.1  317.59  4491.1  317.44  4521.1  315.23
  4571.1  313.72  4621.1  310.79  4651.1     310  4681.1  308.17  4721.1  307.08
  4731.1  306.34  4801.1   304.8  4861.1  304.32  4891.1   303.6  4911.1   303.8
  4947.4  303.41    4955  302.74    4962   303.4  4991.3  303.69  5041.4  303.39
  5095.9     304  5115.9   303.8    5206  304.95    5256  304.97  5366.1  306.18
  5486.2  306.75  5576.2  308.29  5616.3  308.31  5696.3  309.27  5870.4  313.54
#Mann= 3 , 0 , 0
  4417.8     .05       0  4911.1     .03       0  4991.3     .05       0
Bank Sta=4911.1,4991.3
XS Rating Curve= 0 ,0
Exp/Cntr=0.3,0.1

Chan Stop Cuts=-1
Use User Specified Reach Order=0
Composite Channel Slope=5