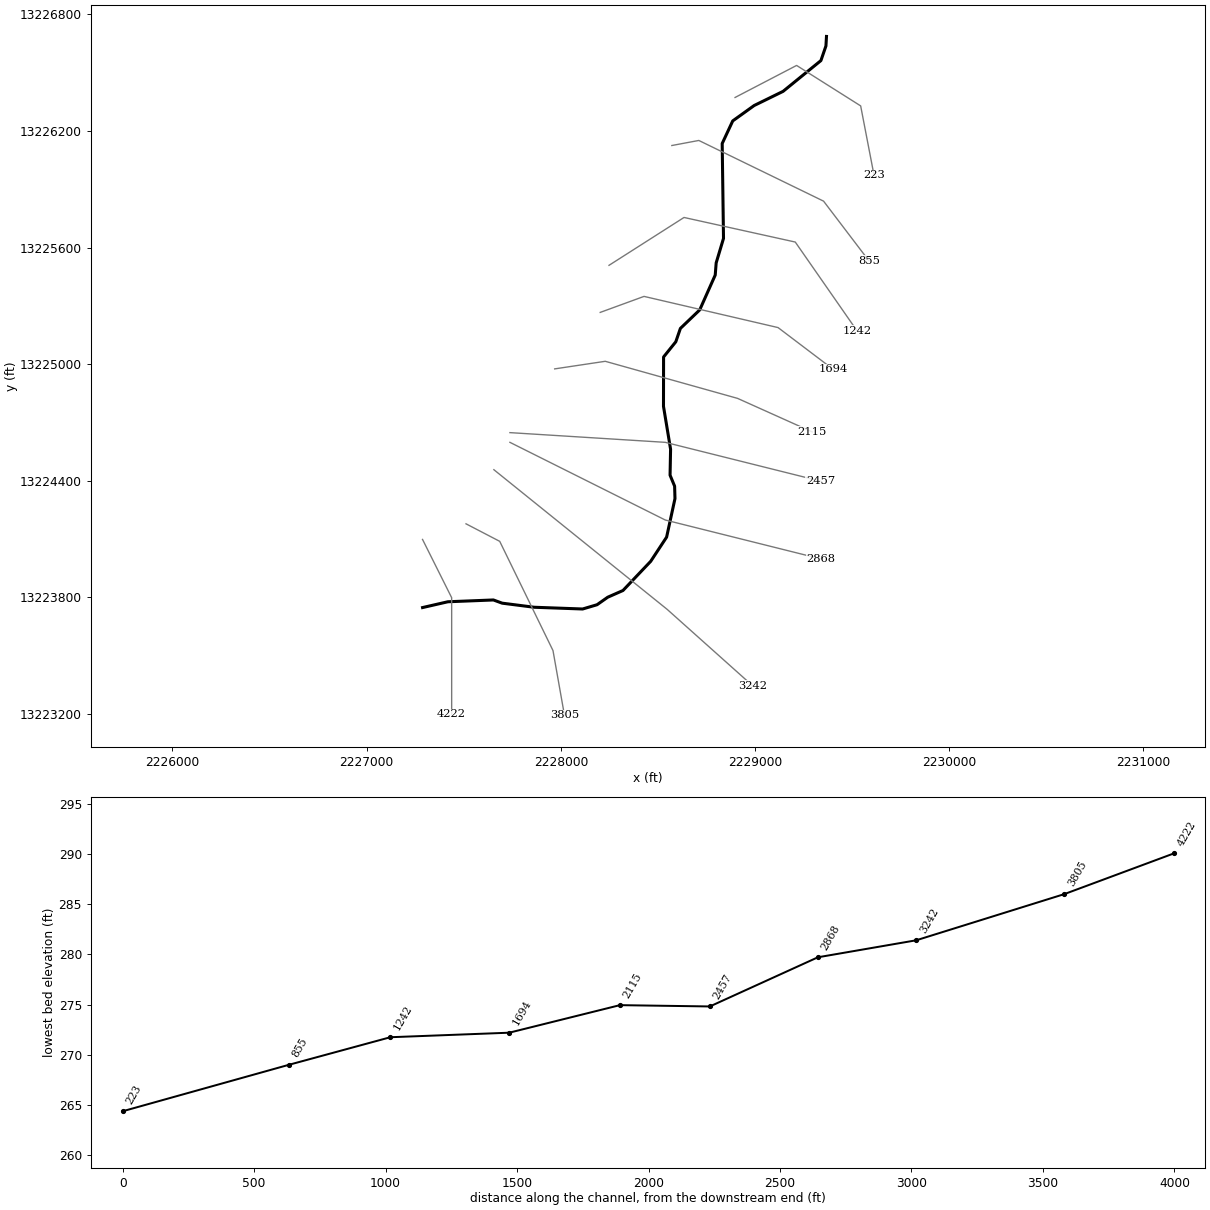
--- UNT 015 IN RACR.prj (project) ---

Proj Title=UNT 015 IN RACR Base Level Engineering
Current Plan=p01
Default Exp/Contr=0.3,0.1
English Units
Geom File=g01
Flow File=f01
Plan File=p01
Y Axis Title=Elevation
X Axis Title(PF)=Main Channel Distance
X Axis Title(XS)=Station
BEGIN DESCRIPTION:
UNT 015 IN RACR
END DESCRIPTION:
DSS Export Rating Curves= 0
DSS Export Rating Curve Sorted= 0
DSS Export Volume Flow Curves= 0
DXF OffsetX= 0
DXF OffsetY= 0
DXF ScaleX= 1
DXF ScaleY= 10

--- UNT 015 IN RACR.p01 (plan) ---

Plan Title=Multiple Run
Short Identifier=Multiple
Geom File=g01
Flow File=f01
Subcritical Flow
K Sum by GR= 0
Std Step Tol= 0.01
Critical Tol= 0.01
Num of Std Step Trials= 20
Max Error Tol= 0.3
Flow Tol Ratio= 0.001
Split Flow NTrial= 30
Split Flow Tol= 0.02
Split Flow Ratio= 0.02
Log Output Level= 0
Friction Slope Method= 1
Unsteady Friction Slope Method= 2
Unsteady Bridges Friction Slope Method= 1
Parabolic Critical Depth
Global Vel Dist=  1 , 1 , 1
Global Log Level= 0
CheckData=True
Encroach Param= -1, 0, 0, 0
BEGIN DESCRIPTION:
Multiple Run
END DESCRIPTION:

--- UNT 015 IN RACR.f01 (steady flow) ---

Flow Title=Multiple
Program Version=4.10
Number of Profiles= 7
Profile Names=10-year,25-year,50-year,1pct_min,100-year,1pct_plu,500-year
River Rch & RM=UNT 015 IN RACR,Reach-1         ,4222
     266     372     460     419     567     767     874
Boundary for River Rch & Prof#=UNT 015 IN RACR,Reach-1         , 1
Up Type= 0
Dn Type= 3
Dn Slope=0.01
Boundary for River Rch & Prof#=UNT 015 IN RACR,Reach-1         , 2
Up Type= 0
Dn Type= 3
Dn Slope=0.01
Boundary for River Rch & Prof#=UNT 015 IN RACR,Reach-1         , 3
Up Type= 0
Dn Type= 3
Dn Slope=0.01
Boundary for River Rch & Prof#=UNT 015 IN RACR,Reach-1         , 4
Up Type= 0
Dn Type= 3
Dn Slope=0.01
Boundary for River Rch & Prof#=UNT 015 IN RACR,Reach-1         , 5
Up Type= 0
Dn Type= 3
Dn Slope=0.01
Boundary for River Rch & Prof#=UNT 015 IN RACR,Reach-1         , 6
Up Type= 0
Dn Type= 3
Dn Slope=0.01
Boundary for River Rch & Prof#=UNT 015 IN RACR,Reach-1         , 7
Up Type= 0
Dn Type= 3
Dn Slope=0.01
DSS Import GetInterval= 0
DSS Import GetPeak= 0
DSS Import FillOption= 0

--- UNT 015 IN RACR.g01 (geometry) ---

Geom Title=Existing Conditions
Program Version=4.10

River Reach=UNT 015 IN RACR ,Reach-1
Reach XY= 30
      2227287.89     13223746.06       2227418.3     13223775.94
       2227652.7      13223785.2      2227697.81     13223768.71
      2227862.42     13223747.69      2228112.13     13223738.69
       2228186.4     13223760.73      2228241.39     13223799.35
      2228319.89     13223833.95      2228462.57     13223984.13
      2228544.52     13224108.78      2228587.59     13224307.05
      2228585.76     13224371.05      2228562.31     13224427.68
      2228564.97     13224561.36      2228528.44     13224782.15
      2228528.91     13225036.41      2228591.79     13225114.52
      2228615.48     13225183.44      2228714.91     13225278.63
      2228794.83     13225458.05      2228799.75     13225521.01
      2228837.47     13225646.96      2228830.75     13226135.58
      2228885.04     13226251.96      2228995.36     13226331.17
      2229144.22     13226404.08      2229339.01     13226562.51
      2229364.93     13226637.95      2229367.72     13226686.85

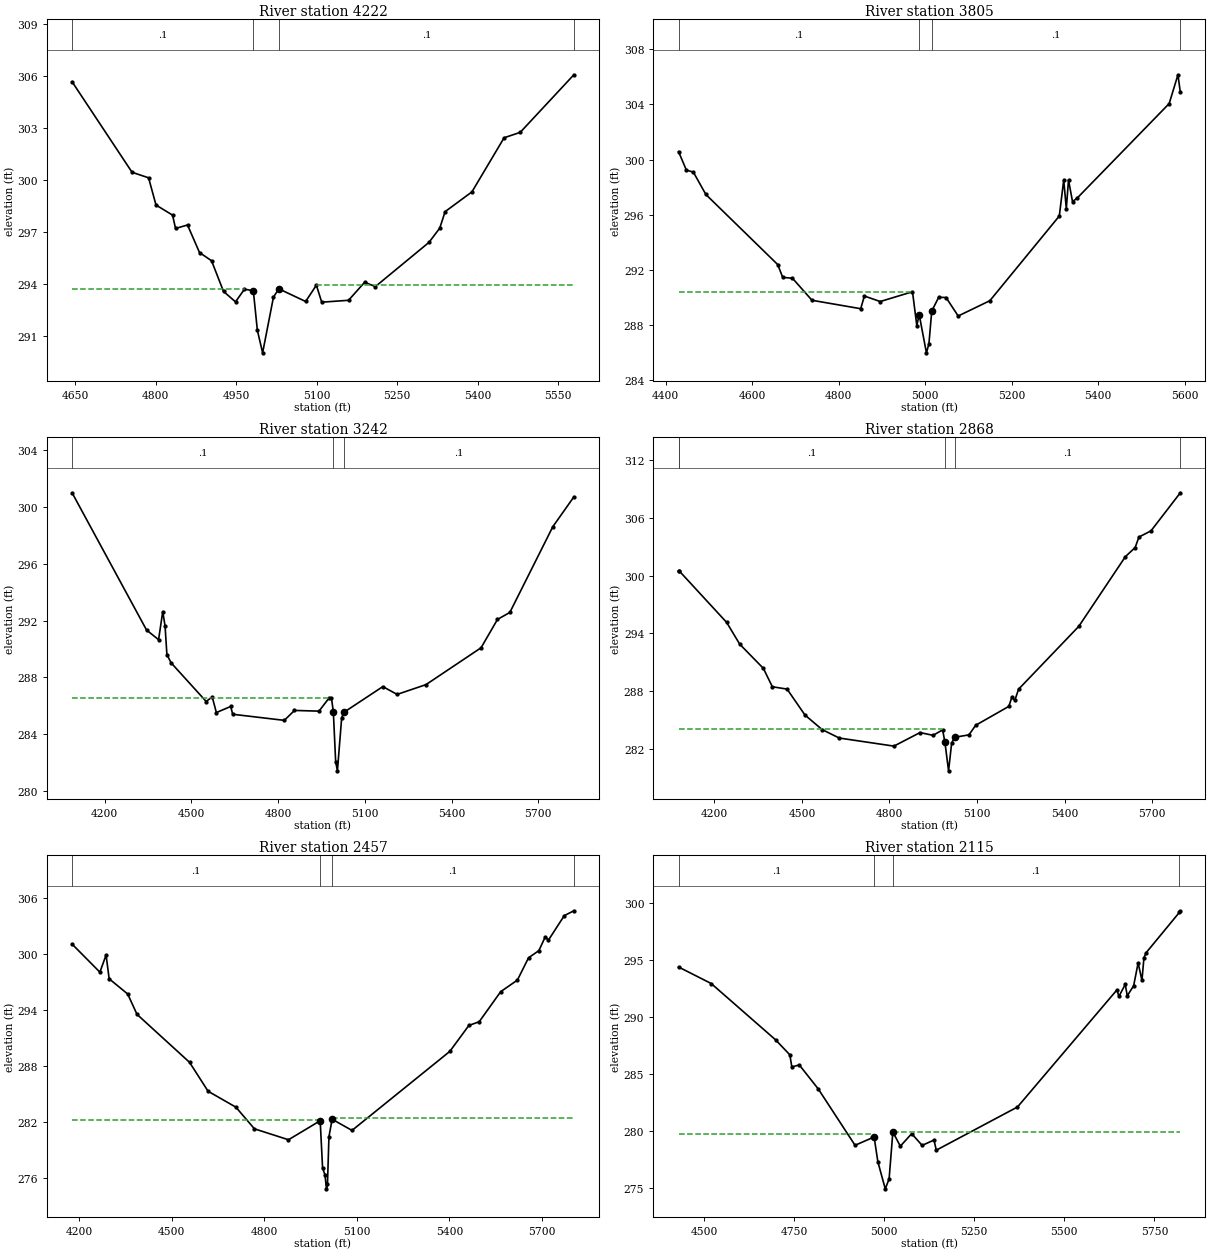
Type RM Length L Ch R = 1 ,4222    ,417,417,417
BEGIN DESCRIPTION:
UNT 015 IN RACR 8.0
END DESCRIPTION:
XS GIS Cut Line= 3
      2227287.72     13224096.86      2227437.72     13223796.85
      2227437.72     13223196.87
#Sta/Elev= 30
  4643.8  305.67  4755.6  300.45  4786.4  300.13  4800.3  298.56  4831.1  297.98
  4836.7  297.21    4859  297.41  4881.4  295.82  4903.8  295.35  4926.1  293.58
  4948.5  292.98  4965.2  293.71  4981.7  293.62  4989.2  291.34    4999  290.04
  5019.2  293.25  5029.2  293.73  5079.2     293  5099.2  293.94  5109.2  292.96
  5159.2  293.07  5189.2  294.11  5209.2  293.86  5309.2  296.41  5329.2  297.23
  5339.2  298.18  5389.2  299.32  5449.2  302.44  5479.2  302.75  5579.2  306.07
#Mann= 4 ,-1 , 0
  4643.8      .1       0  4981.7     .07       0  5029.2      .1       0
  5579.2      .1       0
#XS Ineff= 2 , 0
       0 4965.97  293.72 5099.31       0  293.93
Permanent Ineff=
       T       T
Bank Sta=4981.7,5029.2
XS Rating Curve= 0 ,0
Exp/Cntr=0.3,0.1

Type RM Length L Ch R = 1 ,3805    ,563,563,563
BEGIN DESCRIPTION:
UNT 015 IN RACR 7.0
END DESCRIPTION:
XS GIS Cut Line= 4
      2227511.63      13224177.3      2227685.22     13224087.03
      2227959.52     13223524.53       2228018.5     13223191.49
#Sta/Elev= 30
    4430  300.58  4448.1  299.24  4464.3  299.09  4493.2  297.47  4659.2  292.39
  4670.8  291.46  4693.3   291.4  4738.4   289.8    4851  289.19  4859.5  290.11
  4896.1  289.71  4970.7  290.42  4980.7  287.97  4986.2  288.76  5002.9  285.99
  5008.7  286.65  5015.2  289.02  5031.3  290.02  5048.3     290  5076.3  288.66
  5149.5  289.77    5310  295.91  5320.2  298.52  5326.2  296.45  5331.3  298.52
  5340.5  296.96  5350.7  297.19  5563.9  304.06  5584.2  306.15  5589.7  304.88
#Mann= 4 ,-1 , 0
    4430      .1       0  4986.2     .07       0  5015.2      .1       0
  5589.7     .05       0
#XS Ineff= 2 , 0
       0 4970.83  290.41 5048.33       0  289.97
Permanent Ineff=
       T       T
Bank Sta=4986.2,5015.2
XS Rating Curve= 0 ,0
Exp/Cntr=0.3,0.1

Type RM Length L Ch R = 1 ,3242    ,374,374,374
BEGIN DESCRIPTION:
UNT 015 IN RACR 6.0
END DESCRIPTION:
XS GIS Cut Line= 3
      2227655.07     13224455.95      2228547.61     13223736.59
      2228987.22     13223343.61
#Sta/Elev= 30
  4086.9  301.01  4344.6  291.33  4386.2  290.65  4400.6  292.63  4408.6  291.62
    4415   289.6  4429.4  289.02  4550.9  286.29  4571.7  286.62  4586.1  285.51
  4635.7  285.94  4642.6  285.39  4821.2  284.96  4856.4  285.66  4941.2  285.61
  4976.5  286.55  4984.4  286.52  4990.8  285.57  4998.8  282.05  5004.9   281.4
  5019.6  285.14  5027.5  285.53  5161.9  287.34  5211.5  286.79  5311.3  287.48
  5501.9  290.08  5558.7  292.08  5601.4  292.57  5750.2  298.62  5822.9  300.72
#Mann= 3 , 0 , 0
  4086.9      .1       0  4990.8     .07       0  5027.5      .1       0
#XS Ineff= 2 , 0
       0 4981.94  286.54               0
Permanent Ineff=
       T       F
Bank Sta=4990.8,5027.5
XS Rating Curve= 0 ,0
Exp/Cntr=0.3,0.1

Type RM Length L Ch R = 1 ,2868    ,411,411,411
BEGIN DESCRIPTION:
UNT 015 IN RACR 5.0
END DESCRIPTION:
XS GIS Cut Line= 3
      2227737.71     13224596.86      2228537.72     13224196.85
      2229337.76     13223996.84
#Sta/Elev= 30
  4077.3  300.48  4080.1  300.48  4242.2  295.14  4286.9  292.88    4368  290.36
  4398.7  288.45  4449.1  288.21  4510.5  285.51  4569.2     284  4627.9  283.12
  4815.2  282.28  4904.7  283.69  4949.4   283.4    4982  283.97  4989.8  282.71
  5002.4  279.71    5013   282.6  5023.3   283.2  5072.2  283.45  5095.4  284.45
  5208.8  286.41  5219.1  287.35  5229.4  287.04  5242.3   288.2  5448.5  294.73
  5608.2  301.98  5641.7  302.93  5654.6  304.02  5695.9  304.66  5796.4  308.62
#Mann= 5 ,-1 , 0
  4077.3     .05       0  4080.1      .1       0  4989.8     .07       0
  5023.3      .1       0  5796.4      .1       0
#XS Ineff= 2 , 0
       0 4981.25  284.05               0
Permanent Ineff=
       T       F
Bank Sta=4989.8,5023.3
XS Rating Curve= 0 ,0
Exp/Cntr=0.3,0.1

Type RM Length L Ch R = 1 ,2457    ,342,342,342
BEGIN DESCRIPTION:
UNT 015 IN RACR 4.0
END DESCRIPTION:
XS GIS Cut Line= 3
      2227737.73     13224646.85      2228537.72     13224596.85
      2229337.75     13224396.85
#Sta/Elev= 30
    4177  301.05  4267.2  298.04  4287.2  299.88  4297.2  297.33  4357.3   295.7
  4387.4  293.52  4557.7  288.38  4617.8  285.28    4708  283.57  4768.1  281.25
  4878.4  280.08  4981.1  282.12  4988.9  277.04  4996.6  276.33  5001.5  274.82
  5004.7  275.32  5009.5  280.41  5019.8  282.28  5084.2  281.08  5401.2  289.55
    5463  292.33  5496.5  292.73  5566.1  295.95  5620.2  297.19  5656.3  299.58
  5689.8  300.35  5710.4  301.82  5720.7  301.47  5772.2   304.1  5803.2  304.62
#Mann= 4 ,-1 , 0
    4177      .1       0  4981.1     .07       0  5019.8      .1       0
  5803.2     .05       0
#XS Ineff= 2 , 0
       0 4979.17  282.16    5025       0  282.38
Permanent Ineff=
       T       T
Bank Sta=4981.1,5019.8
XS Rating Curve= 0 ,0
Exp/Cntr=0.3,0.1

Type RM Length L Ch R = 1 ,2115    ,421,421,421
BEGIN DESCRIPTION:
UNT 015 IN RACR 3.0
END DESCRIPTION:
XS GIS Cut Line= 4
      2227968.16     13224975.05      2228228.62     13225014.11
      2228910.04     13224823.14      2229294.54     13224650.33
#Sta/Elev= 30
  4429.2  294.41  4519.8  292.96  4698.9  288.01  4738.2   286.7  4743.6  285.64
  4764.3  285.82  4816.8  283.72  4919.1  278.77    4972   279.5  4982.4  277.32
  5002.9  274.95  5013.6  275.82    5024  279.94  5044.7  278.69  5076.3  279.79
  5105.2  278.76  5138.2  279.23  5144.5  278.34  5369.9  282.13  5645.9   292.4
  5651.3  291.83    5669  292.88  5674.5  291.88  5692.2  292.76  5704.7  294.77
  5715.3  293.23  5720.8  295.21  5726.6  295.65  5819.2   299.2  5821.8  299.34
#Mann= 4 ,-1 , 0
  4429.2      .1       0    4972     .05       0    5024      .1       0
  5819.2     .05       0
#XS Ineff= 2 , 0
       0 4963.33  279.79 5024.44       0  279.94
Permanent Ineff=
       T       T
Bank Sta=4972,5024
XS Rating Curve= 0 ,0
Exp/Cntr=0.3,0.1

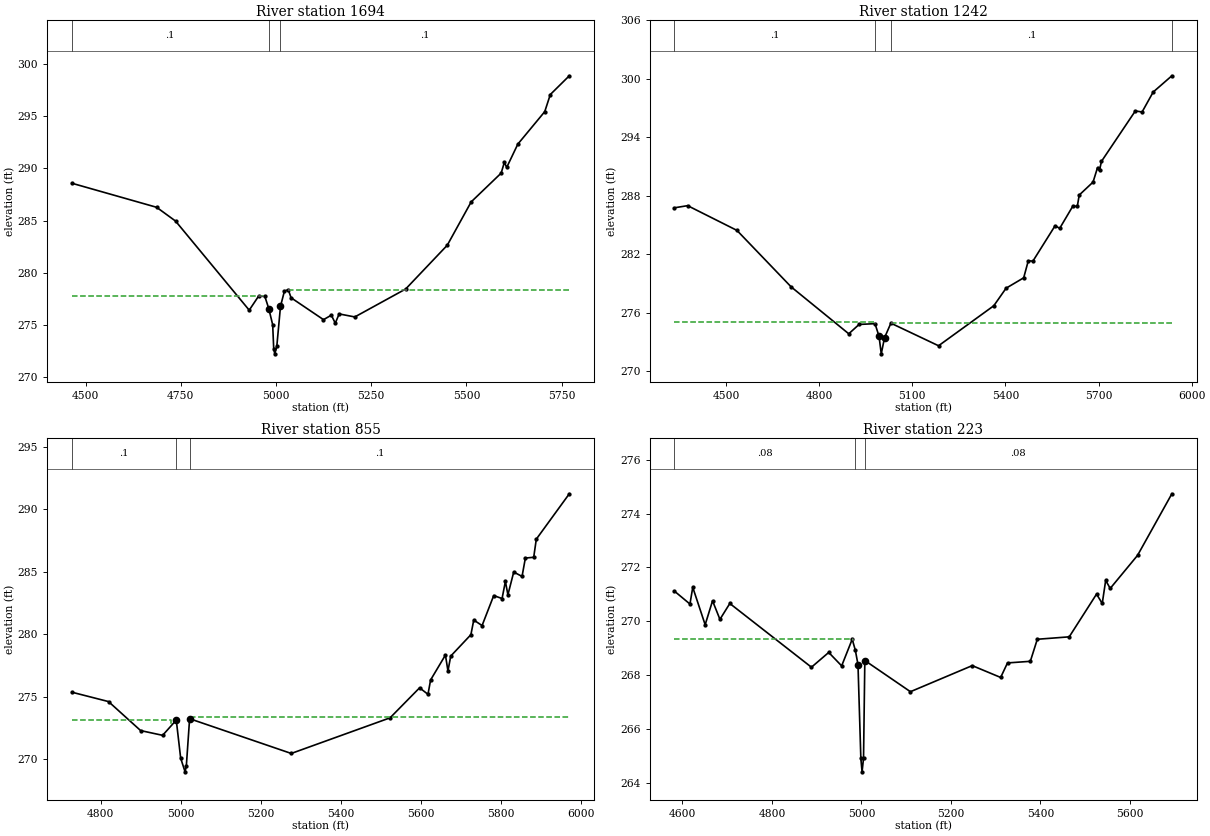
Type RM Length L Ch R = 1 ,1694    ,452,452,452
BEGIN DESCRIPTION:
UNT 015 IN RACR 2.0
END DESCRIPTION:
XS GIS Cut Line= 4
       2228202.6     13225265.86      2228428.27     13225348.32
      2229118.38     13225187.73      2229403.01     13224972.09
#Sta/Elev= 30
    4464  288.58  4686.6  286.27  4736.2  284.95  4929.6   276.4  4954.3  277.75
  4970.6  277.72  4980.9  276.56  4991.2     275  4993.9  272.71  4996.7  272.21
    5002  272.92  5011.7  276.76    5022  278.23  5032.2  278.36  5039.5  277.59
  5124.6  275.49  5145.2  275.92  5155.5  275.15  5165.7  276.04  5206.8  275.75
  5340.3  278.43  5449.5  282.63  5512.3  286.79    5591  289.55  5599.3  290.58
  5605.6   290.1  5634.7  292.33  5705.4  295.45    5720  297.09  5769.9  298.89
#Mann= 3 , 0 , 0
    4464      .1       0  4980.9     .05       0  5011.7      .1       0
#XS Ineff= 2 , 0
       0 4969.72  277.75 5032.17       0  278.37
Permanent Ineff=
       T       T
Bank Sta=4980.9,5011.7
XS Rating Curve= 0 ,0
Exp/Cntr=0.3,0.1

Type RM Length L Ch R = 1 ,1242    ,387,387,387
BEGIN DESCRIPTION:
Mapping XS 8437c95d
END DESCRIPTION:
XS GIS Cut Line= 4
       2228247.9      13225508.3      2228634.19     13225754.73
        2229207.     13225628.18      2229525.58     13225170.21
#Sta/Elev= 30
  4333.6  286.76  4376.2  286.98    4535  284.44  4709.6  278.64  4895.3  273.82
  4928.6  274.78  4979.8  274.86  4992.8  273.57    5000  271.76  5010.5  273.41
    5031  274.91  5184.6  272.59  5362.6   276.7  5402.1   278.5  5458.9  279.57
  5473.7  281.32  5488.5  281.28  5560.1  284.92  5574.9  284.65  5616.8  286.91
  5631.7  286.92  5637.8  288.07  5682.3   289.4  5696.8  290.89  5703.2   290.6
  5709.3  291.52  5818.6  296.71  5840.3   296.6  5876.1  298.65  5936.3  300.32
#Mann= 4 ,-1 , 0
  4333.6      .1       0  4979.8     .05       0    5031      .1       0
  5936.3     .05       0
#XS Ineff= 2 , 0
       0 4978.75  274.98  5032.5       0  274.92
Permanent Ineff=
       T       T
Bank Sta=4992.8,5010.5
XS Rating Curve= 0 ,0
Exp/Cntr=0.3,0.1

Type RM Length L Ch R = 1 ,855     ,631,631,631
BEGIN DESCRIPTION:
Mapping XS 881fe0df
END DESCRIPTION:
XS GIS Cut Line= 4
       2228571.5     13226125.23      2228710.39     13226151.27
      2229352.75     13225838.77      2229586.63     13225531.26
#Sta/Elev= 30
  4728.2  275.38  4819.7  274.63  4899.9  272.31  4954.8  271.93  4988.9  273.15
  4999.9   270.1  5010.9  269.01  5014.1  269.51  5022.2  273.26    5276  270.48
  5522.7  273.33  5596.4  275.73  5617.3  275.21  5623.9  276.36  5660.9  278.35
  5667.2  277.08  5674.2  278.27  5724.5  279.98  5731.6  281.15  5752.4  280.71
  5781.5  283.11  5802.3  282.87  5810.6  284.24  5816.9  283.17  5831.4  284.99
  5852.2  284.64  5860.5  286.11  5881.3  286.17  5887.8  287.62  5970.2  291.25
#Mann= 3 , 0 , 0
  4728.2      .1       0  4988.9     .05       0  5022.2      .1       0
#XS Ineff= 2 , 0
       0 4976.25  273.14 5027.78       0  273.38
Permanent Ineff=
       T       T
Bank Sta=4988.9,5022.2
XS Rating Curve= 0 ,0
Exp/Cntr=0.3,0.1

Type RM Length L Ch R = 1 ,223     ,0,0,0
BEGIN DESCRIPTION:
UNT 015 IN RACR 1.0
END DESCRIPTION:
XS GIS Cut Line= 4
      2228896.98      13226372.6      2229213.86     13226537.55
      2229543.72     13226329.22      2229612.66     13225971.59
#Sta/Elev= 30
    4582  271.12  4616.7  270.64    4623  271.26  4650.7  269.87  4667.2  270.76
  4683.7  270.07  4705.8  270.66  4888.2  268.29  4926.8  268.84  4955.7  268.34
  4979.3  269.33  4986.3  268.92  4992.2  268.39  4998.6   264.9  5001.3   264.4
  5004.6   264.9  5007.5  268.54  5109.4  267.38  5247.5  268.35    5311  267.91
  5326.3  268.45  5377.3  268.51  5392.9  269.33  5464.2  269.42  5525.3  271.01
    5538  270.66  5545.7  271.52  5555.8  271.22  5616.9  272.45  5693.6  274.74
#Mann= 3 ,-1 , 0
    4582     .08       0  4986.3     .05       0  5007.5     .08       0
#XS Ineff= 2 , 0
       0 4980.42  269.35               0
Permanent Ineff=
       T       T
Bank Sta=4992.2,5007.5
XS Rating Curve= 0 ,0
Exp/Cntr=0.3,0.1
Stream Node=UNT 015 IN RACR ,Reach-1         , 0 , 0 ,Upstream end
Stream Node=UNT 015 IN RACR ,Reach-1         , 0 , 1 ,Downstream end

Chan Stop Cuts=-1
Use User Specified Reach Order=0
Composite Channel Slope=5