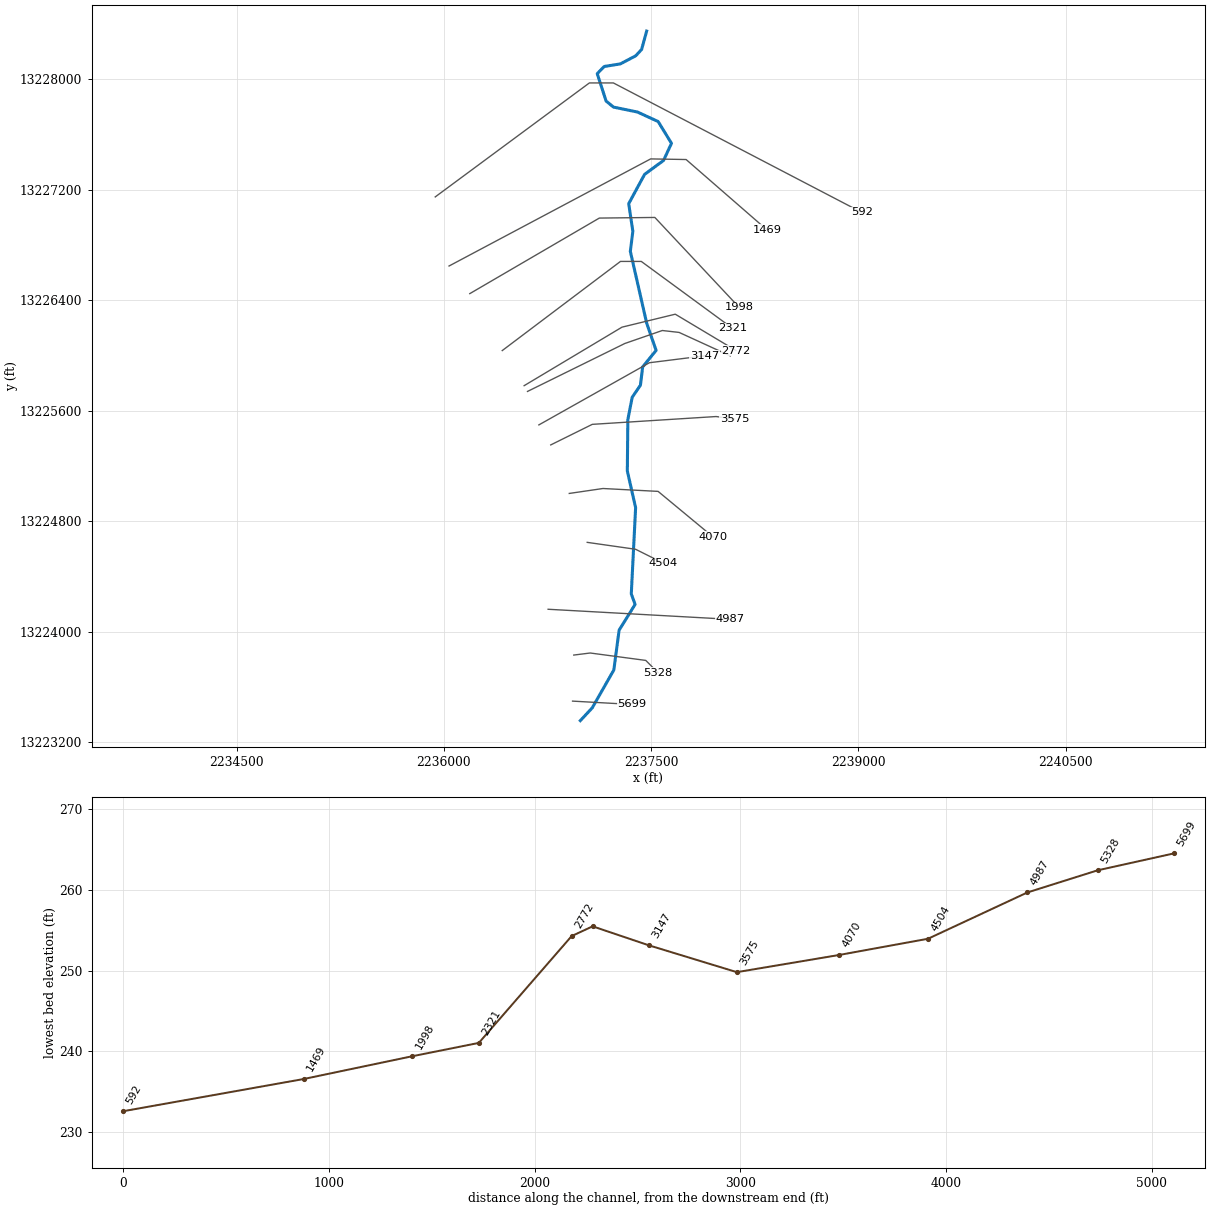
--- UNT 017 IN RACR.prj (project) ---

Proj Title=UNT 017 IN RACR Base Level Engineering
Current Plan=p01
Default Exp/Contr=0.3,0.1
English Units
Geom File=g01
Flow File=f01
Plan File=p01
BEGIN DESCRIPTION:
UNT 017 IN RACR
END DESCRIPTION:

--- UNT 017 IN RACR.p01 (plan) ---

Plan Title=Multiple Run
Short Identifier=Multiple
Geom File=g01
Flow File=f01
Subcritical Flow
K Sum by GR= 0
Std Step Tol= 0.01
Critical Tol= 0.01
Num of Std Step Trials= 20
Max Error Tol= 0.3
Flow Tol Ratio= 0.001
Split Flow NTrial= 30
Split Flow Tol= 0.02
Split Flow Ratio= 0.02
Log Output Level= 0
Friction Slope Method= 1
Unsteady Friction Slope Method= 2
Unsteady Bridges Friction Slope Method= 1
Parabolic Critical Depth
Global Vel Dist=  1 , 1 , 1
Global Log Level= 0
CheckData=True
Encroach Param= -1, 0, 0, 0
BEGIN DESCRIPTION:
Multiple Run
END DESCRIPTION:

--- UNT 017 IN RACR.f01 (steady flow) ---

Flow Title=Multiple
Number of Profiles=7
Profile Names=10-year,25-year,50-year,1pct_min,100-year,1pct_plu,500-year
River Rch & RM= UNT 017 IN RACR,Reach-1,5699
     253     357     446     410     554     750     870
River Rch & RM= UNT 017 IN RACR,Reach-1,4504
     320     455     571     527     713     964    1128
Boundary for River Rch & Prof#=UNT 017 IN RACR,Reach-1,1
Up Type=0
Dn Type=3
Dn Slope=0.005
Boundary for River Rch & Prof#=UNT 017 IN RACR,Reach-1,2
Up Type=0
Dn Type=3
Dn Slope=0.005
Boundary for River Rch & Prof#=UNT 017 IN RACR,Reach-1,3
Up Type=0
Dn Type=3
Dn Slope=0.005
Boundary for River Rch & Prof#=UNT 017 IN RACR,Reach-1,4
Up Type=0
Dn Type=3
Dn Slope=0.005
Boundary for River Rch & Prof#=UNT 017 IN RACR,Reach-1,5
Up Type=0
Dn Type=3
Dn Slope=0.005
Boundary for River Rch & Prof#=UNT 017 IN RACR,Reach-1,6
Up Type=0
Dn Type=3
Dn Slope=0.005
Boundary for River Rch & Prof#=UNT 017 IN RACR,Reach-1,7
Up Type=0
Dn Type=3
Dn Slope=0.005

--- UNT 017 IN RACR.g01 (geometry) ---

Geom Title=Existing Conditions

River Reach=UNT 017 IN RACR,Reach-1
Reach XY= 30
      2236987.72     13223356.85      2237073.92     13223449.02
      2237230.26     13223723.50      2237268.45     13224011.45
      2237384.01     13224197.67      2237356.56     13224274.21
      2237387.87     13224897.64      2237327.92     13225163.27
      2237331.56     13225534.63      2237363.14     13225697.13
      2237422.71     13225784.11      2237438.81     13225916.38
      2237536.08     13226036.41      2237468.02     13226232.93
      2237349.67     13226752.60      2237367.83     13226898.13
      2237337.86     13227097.97      2237452.54     13227309.70
      2237590.03     13227410.85      2237647.42     13227534.75
      2237550.75     13227692.40      2237400.80     13227761.27
      2237227.72     13227796.85      2237174.43     13227840.48
      2237109.94     13228038.86      2237160.55     13228090.76
      2237276.75     13228109.20      2237388.42     13228167.82
      2237431.19     13228213.85      2237467.72     13228346.85

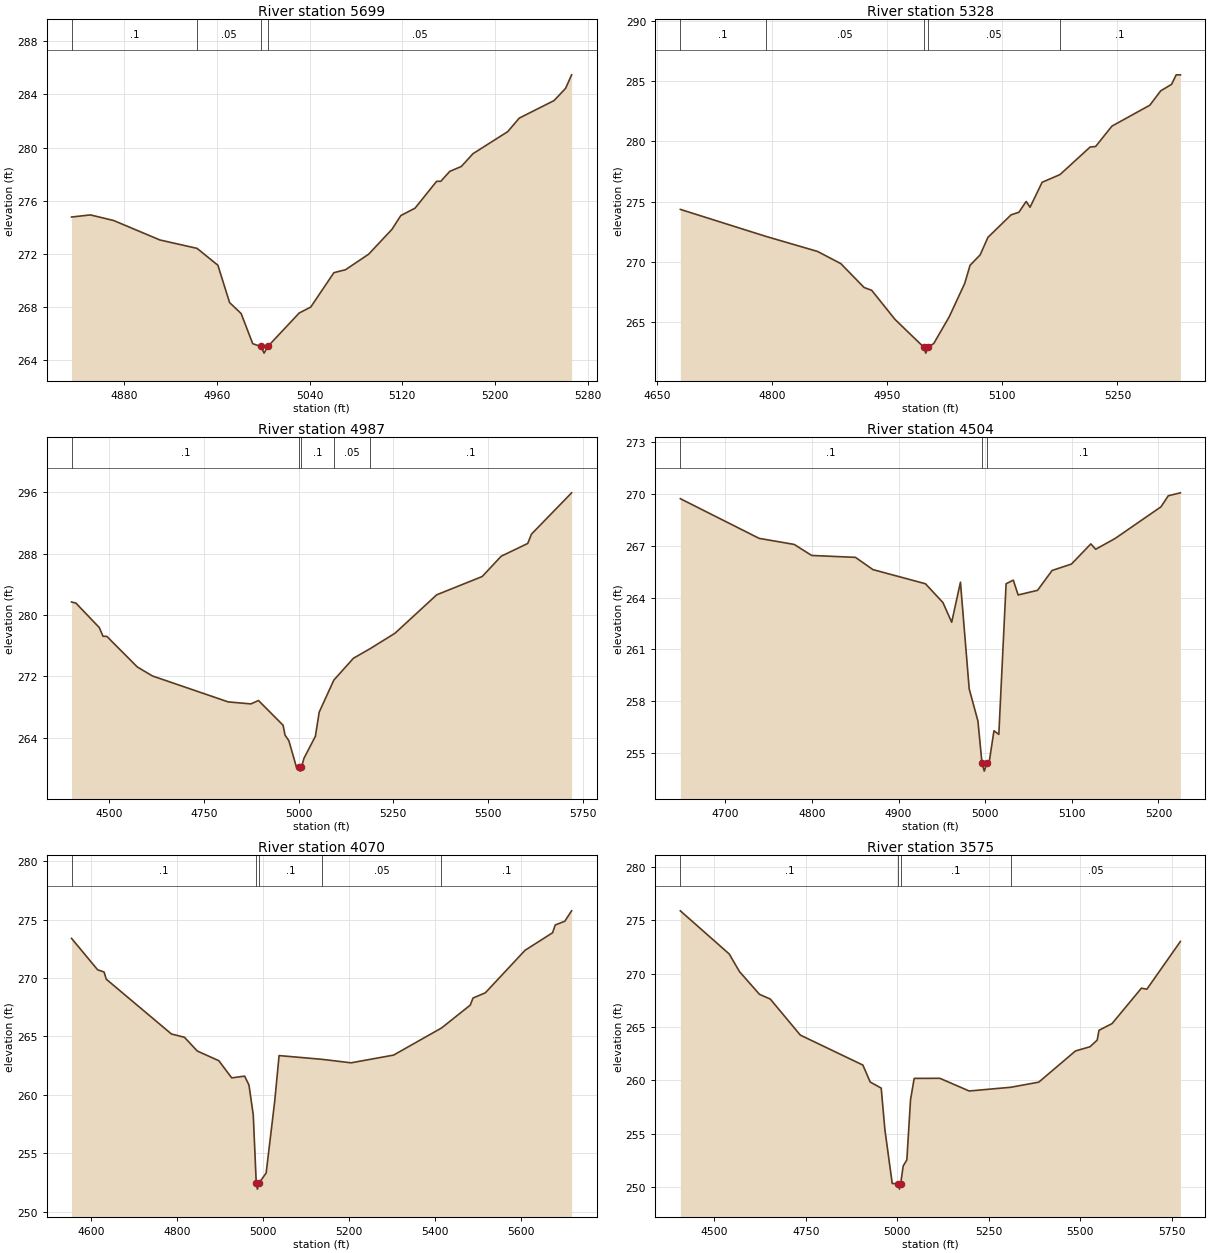
Type RM Length L Ch R = 1,5699,371,371,371
BEGIN DESCRIPTION:
UNT 017 IN RACR 12.0
END DESCRIPTION:
XS GIS Cut Line= 3
      2236931.47     13223497.93      2237249.90     13223480.07
      2237362.87     13223480.07
#Sta/Elev= 30
  4834.3  274.77  4850.6  274.93  4870.6  274.51  4910.7  273.04  4942.7  272.41
  4960.7  271.14  4970.8  268.33  4980.8  267.50  4990.8  265.23  4997.8  265.02
  5000.6  264.52  5003.8  265.02  5030.9  267.54  5040.9  267.99  5060.9  270.58
  5070.9  270.80  5090.9  271.97  5111.0  273.84  5118.7  274.88  5131.0  275.44
  5149.6  277.46  5153.2  277.46  5161.0  278.21  5171.0  278.58  5181.0  279.54
  5211.0  281.20  5221.0  282.22  5251.0  283.54  5261.0  284.46  5266.2  285.48
#Mann=4,-1,0
  4834.3     0.1       0  4942.7    0.05       0  4997.8   0.035       0
  5003.8    0.05       0
Bank Sta=4997.8,5003.8
Exp/Cntr=0.3,0.1

Type RM Length L Ch R = 1,5328,341,341,341
BEGIN DESCRIPTION:
UNT 017 IN RACR 11.0
END DESCRIPTION:
XS GIS Cut Line= 4
      2236940.34     13223831.26      2237059.42     13223846.14
      2237461.21     13223792.57      2237550.48     13223703.30
#Sta/Elev= 30
  4680.5  274.35  4791.5  272.12  4859.3  270.86  4889.6  269.85  4919.9  267.87
  4929.9  267.63  4960.2  265.22  4997.6  262.92  5000.3  262.42  5003.6  262.92
  5010.7  263.22  5030.8  265.43  5051.0  268.20  5058.0  269.71  5071.2  270.58
  5081.3  272.03  5111.5  273.90  5121.6  274.11  5131.1  275.01  5136.2  274.53
  5151.9  276.60  5175.2  277.24  5214.5  279.53  5221.6  279.57  5242.8  281.26
  5292.3  283.00  5306.4  284.19  5320.6  284.73  5326.6  285.52  5332.1  285.52
#Mann=5,-1,0
  4680.5     0.1       0  4791.5    0.05       0  4997.6   0.035       0
  5003.6    0.05       0  5175.2     0.1       0
Bank Sta=4997.6,5003.6
Exp/Cntr=0.3,0.1

Type RM Length L Ch R = 1,4987,483,483,483
BEGIN DESCRIPTION:
UNT 017 IN RACR 10.0
END DESCRIPTION:
XS GIS Cut Line= 2
      2236754.63     13224162.68      2238073.42     13224089.80
#Sta/Elev= 30
  4400.1  281.69  4411.6  281.55  4473.3  278.37  4483.3  277.23  4493.3  277.22
  4573.5  273.25  4613.5  272.07  4813.8  268.69  4873.9  268.43  4893.9  268.87
  4958.9  265.65  4964.0  264.37  4974.1  263.64  4994.1  260.21  5001.1  260.18
  5003.9  259.68  5007.1  260.18  5014.1  261.36  5044.2  264.22  5054.2  267.35
  5092.8  271.52  5144.6  274.37  5188.5  275.61  5254.5  277.63  5364.7  282.63
  5484.8  285.01  5534.9  287.65  5605.0  289.31  5615.0  290.53  5720.9  295.90
#Mann=5,-1,0
  4400.1     0.1       0  5001.1    0.07       0  5007.1     0.1       0
  5092.8    0.05       0  5188.5     0.1       0
Bank Sta=5001.1,5007.1
Exp/Cntr=0.3,0.1

Type RM Length L Ch R = 1,4504,434,434,434
BEGIN DESCRIPTION:
UNT 017 IN RACR 9.0
END DESCRIPTION:
XS GIS Cut Line= 3
      2237037.68     13224646.86      2237387.72     13224596.85
      2237587.72     13224496.86
#Sta/Elev= 30
  4648.1  269.73  4739.1  267.43  4779.5  267.08  4799.7  266.44  4850.2  266.33
  4870.4  265.62  4931.0  264.80  4951.2  263.71  4961.3  262.57  4971.4  264.89
  4981.5  258.71  4991.6  256.84  4996.2  254.44  4998.9  253.94  5002.2  254.44
  5004.5  254.44  5010.1  256.28  5015.7  256.07  5024.1  264.80  5032.4  265.01
  5038.0  264.15  5060.4  264.42  5077.2  265.57  5099.5  265.94  5121.9  267.11
  5127.5  266.80  5149.8  267.42  5202.9  269.26  5211.3  269.90  5225.3  270.07
#Mann=3,-1,0
  4648.1     0.1       0  4996.2    0.07       0  5002.2     0.1       0
Bank Sta=4996.2,5002.2
Exp/Cntr=0.3,0.1

Type RM Length L Ch R = 1,4070,495,495,495
BEGIN DESCRIPTION:
UNT 017 IN RACR 8.0
END DESCRIPTION:
XS GIS Cut Line= 4
      2236907.68     13225000.91      2237151.68     13225036.62
      2237550.49     13225015.78      2237949.29     13224685.44
#Sta/Elev= 30
  4553.7  273.40  4614.4  270.71  4629.4  270.52  4634.6  269.90  4786.2  265.21
  4816.4  264.93  4846.4  263.75  4896.5  262.92  4926.5  261.45  4956.5  261.60
  4966.6  260.84  4976.6  258.29  4983.6  252.42  4986.3  251.92  4989.6  252.42
  5006.6  253.30  5026.6  259.47  5036.7  263.36  5136.4  263.04  5204.2  262.74
  5303.1  263.40  5414.6  265.72  5481.6  267.68  5488.1  268.29  5516.8  268.74
  5609.2  272.38  5673.1  273.88  5679.5  274.55  5701.7  274.87  5717.5  275.76
#Mann=5,-1,0
  4553.7     0.1       0  4983.6    0.07       0  4989.6     0.1       0
  5136.4    0.05       0  5414.6     0.1       0
Bank Sta=4983.6,4989.6
Exp/Cntr=0.3,0.1

Type RM Length L Ch R = 1,3575,428,428,428
BEGIN DESCRIPTION:
UNT 017 IN RACR 7.0
END DESCRIPTION:
XS GIS Cut Line= 4
      2236773.66     13225352.07      2237074.30     13225500.90
      2237970.13     13225557.45      2238103.38     13225539.69
#Sta/Elev= 30
  4406.7  275.89  4540.5  271.84  4568.5  270.19  4623.2  268.06  4652.6  267.62
  4734.8  264.24  4905.9  261.43  4925.9  259.84  4956.0  259.27  4966.0  255.39
  4986.1  250.33  5003.1  250.30  5005.9  249.80  5009.1  250.30  5016.1  251.97
  5026.1  252.54  5036.2  258.19  5046.2  260.18  5116.3  260.19  5196.5  259.00
  5310.7  259.35  5386.9  259.83  5487.1  262.75  5527.1  263.15  5546.6  263.77
  5551.6  264.69  5587.3  265.32  5667.6  268.64  5682.4  268.54  5774.2  273.02
#Mann=4,-1,0
  4406.7     0.1       0  5003.1    0.07       0  5009.1     0.1       0
  5310.7    0.05       0
Bank Sta=5003.1,5009.1
Exp/Cntr=0.3,0.1

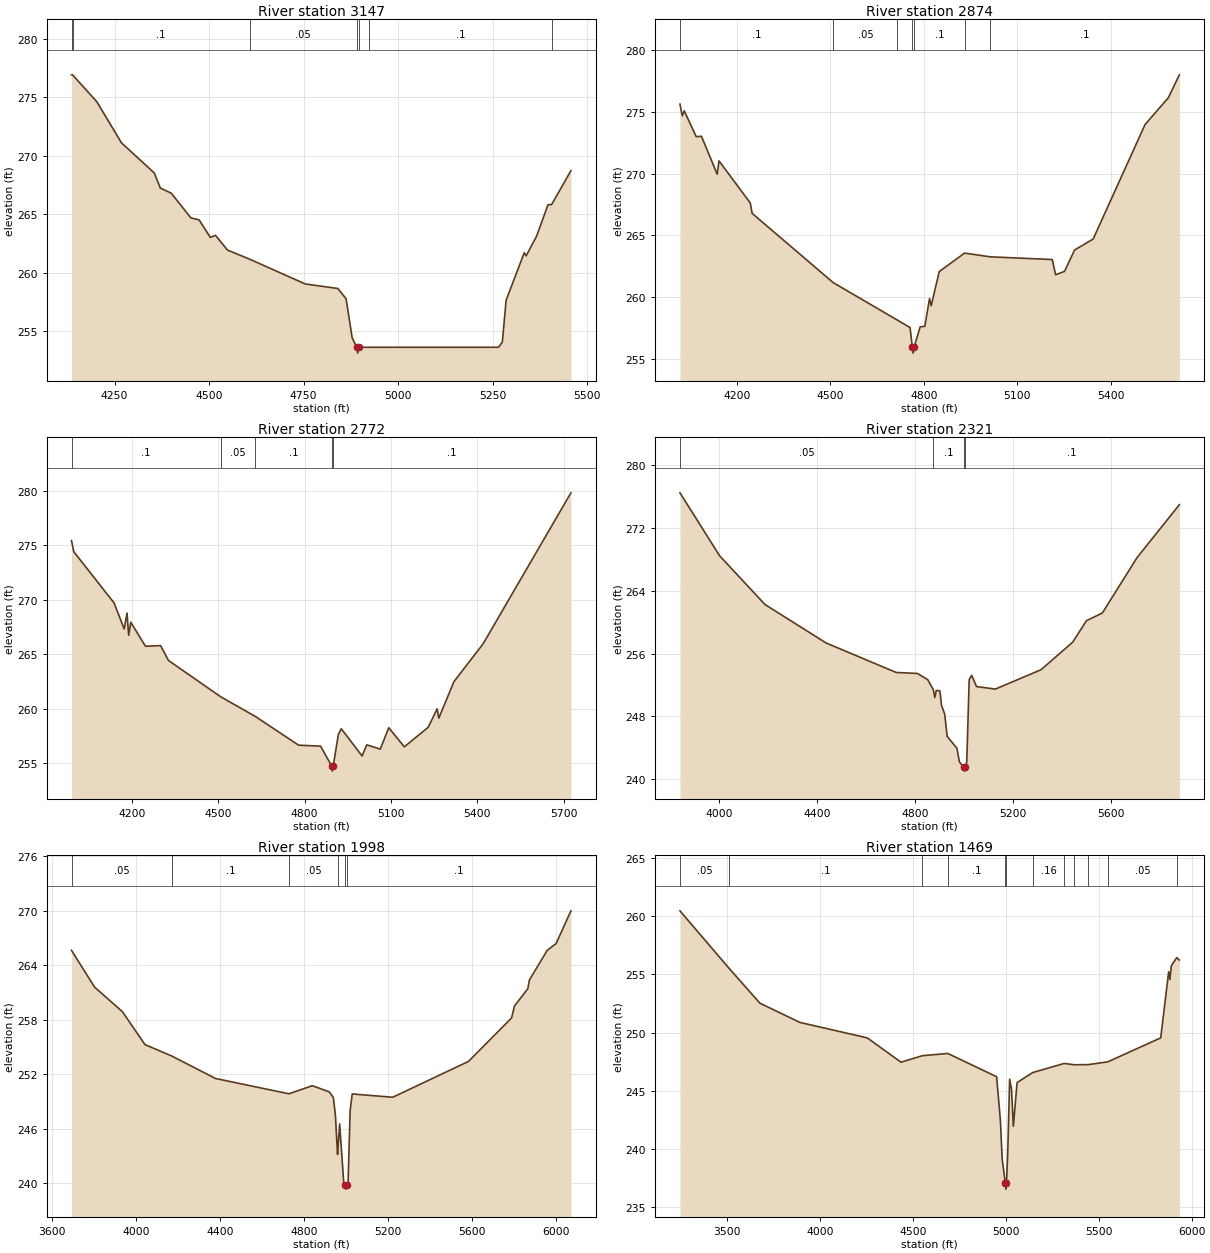
Type RM Length L Ch R = 1,3147,273,273,273
BEGIN DESCRIPTION:
UNT 017 IN RACR 6.0
END DESCRIPTION:
XS GIS Cut Line= 3
      2236687.74     13225496.87      2237487.72     13225946.85
      2237887.75     13225996.86
#Sta/Elev= 30
  4136.1  276.90  4138.9  276.90  4203.3  274.59  4268.3  271.09  4355.0  268.52
  4371.0  267.23  4400.0  266.79  4451.9  264.68  4473.6  264.51  4503.2  263.02
  4516.9  263.19  4548.8  261.93  4607.6  261.15  4754.0  259.04  4840.7  258.65
  4862.4  257.77  4878.3  254.47  4890.3  253.63  4893.1  253.13  4896.3  253.63
  4923.0  253.63  5265.6  253.63  5275.7  254.08  5285.7  257.65  5333.6  261.70
  5338.7  261.44  5366.4  263.13  5396.6  265.81  5405.8  265.81  5457.1  268.71
#Mann=7,-1,0
  4136.1    0.05       0  4138.9     0.1       0  4607.6    0.05       0
  4890.3    0.07       0  4896.3    0.05       0  4923.0     0.1       0
  5405.8    0.05       0
Bank Sta=4890.3,4896.3
Exp/Cntr=0.3,0.1

Type RM Length L Ch R = 1,2874,102,102,102
BEGIN DESCRIPTION:
Mapping XS b07ff1fa
END DESCRIPTION:
XS GIS Cut Line= 5
      2236605.40     13225739.08      2237310.23     13226086.29
      2237581.06     13226180.04      2237702.59     13226166.15
      2238073.43     13225996.32
#Sta/Elev= 30
  4017.2  275.62  4024.4  274.68  4030.9  275.08  4069.3  272.99  4086.2  273.02
  4136.7  269.95  4142.4  271.03  4242.7  267.63  4249.0  266.78  4509.2  261.18
  4715.0  258.15  4755.5  257.55  4762.7  255.98  4765.4  255.48  4768.7  255.98
  4788.1  257.61  4802.9  257.65  4818.0  259.89  4823.3  259.31  4849.2  262.08
  4930.5  263.57  5012.7  263.27  5211.8  263.05  5222.6  261.82  5251.1  262.09
  5283.5  263.82  5343.1  264.71  5509.6  273.97  5584.2  276.13  5619.7  277.99
#Mann=7,-1,0
  4017.2     0.1       0  4509.2    0.05       0  4715.0     0.1       0
  4762.7    0.03       0  4768.7     0.1       0  4930.5    0.05       0
  5012.7     0.1       0
Bank Sta=4762.7,4768.7
Exp/Cntr=0.3,0.1

Type RM Length L Ch R = 1,2772,451,451,451
BEGIN DESCRIPTION:
UNT 017 IN RACR 5.0
END DESCRIPTION:
XS GIS Cut Line= 4
      2236581.07     13225780.74      2237289.39     13226204.34
      2237674.81     13226298.09      2238114.26     13226035.12
#Sta/Elev= 30
  3990.6  275.41  3998.5  274.39  4138.2  269.70  4173.5  267.31  4183.3  268.77
  4189.1  266.73  4196.4  267.92  4247.5  265.72  4300.0  265.78  4327.2  264.42
  4509.2  261.08  4629.2  259.28  4779.0  256.65  4855.4  256.56  4893.5  254.77
  4896.3  254.27  4899.5  254.77  4917.1  257.62  4927.3  258.16  4999.5  255.66
  5015.9  256.68  5062.8  256.29  5092.1  258.25  5146.3  256.50  5229.1  258.29
  5260.2  259.98  5266.0  259.13  5318.6  262.48  5419.7  265.94  5724.7  279.79
#Mann=5,-1,0
  3990.6     0.1       0  4509.2    0.05       0  4629.2     0.1       0
  4893.5    0.07       0  4899.5     0.1       0
Bank Sta=4893.5,4899.5
Exp/Cntr=0.3,0.1

Type RM Length L Ch R = 1,2321,323,323,323
BEGIN DESCRIPTION:
UNT 017 IN RACR 4.0
END DESCRIPTION:
XS GIS Cut Line= 4
      2236422.69     13226034.82      2237278.33     13226680.04
      2237428.84     13226680.04      2238087.71     13226196.86
#Sta/Elev= 30
  3840.9  276.51  4002.9  268.48  4188.2  262.27  4438.0  257.36  4723.9  253.61
  4810.6  253.48  4852.3  252.70  4875.6  251.40  4881.4  250.41  4887.7  251.32
  4902.2  251.26  4909.0  249.42  4921.9  248.29  4931.9  245.47  4971.9  243.94
  4981.9  242.22  4998.9  241.53  5001.7  241.03  5004.9  241.53  5011.9  242.17
  5021.9  252.69  5031.9  253.24  5051.9  251.81  5128.7  251.49  5314.8  253.95
  5444.4  257.47  5500.8  260.21  5565.6  261.19  5707.6  268.26  5880.1  275.00
#Mann=4,-1,0
  3840.9    0.05       0  4875.6     0.1       0  4998.9    0.07       0
  5004.9     0.1       0
Bank Sta=4998.9,5004.9
Exp/Cntr=0.3,0.1

Type RM Length L Ch R = 1,1998,529,529,529
BEGIN DESCRIPTION:
UNT 017 IN RACR 3.0
END DESCRIPTION:
XS GIS Cut Line= 4
      2236187.75     13226446.87      2237125.11     13226993.67
      2237527.05     13226998.24      2238137.71     13226346.87
#Sta/Elev= 30
  3691.5  265.65  3801.0  261.62  3934.2  258.90  4041.7  255.28  4168.9  254.03
  4378.2  251.55  4727.4  249.87  4839.3  250.76  4919.3  250.09  4939.3  249.47
  4949.3  247.47  4959.3  243.20  4962.6  244.31  4969.3  246.55  4989.3  239.96
  4996.3  239.88  4999.1  239.38  5002.3  239.88  5009.3  239.94  5019.3  248.00
  5029.3  249.85  5222.3  249.49  5583.3  253.43  5788.5  258.21  5802.6  259.53
  5866.1  261.43  5873.4  262.38  5958.4  265.65  6000.9  266.40  6071.5  270.00
#Mann=6,-1,0
  3691.5    0.05       0  4168.9     0.1       0  4727.4    0.05       0
  4962.6     0.1       0  4996.3    0.07       0  5002.3     0.1       0
Bank Sta=4996.3,5002.3
Exp/Cntr=0.3,0.1

Type RM Length L Ch R = 1,1469,877,877,877
BEGIN DESCRIPTION:
UNT 017 IN RACR 2.0
END DESCRIPTION:
XS GIS Cut Line= 4
      2236037.76     13226646.88      2237496.62     13227421.89
      2237753.31     13227417.39      2238339.75     13226907.16
#Sta/Elev= 30
  3248.2  260.47  3513.9  255.50  3678.4  252.53  3893.1  250.88  4255.4  249.55
  4437.1  247.46  4552.6  248.02  4688.8  248.21  4951.3  246.21  4971.3  242.52
  4981.3  239.11  4998.3  237.05  5001.0  236.55  5004.3  237.05  5011.3  239.77
  5021.3  246.00  5031.3  245.16  5041.3  241.95  5061.3  245.71  5145.7  246.57
  5313.9  247.35  5369.3  247.24  5444.2  247.25  5549.4  247.49  5833.9  249.55
  5876.6  255.24  5883.2  254.56  5890.9  255.75  5920.4  256.45  5934.2  256.24
#Mann=12,-1,0
  3248.2    0.05       0  3513.9     0.1       0  4552.6    0.05       0
  4688.8     0.1       0  4998.3    0.07       0  5004.3     0.1       0
  5145.7    0.16       0  5313.9     0.1       0  5369.3    0.16       0
  5444.2     0.1       0  5549.4    0.05       0  5920.4     0.1       0
Bank Sta=4998.3,5004.3
Exp/Cntr=0.3,0.1

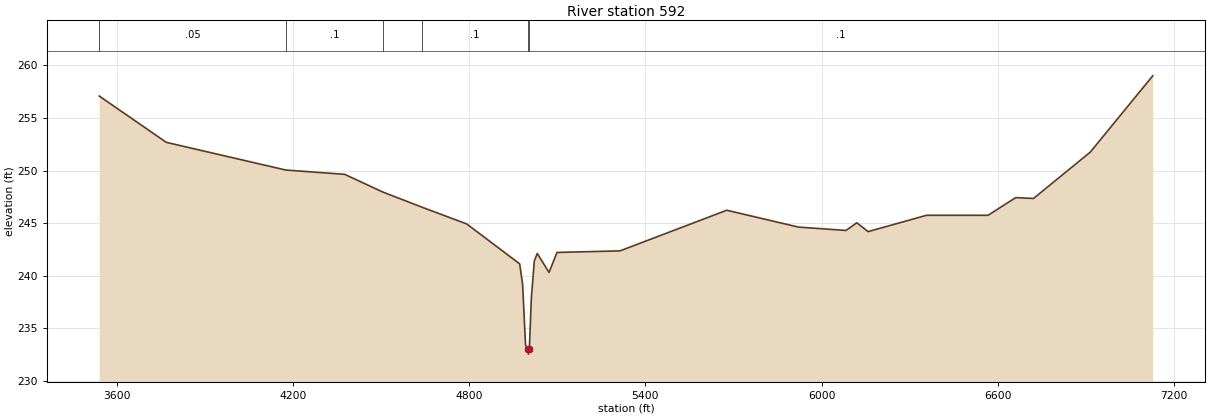
Type RM Length L Ch R = 1,592,0,0,0
BEGIN DESCRIPTION:
UNT 017 IN RACR 1.0
END DESCRIPTION:
XS GIS Cut Line= 4
      2235937.75     13227146.88      2237053.28     13227971.70
      2237226.89     13227971.70      2239024.14     13227034.91
#Sta/Elev= 30
  3540.2  257.08  3768.7  252.68  4175.4  250.05  4376.2  249.64  4505.9  247.96
  4640.2  246.51  4791.6  244.93  4972.0  241.14  4982.0  239.20  4992.0  233.44
  4999.0  233.06  5001.7  232.56  5005.0  233.06  5012.0  237.99  5022.0  241.42
  5032.0  242.12  5072.0  240.32  5099.1  242.22  5313.9  242.37  5677.2  246.23
  5921.3  244.63  6083.2  244.31  6120.2  245.04  6158.7  244.20  6357.6  245.75
  6567.2  245.75  6661.2  247.43  6721.9  247.35  6915.1  251.75  7127.9  259.00
#Mann=6,-1,0
  3540.2    0.05       0  4175.4     0.1       0  4505.9    0.05       0
  4640.2     0.1       0  4999.0    0.07       0  5005.0     0.1       0
Bank Sta=4999,5005
Exp/Cntr=0.3,0.1

Chan Stop Cuts=-1