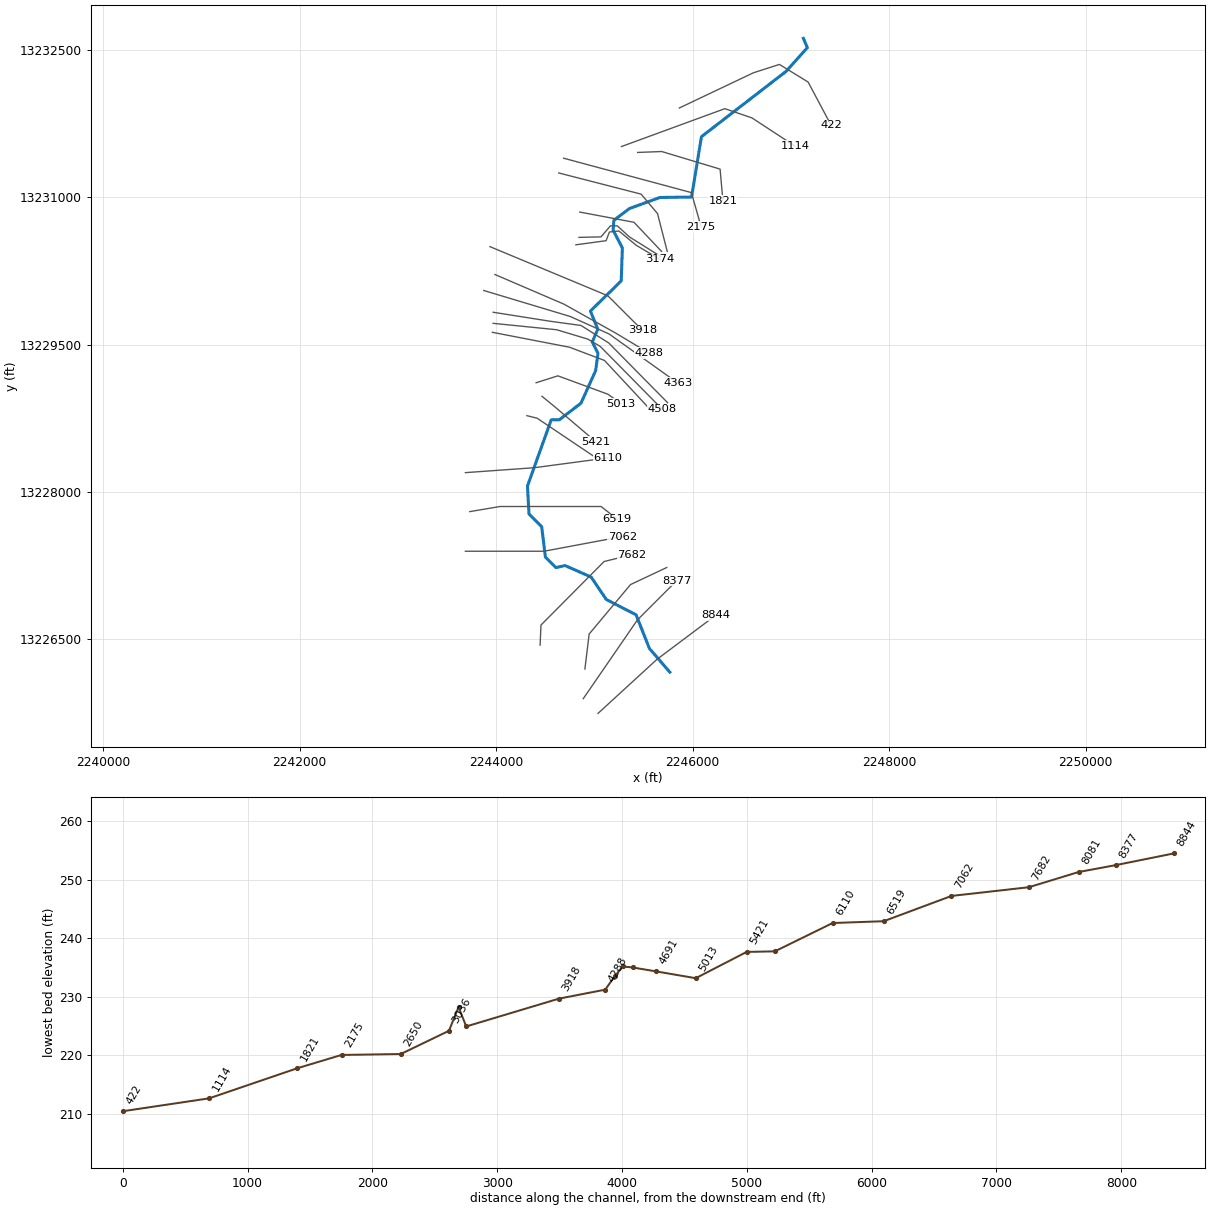
--- UNT 018 IN RACR.prj (project) ---

Proj Title=UNT 018 IN RACR Base Level Engineering
Current Plan=p01
Default Exp/Contr=0.3,0.1
English Units
Geom File=g01
Flow File=f01
Plan File=p01
BEGIN DESCRIPTION:
UNT 018 IN RACR
END DESCRIPTION:

--- UNT 018 IN RACR.p01 (plan) ---

Plan Title=Multiple Run
Short Identifier=Multiple
Geom File=g01
Flow File=f01
Subcritical Flow
K Sum by GR= 0
Std Step Tol= 0.01
Critical Tol= 0.01
Num of Std Step Trials= 20
Max Error Tol= 0.3
Flow Tol Ratio= 0.001
Split Flow NTrial= 30
Split Flow Tol= 0.02
Split Flow Ratio= 0.02
Log Output Level= 0
Friction Slope Method= 1
Unsteady Friction Slope Method= 2
Unsteady Bridges Friction Slope Method= 1
Parabolic Critical Depth
Global Vel Dist=  1 , 1 , 1
Global Log Level= 0
CheckData=True
Encroach Param= -1, 0, 0, 0
BEGIN DESCRIPTION:
Multiple Run
END DESCRIPTION:

--- UNT 018 IN RACR.f01 (steady flow) ---

Flow Title=Multiple
Number of Profiles=7
Profile Names=10-year,25-year,50-year,1pct_min,100-year,1pct_plu,500-year
River Rch & RM= UNT 018 IN RACR,Reach-1,8844
     220     304     375     340     460     622     704
River Rch & RM= UNT 018 IN RACR,Reach-1,7062
     382     545     684     632     854    1155    1352
River Rch & RM= UNT 018 IN RACR,Reach-1,4429
     423     605     760     701     949    1283    1503
Boundary for River Rch & Prof#=UNT 018 IN RACR,Reach-1,1
Up Type=0
Dn Type=3
Dn Slope=0.005
Boundary for River Rch & Prof#=UNT 018 IN RACR,Reach-1,2
Up Type=0
Dn Type=3
Dn Slope=0.005
Boundary for River Rch & Prof#=UNT 018 IN RACR,Reach-1,3
Up Type=0
Dn Type=3
Dn Slope=0.005
Boundary for River Rch & Prof#=UNT 018 IN RACR,Reach-1,4
Up Type=0
Dn Type=3
Dn Slope=0.005
Boundary for River Rch & Prof#=UNT 018 IN RACR,Reach-1,5
Up Type=0
Dn Type=3
Dn Slope=0.005
Boundary for River Rch & Prof#=UNT 018 IN RACR,Reach-1,6
Up Type=0
Dn Type=3
Dn Slope=0.005
Boundary for River Rch & Prof#=UNT 018 IN RACR,Reach-1,7
Up Type=0
Dn Type=3
Dn Slope=0.005

--- UNT 018 IN RACR.g01 (geometry) ---

Geom Title=Existing Conditions

River Reach=UNT 018 IN RACR,Reach-1
Reach XY= 30
      2245767.72     13226166.85      2245560.26     13226407.91
      2245424.82     13226750.32      2245122.30     13226905.44
      2244966.79     13227134.68      2244701.18     13227251.62
      2244609.32     13227229.95      2244501.88     13227337.69
      2244464.38     13227645.39      2244334.90     13227777.32
      2244319.78     13228061.10      2244561.29     13228734.74
      2244644.03     13228735.20      2244864.13     13228903.51
      2245013.55     13229235.65      2245037.15     13229411.50
      2244978.71     13229526.36      2245035.42     13229656.49
      2244960.22     13229841.33      2245273.59     13230148.24
      2245285.47     13230484.66      2245191.37     13230663.48
      2245198.31     13230764.17      2245358.04     13230885.00
      2245667.24     13230997.15      2245989.58     13231001.96
      2246090.09     13231615.79      2246952.17     13232281.10
      2247167.97     13232522.01      2247127.72     13232616.85

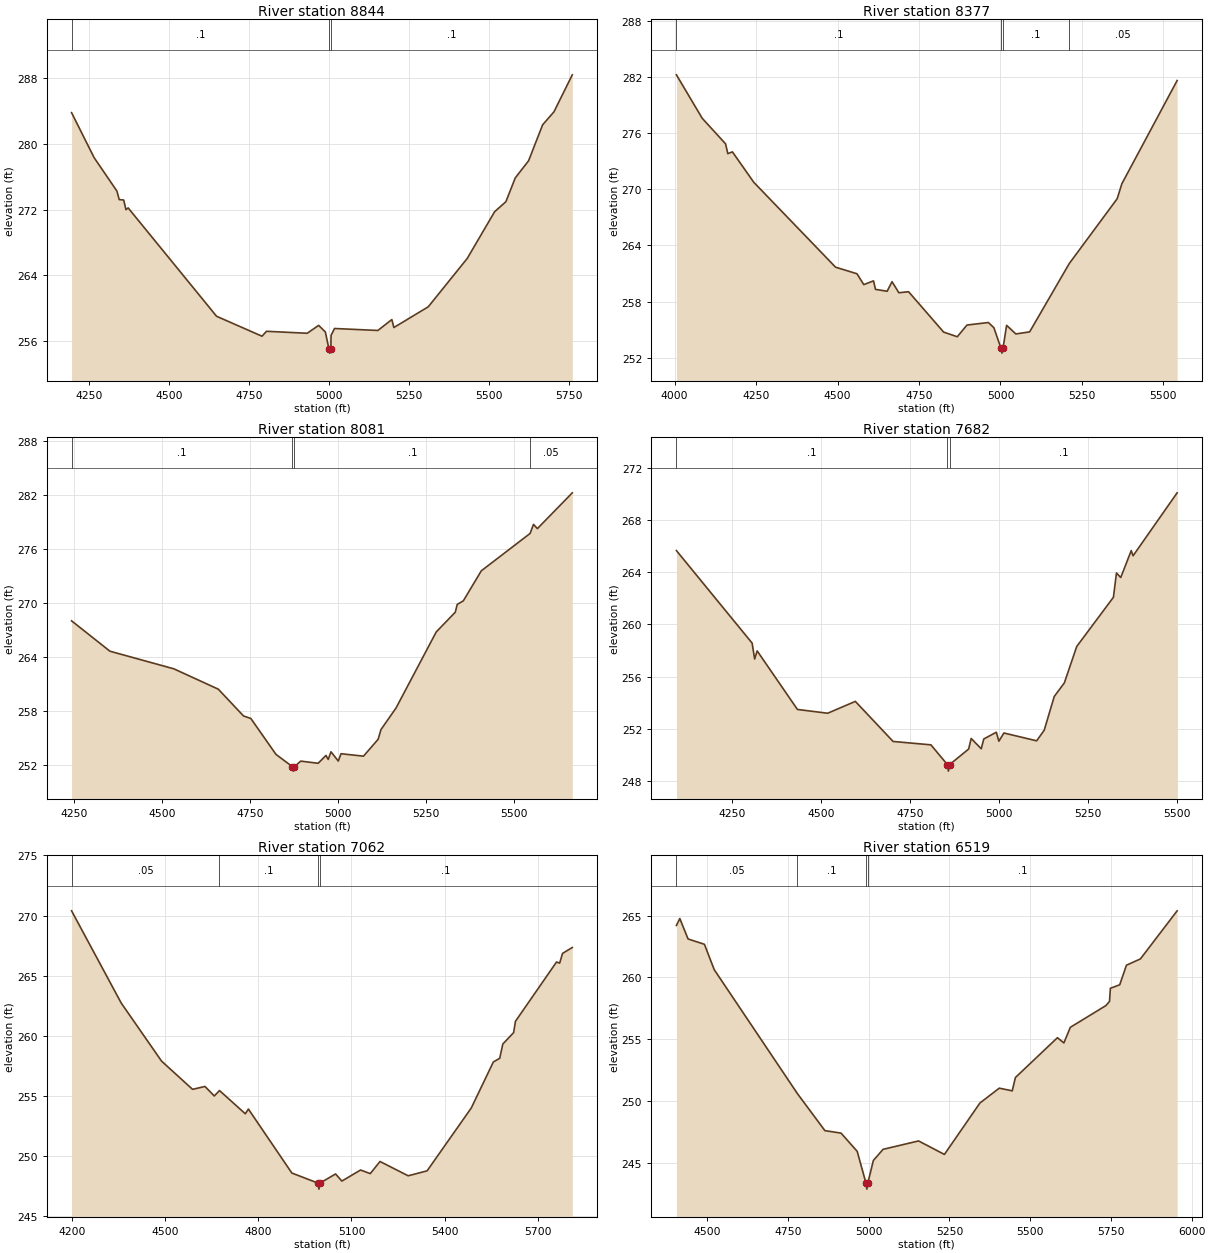
Type RM Length L Ch R = 1,8844,467,467,467
BEGIN DESCRIPTION:
UNT 018 IN RACR 18.0
END DESCRIPTION:
XS GIS Cut Line= 3
      2245037.71     13225746.84      2245637.72     13226296.85
      2246237.75     13226746.88
#Sta/Elev= 30
  4195.4  283.80  4266.0  278.31  4336.9  274.26  4344.3  273.21  4358.2  273.16
  4365.3  271.98  4372.1  272.20  4648.3  259.00  4790.2  256.57  4804.3  257.17
  4931.4  256.93  4967.1  257.89  4988.1  257.09  4999.3  255.01  5002.0  254.51
  5005.3  255.01  5006.0  256.68  5016.7  257.51  5152.1  257.27  5195.8  258.60
  5202.1  257.63  5309.4  260.15  5431.2  266.04  5516.7  271.73  5552.1  272.96
  5581.2  275.85  5622.9  277.94  5666.7  282.32  5702.1  283.90  5759.4  288.41
#Mann=3,-1,0
  4195.4     0.1       0  4999.3    0.07       0  5005.3     0.1       0
Bank Sta=4999.3,5005.3
Exp/Cntr=0.3,0.1

Type RM Length L Ch R = 1,8377,296,296,296
BEGIN DESCRIPTION:
UNT 018 IN RACR 17.0
END DESCRIPTION:
XS GIS Cut Line= 3
      2244887.75     13225896.89      2245437.72     13226696.85
      2245837.75     13227096.88
#Sta/Elev= 30
  4005.7  282.23  4084.8  277.59  4156.5  274.86  4163.4  273.81  4177.5  274.00
  4243.1  270.75  4494.1  261.68  4559.7  260.98  4580.7  259.82  4610.5  260.22
  4616.6  259.31  4652.4  259.11  4667.3  260.13  4688.3  258.95  4718.1  259.06
  4825.6  254.75  4867.5  254.25  4897.3  255.50  4963.0  255.77  4980.0  255.21
  5001.8  253.00  5004.5  252.50  5007.8  253.00  5018.9  255.47  5047.2  254.55
  5089.6  254.77  5211.0  262.06  5358.3  269.00  5372.5  270.59  5542.2  281.62
#Mann=4,-1,0
  4005.7     0.1       0  5001.8    0.07       0  5007.8     0.1       0
  5211.0    0.05       0
Bank Sta=5001.8,5007.8
Exp/Cntr=0.3,0.1

Type RM Length L Ch R = 1,8081,399,399,399
BEGIN DESCRIPTION:
UNT 018 IN RACR 16.0
END DESCRIPTION:
XS GIS Cut Line= 4
      2244904.09     13226198.54      2244947.49     13226554.48
      2245368.50     13227057.95      2245737.42     13227231.56
#Sta/Elev= 30
  4243.2  268.00  4352.3  264.63  4533.6  262.68  4660.1  260.42  4731.7  257.45
  4752.5  257.17  4824.1  253.18  4870.5  251.83  4873.3  251.33  4876.5  251.83
  4894.3  252.44  4943.8  252.20  4965.9  253.07  4972.4  252.63  4980.2  253.47
  5001.0  252.45  5008.8  253.26  5072.6  252.99  5114.3  254.87  5122.1  255.93
  5165.0  258.33  5279.3  266.77  5333.4  268.96  5338.9  269.82  5356.2  270.22
  5407.3  273.55  5545.8  277.69  5555.6  278.70  5566.7  278.23  5665.8  282.20
#Mann=4,-1,0
  4243.2     0.1       0  4870.5    0.07       0  4876.5     0.1       0
  5545.8    0.05       0
Bank Sta=4870.5,4876.5
Exp/Cntr=0.3,0.1

Type RM Length L Ch R = 1,7682,620,620,620
BEGIN DESCRIPTION:
UNT 018 IN RACR 15.0
END DESCRIPTION:
XS GIS Cut Line= 4
      2244448.36     13226441.58      2244457.04     13226645.62
      2245099.40     13227292.32      2245381.55     13227361.77
#Sta/Elev= 30
  4094.7  265.68  4307.3  258.57  4314.4  257.35  4321.5  257.97  4434.6  253.47
  4519.5  253.18  4597.2  254.09  4703.3  251.01  4809.4  250.75  4855.9  249.23
  4858.6  248.73  4861.9  249.23  4915.5  250.43  4922.5  251.24  4950.8  250.45
  4957.9  251.20  4993.2  251.72  5000.3  251.03  5014.5  251.66  5106.4  251.06
  5127.6  251.87  5155.9  254.47  5184.2  255.51  5219.0  258.31  5322.0  262.09
  5330.6  263.96  5342.6  263.61  5372.1  265.68  5377.2  265.28  5501.0  270.12
#Mann=3,-1,0
  4094.7     0.1       0  4855.9    0.07       0  4861.9     0.1       0
Bank Sta=4855.9,4861.9
Exp/Cntr=0.3,0.1

Type RM Length L Ch R = 1,7062,543,543,543
BEGIN DESCRIPTION:
UNT 018 IN RACR 14.0
END DESCRIPTION:
XS GIS Cut Line= 3
      2243687.68     13227396.85      2244487.72     13227396.85
      2245287.74     13227546.86
#Sta/Elev= 30
  4197.9  270.39  4357.9  262.72  4487.9  257.89  4587.9  255.54  4627.9  255.78
  4657.9  254.99  4674.7  255.44  4757.9  253.51  4767.9  253.90  4907.9  248.58
  4992.4  247.74  4995.2  247.24  4998.4  247.74  5048.8  248.50  5069.2  247.91
  5129.4  248.83  5160.7  248.53  5192.1  249.54  5282.8  248.35  5343.9  248.76
  5486.3  253.99  5557.5  257.82  5577.9  258.12  5588.0  259.31  5622.8  260.26
  5628.7  261.20  5761.0  266.13  5771.2  266.04  5780.5  266.85  5811.9  267.34
#Mann=4,-1,0
  4197.9    0.05       0  4674.7     0.1       0  4992.4    0.07       0
  4998.4     0.1       0
Bank Sta=4992.4,4998.4
Exp/Cntr=0.3,0.1

Type RM Length L Ch R = 1,6519,409,409,409
BEGIN DESCRIPTION:
UNT 018 IN RACR 13.0
END DESCRIPTION:
XS GIS Cut Line= 4
      2243732.25     13227800.14      2244040.37     13227852.22
      2245069.02     13227852.22      2245233.34     13227722.49
#Sta/Elev= 30
  4404.6  264.20  4415.1  264.76  4440.6  263.11  4491.3  262.68  4521.7  260.63
  4779.5  250.62  4864.4  247.64  4914.4  247.44  4964.4  245.97  4991.4  243.42
  4994.2  242.92  4997.4  243.42  5014.4  245.23  5044.4  246.13  5154.4  246.81
  5234.4  245.72  5344.4  249.87  5404.4  251.07  5444.4  250.85  5454.4  251.93
  5584.4  255.14  5604.4  254.72  5624.4  255.98  5734.4  257.73  5745.7  258.07
  5748.4  259.13  5777.3  259.41  5798.1  260.99  5841.4  261.50  5955.1  265.38
#Mann=4,-1,0
  4404.6    0.05       0  4779.5     0.1       0  4991.4    0.07       0
  4997.4     0.1       0
Bank Sta=4991.4,4997.4
Exp/Cntr=0.3,0.1

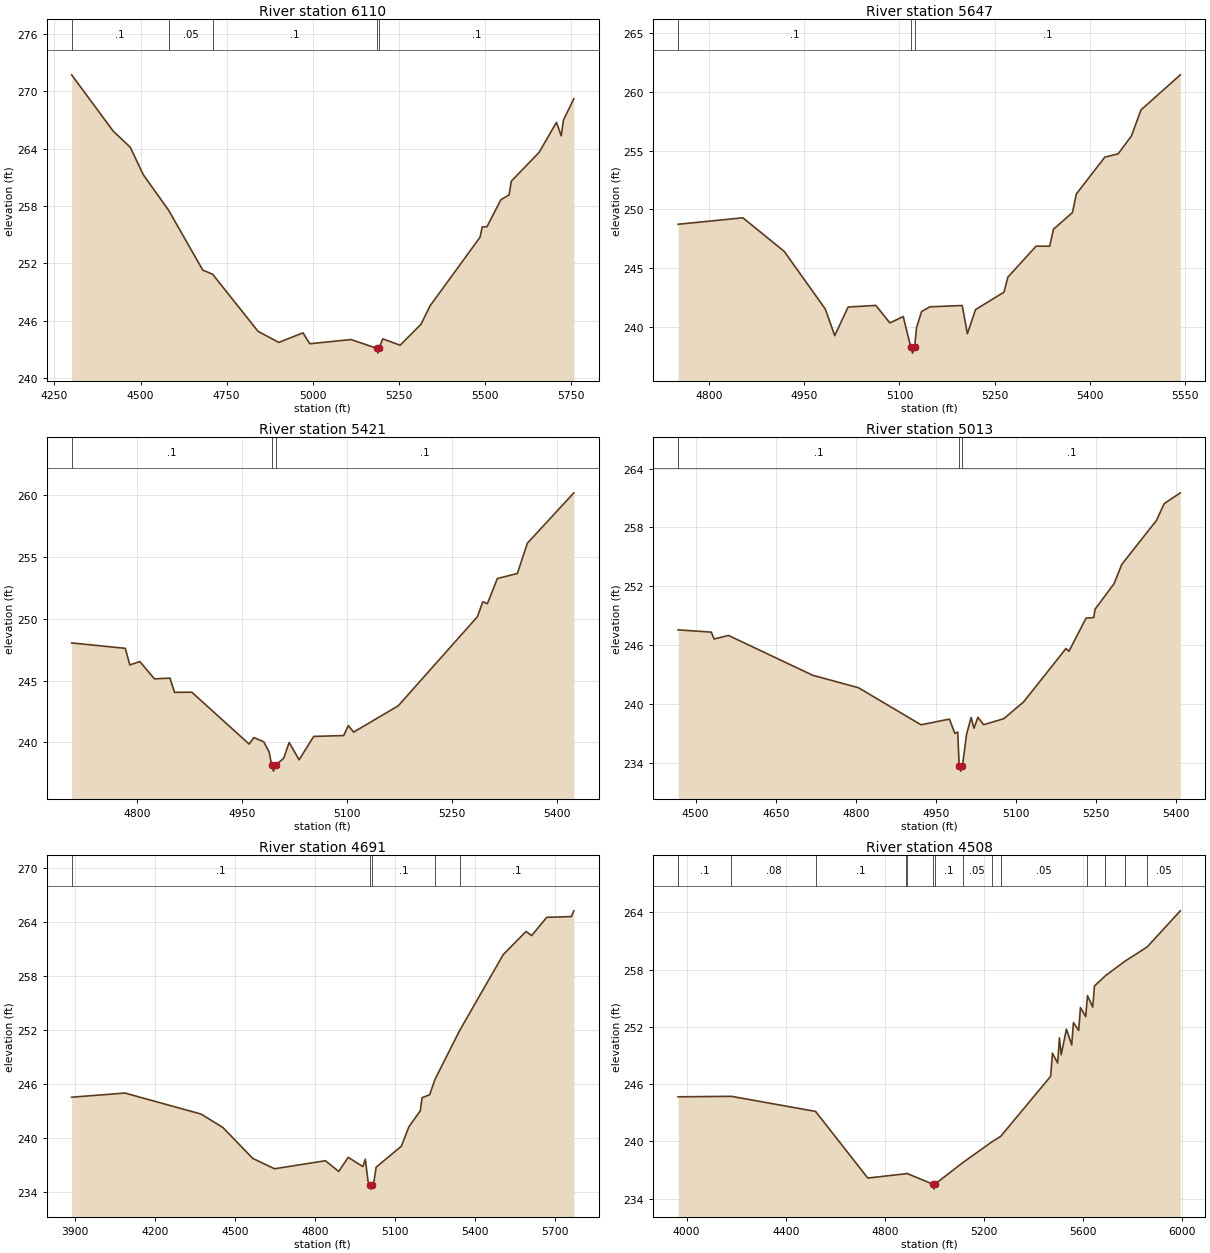
Type RM Length L Ch R = 1,6110,463,463,463
BEGIN DESCRIPTION:
UNT 018 IN RACR 12.0
END DESCRIPTION:
XS GIS Cut Line= 3
      2243687.75     13228196.86      2244387.72     13228246.85
      2245137.73     13228346.86
#Sta/Elev= 30
  4300.0  271.71  4420.3  265.84  4470.4  264.13  4508.0  261.27  4581.6  257.55
  4680.9  251.29  4709.4  250.86  4841.3  244.89  4901.5  243.73  4971.7  244.73
  4991.7  243.59  5111.5  244.03  5186.6  243.11  5189.4  242.61  5192.6  243.11
  5203.5  244.10  5254.0  243.44  5314.5  245.63  5341.0  247.56  5486.0  254.73
  5492.3  255.81  5506.2  255.83  5546.5  258.65  5570.5  259.16  5576.8  260.59
  5657.5  263.60  5707.9  266.74  5721.8  265.33  5728.1  266.96  5758.4  269.21
#Mann=5,-1,0
  4300.0     0.1       0  4581.6    0.05       0  4709.4     0.1       0
  5186.6    0.07       0  5192.6     0.1       0
Bank Sta=5186.6,5192.6
Exp/Cntr=0.3,0.1

Type RM Length L Ch R = 1,5647,226,226,226
BEGIN DESCRIPTION:
UNT 018 IN RACR 11.0
END DESCRIPTION:
XS GIS Cut Line= 3
      2244313.82     13228776.70      2244417.98     13228750.66
      2244986.54     13228368.72
#Sta/Elev= 30
  4750.8  248.73  4853.0  249.28  4918.1  246.43  4982.9  241.53  4997.9  239.26
  5019.0  241.69  5062.7  241.83  5084.9  240.34  5106.0  240.88  5117.9  238.27
  5120.7  237.77  5123.9  238.27  5127.0  239.94  5134.9  241.31  5148.0  241.71
  5199.0  241.82  5207.2  239.42  5220.0  241.47  5265.0  242.96  5271.0  244.23
  5315.6  246.87  5337.0  246.86  5343.0  248.31  5373.0  249.73  5379.0  251.30
  5424.0  254.44  5445.0  254.72  5466.0  256.24  5481.0  258.45  5543.1  261.44
#Mann=3,-1,0
  4750.8     0.1       0  5117.9    0.07       0  5123.9     0.1       0
Bank Sta=5117.9,5123.9
Exp/Cntr=0.3,0.1

Type RM Length L Ch R = 1,5421,408,408,408
BEGIN DESCRIPTION:
UNT 018 IN RACR 10.0
END DESCRIPTION:
XS GIS Cut Line= 3
      2244467.45     13228973.75      2244597.67     13228866.98
      2245015.93     13228511.06
#Sta/Elev= 30
  4707.0  248.05  4783.7  247.61  4790.1  246.27  4804.5  246.54  4825.3  245.14
  4847.5  245.20  4854.0  244.05  4878.7  244.06  4960.6  239.86  4967.4  240.39
  4981.5  240.04  4989.2  239.22  4992.8  238.17  4995.5  237.67  4998.8  238.17
  5010.0  238.71  5017.8  239.99  5032.0  238.59  5052.9  240.48  5095.7  240.55
  5102.3  241.36  5110.0  240.83  5173.7  242.96  5286.8  250.17  5294.5  251.38
  5301.1  251.23  5315.3  253.26  5343.9  253.67  5358.2  256.12  5424.6  260.20
#Mann=3,-1,0
  4707.0     0.1       0  4992.8    0.07       0  4998.8     0.1       0
Bank Sta=4992.8,4998.8
Exp/Cntr=0.3,0.1

Type RM Length L Ch R = 1,5013,322,322,322
BEGIN DESCRIPTION:
UNT 018 IN RACR 9.0
END DESCRIPTION:
XS GIS Cut Line= 4
      2244407.60     13229111.78      2244628.92     13229182.08
      2245139.33     13228994.58      2245272.17     13228898.20
#Sta/Elev= 30
  4467.3  247.57  4529.4  247.34  4534.6  246.64  4561.6  247.00  4719.5  242.94
  4804.8  241.68  4922.0  237.90  4975.2  238.48  4985.4  237.02  4990.7  237.16
  4993.5  233.68  4996.3  233.18  4999.5  233.68  5007.2  236.91  5015.8  238.65
  5021.2  237.55  5028.5  238.66  5039.2  237.91  5076.8  238.52  5113.7  240.21
  5193.4  245.67  5199.0  245.39  5230.9  248.76  5245.4  248.83  5247.7  249.66
  5283.3  252.27  5297.9  254.24  5362.9  258.73  5377.2  260.43  5407.4  261.53
#Mann=3,-1,0
  4467.3     0.1       0  4993.5    0.07       0  4999.5     0.1       0
Bank Sta=4993.5,4999.5
Exp/Cntr=0.3,0.1

Type RM Length L Ch R = 1,4691,183,183,183
BEGIN DESCRIPTION:
Mapping XS 4b495e28
END DESCRIPTION:
XS GIS Cut Line= 4
      2243961.73     13229625.13      2244747.32     13229473.22
      2245103.22     13229338.67      2245580.65     13228826.52
#Sta/Elev= 30
  3888.2  244.56  4087.8  245.02  4373.0  242.69  4454.5  241.20  4566.5  237.77
  4648.0  236.62  4838.7  237.51  4888.4  236.32  4924.0  237.89  4978.9  236.86
  4988.1  237.68  4998.4  235.20  5006.5  234.86  5009.2  234.36  5012.5  234.86
  5020.2  235.16  5028.5  236.79  5123.0  239.12  5151.3  241.28  5193.8  243.04
  5200.6  244.51  5229.0  244.83  5249.2  246.55  5341.0  251.94  5505.0  260.40
  5590.0  262.95  5611.0  262.49  5667.7  264.52  5759.5  264.60  5769.0  265.24
#Mann=5,-1,0
  3888.2     0.1       0  5006.5    0.07       0  5012.5     0.1       0
  5249.2    0.05       0  5341.0     0.1       0
Bank Sta=5006.5,5012.5
Exp/Cntr=0.3,0.1

Type RM Length L Ch R = 1,4508,79,79,79
BEGIN DESCRIPTION:
Mapping XS a3aceadc
END DESCRIPTION:
XS GIS Cut Line= 5
      2243970.40     13229716.28      2244617.11     13229651.17
      2244933.95     13229555.69      2245059.82     13229481.90
      2245691.95     13228841.11
#Sta/Elev= 30
  3965.8  244.68  4181.0  244.73  4520.6  243.15  4731.3  236.17  4885.4  236.62
  4888.1  236.67  4995.5  235.51  4998.3  235.01  5001.5  235.51  5113.9  237.77
  5231.0  239.94  5268.2  240.55  5469.4  246.83  5476.6  249.25  5497.7  248.22
  5504.8  250.86  5511.9  249.08  5533.1  251.77  5554.3  250.11  5561.4  252.45
  5582.6  251.63  5589.7  254.03  5610.9  253.08  5618.0  255.29  5639.2  254.08
  5646.3  256.29  5690.3  257.36  5770.1  258.90  5858.7  260.37  5992.7  264.16
#Mann=14,-1,0
  3965.8     0.1       0  4181.0    0.08       0  4520.6     0.1       0
  4885.4    0.08       0  4888.1     0.1       0  4995.5    0.07       0
  5001.5     0.1       0  5113.9    0.05       0  5231.0     0.1       0
  5268.2    0.05       0  5618.0     0.1       0  5690.3    0.05       0
  5770.1     0.1       0  5858.7    0.05       0
Bank Sta=4995.5,5001.5
Exp/Cntr=0.3,0.1

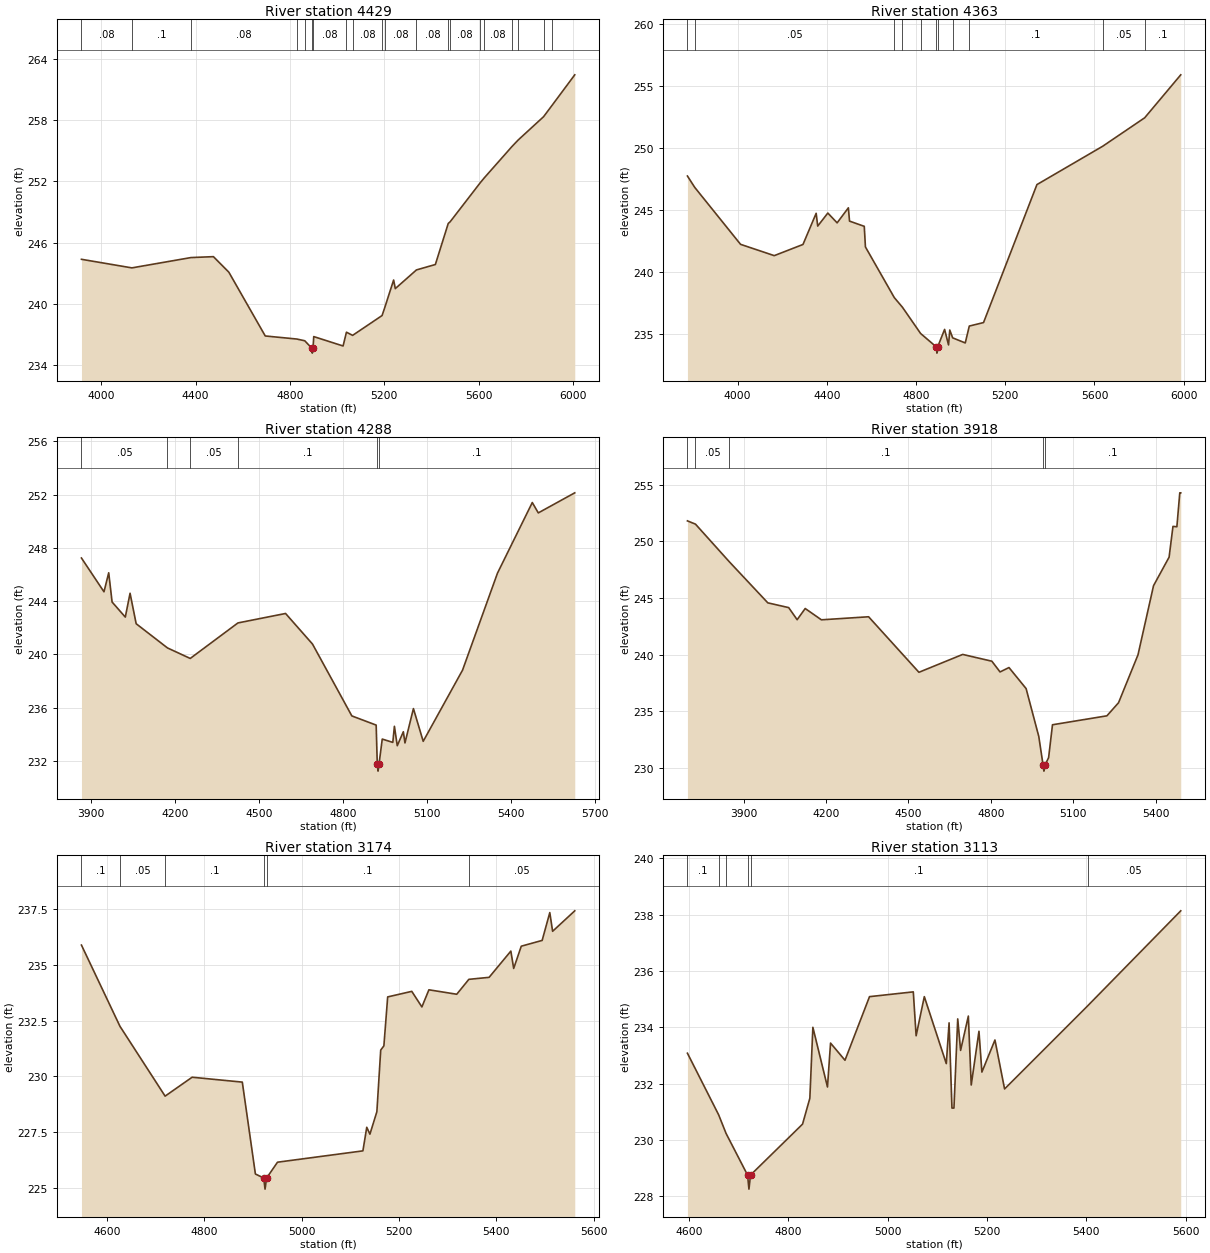
Type RM Length L Ch R = 1,4429,66,66,66
BEGIN DESCRIPTION:
Mapping XS e27483e4
END DESCRIPTION:
XS GIS Cut Line= 5
      2243970.37     13229829.13      2244547.66     13229737.98
      2244864.50     13229694.58      2245146.62     13229516.63
      2245745.57     13228908.99
#Sta/Elev= 30
  3916.2  244.37  4130.0  243.53  4380.6  244.54  4475.6  244.63  4540.9  243.11
  4695.3  236.86  4829.1  236.56  4862.7  236.39  4891.9  235.68  4894.6  235.18
  4897.9  235.68  4900.8  236.80  5025.2  235.88  5039.4  237.23  5065.6  236.92
  5190.4  238.86  5201.4  239.61  5239.4  242.34  5246.5  241.50  5336.2  243.33
  5416.3  243.86  5470.9  247.88  5478.8  248.04  5605.6  251.84  5623.0  252.33
  5740.4  255.40  5767.1  256.05  5875.1  258.34  5911.3  259.46  6007.2  262.44
#Mann=20,-1,0
  3916.2    0.08       0  4130.0     0.1       0  4380.6    0.08       0
  4829.1     0.1       0  4862.7    0.08       0  4891.9    0.07       0
  4897.9    0.08       0  5039.4     0.1       0  5065.6    0.08       0
  5190.4     0.1       0  5201.4    0.08       0  5336.2    0.08       0
  5470.9    0.05       0  5478.8    0.08       0  5605.6    0.05       0
  5623.0    0.08       0  5740.4    0.05       0  5767.1    0.08       0
  5875.1    0.05       0  5911.3    0.08       0
Bank Sta=4891.9,4897.9
Exp/Cntr=0.3,0.1

Type RM Length L Ch R = 1,4363,75,75,75
BEGIN DESCRIPTION:
Mapping XS 17488322
END DESCRIPTION:
XS GIS Cut Line= 4
      2243874.89     13230050.49      2244756.00     13229785.72
      2245150.96     13229607.77      2245849.77     13229108.62
#Sta/Elev= 30
  3774.8  247.74  3807.8  246.82  4013.0  242.24  4164.1  241.33  4292.9  242.23
  4352.0  244.74  4359.0  243.71  4404.3  244.76  4446.0  243.97  4496.4  245.18
  4501.6  244.11  4567.7  243.69  4572.9  242.03  4702.4  237.95  4738.7  237.18
  4820.4  235.06  4890.8  233.98  4893.6  233.48  4896.8  233.98  4927.9  235.39
  4945.6  234.14  4951.1  235.34  4964.1  234.71  5020.5  234.30  5038.7  235.66
  5102.5  235.94  5341.9  247.05  5636.9  250.14  5825.1  252.43  5986.8  255.89
#Mann=11,-1,0
  3774.8    0.08       0  3807.8    0.05       0  4702.4     0.1       0
  4738.7    0.08       0  4820.4     0.1       0  4890.8    0.07       0
  4896.8     0.1       0  4964.1    0.08       0  5038.7     0.1       0
  5636.9    0.05       0  5825.1     0.1       0
Bank Sta=4890.8,4896.8
Exp/Cntr=0.3,0.1

Type RM Length L Ch R = 1,4288,370,370,370
BEGIN DESCRIPTION:
UNT 018 IN RACR 8.0
END DESCRIPTION:
XS GIS Cut Line= 4
      2243988.29     13230213.33      2244691.42     13229911.25
      2245217.46     13229616.98      2245554.34     13229414.84
#Sta/Elev= 30
  3867.0  247.24  3947.4  244.70  3964.3  246.13  3976.4  243.93  4023.5  242.80
  4040.5  244.59  4062.3  242.30  4174.1  240.48  4255.3  239.69  4425.6  242.36
  4595.6  243.07  4691.8  240.77  4832.2  235.37  4919.0  234.68  4923.0  231.72
  4925.7  231.22  4929.0  231.72  4940.7  233.63  4978.4  233.38  4984.1  234.59
  4994.3  233.13  5016.0  234.18  5021.8  233.34  5052.0  235.92  5086.9  233.46
  5227.3  238.81  5352.0  246.10  5476.3  251.41  5497.7  250.63  5627.9  252.14
#Mann=6,-1,0
  3867.0    0.05       0  4174.1     0.1       0  4255.3    0.05       0
  4425.6     0.1       0  4923.0    0.07       0  4929.0     0.1       0
Bank Sta=4923,4929
Exp/Cntr=0.3,0.1

Type RM Length L Ch R = 1,3918,744,744,744
BEGIN DESCRIPTION:
UNT 018 IN RACR 7.0
END DESCRIPTION:
XS GIS Cut Line= 3
      2243937.70     13230496.86      2245137.72     13229996.85
      2245487.72     13229646.85
#Sta/Elev= 30
  3696.0  251.82  3725.3  251.53  3848.5  248.20  3988.5  244.57  4064.4  244.15
  4095.2  243.08  4124.5  244.07  4183.5  243.07  4355.2  243.34  4538.3  238.43
  4697.6  240.01  4803.7  239.41  4833.5  238.46  4866.0  238.85  4928.3  236.99
  4974.4  232.76  4990.3  230.19  4993.1  229.69  4996.3  230.19  5010.2  230.88
  5024.3  233.79  5222.3  234.58  5264.7  235.74  5335.4  239.97  5392.0  246.09
  5448.6  248.61  5462.7  251.33  5476.9  251.30  5487.5  254.30  5491.0  254.30
#Mann=5,-1,0
  3696.0     0.1       0  3725.3    0.05       0  3848.5     0.1       0
  4990.3    0.07       0  4996.3     0.1       0
Bank Sta=4990.3,4996.3
Exp/Cntr=0.3,0.1

Type RM Length L Ch R = 1,3174,61,61,61
BEGIN DESCRIPTION:
Mapping XS 22b72a62
END DESCRIPTION:
XS GIS Cut Line= 6
      2244812.41     13230515.54      2245119.69     13230557.21
      2245153.54     13230645.75      2245249.90     13230656.16
      2245426.98     13230510.33      2245669.21     13230367.08
#Sta/Elev= 30
  4547.4  235.90  4626.5  232.25  4719.3  229.11  4774.8  229.96  4877.9  229.74
  4904.8  225.61  4921.9  225.43  4924.6  224.93  4927.9  225.43  4950.2  226.14
  5125.7  226.65  5133.6  227.71  5140.1  227.40  5154.4  228.41  5162.3  231.18
  5168.8  231.37  5176.6  233.57  5226.1  233.82  5246.9  233.12  5261.3  233.89
  5318.5  233.69  5343.4  234.36  5385.0  234.45  5429.7  235.63  5435.5  234.85
  5451.1  235.85  5494.0  236.11  5509.7  237.36  5515.5  236.52  5561.0  237.44
#Mann=6,-1,0
  4547.4     0.1       0  4626.5    0.05       0  4719.3     0.1       0
  4921.9    0.07       0  4927.9     0.1       0  5343.4    0.05       0
Bank Sta=4921.9,4927.9
Exp/Cntr=0.3,0.1

Type RM Length L Ch R = 1,3113,77,77,77
BEGIN DESCRIPTION:
Mapping XS 10869fbb
END DESCRIPTION:
XS GIS Cut Line= 6
      2244843.64     13230591.06      2245067.61     13230596.27
      2245163.96     13230708.25      2245234.27     13230708.25
      2245356.67     13230596.27      2245676.99     13230395.75
#Sta/Elev= 30
  4596.5  233.08  4659.4  230.89  4674.3  230.23  4717.6  228.75  4720.4  228.25
  4723.6  228.75  4828.4  230.56  4843.1  231.48  4849.2  234.00  4878.6  231.88
  4884.8  233.44  4913.9  232.83  4963.3  235.09  5051.5  235.26  5057.2  233.70
  5073.7  235.09  5118.0  232.71  5123.6  234.16  5129.4  231.13  5133.4  231.13
  5141.0  234.30  5146.8  233.18  5162.4  234.40  5168.2  231.95  5183.8  233.86
  5189.7  232.41  5216.0  233.55  5235.4  231.81  5402.6  234.76  5590.3  238.14
#Mann=6,-1,0
  4596.5     0.1       0  4659.4    0.05       0  4674.3     0.1       0
  4717.6    0.07       0  4723.6     0.1       0  5402.6    0.05       0
Bank Sta=4717.6,4723.6
Exp/Cntr=0.3,0.1

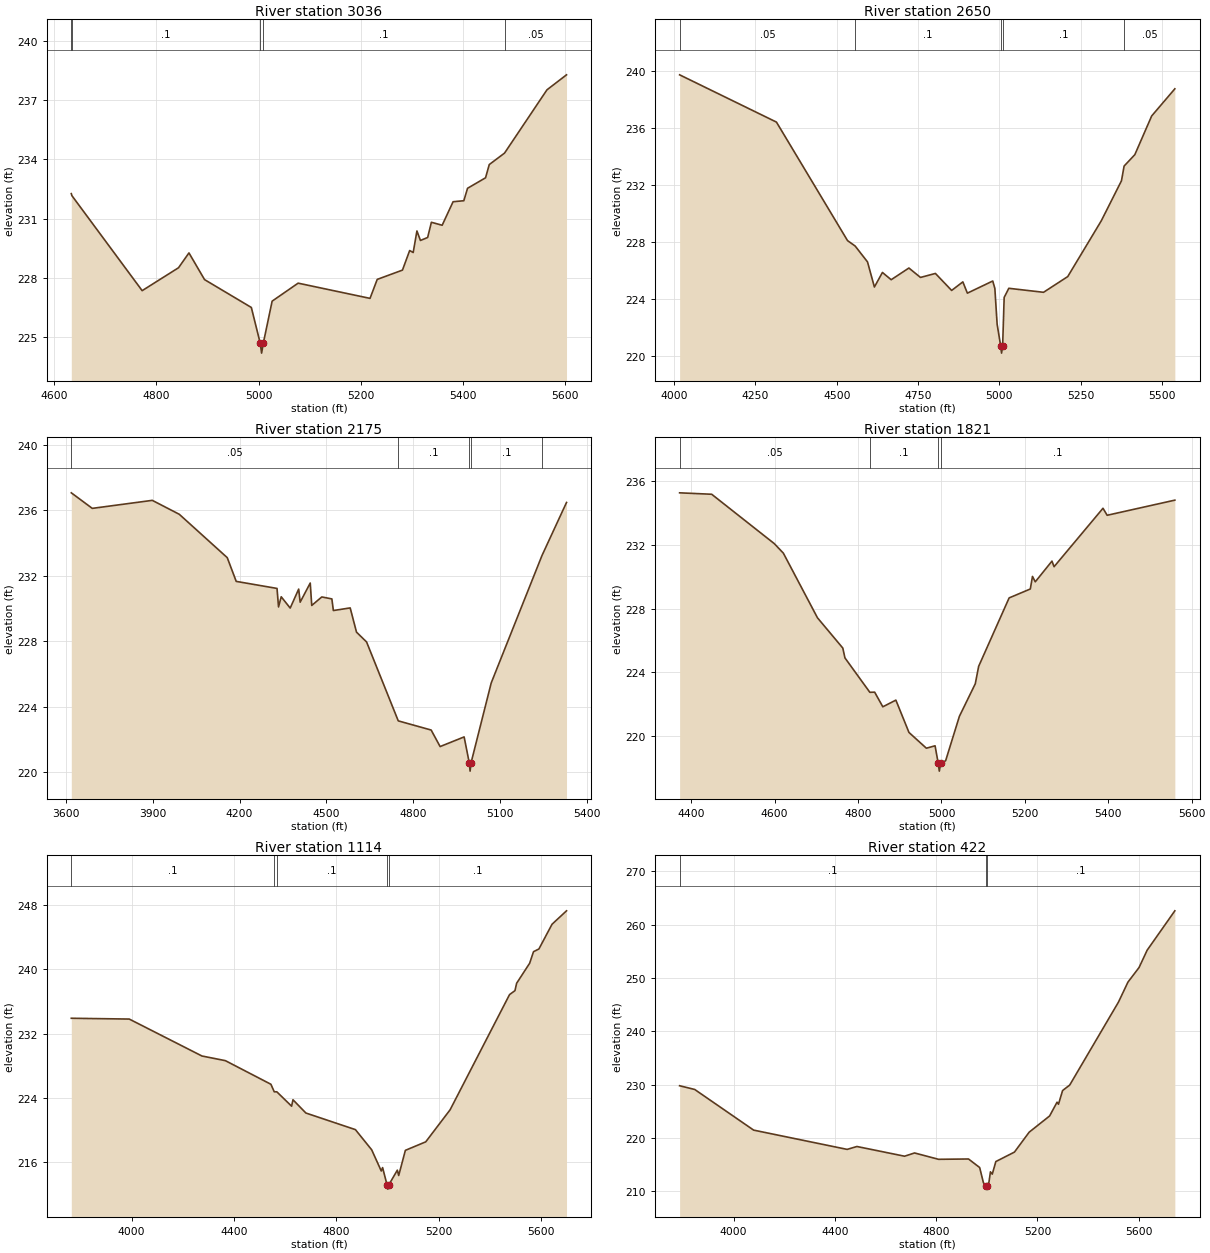
Type RM Length L Ch R = 1,3036,386,386,386
BEGIN DESCRIPTION:
Mapping XS 858e8c0d
END DESCRIPTION:
XS GIS Cut Line= 3
      2244851.41     13230848.88      2245403.54     13230744.71
      2245683.75     13230448.93
#Sta/Elev= 30
  4633.4  232.26  4634.5  232.16  4772.1  227.35  4843.3  228.51  4863.7  229.26
  4894.2  227.91  4985.8  226.50  5003.2  224.69  5005.9  224.19  5009.2  224.69
  5026.5  226.82  5077.4  227.73  5218.1  226.96  5232.2  227.92  5281.6  228.39
  5295.7  229.38  5302.6  229.28  5309.9  230.37  5316.8  229.89  5330.9  230.04
  5338.2  230.81  5359.3  230.66  5380.7  231.85  5401.7  231.90  5409.0  232.53
  5444.2  233.06  5451.5  233.73  5481.4  234.31  5564.4  237.51  5602.7  238.27
#Mann=5,-1,0
  4633.4    0.05       0  4634.5     0.1       0  5003.2    0.07       0
  5009.2     0.1       0  5481.4    0.05       0
Bank Sta=5003.2,5009.2
Exp/Cntr=0.3,0.1

Type RM Length L Ch R = 1,2650,475,475,475
BEGIN DESCRIPTION:
UNT 018 IN RACR 6.0
END DESCRIPTION:
XS GIS Cut Line= 4
      2244637.68     13231246.87      2245476.46     13231031.16
      2245643.13     13230833.25      2245742.08     13230447.86
#Sta/Elev= 30
  4016.9  239.71  4314.6  236.40  4533.2  228.10  4556.6  227.72  4594.6  226.61
  4615.8  224.85  4640.5  225.87  4667.4  225.36  4721.9  226.18  4757.5  225.52
  4803.4  225.80  4853.3  224.61  4887.8  225.21  4901.7  224.42  4979.7  225.27
  4986.2  224.75  4993.2  222.24  5004.1  220.72  5006.8  220.22  5010.1  220.72
  5014.8  224.12  5029.1  224.76  5135.8  224.48  5210.3  225.58  5313.5  229.49
  5375.5  232.29  5383.6  233.32  5416.6  234.12  5468.4  236.83  5539.6  238.73
#Mann=5,-1,0
  4016.9    0.05       0  4556.6     0.1       0  5004.1    0.07       0
  5010.1     0.1       0  5383.6    0.05       0
Bank Sta=5004.1,5010.1
Exp/Cntr=0.3,0.1

Type RM Length L Ch R = 1,2175,354,354,354
BEGIN DESCRIPTION:
UNT 018 IN RACR 5.0
END DESCRIPTION:
XS GIS Cut Line= 3
      2244687.68     13231396.87      2245987.72     13231046.85
      2246087.71     13230696.90
#Sta/Elev= 30
  3618.8  237.06  3691.3  236.11  3898.5  236.60  3991.7  235.75  4157.4  233.10
  4188.4  231.65  4329.3  231.22  4334.5  230.09  4343.8  230.71  4374.8  230.02
  4404.1  231.18  4409.2  230.38  4444.0  231.55  4449.2  230.18  4483.9  230.70
  4518.7  230.58  4523.9  229.87  4582.0  230.03  4603.8  228.55  4638.6  227.95
  4748.0  223.13  4861.6  222.57  4892.6  221.56  4975.5  222.15  4993.3  220.56
  4996.1  220.06  4999.3  220.56  5069.1  225.45  5244.4  233.23  5329.1  236.47
#Mann=5,-1,0
  3618.8    0.05       0  4748.0     0.1       0  4993.3    0.07       0
  4999.3     0.1       0  5244.4    0.05       0
Bank Sta=4993.3,4999.3
Exp/Cntr=0.3,0.1

Type RM Length L Ch R = 1,1821,707,707,707
BEGIN DESCRIPTION:
UNT 018 IN RACR 4.0
END DESCRIPTION:
XS GIS Cut Line= 4
      2245440.91     13231455.51      2245686.05     13231464.94
      2246280.05     13231285.80      2246308.34     13230965.20
#Sta/Elev= 30
  4372.1  235.27  4449.0  235.18  4599.1  232.08  4620.9  231.48  4702.7  227.42
  4763.4  225.52  4768.6  224.90  4828.3  222.74  4839.8  222.75  4859.4  221.83
  4890.7  222.25  4922.1  220.22  4963.8  219.23  4984.7  219.38  4992.2  218.29
  4994.9  217.79  4998.2  218.29  5010.0  218.44  5043.0  221.23  5081.2  223.28
  5089.2  224.37  5162.3  228.67  5213.1  229.23  5218.3  230.02  5225.0  229.68
  5265.0  230.98  5270.1  230.63  5387.4  234.30  5397.4  233.86  5559.7  234.81
#Mann=4,-1,0
  4372.1    0.05       0  4828.3     0.1       0  4992.2    0.07       0
  4998.2     0.1       0
Bank Sta=4992.2,4998.2
Exp/Cntr=0.3,0.1

Type RM Length L Ch R = 1,1114,692,692,692
BEGIN DESCRIPTION:
UNT 018 IN RACR 3.0
END DESCRIPTION:
XS GIS Cut Line= 4
      2245275.91     13231515.53      2246328.02     13231900.96
      2246604.06     13231807.21      2247040.68     13231521.33
#Sta/Elev= 30
  3764.9  233.92  3991.3  233.82  4275.1  229.22  4366.6  228.64  4544.4  225.70
  4557.5  224.76  4567.5  224.76  4625.2  222.97  4630.6  223.77  4680.9  222.12
  4874.4  220.05  4937.9  217.54  4975.4  214.90  4980.6  215.32  4998.2  213.14
  5001.0  212.64  5004.2  213.14  5038.1  215.00  5043.5  214.34  5069.5  217.47
  5149.1  218.53  5244.2  222.52  5476.4  236.87  5497.5  237.36  5504.0  238.28
  5554.8  240.77  5569.9  242.21  5591.0  242.55  5642.3  245.63  5698.8  247.30
#Mann=5,-1,0
  3764.9     0.1       0  4557.5    0.05       0  4567.5     0.1       0
  4998.2    0.07       0  5004.2     0.1       0
Bank Sta=4998.2,5004.2
Exp/Cntr=0.3,0.1

Type RM Length L Ch R = 1,422,0,0,0
BEGIN DESCRIPTION:
UNT 018 IN RACR 1.0
END DESCRIPTION:
XS GIS Cut Line= 5
      2245865.19     13231908.08      2246619.48     13232266.37
      2246883.48     13232351.23      2247175.77     13232172.09
      2247410.72     13231730.37
#Sta/Elev= 30
  3787.1  229.82  3846.7  229.12  4079.4  221.50  4448.6  217.89  4487.4  218.43
  4675.4  216.61  4714.9  217.22  4809.4  216.03  4927.9  216.09  4971.9  214.49
  4986.5  211.68  4996.0  210.94  4998.8  210.44  5002.0  210.94  5008.6  211.76
  5014.5  213.68  5021.7  213.25  5035.8  215.61  5109.2  217.38  5167.3  221.11
  5248.2  224.16  5277.5  226.74  5283.1  226.35  5299.4  228.92  5327.5  229.95
  5520.1  245.51  5557.5  249.25  5601.4  251.99  5633.3  255.23  5742.6  262.61
#Mann=3,-1,0
  3787.1     0.1       0  4996.0    0.07       0  5002.0     0.1       0
Bank Sta=4996,5002
Exp/Cntr=0.3,0.1

Chan Stop Cuts=-1