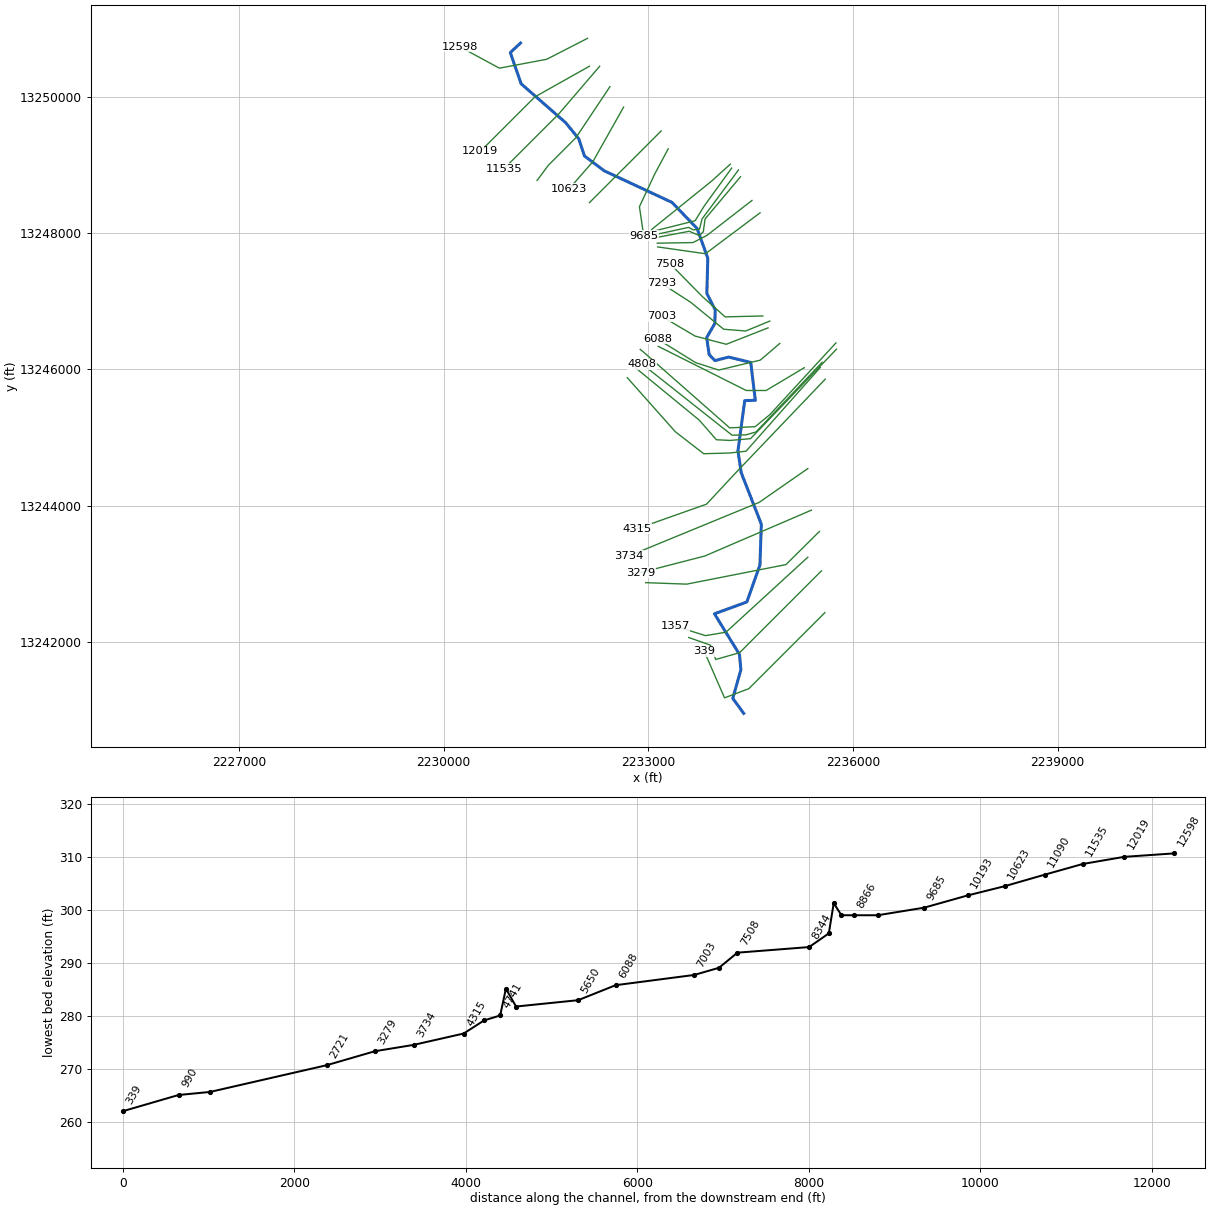
--- UNT 020 IN RACR.prj (project) ---

Proj Title=UNT 020 IN RACR Base Level Engineering
Current Plan=p01
Default Exp/Contr=0.3,0.1
English Units
Geom File=g01
Flow File=f01
Plan File=p01
Y Axis Title=Elevation
X Axis Title(PF)=Main Channel Distance
X Axis Title(XS)=Station
BEGIN DESCRIPTION:
UNT 020 IN RACR
END DESCRIPTION:
DSS Export Rating Curves= 0
DSS Export Rating Curve Sorted= 0
DSS Export Volume Flow Curves= 0
DXF OffsetX= 0
DXF OffsetY= 0
DXF ScaleX= 1
DXF ScaleY= 10

--- UNT 020 IN RACR.p01 (plan) ---

Plan Title=Multiple Run
Short Identifier=Multiple
Geom File=g01
Flow File=f01
Subcritical Flow
K Sum by GR= 0
Std Step Tol= 0.01
Critical Tol= 0.01
Num of Std Step Trials= 20
Max Error Tol= 0.3
Flow Tol Ratio= 0.001
Split Flow NTrial= 30
Split Flow Tol= 0.02
Split Flow Ratio= 0.02
Log Output Level= 0
Friction Slope Method= 1
Unsteady Friction Slope Method= 2
Unsteady Bridges Friction Slope Method= 1
Parabolic Critical Depth
Global Vel Dist=  1 , 1 , 1
Global Log Level= 0
CheckData=True
Encroach Param= -1, 0, 0, 0
BEGIN DESCRIPTION:
Multiple Run
END DESCRIPTION:

--- UNT 020 IN RACR.f01 (steady flow) ---

Flow Title=Multiple
Program Version=4.10
Number of Profiles= 7
Profile Names=10-year,25-year,50-year,1pct_min,100-year,1pct_plu,500-year
River Rch & RM=UNT 020 IN RACR,Reach-1         ,12598
     345     490     613     563     762    1030    1197
River Rch & RM=UNT 020 IN RACR,Reach-1         ,9144
     584     847    1073     999    1351    1827    2174
River Rch & RM=UNT 020 IN RACR,Reach-1         ,8721
     584     847    1073     999    1351    1827    2174
Boundary for River Rch & Prof#=UNT 020 IN RACR,Reach-1         , 1
Up Type= 0
Dn Type= 3
Dn Slope=0.005
Boundary for River Rch & Prof#=UNT 020 IN RACR,Reach-1         , 2
Up Type= 0
Dn Type= 3
Dn Slope=0.005
Boundary for River Rch & Prof#=UNT 020 IN RACR,Reach-1         , 3
Up Type= 0
Dn Type= 3
Dn Slope=0.005
Boundary for River Rch & Prof#=UNT 020 IN RACR,Reach-1         , 4
Up Type= 0
Dn Type= 3
Dn Slope=0.005
Boundary for River Rch & Prof#=UNT 020 IN RACR,Reach-1         , 5
Up Type= 0
Dn Type= 3
Dn Slope=0.005
Boundary for River Rch & Prof#=UNT 020 IN RACR,Reach-1         , 6
Up Type= 0
Dn Type= 3
Dn Slope=0.005
Boundary for River Rch & Prof#=UNT 020 IN RACR,Reach-1         , 7
Up Type= 0
Dn Type= 3
Dn Slope=0.005
DSS Import GetInterval= 0
DSS Import GetPeak= 0
DSS Import FillOption= 0

--- UNT 020 IN RACR.g01 (geometry) ---

Geom Title=Existing Conditions
Program Version=4.10

River Reach=UNT 020 IN RACR ,Reach-1
Reach XY= 30
      2231127.72     13250786.85       2230977.9     13250646.96
      2231135.68     13250189.88      2231790.97     13249616.47
      2231980.25     13249383.08      2232064.37     13249130.06
      2232355.17     13248912.65      2233346.98     13248449.83
       2233714.4     13248067.68      2233872.03     13247631.57
      2233857.71     13247114.39      2233980.56     13246873.96
      2233974.83     13246674.64      2233855.03     13246467.18
      2233891.49     13246218.05      2233975.69     13246130.37
      2234177.95     13246181.59      2234500.78     13246103.37
      2234568.58     13245547.91      2234413.19     13245543.57
      2234313.79     13244806.76      2234360.88     13244488.16
      2234656.36      13243730.8      2234635.97     13243132.66
      2234444.09     13242590.39      2233969.64       13242417.
      2234335.74     13241821.75      2234356.59       13241597.
      2234238.01     13241176.99      2234397.72     13240956.85

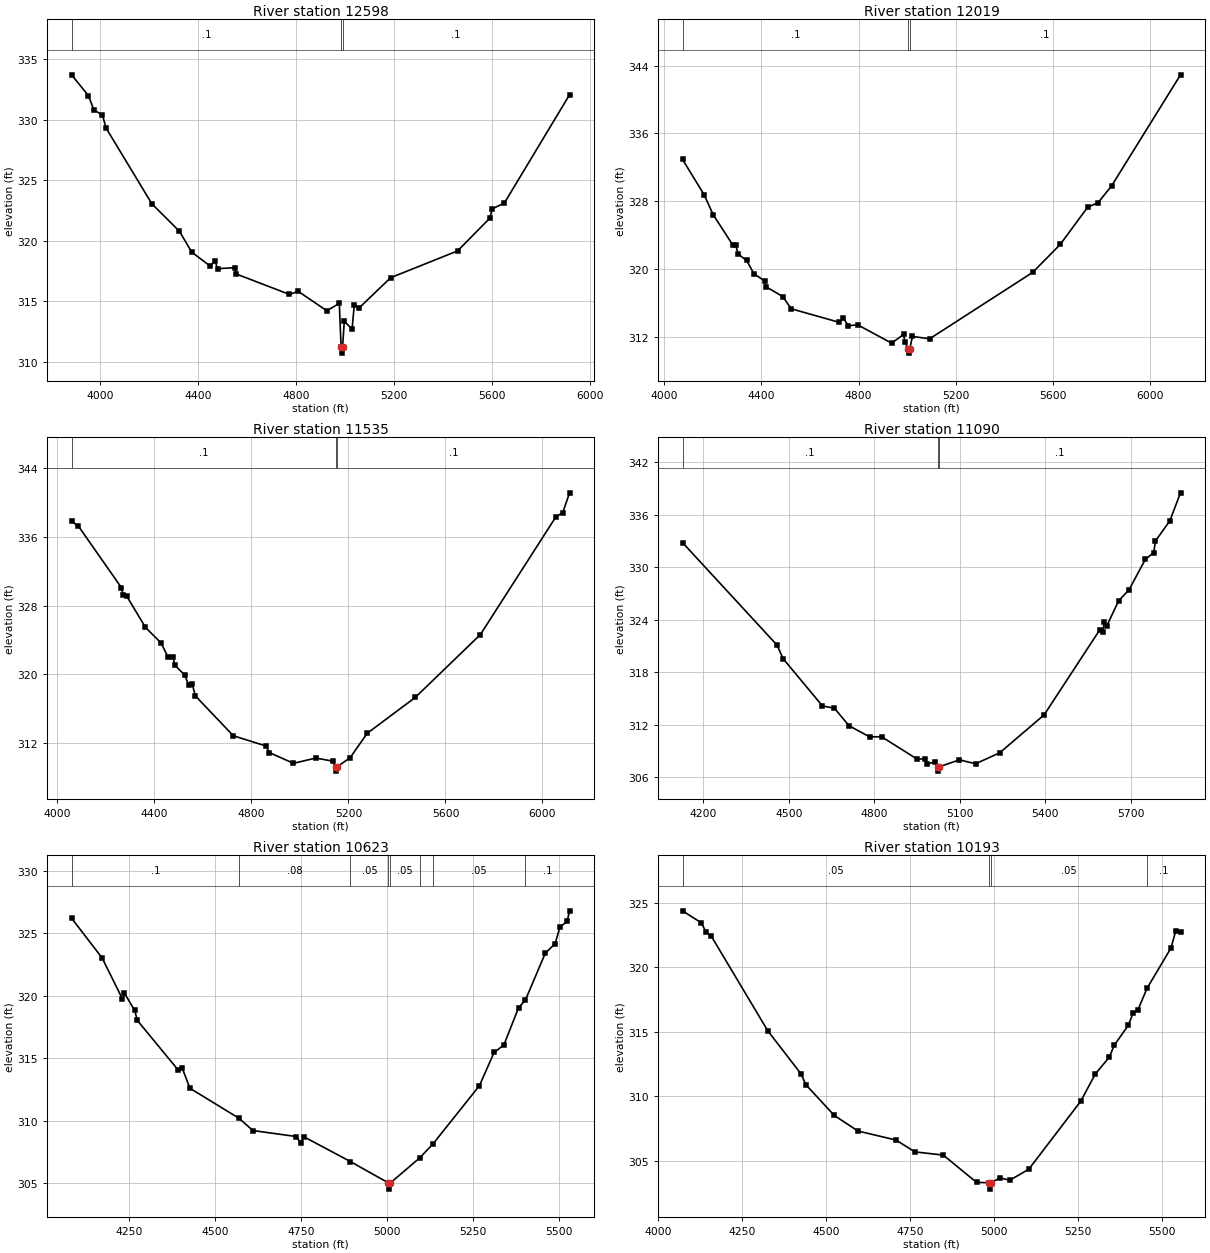
Type RM Length L Ch R = 1 ,12598   ,579,579,579
BEGIN DESCRIPTION:
UNT 020 IN RACR 23.0
END DESCRIPTION:
XS GIS Cut Line= 4
      2232109.56     13250855.67      2231510.63     13250548.39
      2230817.92     13250418.18      2230241.27     13250729.88
#Sta/Elev= 30
  3884.5  333.69  3953.5  331.97  3975.7  330.79  4010.2  330.38  4025.7  329.29
  4212.5  323.05  4324.9  320.79  4375.1  319.07  4448.5  317.95    4471  318.31
  4480.5   317.7  4552.7  317.79  4556.5  317.27  4774.3  315.58  4809.7  315.84
  4926.9  314.23  4977.8  314.85    4985  311.24  4987.7  310.74    4991  311.24
  4998.1  313.36  5029.9  312.72  5038.8  314.73  5059.2  314.48  5187.4  316.96
  5460.6  319.17  5592.4  321.87  5602.4  322.64  5651.8  323.12    5918  332.05
#Mann= 3 ,-1 , 0
  3884.5      .1       0    4985     .07       0    4991      .1       0
Bank Sta=4985,4991
XS Rating Curve= 0 ,0
Exp/Cntr=0.3,0.1

Type RM Length L Ch R = 1 ,12019   ,484,484,484
BEGIN DESCRIPTION:
UNT 020 IN RACR 22.0
END DESCRIPTION:
XS GIS Cut Line= 3
      2232137.75     13250446.87      2231337.72     13249996.85
      2230537.71     13249196.84
#Sta/Elev= 30
  4075.4  332.94  4164.4  328.78  4201.6  326.42    4282  322.86  4294.4  322.82
  4304.6  321.77  4339.3  321.02  4369.6  319.44  4412.9  318.62  4419.6  317.91
  4488.2  316.76  4522.9  315.32  4720.8  313.72  4736.8  314.22  4758.4  313.32
    4796  313.43  4935.9  311.27  4985.3   312.3  4990.4  311.39  5004.5  310.59
  5007.2  310.09  5010.5  310.59  5021.6  312.06  5092.3  311.78  5516.6  319.62
  5629.7  322.91  5742.8  327.31  5785.3  327.83  5841.8  329.85  6124.7  342.92
#Mann= 3 ,-1 , 0
  4075.4      .1       0  5004.5     .07       0  5010.5      .1       0
Bank Sta=5004.5,5010.5
XS Rating Curve= 0 ,0
Exp/Cntr=0.3,0.1

Type RM Length L Ch R = 1 ,11535   ,445,445,445
BEGIN DESCRIPTION:
UNT 020 IN RACR 21.0
END DESCRIPTION:
XS GIS Cut Line= 3
      2232287.69     13250446.82      2231687.72     13249746.85
      2230887.71     13248946.84
#Sta/Elev= 30
  4058.5  337.79  4086.4  337.26  4264.2  330.08  4270.8  329.19  4285.1  329.14
    4363  325.47  4427.2  323.66  4455.2  322.07  4477.2  321.98  4483.8  321.08
  4526.6  319.87  4540.8  318.72  4555.1  318.93  4569.4  317.48  4725.2  312.86
  4860.2  311.66  4874.5  310.89  4973.3  309.65  5065.3  310.26    5136   309.9
  5147.1  309.24  5149.9  308.74  5153.1  309.24  5206.7  310.29  5277.4  313.14
  5475.4  317.31  5744.1  324.63  6055.2  338.32  6083.5  338.82  6111.8  341.12
#Mann= 3 ,-1 , 0
  4058.5      .1       0  5147.1     .07       0  5153.1      .1       0
Bank Sta=5147.1,5153.1
XS Rating Curve= 0 ,0
Exp/Cntr=0.3,0.1

Type RM Length L Ch R = 1 ,11090   ,467,467,467
BEGIN DESCRIPTION:
UNT 020 IN RACR 20.0
END DESCRIPTION:
XS GIS Cut Line= 4
      2232437.71     13250146.84      2231937.72     13249396.85
      2231537.72     13248996.85      2231369.89      13248771.8
#Sta/Elev= 30
  4127.2  332.84  4459.2  321.11  4480.2  319.57  4618.4  314.16  4660.5   313.9
  4711.6   311.9  4783.7  310.63  4825.8  310.64  4948.9  308.12    4979  308.08
    4985  307.52    5015  307.78  5022.6  307.21  5025.3  306.71  5028.6  307.21
  5099.3     308  5155.8  307.55  5240.7  308.81  5396.3  313.14  5590.7  322.82
  5601.6  322.62  5607.8  323.74  5616.2  323.31  5657.8  326.19    5694  327.43
  5751.7  330.93  5780.9  331.69  5787.1  333.03  5837.2  335.31    5875  338.53
#Mann= 3 ,-1 , 0
  4127.2      .1       0  5022.6     .07       0  5028.6      .1       0
Bank Sta=5022.6,5028.6
XS Rating Curve= 0 ,0
Exp/Cntr=0.3,0.1

Type RM Length L Ch R = 1 ,10623   ,430,430,430
BEGIN DESCRIPTION:
UNT 020 IN RACR 19.0
END DESCRIPTION:
XS GIS Cut Line= 3
      2232637.73     13249846.87      2232187.72     13249046.85
      2231837.72     13248646.85
#Sta/Elev= 30
    4082  326.22  4170.9  323.04  4230.2  319.75    4236  320.21  4265.6  318.84
  4273.6  318.03  4391.8  314.08  4403.6  314.26  4426.2  312.61  4569.4   310.2
  4609.8  309.22    4736  308.74  4749.1  308.22  4758.9  308.71  4893.3  306.74
    5004  305.03  5006.8  304.53    5010  305.03  5094.8  307.02  5133.3  308.13
    5269  312.81  5311.7  315.47  5340.2  316.07  5382.9  319.05  5402.9  319.67
  5460.7  323.42  5489.2  324.18  5503.4  325.51  5524.3  325.97  5531.4  326.81
#Mann= 8 ,-1 , 0
    4082      .1       0  4569.4     .08       0  4893.3     .05       0
    5004     .03       0    5010     .05       0  5094.8     .08       0
  5133.3     .05       0  5402.9      .1       0
Bank Sta=5004,5010
XS Rating Curve= 0 ,0
Exp/Cntr=0.3,0.1

Type RM Length L Ch R = 1 ,10193   ,508,508,508
BEGIN DESCRIPTION:
UNT 020 IN RACR 18.0
END DESCRIPTION:
XS GIS Cut Line= 3
      2233187.71     13249496.85      2232537.72     13248846.85
      2232137.73     13248446.86
#Sta/Elev= 30
  4071.7  324.39  4128.3  323.45  4142.4  322.71  4156.5  322.47  4326.2  315.07
  4425.2  311.73  4439.4   310.9  4524.2  308.51  4594.9   307.3  4708.1   306.6
  4764.7  305.68  4849.5  305.43  4948.5  303.31  4984.4  303.29  4987.1  302.79
  4990.4  303.29  5019.2  303.66  5047.5  303.48  5104.1  304.33  5259.6  309.63
  5302.1  311.71  5344.5  313.04  5358.6  313.94    5401  315.51  5415.2  316.45
  5429.3  316.68  5456.6  318.37  5528.3  321.51  5542.5  322.85  5556.6  322.76
#Mann= 4 ,-1 , 0
  4071.7     .05       0  4984.4     .03       0  4990.4     .05       0
  5456.6      .1       0
Bank Sta=4984.4,4990.4
XS Rating Curve= 0 ,0
Exp/Cntr=0.3,0.1

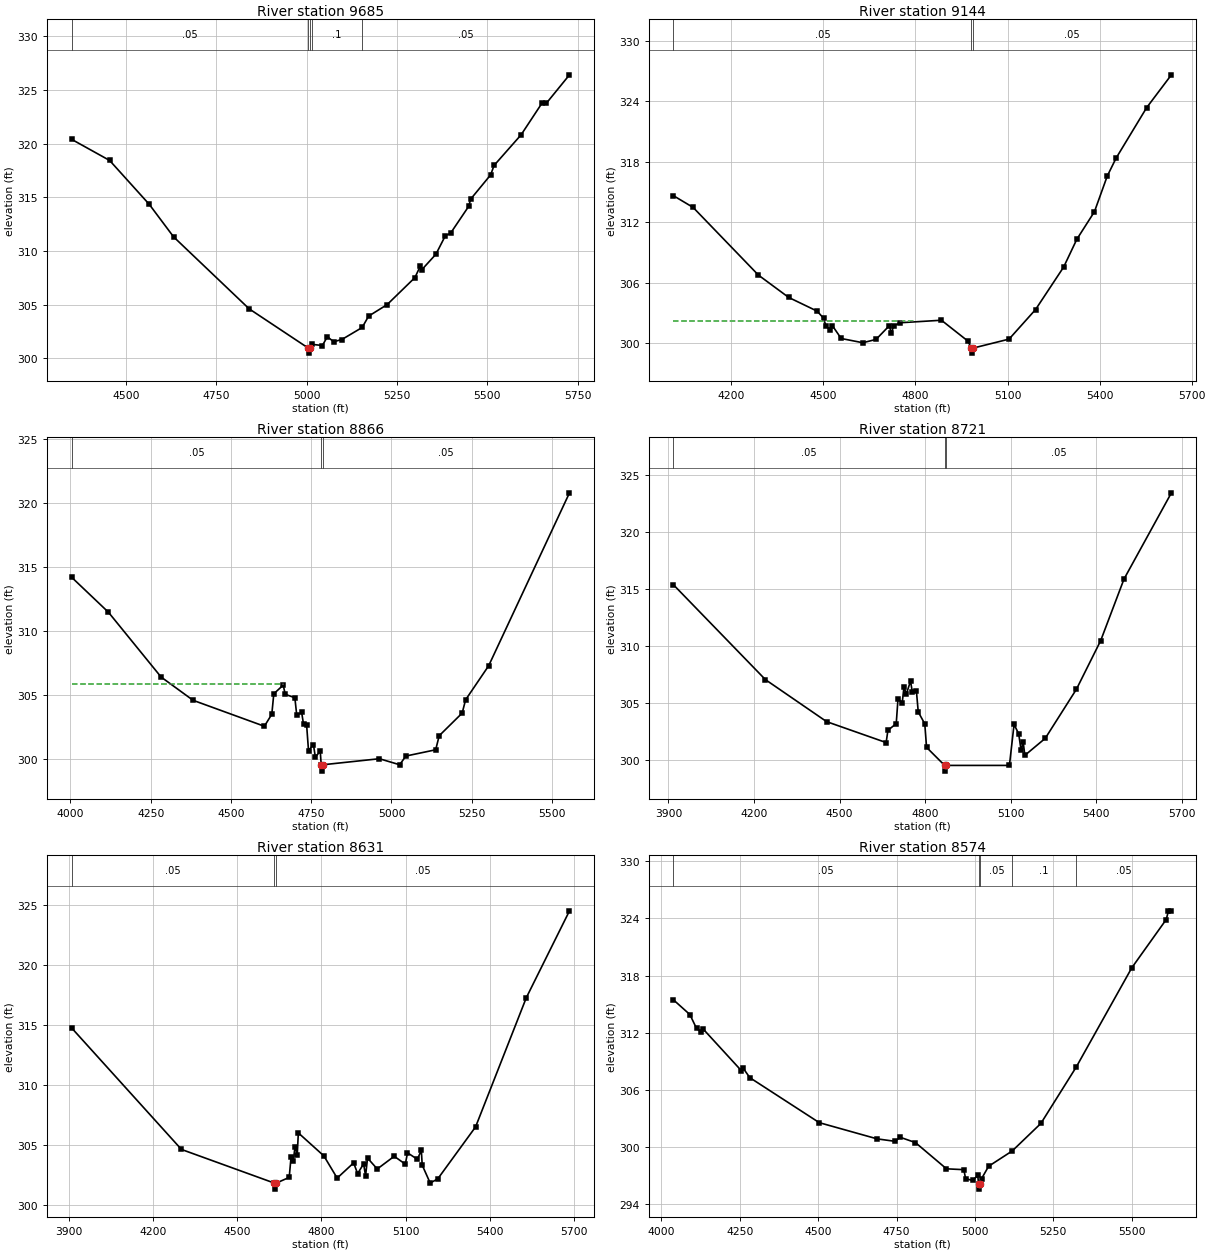
Type RM Length L Ch R = 1 ,9685    ,541,541,541
BEGIN DESCRIPTION:
UNT 020 IN RACR 17.0
END DESCRIPTION:
XS GIS Cut Line= 4
      2233291.89     13249235.91      2233093.96      13248866.1
        2232870.     13248386.93      2232932.36     13247960.84
#Sta/Elev= 30
  4348.7   320.4  4454.1  318.43  4563.8  314.34  4631.2  311.31  4840.5   304.6
  5002.9  300.97  5005.7  300.47  5008.9  300.97    5014  301.29  5043.3  301.18
  5057.2     302  5074.5  301.53  5097.3  301.74  5153.5  302.86  5171.4  303.92
  5222.6  304.99  5299.6  307.51  5314.1  308.55  5319.1  308.26  5357.8  309.69
    5384  311.42  5398.2  311.64  5448.7  314.16  5453.9  314.82  5509.4  317.09
  5518.7  317.96  5593.7  320.82  5650.9  323.74  5663.6  323.76  5727.7  326.41
#Mann= 5 ,-1 , 0
  4348.7     .05       0  5002.9     .03       0  5008.9     .05       0
    5014      .1       0  5153.5     .05       0
Bank Sta=5002.9,5008.9
XS Rating Curve= 0 ,0
Exp/Cntr=0.3,0.1

Type RM Length L Ch R = 1 ,9144    ,278,278,278
BEGIN DESCRIPTION:
UNT 020 IN RACR 16.0
END DESCRIPTION:
XS GIS Cut Line= 4
      2234203.35     13249011.94      2233927.29     13248761.93
      2233062.71     13248064.01      2232969.83     13247960.82
#Sta/Elev= 30
  4011.6  314.64  4075.6  313.48  4288.5  306.77    4387  304.56  4479.8   303.2
  4500.6   302.5  4508.6   301.7  4522.9  301.38  4529.4  301.76  4558.1  300.49
  4628.5  300.07  4671.7   300.4  4714.9  301.76  4721.3  301.02  4729.2  301.73
    4750  302.05  4884.7   302.3  4970.7  300.24  4982.1  299.54  4984.9  299.04
  4988.1  299.54  5105.1  300.43  5191.4  303.36  5283.1  307.58  5325.8  310.32
  5383.3  313.06  5424.9  316.58  5453.7  318.36  5553.4  323.37    5634  326.62
#Mann= 3 ,-1 , 0
  4011.6     .05       0  4982.1     .03       0  4988.1     .05       0
#XS Ineff= 2 , 0
         4793.83  302.22
Permanent Ineff=
       F       F
Bank Sta=4982.1,4988.1
XS Rating Curve= 0 ,0
Exp/Cntr=0.3,0.1

Type RM Length L Ch R = 1 ,8866    ,145,145,145
BEGIN DESCRIPTION:
Mapping XS 3dd6c1c6
END DESCRIPTION:
XS GIS Cut Line= 4
      2234221.65     13248952.71      2233822.11     13248401.07
       2233685.9     13248180.86      2233093.56     13248031.65
#Sta/Elev= 30
  4003.5  314.21  4118.3  311.47  4282.4   306.4    4382  304.58    4604  302.55
  4627.2  303.49  4633.4  305.09  4662.8  305.77  4668.9  305.05    4699  304.78
  4704.9  303.41  4720.2  303.63  4726.1  302.69  4735.6  302.66  4741.5  300.65
  4756.9  301.11  4762.8  300.14  4778.1   300.6    4781  299.54  4783.8  299.04
    4787  299.54  4962.3  300.01  5025.4  299.54  5044.8  300.22  5137.6  300.71
  5148.6  301.81  5220.1  303.58  5230.8  304.62  5302.6  307.28  5554.4  320.81
#Mann= 3 ,-1 , 0
  4003.5     .05       0    4781    .035       0    4787     .05       0
#XS Ineff= 2 , 0
          4661.6  305.83
Permanent Ineff=
       F       F
Bank Sta=4781,4787
XS Rating Curve= 0 ,0
Exp/Cntr=0.3,0.1

Type RM Length L Ch R = 1 ,8721    ,90,90,90
BEGIN DESCRIPTION:
Mapping XS 1f788113
END DESCRIPTION:
XS GIS Cut Line= 6
      2234321.55     13248925.49      2233788.05     13248208.11
      2233749.46       13248056.      2233658.65     13248046.92
      2233590.55     13248083.24       2233075.2       13247972.
#Sta/Elev= 30
  3917.6  315.35  4240.1  307.05  4454.9  303.37  4663.6  301.54  4669.8  302.61
    4699   303.2  4705.2  305.38  4719.9  305.01  4726.1  306.39  4734.5  305.79
  4749.1  306.92  4755.3  305.99  4769.9  306.01  4776.2  304.22  4799.1  303.18
  4805.4  301.12  4868.8  299.54  4871.6  299.04  4874.8  299.54    5096  299.54
  5112.3  303.13  5128.6   302.3    5137  300.85  5144.3  301.58  5150.1  300.42
  5221.7  301.91  5331.1  306.21  5416.1  310.46  5497.9  315.85  5664.2   323.4
#Mann= 3 ,-1 , 0
  3917.6     .05       0  4868.8    .035       0  4874.8     .05       0
Bank Sta=4868.8,4874.8
XS Rating Curve= 0 ,0
Exp/Cntr=0.3,0.1

Type RM Length L Ch R = 1 ,8631    ,57,57,57
BEGIN DESCRIPTION:
Mapping XS 41634abc
END DESCRIPTION:
XS GIS Cut Line= 6
      2234351.05     13248825.59      2233831.19     13248205.83
      2233806.22     13248019.68      2233749.46     13247962.92
      2233599.63     13248026.49      2233086.58     13247928.87
#Sta/Elev= 30
    3910  314.78  4301.4  304.64  4632.7  301.83  4635.5  301.33  4638.7  301.83
  4685.2  302.31  4691.7  303.99  4699.5  303.65    4706  304.88  4713.8   304.2
  4717.7  306.02  4808.7   304.1    4856  302.25  4914.7  303.52  4928.9  302.62
  4950.1  303.44  4957.2  302.45  4964.2  303.92  4998.8  303.01  5059.2  304.07
  5098.8  303.41  5106.5  304.36  5141.6  303.82  5155.8  304.56  5158.9  303.33
  5187.3  301.84  5214.1  302.18    5349  306.52  5529.6  317.29  5683.5  324.54
#Mann= 3 ,-1 , 0
    3910     .05       0  4632.7    .035       0  4638.7     .05       0
Bank Sta=4632.7,4638.7
XS Rating Curve= 0 ,0
Exp/Cntr=0.3,0.1

Type RM Length L Ch R = 1 ,8574    ,230,230,230
BEGIN DESCRIPTION:
UNT 020 IN RACR 15.0
END DESCRIPTION:
XS GIS Cut Line= 4
      2234519.08     13248478.28      2233858.43     13247965.19
      2233654.11     13247860.76      2233131.24     13247851.71
#Sta/Elev= 30
  4038.3  315.46  4090.7  313.92  4111.8  312.47  4126.3  312.09  4132.6  312.42
  4254.8  308.04  4261.2  308.27    4282   307.3  4503.7  302.58  4688.3  300.88
  4746.3  300.62  4760.8  301.06  4810.5  300.49  4909.5  297.74  4964.9  297.65
  4970.5  296.71  4992.7  296.52  5009.3  297.04    5012  296.11  5014.7  295.61
    5018  296.11  5021.6  296.72    5044  298.01  5119.1  299.61  5210.7   302.5
  5323.6  308.42  5500.7  318.82  5610.7  323.89  5617.3  324.73  5627.2   324.8
#Mann= 5 ,-1 , 0
  4038.3     .05       0    5012    .035       0    5018     .05       0
  5119.1      .1       0  5323.6     .05       0
Bank Sta=5012,5018
XS Rating Curve= 0 ,0
Exp/Cntr=0.3,0.1

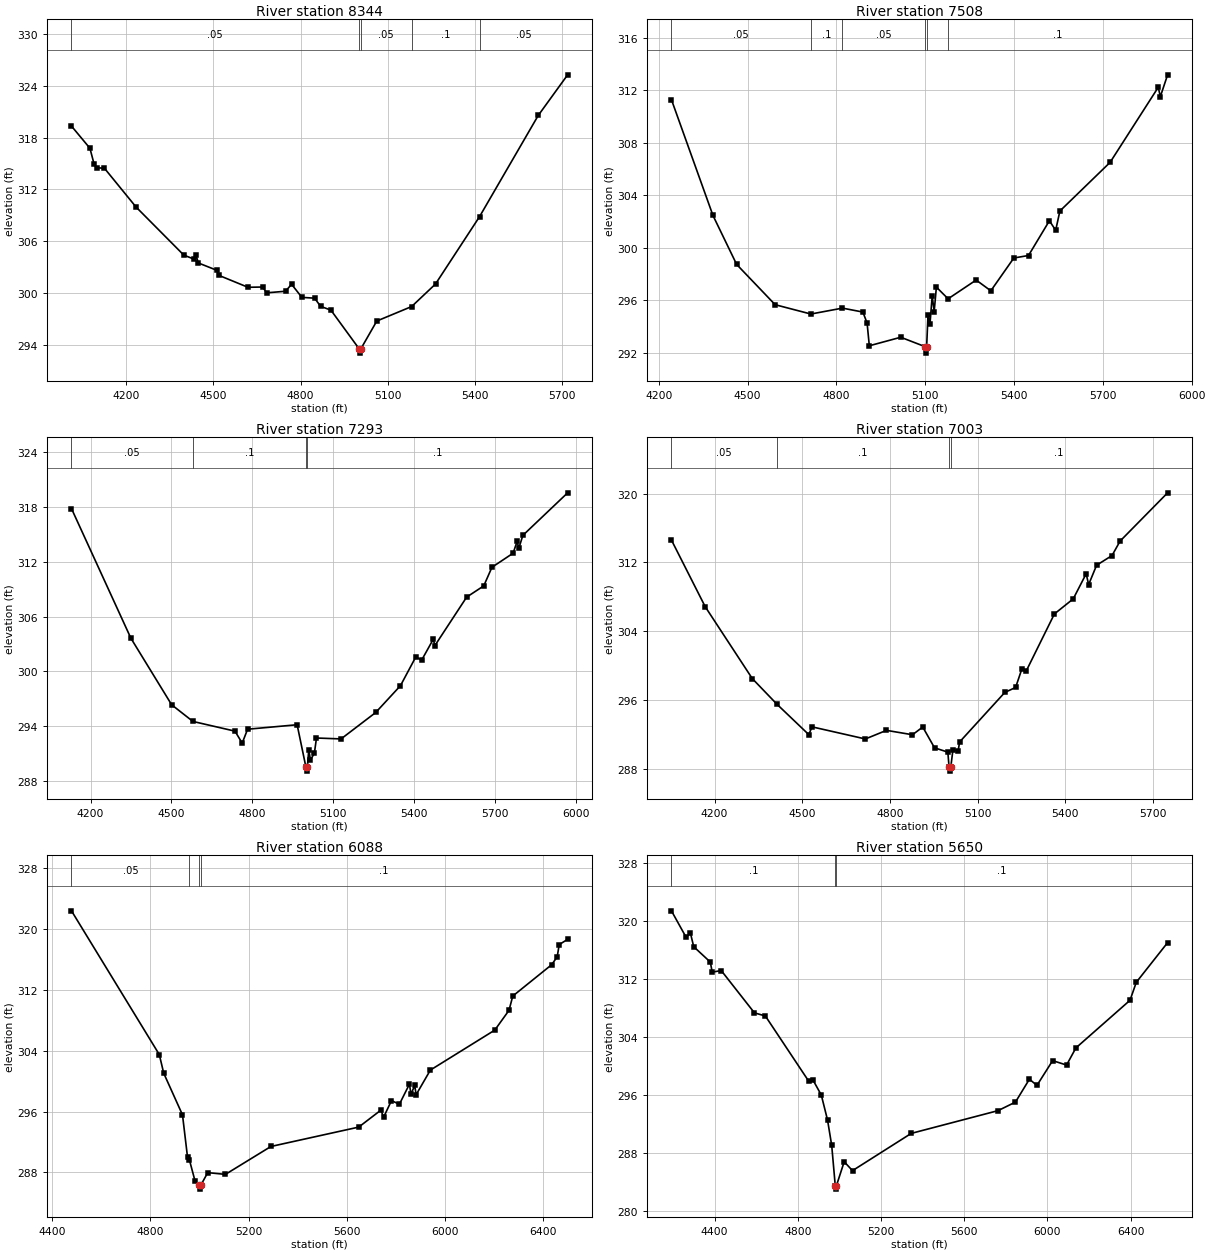
Type RM Length L Ch R = 1 ,8344    ,836,836,836
BEGIN DESCRIPTION:
UNT 020 IN RACR 14.0
END DESCRIPTION:
XS GIS Cut Line= 3
      2234637.71     13248296.84      2233837.72     13247696.85
      2233137.71     13247796.86
#Sta/Elev= 30
  4011.6  319.33  4075.1  316.76  4089.7  314.89    4098  314.51  4125.1  314.44
  4233.5  309.96    4398  304.38  4433.5  303.91  4439.7  304.41    4448  303.47
  4511.6  302.62  4518.9  302.03  4618.9  300.65  4668.9  300.68  4683.5  300.01
    4748  300.19  4768.9     301  4804.3  299.48    4848  299.39  4868.9  298.44
  4904.3     298  5001.3  293.52    5004  293.02  5007.3  293.52  5062.1  296.74
  5182.1  298.42  5264.1  301.03  5415.5  308.83  5617.7  320.57  5718.7  325.27
#Mann= 5 ,-1 , 0
  4011.6     .05       0  5001.3    .035       0  5007.3     .05       0
  5182.1      .1       0  5415.5     .05       0
Bank Sta=5001.3,5007.3
XS Rating Curve= 0 ,0
Exp/Cntr=0.3,0.1

Type RM Length L Ch R = 1 ,7508    ,215,215,215
BEGIN DESCRIPTION:
UNT 020 IN RACR 13.0
END DESCRIPTION:
XS GIS Cut Line= 4
      2234677.98     13246784.69      2234126.31     13246771.07
      2233792.59     13247068.46      2233318.19     13247551.95
#Sta/Elev= 30
  4242.5  311.28  4382.8  302.45  4462.8  298.72  4592.9  295.65  4713.6  294.94
  4820.3  295.39  4889.3  295.09  4903.5  294.25    4911  292.52  5017.2  293.17
  5098.7  292.46  5101.4  291.96  5104.7  292.46  5109.2  294.86  5115.9  294.17
  5123.4  296.32  5130.1  295.13  5137.6  296.99  5177.2   296.1  5271.9  297.53
  5321.5  296.71  5399.2  299.21  5448.8   299.4  5519.4  302.05  5540.6  301.32
  5554.8  302.79  5724.5   306.5  5887.1  312.22  5894.2  311.51  5918.7  313.17
#Mann= 6 ,-1 , 0
  4242.5     .05       0  4713.6      .1       0  4820.3     .05       0
  5098.7    .035       0  5104.7     .05       0  5177.2      .1       0
Bank Sta=5098.7,5104.7
XS Rating Curve= 0 ,0
Exp/Cntr=0.3,0.1

Type RM Length L Ch R = 1 ,7293    ,290,290,290
BEGIN DESCRIPTION:
UNT 020 IN RACR 12.0
END DESCRIPTION:
XS GIS Cut Line= 5
       2234781.5     13246709.87      2234427.29     13246564.01
      2234104.38     13246590.06        2233620.     13246985.89
        2233193.     13247261.88
#Sta/Elev= 30
  4129.1   317.8  4349.5  303.63  4500.9  296.35  4579.8  294.53  4735.8  293.47
  4762.5  292.16  4782.6  293.68  4966.4  294.17  4998.6   289.6  5001.3   289.1
  5004.6   289.6  5009.5  291.41  5015.9  290.33  5030.3  291.05  5038.2  292.72
  5129.4  292.62    5258  295.51  5349.8  298.44  5407.2  301.61    5428  301.21
  5471.5  303.51  5477.5  302.82  5595.4  308.12  5658.9  309.35  5689.2  311.38
  5767.7  312.92  5782.9  314.23  5788.8  313.45    5804  314.87  5970.1  319.52
#Mann= 4 ,-1 , 0
  4129.1     .05       0  4579.8      .1       0  4998.6     .07       0
  5004.6      .1       0
Bank Sta=4998.6,5004.6
XS Rating Curve= 0 ,0
Exp/Cntr=0.3,0.1

Type RM Length L Ch R = 1 ,7003    ,915,915,915
BEGIN DESCRIPTION:
UNT 020 IN RACR 11.0
END DESCRIPTION:
XS GIS Cut Line= 4
       2234755.2      13246609.9      2234142.21     13246369.24
       2233685.9     13246489.56      2233197.83     13246777.86
#Sta/Elev= 30
  4052.3  314.61  4167.8  306.86  4328.9   298.5  4413.5  295.51  4522.3  291.98
    4533  292.89  4715.7  291.48  4787.9  292.48  4876.9  291.97    4912  292.87
  4952.3  290.45  4997.8  289.95    5002  288.24  5004.8  287.74    5008  288.24
  5015.4  290.25  5032.9  290.06  5038.1  291.13  5192.7  296.89  5229.7  297.47
  5251.2  299.64  5266.8  299.44  5362.4  306.02  5426.8  307.77    5471  310.69
  5479.5  309.43  5506.7  311.68  5559.5  312.81  5587.1  314.49  5749.6   320.1
#Mann= 4 ,-1 , 0
  4052.3     .05       0  4413.5      .1       0    5002     .07       0
    5008      .1       0
Bank Sta=5002,5008
XS Rating Curve= 0 ,0
Exp/Cntr=0.3,0.1

Type RM Length L Ch R = 1 ,6088    ,438,438,438
BEGIN DESCRIPTION:
Mapping XS 6934f8e0
END DESCRIPTION:
XS GIS Cut Line= 5
      2234927.26     13246381.69      2234640.83     13246136.93
      2234031.46      13245991.1      2233692.92     13246100.47
      2233131.58     13246448.71
#Sta/Elev= 30
  4479.2  322.42  4836.7  303.51  4854.7  301.06  4931.1  295.58  4951.7  289.99
  4959.4  289.64  4982.5  286.84  4999.3  286.31  5002.1  285.81  5005.3  286.31
    5034  287.98  5105.9  287.75    5291  291.42  5648.5  293.97  5738.7   296.2
  5749.8  295.27  5781.9  297.46  5813.9  296.97  5855.1  299.63    5861  298.29
  5876.4  299.45  5882.2  298.23  5940.1  301.47  6202.4  306.73  6260.2  309.33
  6275.6  311.21  6433.8  315.33  6456.4  316.37  6464.6  317.98  6498.9  318.67
#Mann= 4 ,-1 , 0
  4479.2     .05       0  4959.4      .1       0  4999.3     .07       0
  5005.3      .1       0
Bank Sta=4999.3,5005.3
XS Rating Curve= 0 ,0
Exp/Cntr=0.3,0.1

Type RM Length L Ch R = 1 ,5650    ,724,724,724
BEGIN DESCRIPTION:
UNT 020 IN RACR 10.0
END DESCRIPTION:
XS GIS Cut Line= 4
      2235286.01     13246025.93      2234726.12     13245691.73
      2234435.32     13245691.73      2233146.28     13246338.42
#Sta/Elev= 30
  4192.4  321.37  4262.5  317.74  4283.9  318.27  4299.5  316.42  4379.3   314.3
  4388.4  312.91  4431.8  313.13  4591.4  307.29  4643.9  306.86  4852.8  297.84
  4872.8  298.03  4912.8  295.95  4942.8   292.5  4962.8     289  4979.8  283.47
  4982.6  282.97  4985.8  283.47  5022.8  286.75  5062.8  285.52  5345.1  290.66
  5762.3   293.8  5846.1  294.98  5913.1  298.14  5949.3  297.28  6024.8   300.7
  6091.8  300.09  6136.5  302.45  6396.8  309.03  6426.9  311.51  6577.4  316.98
#Mann= 3 ,-1 , 0
  4192.4      .1       0  4979.8     .07       0  4985.8      .1       0
Bank Sta=4979.8,4985.8
XS Rating Curve= 0 ,0
Exp/Cntr=0.3,0.1

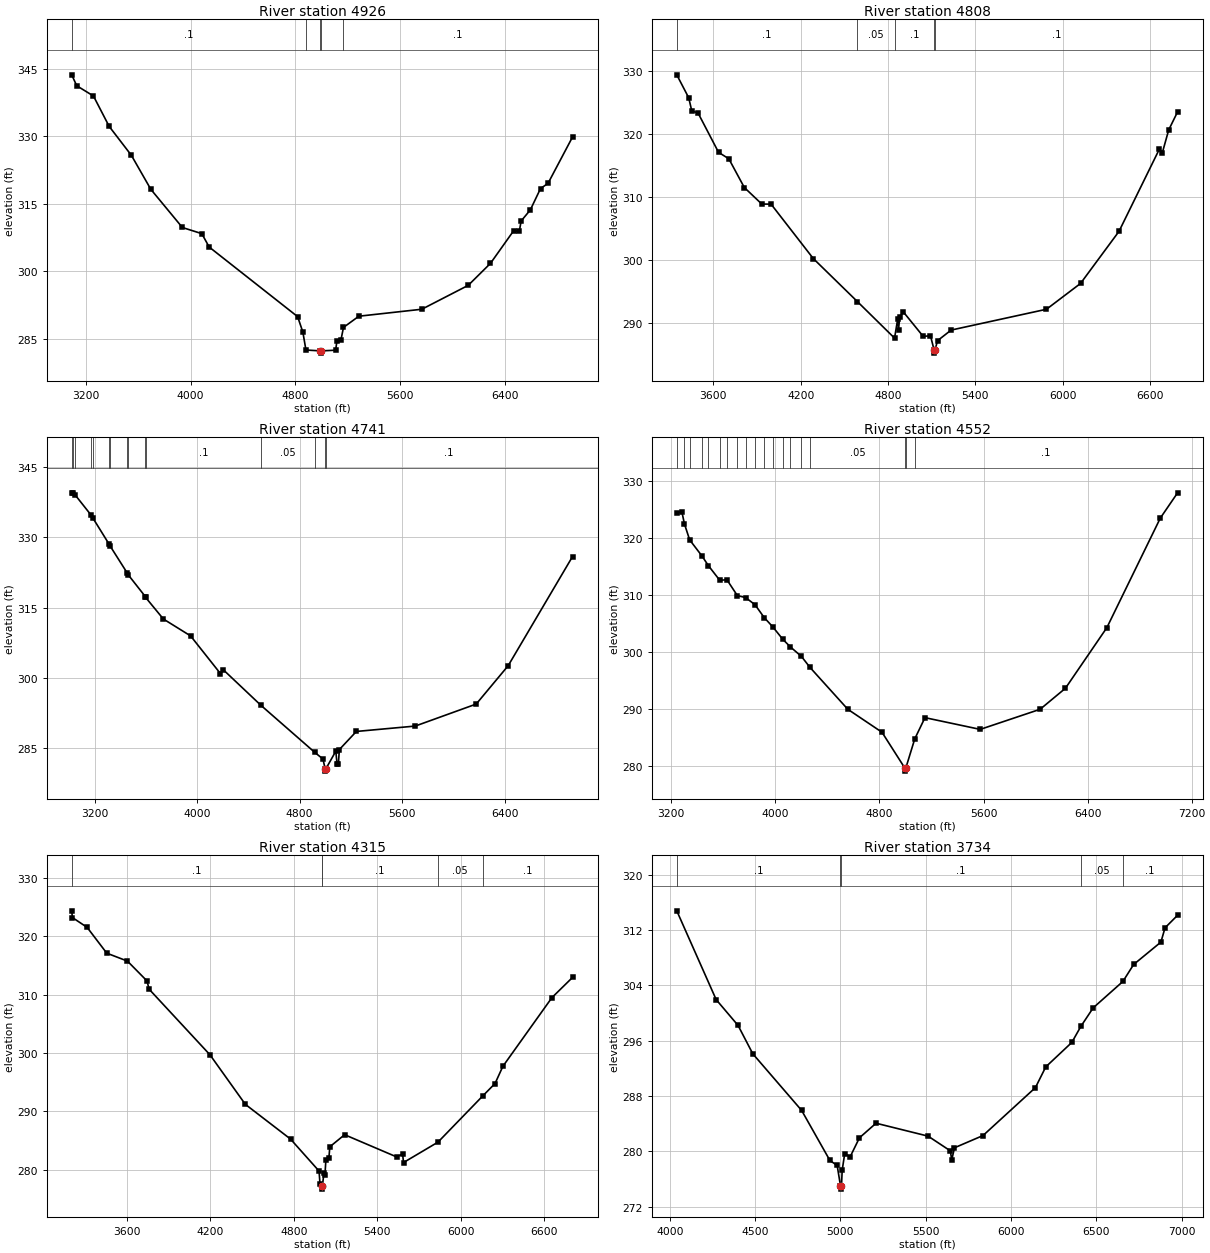
Type RM Length L Ch R = 1 ,4926    ,118,118,118
BEGIN DESCRIPTION:
UNT 020 IN RACR 9.0
END DESCRIPTION:
XS GIS Cut Line= 6
      2235749.53     13246389.41       2234780.8     13245337.35
      2234565.82     13245161.05      2234192.56     13245143.69
      2232937.05     13246248.81      2232881.26     13246294.46
#Sta/Elev= 30
  3091.6  343.66  3130.1  341.23  3257.7  338.95  3377.9  332.19  3547.5  325.76
  3696.1   318.2  3937.1  309.71  4085.7  308.34  4141.8  305.37  4817.9  289.88
  4857.9  286.43  4881.3  282.46  4992.4  282.27  4995.2  281.77  4998.4  282.27
  5108.2  282.42  5118.2  284.48  5148.2  284.62  5168.2  287.49  5285.7  289.98
  5766.8  291.53  6121.6  296.85  6291.4  301.74  6468.8  309.01  6511.5  308.82
  6525.4  311.15    6596  313.63  6673.8  318.38  6730.7  319.51  6918.1  329.83
#Mann= 5 ,-1 , 0
  3091.6      .1       0  4881.3     .05       0  4992.4    .033       0
  4998.4     .05       0  5168.2      .1       0
Bank Sta=4992.4,4998.4
XS Rating Curve= 0 ,0
Exp/Cntr=0.3,0.1

Type RM Length L Ch R = 1 ,4808    ,67,67,67
BEGIN DESCRIPTION:
Mapping XS cad8d48e
END DESCRIPTION:
XS GIS Cut Line= 5
      2235546.41     13246104.04      2234578.55     13245084.09
      2234430.98     13245040.69      2234226.98     13245036.35
      2232912.27      13246077.7
#Sta/Elev= 30
  3348.3  329.37  3430.2  325.73  3451.6  323.62  3494.1  323.32  3635.3  317.06
    3706  316.03  3812.4  311.47  3932.5  308.84  3996.1  308.83  4286.1  300.19
  4589.2  293.35  4844.7  287.54  4866.7  290.65  4871.9  288.89  4880.3   290.9
  4905.2   291.7  5041.5  287.82  5091.5  287.92  5116.4  285.66  5119.1  285.16
  5122.4  285.66  5140.2  287.14  5233.2  288.82  5888.6  292.13  6122.6  296.23
    6387  304.51  6664.3  317.57  6685.1  317.03  6728.4  320.62  6789.4  323.49
#Mann= 5 ,-1 , 0
  3348.3      .1       0  4589.2     .05       0  4844.7      .1       0
  5116.4     .07       0  5122.4      .1       0
Bank Sta=5116.4,5122.4
XS Rating Curve= 0 ,0
Exp/Cntr=0.3,0.1

Type RM Length L Ch R = 1 ,4741    ,189,189,189
BEGIN DESCRIPTION:
Mapping XS d692bde8
END DESCRIPTION:
XS GIS Cut Line= 6
      2235758.26     13246297.66      2234497.82     13244985.14
      2234195.73     13244959.09      2233997.82     13244969.51
      2233747.82     13245255.97      2232815.54     13246021.58
#Sta/Elev= 30
  3022.1   339.4  3032.2  339.49  3048.9  339.04  3173.2  334.74  3186.4  334.15
  3314.3  328.51  3323.9  328.05  3455.3  322.37  3461.3  322.05  3596.3  317.35
  3598.8  317.16  3737.4  312.55  3949.6  308.95    4183  300.89  4204.1  301.74
  4498.5  294.13  4919.1  284.07  4982.5  282.67  4999.5  280.58  5002.3  280.08
  5005.5  280.58  5082.8  284.34  5092.9  281.53  5102.9  281.55  5110.4  284.68
  5243.2  288.55  5702.7   289.7  6178.4   294.4  6427.4  302.57  6929.8  325.88
#Mann= 15 ,-1 , 0
  3022.1      .1       0  3032.2     .05       0  3048.9      .1       0
  3173.2     .05       0  3186.4      .1       0  3314.3     .05       0
  3323.9      .1       0  3455.3     .05       0  3461.3      .1       0
  3596.3     .05       0  3598.8      .1       0  4498.5     .05       0
  4919.1      .1       0  4999.5     .07       0  5005.5      .1       0
Bank Sta=4999.5,5005.5
XS Rating Curve= 0 ,0
Exp/Cntr=0.3,0.1

Type RM Length L Ch R = 1 ,4552    ,237,237,237
BEGIN DESCRIPTION:
UNT 020 IN RACR 8.0
END DESCRIPTION:
XS GIS Cut Line= 6
       2235520.4     13246030.08      2234431.84     13244800.89
      2234187.05     13244774.85      2233812.05     13244764.43
      2233395.39     13245087.35      2232692.46     13245878.79
#Sta/Elev= 30
  3242.6  324.53  3282.3  324.61  3301.6  322.53  3341.6  319.74  3437.2  316.88
  3484.9  315.23  3572.7  312.65  3628.1  312.73  3708.3  309.95  3771.3  309.61
  3843.9  308.35  3914.6  306.09  3979.4  304.49  4057.8  302.27    4115  300.96
  4201.1  299.26  4266.5  297.34    4557  289.99  4819.6  285.96  4996.3  279.63
    4999  279.13  5002.3  279.63  5071.5  284.79    5150  288.52  5574.6  286.46
    6035  289.99  6229.5  293.68  6548.1  304.33  6958.7  323.56  7091.5     328
#Mann= 19 ,-1 , 0
  3242.6      .1       0  3301.6     .05       0  3341.6      .1       0
  3437.2     .05       0  3484.9      .1       0  3572.7     .05       0
  3628.1      .1       0  3708.3     .05       0  3771.3      .1       0
  3843.9     .05       0  3914.6      .1       0  3979.4     .05       0
  4057.8      .1       0    4115     .05       0  4201.1      .1       0
  4266.5     .05       0  4996.3     .04       0  5002.3     .05       0
  5071.5      .1       0
Bank Sta=4996.3,5002.3
XS Rating Curve= 0 ,0
Exp/Cntr=0.3,0.1

Type RM Length L Ch R = 1 ,4315    ,581,581,581
BEGIN DESCRIPTION:
UNT 020 IN RACR 7.0
END DESCRIPTION:
XS GIS Cut Line= 4
      2235593.32     13245858.21      2234265.18     13244467.56
      2233853.72     13244024.85       2232838.1     13243665.48
#Sta/Elev= 30
  3201.1  324.38  3205.9  323.23  3312.2  321.54  3453.4  317.12  3602.2  315.76
  3743.4  312.35  3757.6  310.96  4196.3  299.69  4450.8   291.2  4776.3  285.24
  4981.4  279.76  4988.3  277.54  4999.4  277.16  5002.2  276.66  5005.4  277.16
  5016.6  279.43  5023.8  279.03  5030.7  281.73  5052.1  281.94    5059  283.92
  5165.5  285.99  5540.2  282.18  5582.7  282.69  5589.5  281.22  5837.6  284.72
  6158.5  292.61  6248.2  294.77  6304.7  297.72  6657.7   309.5  6805.8  312.96
#Mann= 5 ,-1 , 0
  3201.1      .1       0  4999.4     .07       0  5005.4      .1       0
  5837.6     .05       0  6158.5      .1       0
Bank Sta=4999.4,5005.4
XS Rating Curve= 0 ,0
Exp/Cntr=0.3,0.1

Type RM Length L Ch R = 1 ,3734    ,455,455,455
BEGIN DESCRIPTION:
UNT 020 IN RACR 6.0
END DESCRIPTION:
XS GIS Cut Line= 4
       2235337.7     13244546.84      2234624.55     13244050.89
      2234447.47     13243977.97      2232713.07     13243264.42
#Sta/Elev= 30
  4041.3  314.76  4272.2  301.92  4400.5  298.19  4486.9  294.09  4773.2   285.9
    4939  278.66  4981.5  277.94  5000.8  275.02  5003.6  274.52  5006.8  275.02
  5010.9  277.26  5025.5  279.62  5057.9  279.21    5112  281.94  5209.3  284.05
  5514.6  282.18  5645.2  280.05  5652.7  278.71  5669.2   280.5  5836.5  282.27
  6143.6   289.2  6204.1  292.19  6356.9  295.73  6409.9  298.05  6482.1  300.73
  6656.4  304.55  6719.3     307  6879.2  310.24  6903.2   312.3  6976.9  314.12
#Mann= 5 ,-1 , 0
  4041.3      .1       0  5000.8     .07       0  5006.8      .1       0
  6409.9     .05       0  6656.4      .1       0
Bank Sta=5000.8,5006.8
XS Rating Curve= 0 ,0
Exp/Cntr=0.3,0.1

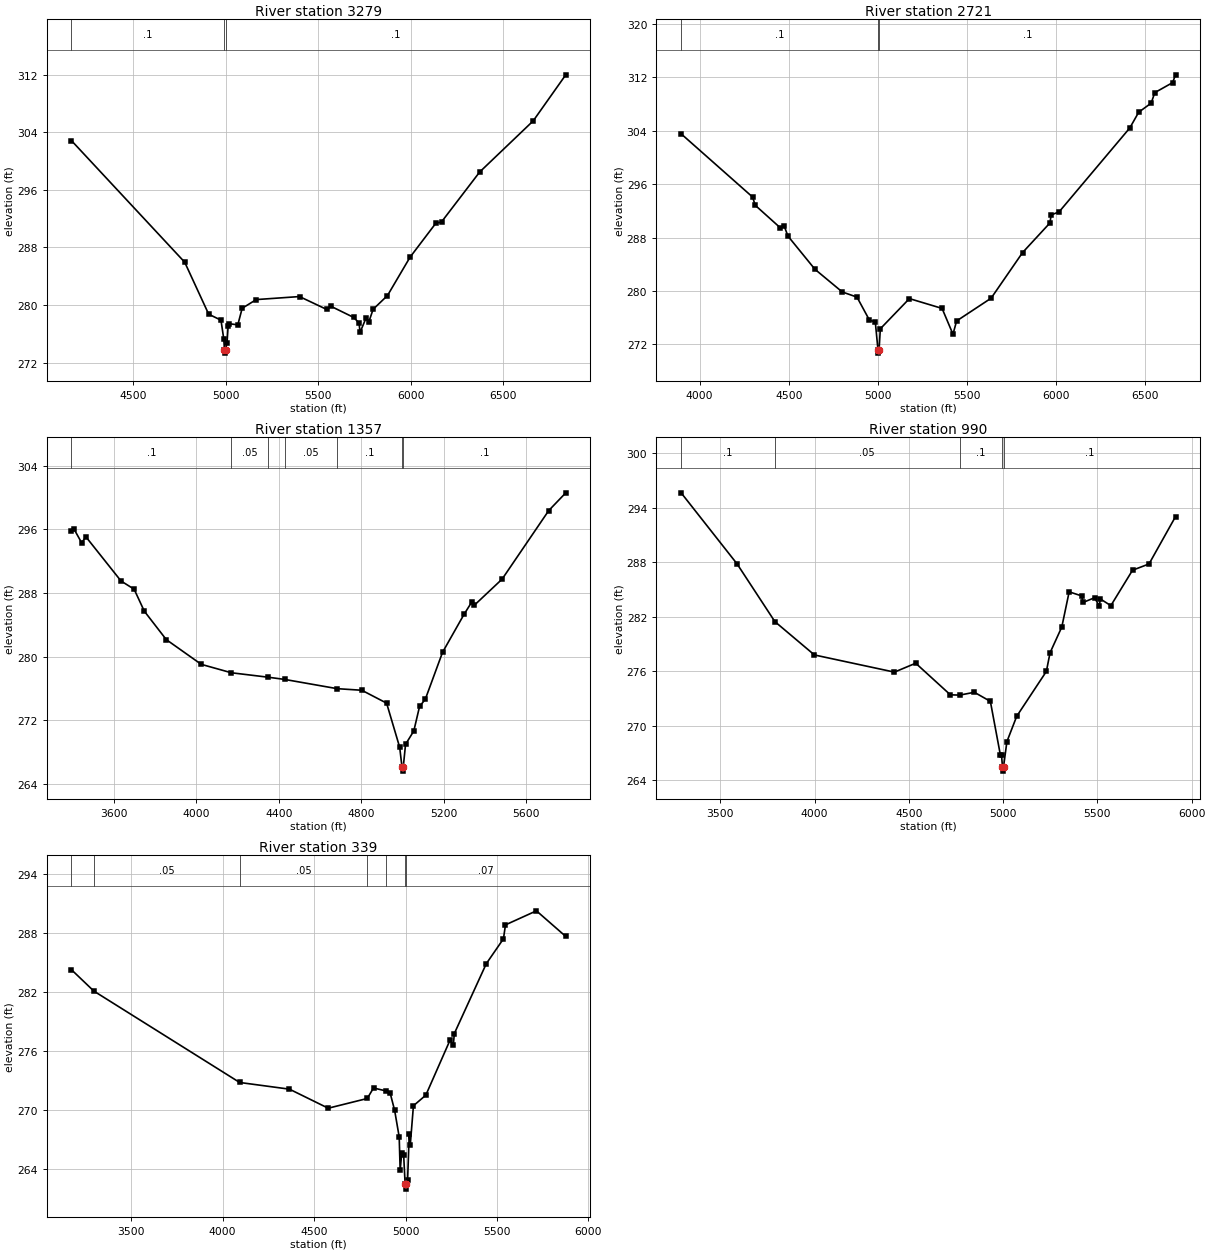
Type RM Length L Ch R = 1 ,3279    ,558,558,558
BEGIN DESCRIPTION:
UNT 020 IN RACR 5.0
END DESCRIPTION:
XS GIS Cut Line= 3
      2235390.51     13243937.11      2233827.98     13243264.35
      2232887.21     13243021.57
#Sta/Elev= 30
  4164.7  302.85  4777.4  285.94    4907  278.72  4973.4  277.89  4988.5  275.29
  4992.2  273.81  4994.9  273.31  4998.2  273.81  5006.1  274.76    5012  277.04
  5017.4   277.4  5064.5  277.24    5088  279.54  5164.1  280.75    5398  281.17
  5544.3  279.39  5567.8  279.82  5690.9  278.27  5719.9   277.5  5725.3  276.19
  5757.3  278.16  5772.4  277.62  5795.9   279.4  5873.6  281.31  5995.6  286.64
  6134.7  291.35  6165.7  291.54  6372.2  298.48  6661.4  305.58  6837.5  311.98
#Mann= 3 ,-1 , 0
  4164.7      .1       0  4992.2     .07       0  4998.2      .1       0
Bank Sta=4992.2,4998.2
XS Rating Curve= 0 ,0
Exp/Cntr=0.3,0.1

Type RM Length L Ch R = 1 ,2721    ,1364,1364,1364
BEGIN DESCRIPTION:
UNT 020 IN RACR 4.0
END DESCRIPTION:
XS GIS Cut Line= 4
      2235507.67     13243624.61      2235017.21     13243138.49
      2233563.22     13242852.03       2232961.3     13242873.68
#Sta/Elev= 30
  3896.3  303.54  4297.7  294.06  4311.9  292.84  4453.3  289.45  4474.5  289.75
  4495.7  288.22  4647.5  283.24  4800.4  279.85  4883.4  279.07  4953.3  275.62
  4986.1  275.35  5001.2  271.18    5004  270.68  5007.2  271.18  5014.4  274.33
  5177.5  278.85  5360.9  277.38  5422.1  273.51  5442.5   275.5  5636.1  278.91
  5812.8  285.75  5966.8   290.2  5972.5  291.37  6018.1  291.86  6414.5  304.42
  6464.6  306.78  6534.6  308.14  6554.6  309.71  6654.7  311.21  6671.1  312.38
#Mann= 3 ,-1 , 0
  3896.3      .1       0  5001.2     .07       0  5007.2      .1       0
Bank Sta=5001.2,5007.2
XS Rating Curve= 0 ,0
Exp/Cntr=0.3,0.1

Type RM Length L Ch R = 1 ,1357    ,367,367,367
BEGIN DESCRIPTION:
UNT 020 IN RACR 3.0
END DESCRIPTION:
XS GIS Cut Line= 4
      2235337.72     13243246.86      2234137.72     13242146.85
      2233837.72     13242096.85      2233393.23     13242236.37
#Sta/Elev= 30
  3394.1  295.84    3408     296  3443.7  294.33  3464.7  295.07  3634.9  289.52
  3698.4  288.49  3747.7  285.73  3854.4  282.15    4024  279.04    4170  277.98
  4348.9  277.42  4429.2  277.14  4683.3  275.98  4802.8  275.78    4923  274.16
  4986.5   268.6  4997.7  266.11  5000.5  265.61  5003.7  266.11  5014.9  268.98
  5054.9  270.66  5082.8  273.74  5110.7  274.65  5194.3  280.55  5298.2  285.31
  5336.6   286.9  5347.6  286.45  5483.3  289.76  5709.4  298.38    5792  300.61
#Mann= 7 ,-1 , 0
  3394.1      .1       0    4170     .05       0  4348.9      .1       0
  4429.2     .05       0  4683.3      .1       0  4997.7     .07       0
  5003.7      .1       0
Bank Sta=4997.7,5003.7
XS Rating Curve= 0 ,0
Exp/Cntr=0.3,0.1

Type RM Length L Ch R = 1 ,990     ,651,651,651
BEGIN DESCRIPTION:
UNT 020 IN RACR 2.0
END DESCRIPTION:
XS GIS Cut Line= 5
      2235537.73     13243046.86      2234337.72     13241846.85
      2233987.72     13241746.85      2233910.78     13241957.69
      2233592.52     13242069.08
#Sta/Elev= 30
  3291.7  295.67  3588.7  287.84  3789.1  281.49  3998.8  277.82  4423.1  275.93
  4536.2  276.91  4720.1  273.43  4769.5   273.4  4847.3  273.71  4932.2  272.71
  4985.2  266.82  4991.4  266.82  4996.2  265.53  4998.9  265.03  5002.2  265.53
    5020  268.28    5072  271.07  5229.3  276.01  5248.8  278.06  5311.2   280.9
  5350.2  284.77  5416.6  284.32  5423.8   283.6  5484.9  284.12  5510.2   283.2
  5515.5  283.99  5571.3  283.25  5686.4  287.15  5773.9  287.84  5914.4  293.05
#Mann= 5 ,-1 , 0
  3291.7      .1       0  3789.1     .05       0  4769.5      .1       0
  4996.2     .07       0  5002.2      .1       0
Bank Sta=4996.2,5002.2
XS Rating Curve= 0 ,0
Exp/Cntr=0.3,0.1

Type RM Length L Ch R = 1 ,339     ,0,0,0
BEGIN DESCRIPTION:
UNT 020 IN RACR 1.0
END DESCRIPTION:
XS GIS Cut Line= 4
      2235587.11     13242433.14      2234472.91     13241318.94
      2234116.91     13241184.73      2233818.68       13241869.
#Sta/Elev= 30
  3173.3  284.31  3295.9  282.13  4093.3  272.82  4365.3  272.14  4577.4   270.2
  4790.7  271.19  4824.9  272.26  4893.1  271.96  4915.5  271.77  4940.4  269.98
  4965.3  267.28  4970.6  263.87    4979   265.6  4989.7  265.44  4997.8  262.46
  5000.5  261.96  5003.8  262.46  5011.1  262.84  5020.3  267.59  5025.7  266.42
  5043.1  270.45  5110.9  271.53  5243.2  277.13  5261.2  276.62  5266.6   277.8
  5441.5  284.92  5535.2  287.45  5546.3  288.87  5715.5   290.3  5875.9  287.69
#Mann= 7 ,-1 , 0
  3173.3      .1       0  3295.9     .05       0  4093.3     .05       0
  4790.7     .05       0  4893.1     .06       0  4997.8     .07       0
  5003.8     .07       0
Bank Sta=4997.8,5003.8
XS Rating Curve= 0 ,0
Exp/Cntr=0.3,0.1

Chan Stop Cuts=-1
Use User Specified Reach Order=0
Composite Channel Slope=5