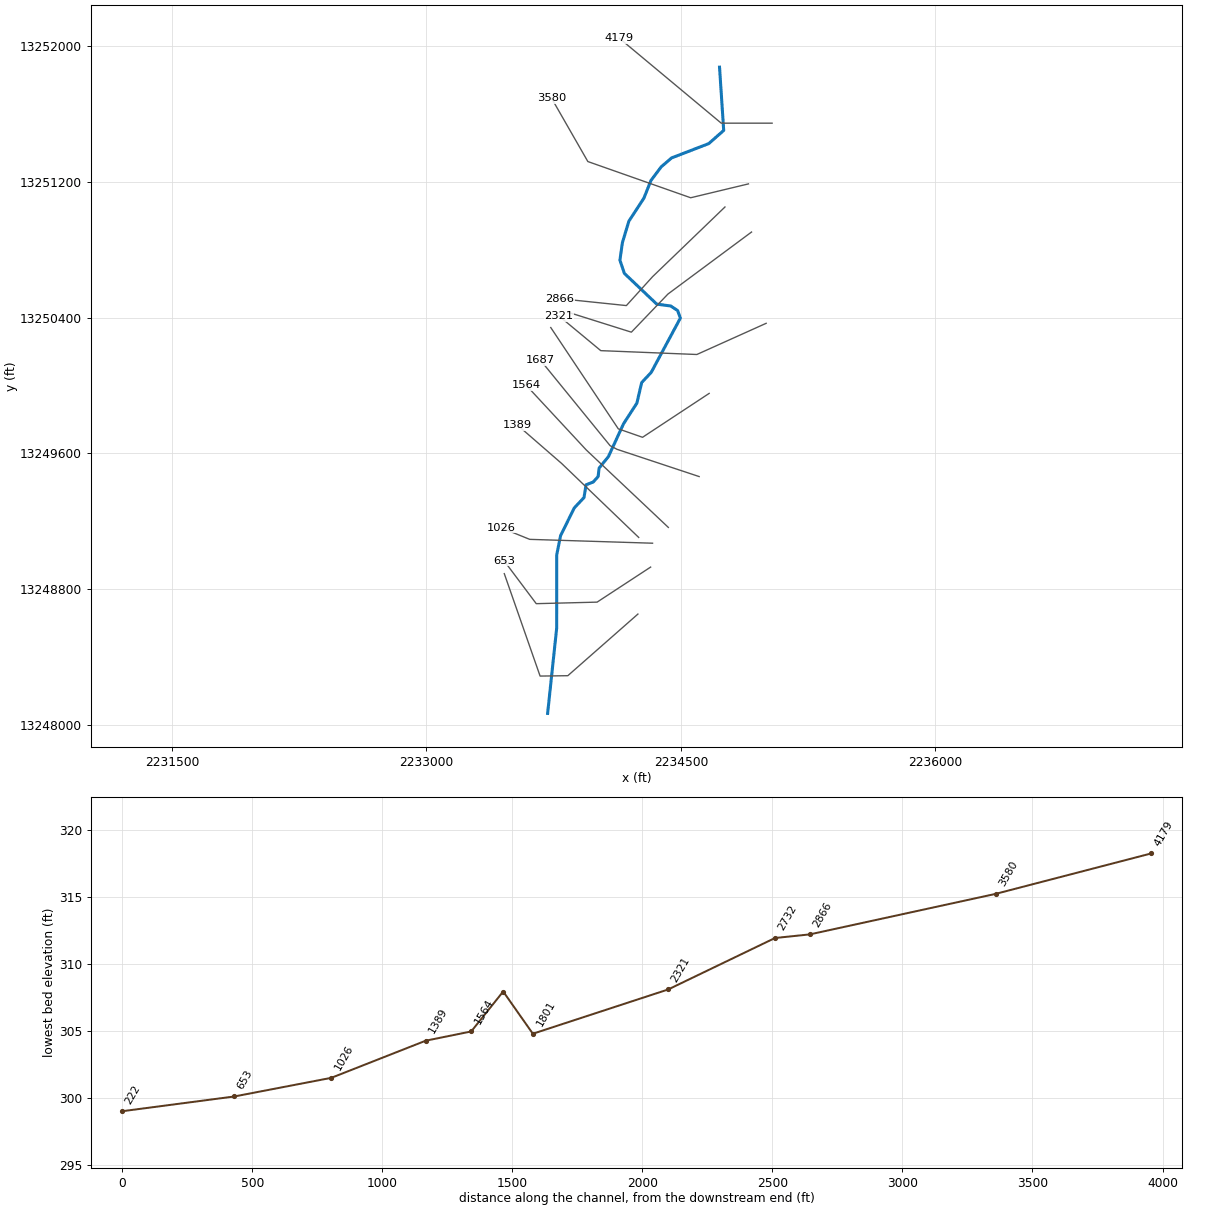
--- UNT 021 IN RACR.prj (project) ---

Proj Title=UNT 021 IN RACR Base Level Engineering
Current Plan=p01
Default Exp/Contr=0.3,0.1
English Units
Geom File=g01
Flow File=f01
Plan File=p01
BEGIN DESCRIPTION:
UNT 021 IN RACR
END DESCRIPTION:

--- UNT 021 IN RACR.p01 (plan) ---

Plan Title=Multiple Run
Short Identifier=Multiple
Geom File=g01
Flow File=f01
Subcritical Flow
K Sum by GR= 0
Std Step Tol= 0.01
Critical Tol= 0.01
Num of Std Step Trials= 20
Max Error Tol= 0.3
Flow Tol Ratio= 0.001
Split Flow NTrial= 30
Split Flow Tol= 0.02
Split Flow Ratio= 0.02
Log Output Level= 0
Friction Slope Method= 1
Unsteady Friction Slope Method= 2
Unsteady Bridges Friction Slope Method= 1
Parabolic Critical Depth
Global Vel Dist=  1 , 1 , 1
Global Log Level= 0
CheckData=True
Encroach Param= -1, 0, 0, 0
BEGIN DESCRIPTION:
Multiple Run
END DESCRIPTION:

--- UNT 021 IN RACR.f01 (steady flow) ---

Flow Title=Multiple
Number of Profiles=7
Profile Names=10-year,25-year,50-year,1pct_min,100-year,1pct_plu,500-year
River Rch & RM= UNT 021 IN RACR,Reach-1,4179
     258     361     448     408     552     747     854
Boundary for River Rch & Prof#=UNT 021 IN RACR,Reach-1,1
Up Type=0
Dn Type=3
Dn Slope=0.005
Boundary for River Rch & Prof#=UNT 021 IN RACR,Reach-1,2
Up Type=0
Dn Type=3
Dn Slope=0.005
Boundary for River Rch & Prof#=UNT 021 IN RACR,Reach-1,3
Up Type=0
Dn Type=3
Dn Slope=0.005
Boundary for River Rch & Prof#=UNT 021 IN RACR,Reach-1,4
Up Type=0
Dn Type=3
Dn Slope=0.005
Boundary for River Rch & Prof#=UNT 021 IN RACR,Reach-1,5
Up Type=0
Dn Type=3
Dn Slope=0.005
Boundary for River Rch & Prof#=UNT 021 IN RACR,Reach-1,6
Up Type=0
Dn Type=3
Dn Slope=0.005
Boundary for River Rch & Prof#=UNT 021 IN RACR,Reach-1,7
Up Type=0
Dn Type=3
Dn Slope=0.005

--- UNT 021 IN RACR.g01 (geometry) ---

Geom Title=Existing Conditions

River Reach=UNT 021 IN RACR,Reach-1
Reach XY= 30
      2234727.72     13251876.86      2234752.25     13251504.13
      2234664.36     13251426.31      2234445.26     13251342.00
      2234383.10     13251288.56      2234323.56     13251209.17
      2234281.80     13251104.59      2234193.36     13250969.23
      2234155.10     13250842.51      2234140.51     13250739.04
      2234166.90     13250661.26      2234357.55     13250480.18
      2234440.11     13250469.07      2234480.78     13250442.11
      2234496.83     13250397.77      2234325.15     13250077.92
      2234268.75     13250017.75      2234240.51     13249896.68
      2234161.35     13249773.76      2234072.46     13249580.70
      2234017.91     13249513.79      2234012.17     13249464.16
      2233983.63     13249431.82      2233940.87     13249414.94
      2233928.84     13249340.00      2233871.28     13249278.46
      2233790.85     13249115.46      2233767.85     13249001.91
      2233767.73     13248570.46      2233714.40     13248067.68

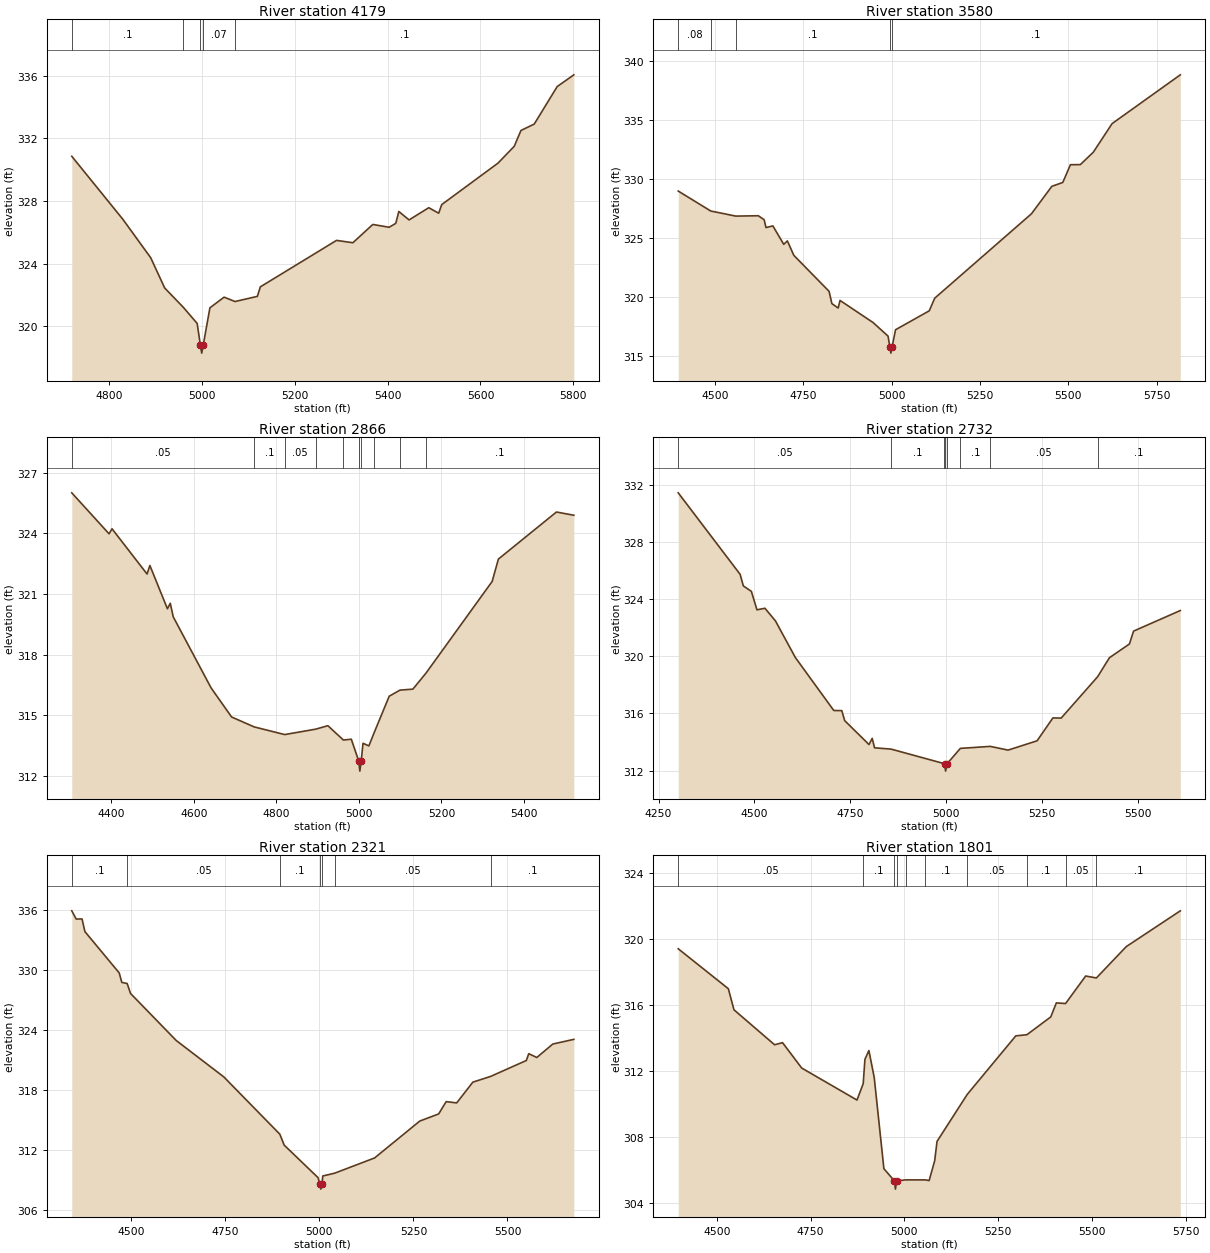
Type RM Length L Ch R = 1,4179,599,599,599
BEGIN DESCRIPTION:
UNT 021 IN RACR 8.0
END DESCRIPTION:
XS GIS Cut Line= 3
      2235037.76     13251546.85      2234737.72     13251546.85
      2234137.69     13252046.88
#Sta/Elev= 30
  4719.9  330.86  4829.9  326.83  4889.9  324.37  4919.9  322.44  4960.4  321.19
  4989.9  320.17  4996.9  318.77  4999.7  318.27  5002.9  318.77  5017.4  321.17
  5047.9  321.85  5071.5  321.57  5119.5  321.90  5126.0  322.51  5290.0  325.48
  5325.2  325.33  5368.1  326.50  5403.3  326.32  5417.6  326.57  5424.1  327.33
  5446.2  326.79  5488.6  327.57  5510.0  327.22  5516.5  327.77  5637.6  330.42
  5672.7  331.50  5687.1  332.51  5715.7  332.92  5765.2  335.32  5801.0  336.07
#Mann=5,-1,0
  4719.9     0.1       0  4960.4    0.07       0  4996.9    0.07       0
  5002.9    0.07       0  5071.5     0.1       0
Bank Sta=4996.9,5002.9
Exp/Cntr=0.3,0.1

Type RM Length L Ch R = 1,3580,714,714,714
BEGIN DESCRIPTION:
UNT 021 IN RACR 7.0
END DESCRIPTION:
XS GIS Cut Line= 4
      2234898.19     13251188.88      2234557.65     13251107.15
      2233951.51     13251320.55      2233738.39     13251692.39
#Sta/Elev= 30
  4395.8  328.97  4487.9  327.28  4558.9  326.85  4622.5  326.88  4639.1  326.54
  4644.2  325.88  4663.7  326.02  4694.5  324.46  4704.8  324.75  4723.0  323.53
  4822.9  320.48  4830.8  319.44  4848.6  319.07  4853.9  319.71  4947.4  317.84
  4989.8  316.69  4995.1  315.75  4997.8  315.25  5001.1  315.75  5011.0  317.23
  5106.4  318.83  5121.9  319.90  5395.9  327.05  5453.5  329.37  5484.5  329.70
  5506.1  331.20  5534.2  331.21  5570.9  332.26  5624.1  334.68  5817.2  338.81
#Mann=5,-1,0
  4395.8    0.08       0  4487.9    0.05       0  4558.9     0.1       0
  4995.1    0.07       0  5001.1     0.1       0
Bank Sta=4995.1,5001.1
Exp/Cntr=0.3,0.1

Type RM Length L Ch R = 1,2866,134,134,134
BEGIN DESCRIPTION:
UNT 021 IN RACR 6.0
END DESCRIPTION:
XS GIS Cut Line= 4
      2234759.72     13251052.69      2234332.90     13250641.76
      2234178.53     13250471.50      2233785.76     13250512.36
#Sta/Elev= 30
  4303.7  326.01  4394.1  323.98  4401.3  324.23  4486.2  321.99  4493.1  322.41
  4535.6  320.27  4542.5  320.54  4549.7  319.87  4641.5  316.35  4691.2  314.91
  4745.9  314.42  4820.0  314.04  4895.5  314.31  4924.6  314.48  4962.2  313.77
  4981.4  313.81  4999.4  312.73  5002.1  312.23  5005.4  312.73  5009.8  313.61
  5024.0  313.48  5036.9  314.14  5073.3  315.94  5099.3  316.24  5130.7  316.29
  5162.7  317.09  5322.8  321.62  5338.0  322.73  5478.7  325.06  5520.9  324.90
#Mann=10,-1,0
  4303.7    0.05       0  4745.9     0.1       0  4820.0    0.05       0
  4895.5     0.1       0  4962.2    0.05       0  4999.4    0.04       0
  5005.4    0.05       0  5036.9     0.1       0  5099.3    0.05       0
  5162.7     0.1       0
Bank Sta=4999.4,5005.4
Exp/Cntr=0.3,0.1

Type RM Length L Ch R = 1,2732,411,411,411
BEGIN DESCRIPTION:
UNT 021 IN RACR 5.0
END DESCRIPTION:
XS GIS Cut Line= 4
      2234916.35     13250905.11      2234423.71     13250539.60
      2234208.04     13250314.85      2233841.49     13250430.25
#Sta/Elev= 30
  4301.4  331.42  4462.8  325.72  4471.2  324.91  4492.1  324.53  4506.7  323.24
  4527.5  323.35  4555.0  322.46  4606.9  319.90  4707.0  316.20  4727.9  316.19
  4735.5  315.49  4798.8  313.82  4807.2  314.25  4813.4  313.59  4856.4  313.50
  4995.5  312.48  4995.9  312.46  4998.6  311.96  5001.9  312.46  5037.0  313.55
  5115.0  313.69  5161.5  313.43  5237.1  314.08  5278.4  315.68  5300.0  315.67
  5395.0  318.56  5425.8  319.89  5477.9  320.85  5488.7  321.75  5610.6  323.19
#Mann=8,-1,0
  4301.4    0.05       0  4856.4     0.1       0  4995.5    0.05       0
  4995.9    0.03       0  5001.9    0.05       0  5037.0     0.1       0
  5115.0    0.05       0  5395.0     0.1       0
Bank Sta=4995.9,5001.9
Exp/Cntr=0.3,0.1

Type RM Length L Ch R = 1,2321,520,520,520
BEGIN DESCRIPTION:
UNT 021 IN RACR 4.0
END DESCRIPTION:
XS GIS Cut Line= 4
      2235002.60     13250367.06      2234593.98     13250183.18
      2234027.60     13250205.92      2233781.98     13250409.59
#Sta/Elev= 30
  4342.3  335.88  4354.1  335.06  4369.6  335.07  4377.2  333.81  4468.3  329.69
  4475.3  328.74  4489.5  328.63  4498.4  327.64  4619.7  322.95  4746.4  319.31
  4895.1  313.60  4906.7  312.51  4996.8  309.26  5001.2  308.62  5003.9  308.12
  5007.2  308.62  5009.2  309.43  5040.8  309.71  5146.9  311.23  5267.0  314.91
  5317.1  315.62  5337.1  316.85  5365.0  316.72  5408.0  318.79  5455.6  319.37
  5550.0  320.95  5556.5  321.63  5577.9  321.25  5620.3  322.59  5676.3  323.06
#Mann=7,-1,0
  4342.3     0.1       0  4489.5    0.05       0  4895.1     0.1       0
  5001.2    0.07       0  5007.2     0.1       0  5040.8    0.05       0
  5455.6     0.1       0
Bank Sta=5001.2,5007.2
Exp/Cntr=0.3,0.1

Type RM Length L Ch R = 1,1801,114,114,114
BEGIN DESCRIPTION:
Mapping XS 012f9476
END DESCRIPTION:
XS GIS Cut Line= 4
      2234666.59     13249953.87      2234273.88     13249695.09
      2234130.85     13249745.03      2233732.86     13250342.03
#Sta/Elev= 30
  4396.7  319.39  4530.3  316.97  4545.4  315.69  4653.8  313.57  4674.9  313.70
  4726.1  312.16  4873.5  310.22  4890.1  311.21  4894.7  312.69  4905.3  313.22
  4919.5  311.59  4945.3  306.06  4973.3  305.32  4976.1  304.82  4979.3  305.32
  5003.3  305.38  5055.5  305.38  5066.0  305.34  5080.8  306.54  5087.0  307.71
  5167.6  310.56  5297.1  314.11  5326.8  314.18  5390.5  315.26  5405.3  316.11
  5429.9  316.07  5483.6  317.74  5512.1  317.62  5591.8  319.52  5736.0  321.69
#Mann=10,-1,0
  4396.7    0.05       0  4890.1     0.1       0  4973.3    0.07       0
  4979.3     0.1       0  5003.3    0.05       0  5055.5     0.1       0
  5167.6    0.05       0  5326.8     0.1       0  5429.9    0.05       0
  5512.1     0.1       0
Bank Sta=4973.3,4979.3
Exp/Cntr=0.3,0.1

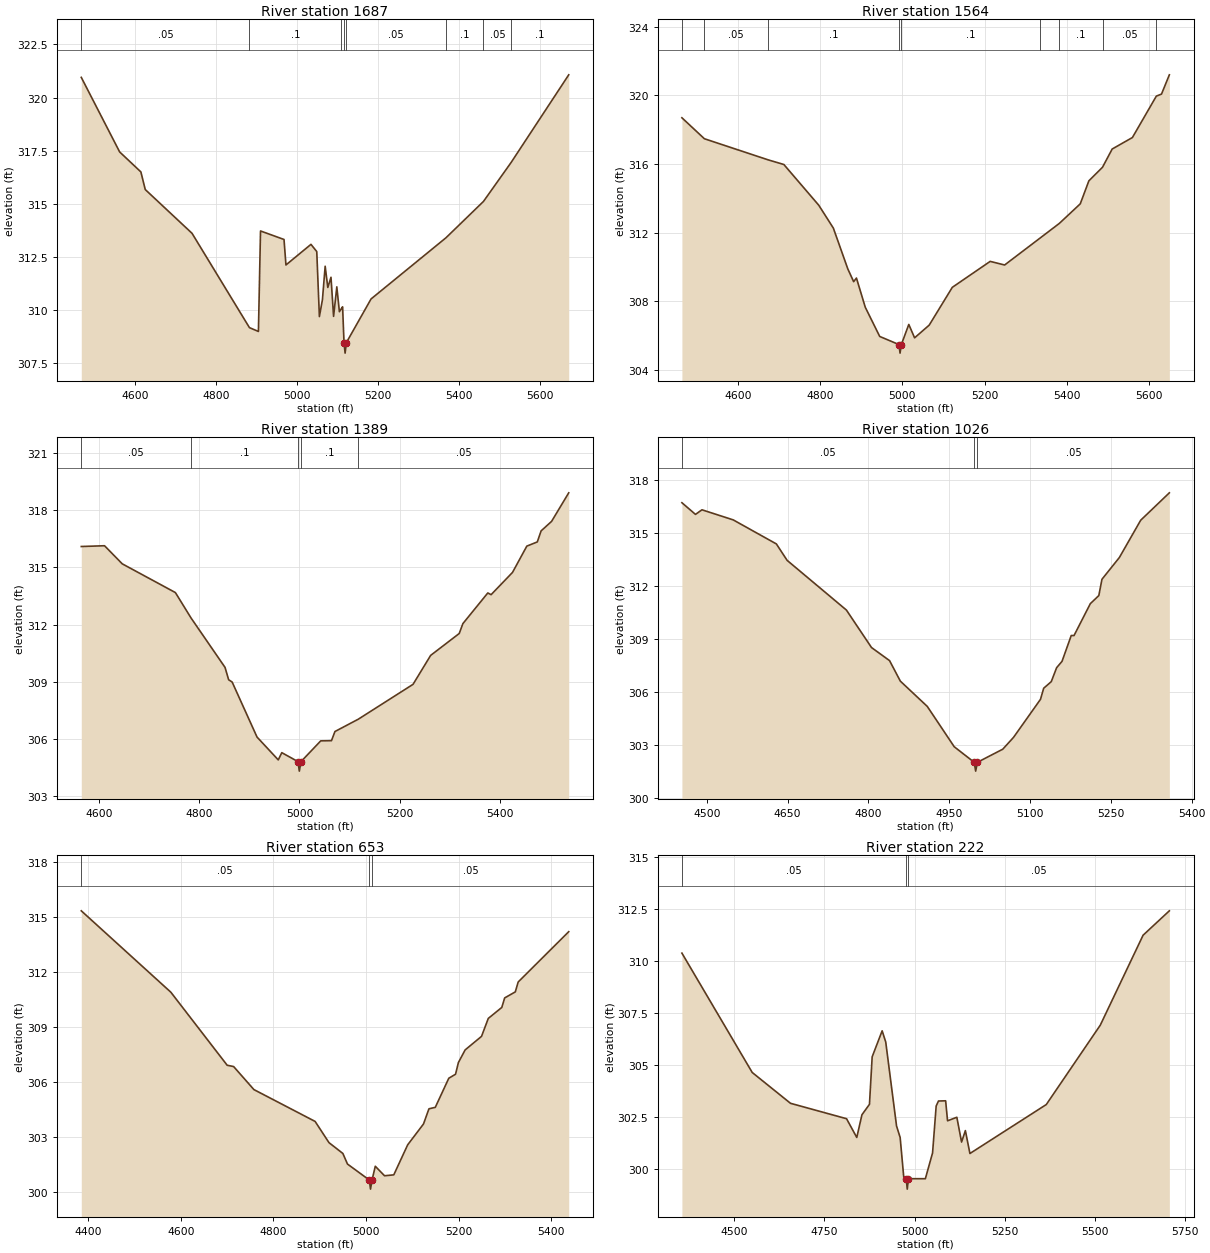
Type RM Length L Ch R = 1,1687,123,123,123
BEGIN DESCRIPTION:
Mapping XS aafc884a
END DESCRIPTION:
XS GIS Cut Line= 4
      2234607.65     13249463.60      2234123.70     13249624.19
      2234082.47     13249645.89      2233672.49     13250149.15
#Sta/Elev= 30
  4466.0  320.95  4560.9  317.44  4613.4  316.50  4624.2  315.67  4739.9  313.61
  4881.9  309.17  4904.1  308.99  4909.3  313.72  4967.4  313.32  4972.2  312.12
  5034.1  313.09  5048.4  312.75  5054.9  309.69  5062.4  310.48  5069.2  312.06
  5075.7  311.06  5083.6  311.54  5090.0  309.70  5098.0  311.09  5104.4  309.92
  5109.5  310.07  5112.3  310.15  5115.8  308.47  5118.5  307.97  5121.8  308.47
  5182.7  310.52  5368.0  313.40  5460.7  315.11  5529.3  316.95  5671.6  321.07
#Mann=8,-1,0
  4466.0    0.05       0  4881.9     0.1       0  5109.5    0.05       0
  5115.8    0.07       0  5121.8    0.05       0  5368.0     0.1       0
  5460.7    0.05       0  5529.3     0.1       0
Bank Sta=5115.8,5121.8
Exp/Cntr=0.3,0.1

Type RM Length L Ch R = 1,1564,175,175,175
BEGIN DESCRIPTION:
UNT 021 IN RACR 3.0
END DESCRIPTION:
XS GIS Cut Line= 3
      2234425.96     13249163.88      2233942.43     13249620.17
      2233586.90     13250002.88
#Sta/Elev= 30
  4463.0  318.69  4517.7  317.47  4673.1  316.24  4711.3  315.97  4796.3  313.60
  4831.8  312.27  4867.1  309.89  4881.3  309.15  4888.1  309.36  4909.6  307.66
  4944.8  305.96  4991.5  305.49  4994.3  304.99  4997.5  305.49  5015.6  306.66
  5029.7  305.88  5065.3  306.62  5121.6  308.82  5213.8  310.33  5249.0  310.12
  5336.0  311.70  5382.2  312.54  5433.2  313.68  5454.2  315.02  5487.4  315.81
  5510.9  316.87  5560.2  317.54  5618.5  319.95  5631.1  320.07  5650.2  321.19
#Mann=9,-1,0
  4463.0     0.1       0  4517.7    0.05       0  4673.1     0.1       0
  4991.5    0.07       0  4997.5     0.1       0  5336.0    0.05       0
  5382.2     0.1       0  5487.4    0.05       0  5618.5     0.1       0
Bank Sta=4991.5,4997.5
Exp/Cntr=0.3,0.1

Type RM Length L Ch R = 1,1389,363,363,363
BEGIN DESCRIPTION:
UNT 021 IN RACR 2.0
END DESCRIPTION:
XS GIS Cut Line= 3
      2234251.17     13249104.84      2233797.14     13249540.71
      2233538.30     13249765.49
#Sta/Elev= 30
  4564.8  316.10  4611.2  316.14  4646.5  315.19  4752.5  313.68  4783.6  312.35
  4851.5  309.75  4858.7  309.10  4865.7  308.98  4915.3  306.09  4957.7  304.89
  4964.7  305.27  4997.0  304.80  4999.7  304.30  5003.0  304.80  5042.4  305.89
  5063.8  305.90  5070.7  306.38  5117.4  307.03  5226.5  308.86  5261.6  310.38
  5318.6  311.53  5325.9  312.05  5375.6  313.66  5382.2  313.57  5424.9  314.74
  5453.4  316.12  5474.3  316.34  5481.9  316.92  5502.8  317.42  5537.0  318.92
#Mann=5,-1,0
  4564.8    0.05       0  4783.6     0.1       0  4997.0    0.07       0
  5003.0     0.1       0  5117.4    0.05       0
Bank Sta=4997,5003
Exp/Cntr=0.3,0.1

Type RM Length L Ch R = 1,1026,373,373,373
BEGIN DESCRIPTION:
Mapping XS 67dff69d
END DESCRIPTION:
XS GIS Cut Line= 3
      2234332.91     13249070.78      2233608.71     13249093.48
      2233441.76     13249161.16
#Sta/Elev= 30
  4453.9  316.71  4479.1  316.05  4491.1  316.31  4549.1  315.74  4629.2  314.38
  4649.2  313.45  4759.2  310.64  4805.8  308.52  4839.3  307.78  4859.3  306.62
  4909.3  305.19  4959.3  302.91  4996.4  302.03  4999.1  301.53  5002.4  302.03
  5049.4  302.77  5069.4  303.44  5119.4  305.59  5125.4  306.22  5139.4  306.59
  5149.4  307.38  5159.4  307.74  5176.5  309.20  5181.7  309.20  5211.9  311.00
  5227.7  311.46  5233.5  312.38  5265.8  313.61  5305.4  315.72  5358.6  317.27
#Mann=3,-1,0
  4453.9    0.05       0  4996.4    0.03       0  5002.4    0.05       0
Bank Sta=4996.4,5002.4
Exp/Cntr=0.3,0.1

Type RM Length L Ch R = 1,653,431,431,431
BEGIN DESCRIPTION:
Mapping XS 1c9789e2
END DESCRIPTION:
XS GIS Cut Line= 4
      2234321.58     13248930.05      2234005.99     13248723.44
      2233647.30     13248714.36      2233456.63     13248968.59
#Sta/Elev= 30
  4384.5  315.35  4578.2  310.90  4699.9  306.91  4713.8  306.84  4757.7  305.58
  4890.0  303.84  4920.0  302.68  4950.0  302.09  4960.0  301.51  5007.1  300.64
  5009.8  300.14  5013.1  300.64  5020.1  301.39  5040.1  300.87  5060.1  300.92
  5090.1  302.56  5124.3  303.70  5136.1  304.53  5149.8  304.61  5179.0  306.20
  5193.6  306.42  5199.8  307.06  5214.4  307.75  5249.8  308.49  5264.4  309.47
  5293.6  310.07  5299.8  310.59  5322.8  310.92  5329.0  311.46  5438.3  314.21
#Mann=3,-1,0
  4384.5    0.05       0  5007.1   0.035       0  5013.1    0.05       0
Bank Sta=5007.1,5013.1
Exp/Cntr=0.3,0.1

Type RM Length L Ch R = 1,222,0,0,0
BEGIN DESCRIPTION:
UNT 021 IN RACR 1.0
END DESCRIPTION:
XS GIS Cut Line= 4
      2234246.65     13248653.07      2233833.46     13248289.83
      2233670.00     13248287.56      2233458.89     13248891.40
#Sta/Elev= 30
  4354.2  310.37  4549.4  304.64  4655.7  303.16  4811.3  302.42  4839.7  301.52
  4854.0  302.61  4874.9  303.11  4882.4  305.39  4910.1  306.64  4920.1  306.10
  4950.1  302.07  4960.1  301.52  4970.1  299.61  4977.1  299.54  4979.8  299.04
  4983.1  299.54  5030.1  299.54  5050.1  300.78  5060.1  303.03  5066.5  303.27
  5086.4  303.28  5091.7  302.32  5117.5  302.49  5130.6  301.30  5141.2  301.85
  5153.8  300.75  5365.8  303.10  5515.7  306.91  5634.6  311.23  5707.5  312.40
#Mann=3,-1,0
  4354.2    0.05       0  4977.1   0.035       0  4983.1    0.05       0
Bank Sta=4977.1,4983.1
Exp/Cntr=0.3,0.1

Chan Stop Cuts=-1