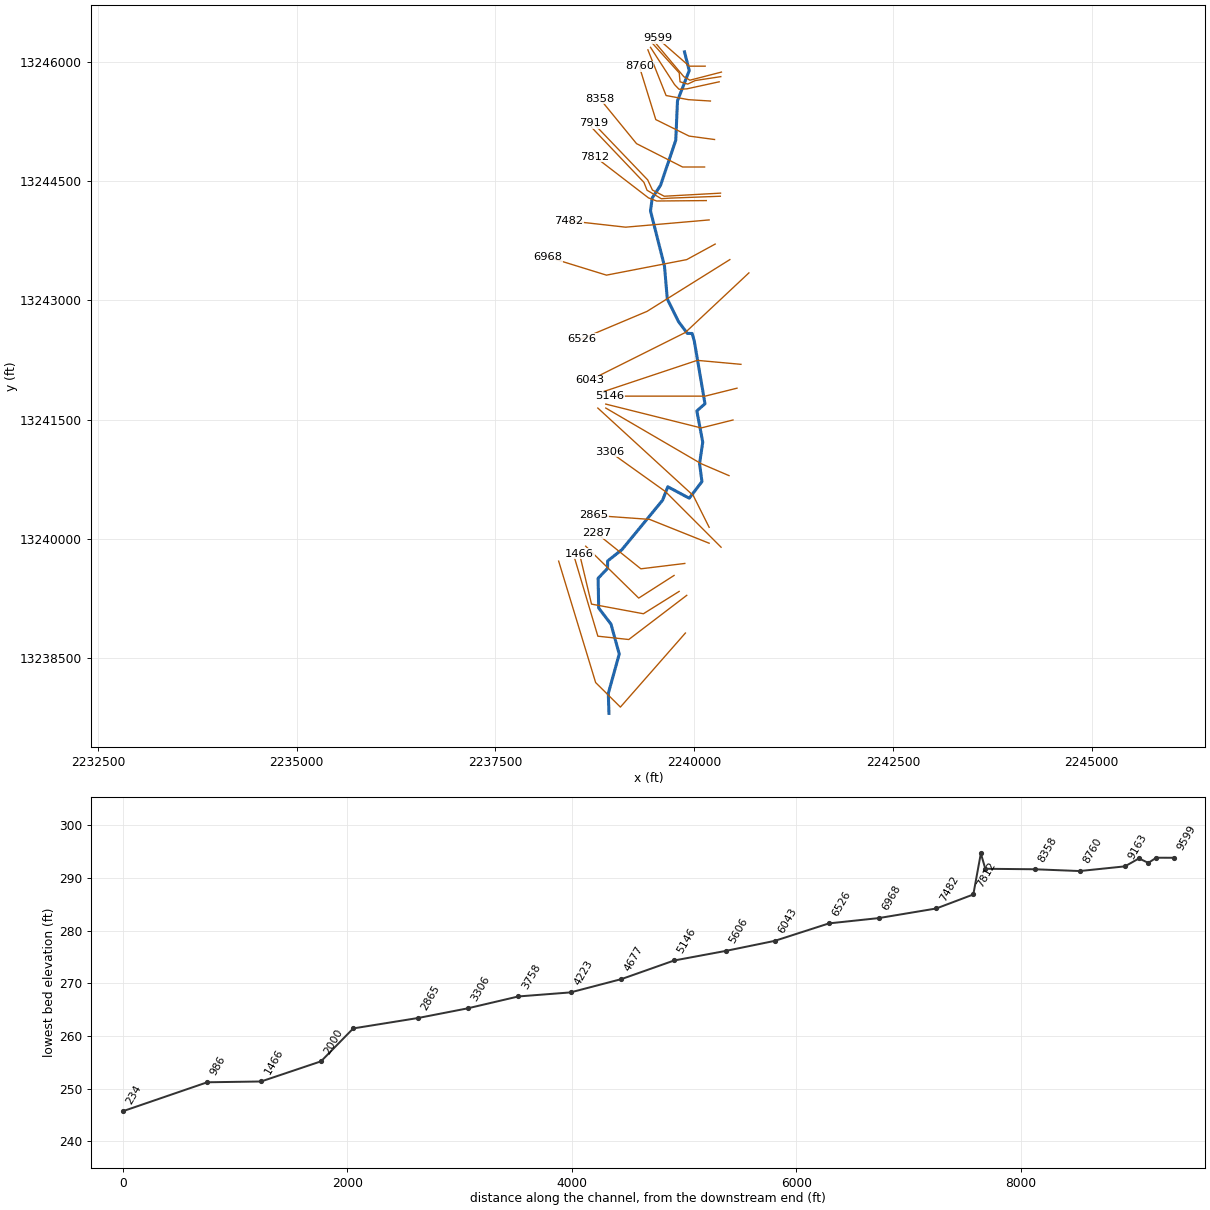
--- UNT 023 IN RACR.prj (project) ---

Proj Title=UNT 023 IN RACR Base Level Engineering
Current Plan=p01
Default Exp/Contr=0.3,0.1
English Units
Geom File=g01
Flow File=f01
Plan File=p01
Y Axis Title=Elevation
X Axis Title(PF)=Main Channel Distance
X Axis Title(XS)=Station
BEGIN DESCRIPTION:
UNT 023 IN RACR
END DESCRIPTION:
DSS Export Rating Curves= 0
DSS Export Rating Curve Sorted= 0
DSS Export Volume Flow Curves= 0
DXF OffsetX= 0
DXF OffsetY= 0
DXF ScaleX= 1
DXF ScaleY= 10

--- UNT 023 IN RACR.p01 (plan) ---

Plan Title=Multiple Run
Short Identifier=Multiple
Geom File=g01
Flow File=f01
Subcritical Flow
K Sum by GR= 0
Std Step Tol= 0.01
Critical Tol= 0.01
Num of Std Step Trials= 20
Max Error Tol= 0.3
Flow Tol Ratio= 0.001
Split Flow NTrial= 30
Split Flow Tol= 0.02
Split Flow Ratio= 0.02
Log Output Level= 0
Friction Slope Method= 1
Unsteady Friction Slope Method= 2
Unsteady Bridges Friction Slope Method= 1
Parabolic Critical Depth
Global Vel Dist=  1 , 1 , 1
Global Log Level= 0
CheckData=True
Encroach Param= -1, 0, 0, 0
BEGIN DESCRIPTION:
Multiple Run
END DESCRIPTION:

--- UNT 023 IN RACR.f01 (steady flow) ---

Flow Title=Multiple
Number of Profiles=7
Profile Names=10-year,25-year,50-year,1pct_min,100-year,1pct_plu,500-year
River Rch & RM= UNT 023 IN RACR,Reach-1,9599
     340     482     602     553     748    1012    1173
Boundary for River Rch & Prof#=UNT 023 IN RACR,Reach-1,1
Up Type=0
Dn Type=3
Dn Slope=0.005
Boundary for River Rch & Prof#=UNT 023 IN RACR,Reach-1,2
Up Type=0
Dn Type=3
Dn Slope=0.005
Boundary for River Rch & Prof#=UNT 023 IN RACR,Reach-1,3
Up Type=0
Dn Type=3
Dn Slope=0.005
Boundary for River Rch & Prof#=UNT 023 IN RACR,Reach-1,4
Up Type=0
Dn Type=3
Dn Slope=0.005
Boundary for River Rch & Prof#=UNT 023 IN RACR,Reach-1,5
Up Type=0
Dn Type=3
Dn Slope=0.005
Boundary for River Rch & Prof#=UNT 023 IN RACR,Reach-1,6
Up Type=0
Dn Type=3
Dn Slope=0.005
Boundary for River Rch & Prof#=UNT 023 IN RACR,Reach-1,7
Up Type=0
Dn Type=3
Dn Slope=0.005

--- UNT 023 IN RACR.g01 (geometry) ---

Geom Title=Existing Conditions
Program Version=4.10

River Reach=UNT 023 IN RACR ,Reach-1
Reach XY= 30
      2239877.72     13246126.86      2239937.33     13245891.43
      2239789.54     13245511.15      2239767.78     13245015.24
      2239576.03     13244447.43      2239472.13     13244289.74
      2239450.03     13244126.77      2239625.98     13243431.04
      2239661.42     13243018.39      2239802.36     13242734.06
      2239913.35     13242586.06      2239974.26     13242584.71
      2240000.89     13242489.19      2240135.29     13241701.15
      2240032.93     13241611.04      2240107.33     13241217.36
      2240067.06     13240946.73      2240097.26     13240722.09
      2239937.42     13240513.12      2239667.72     13240656.85
      2239601.87     13240487.51      2239091.37     13239866.66
      2238910.94     13239723.44      2238909.83     13239630.24
      2238791.21     13239505.49      2238798.45     13239131.46
      2238953.23     13238929.56      2239056.98     13238552.84
      2238919.17     13238056.91      2238927.72     13237806.85

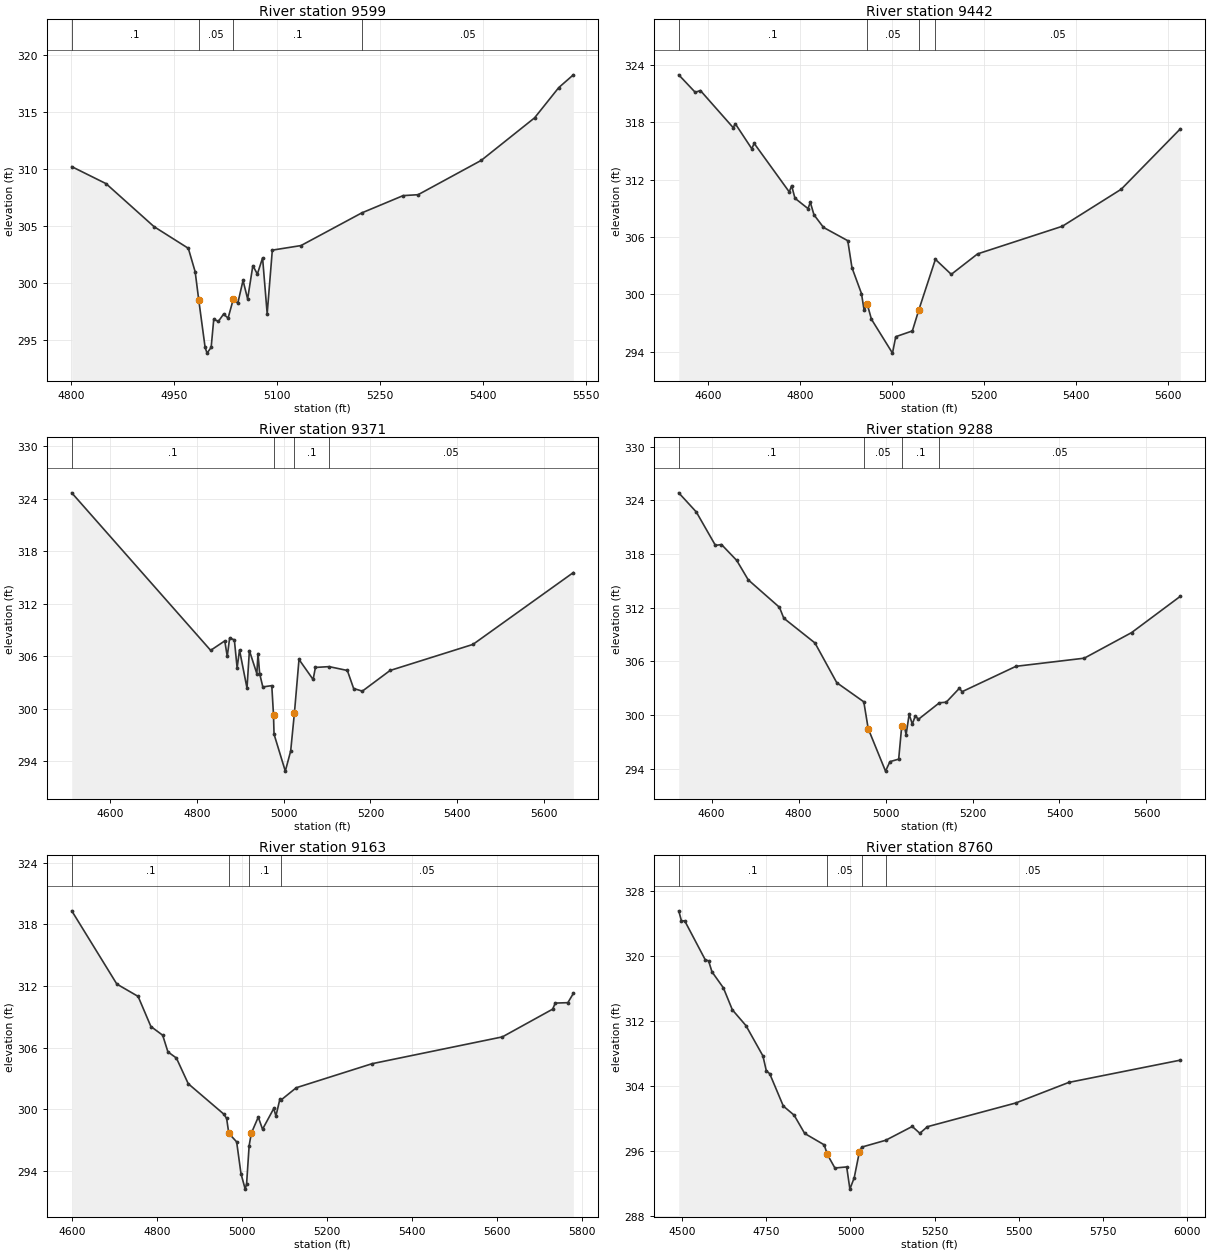
Type RM Length L Ch R = 1 ,9599    ,157,157,157
BEGIN DESCRIPTION:
UNT 023 IN RACR 18.0
END DESCRIPTION:
XS GIS Cut Line= 3
      2240137.72     13245946.85      2239937.72     13245946.85
      2239537.73     13246296.85
#Sta/Elev= 30
  4800.5   310.2  4850.5  308.71  4920.5  304.94  4970.5  303.04  4980.5  300.98
 4985.71  298.51    4995  294.35  4997.8  293.85  5003.8  294.35  5007.6  296.82
  5014.3  296.63  5021.9  297.27  5028.5  296.92  5036.1  298.58  5042.7  298.24
  5050.3  300.22    5057   298.6  5064.6  301.52  5071.2  300.78  5078.8   302.2
  5085.5   297.3    5093  302.88  5134.8  303.28  5223.3  306.14  5283.8  307.66
  5305.6  307.74  5397.7  310.75  5475.5  314.48  5510.7  317.13    5532  318.25
#Mann= 4 ,-1 , 0
  4800.5      .1       0 4985.71     .05       0  5036.1      .1       0
  5223.3     .05       0
Bank Sta=4985.71,5036.1
XS Rating Curve= 0 ,0
Exp/Cntr=0.3,0.1

Type RM Length L Ch R = 1 ,9442    ,71,71,71
BEGIN DESCRIPTION:
Mapping XS c3f0bf5c
END DESCRIPTION:
XS GIS Cut Line= 4
      2240342.46     13245872.51       2239945.9     13245770.41
      2239869.54     13245814.04      2239488.29     13246268.31
#Sta/Elev= 30
  4536.2  322.97  4572.1  321.14  4583.3  321.33  4654.3  317.46  4659.5  317.83
    4695  315.24  4700.2   315.8  4776.5  310.72  4781.6  311.38  4788.9  310.06
  4817.2  308.98  4822.3  309.63  4830.2  308.33  4850.9  307.01  4903.7  305.62
  4912.8   302.8  4933.5  300.09  4939.3  298.32  4945.7  299.04  4955.1  297.41
  5000.9  293.86    5008  295.58  5044.1  296.18  5058.4  298.42  5094.2  303.67
  5128.7   302.1  5185.9  304.24  5370.2  307.13  5498.1     311  5626.7  317.32
#Mann= 4 ,-1 , 0
  4536.2      .1       0  4945.7     .05       0  5058.4      .1       0
  5094.2     .05       0
Bank Sta=4945.7,5058.4
XS Rating Curve= 0 ,0
Exp/Cntr=0.3,0.1

Type RM Length L Ch R = 1 ,9371    ,83,83,83
BEGIN DESCRIPTION:
Mapping XS 2d016f01
END DESCRIPTION:
XS GIS Cut Line= 6
      2240334.58     13245815.21      2240011.71     13245765.74
      2239917.96     13245721.46       2239821.6     13245750.11
      2239811.18     13245862.09      2239471.35     13246238.24
#Sta/Elev= 30
  4510.6  324.68  4831.2  306.68  4863.8  307.76  4869.5  305.98    4875  308.09
  4885.9  307.88  4892.3  304.67  4897.8  306.73  4915.1  302.36  4920.6  306.65
  4937.8  304.02  4940.5  306.32  4944.3  304.02  4951.6   302.5  4972.3  302.65
 4976.25   299.3  4977.5   297.1  5003.5  292.88  5015.9  295.18  5024.6  299.56
  5035.1  305.64  5067.7  303.35    5073  304.73  5104.8  304.82  5146.7  304.38
  5161.2  302.32  5181.3  302.02  5245.3  304.38  5436.6  307.36  5668.3  315.57
#Mann= 4 ,-1 , 0
  4510.6      .1       0  4977.5     .05       0  5024.6      .1       0
  5104.8     .05       0
Bank Sta=4976.25,5024.6
XS Rating Curve= 0 ,0
Exp/Cntr=0.3,0.1

Type RM Length L Ch R = 1 ,9288    ,125,125,125
BEGIN DESCRIPTION:
Mapping XS 9a6847d4
END DESCRIPTION:
XS GIS Cut Line= 5
      2240313.81     13245750.11      2239907.54     13245661.57
      2239808.58     13245656.36      2239753.89     13245713.65
      2239450.22     13246183.44
#Sta/Elev= 30
  4524.4  324.85  4564.8  322.71  4608.8  318.97  4622.7  319.07  4657.8  317.29
  4684.2  315.12    4756  312.05    4766  310.83  4837.7  308.06  4887.8  303.62
    4950  301.48  4960.1  298.48  4999.9  293.73  5010.1  294.79  5030.2  295.07
  5037.2  298.76  5043.1  298.76  5047.3  297.81  5054.3  300.09  5061.5  298.99
  5068.4   299.9  5075.7  299.53  5123.8  301.37  5139.6  301.44  5169.9     303
  5175.9  302.61  5299.9  305.45    5457  306.36  5565.8  309.22  5677.9  313.28
#Mann= 4 ,-1 , 0
  4524.4      .1       0    4950     .05       0  5037.2      .1       0
  5123.8     .05       0
Bank Sta=4960.1,5037.2
XS Rating Curve= 0 ,0
Exp/Cntr=0.3,0.1

Type RM Length L Ch R = 1 ,9163    ,403,403,403
BEGIN DESCRIPTION:
UNT 023 IN RACR 17.0
END DESCRIPTION:
XS GIS Cut Line= 4
      2240203.75     13245508.32      2239927.11     13245525.61
      2239646.18     13245577.48      2239417.21     13246152.08
#Sta/Elev= 30
  4598.5  319.31  4704.7  312.18  4754.8  310.98  4784.9  308.05  4812.7   307.2
    4825  305.58    4845  304.98  4872.9  302.48  4956.4  299.53  4963.3   299.1
  4968.4  297.65  4986.9  296.82  4997.1  293.73    5007  292.22  5010.3  292.72
  5016.3  296.44  5021.4  297.66  5037.8  299.23  5047.9  298.05  5074.3  300.07
  5079.4  299.34  5088.6  300.96  5091.6   300.9  5127.3  302.09  5305.9  304.43
  5612.8  307.04  5731.2  309.74  5737.3  310.33    5767  310.37  5779.9  311.27
#Mann= 4 ,-1 , 0
  4598.5      .1       0  4968.4     .05       0  5016.3      .1       0
  5091.6     .05       0
Bank Sta=4968.4,5021.4
XS Rating Curve= 0 ,0
Exp/Cntr=0.3,0.1

Type RM Length L Ch R = 1 ,8760    ,402,402,402
BEGIN DESCRIPTION:
UNT 023 IN RACR 16.0
END DESCRIPTION:
XS GIS Cut Line= 4
      2240255.57     13245024.26      2239935.76     13245067.48
      2239516.52     13245274.94      2239309.53     13245943.34
#Sta/Elev= 30
  4489.8  325.57  4497.7  324.36  4507.8  324.32  4568.4  319.56  4578.5  319.41
  4588.5  318.07  4622.5  316.09  4649.1  313.39  4689.5  311.45  4739.9  307.72
    4750  305.89  4760.1  305.53  4800.5  301.55  4832.6  300.43    4864  298.18
  4921.9  296.78  4931.3   295.6  4953.7  293.93  4988.8  294.06  4998.3  291.33
  5011.2  292.74  5026.6  295.93  5033.5   296.5  5104.6  297.34  5183.6  299.04
  5206.1   298.2  5228.5  299.01  5491.2  301.93  5648.7  304.46    5980   307.2
#Mann= 4 ,-1 , 0
  4489.8      .1       0  4931.3     .05       0  5033.5      .1       0
  5104.6     .05       0
Bank Sta=4931.3,5026.6
XS Rating Curve= 0 ,0
Exp/Cntr=0.3,0.1

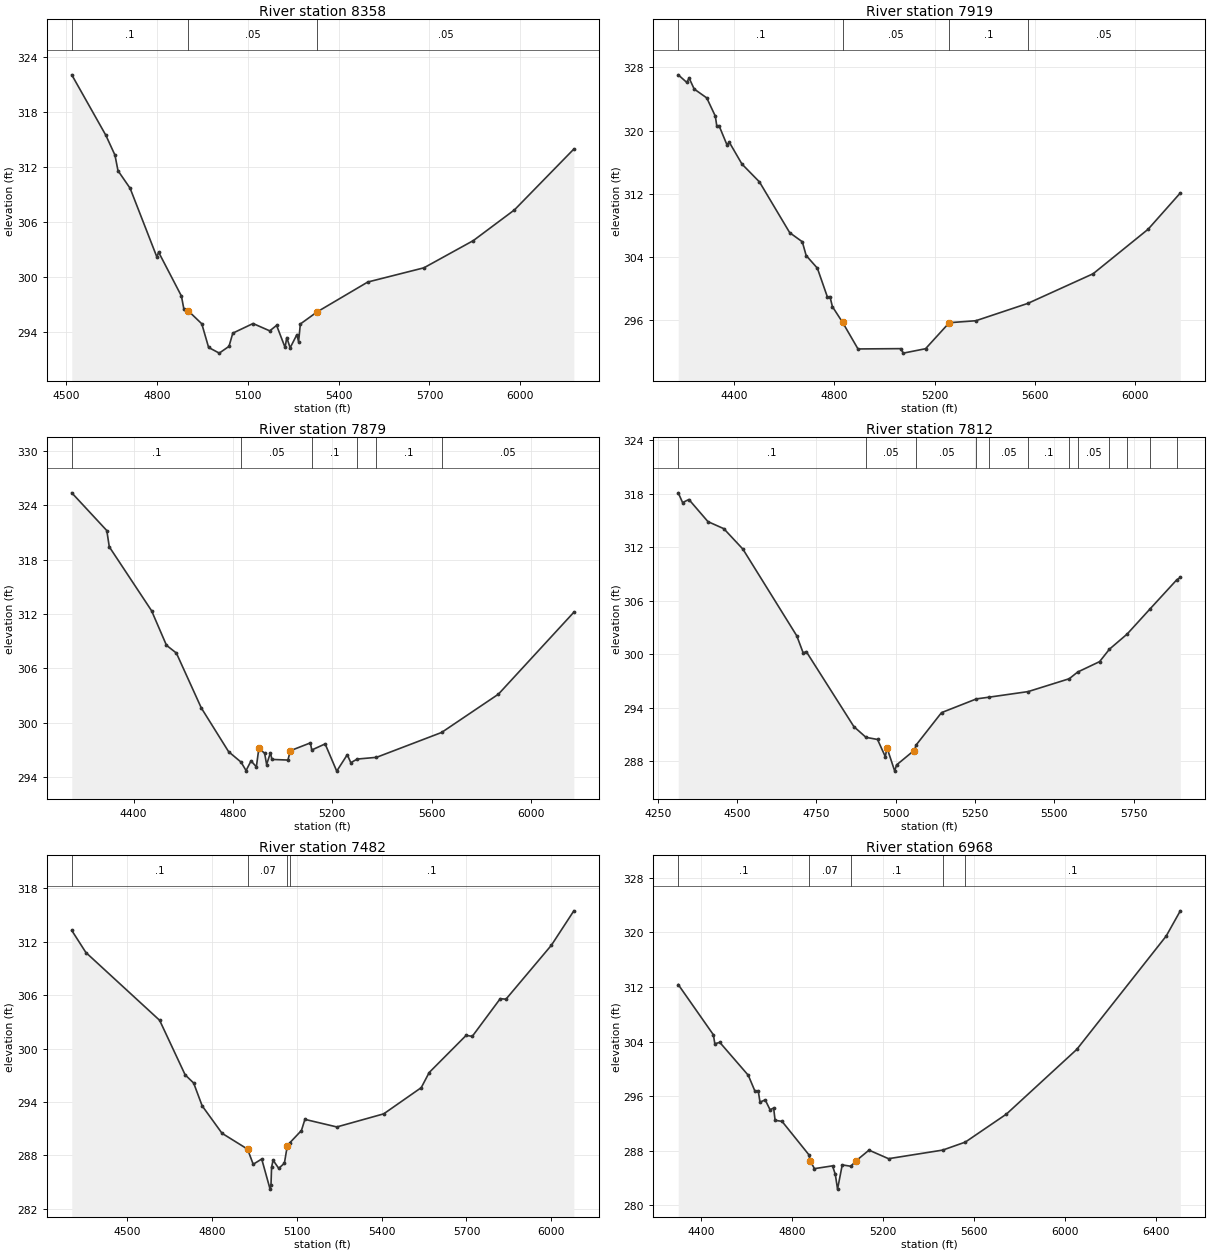
Type RM Length L Ch R = 1 ,8358    ,439,439,439
BEGIN DESCRIPTION:
UNT 023 IN RACR 15.0
END DESCRIPTION:
XS GIS Cut Line= 4
      2240130.27      13244678.5      2239853.64      13244678.5
      2239274.49      13244972.4      2238812.37     13245538.17
#Sta/Elev= 30
  4519.8  322.04  4632.3  315.44  4662.3  313.28  4672.3  311.58  4712.3  309.66
  4800.6  302.16  4806.3  302.69  4881.6   297.9  4889.7  296.48    4904  296.29
  4948.8  294.87  4971.3  292.29  5006.4  291.67  5038.6  292.41  5051.1  293.85
  5117.9   294.9  5173.1   294.1  5195.6   294.7  5223.6  292.29  5229.2  293.37
  5240.3  292.25  5262.6  293.69  5268.2  292.91    5274  294.85  5329.4  296.17
  5496.5  299.43  5681.7  300.98  5844.7  303.95  5980.4   307.3  6176.4  313.94
#Mann= 3 , 0 , 0
  4519.8      .1       0    4904     .05       0  5329.4     .05       0
Bank Sta=4904,5329.4
XS Rating Curve= 0 ,0
Exp/Cntr=0.3,0.1

Type RM Length L Ch R = 1 ,7919    ,40,40,40
BEGIN DESCRIPTION:
Mapping XS d04031b7
END DESCRIPTION:
XS GIS Cut Line= 6
      2240331.12     13244349.94      2239622.82     13244310.87
      2239474.38       13244389.      2239414.48      13244516.6
      2238763.44     13245196.29      2238737.37     13245227.58
#Sta/Elev= 30
  4178.8  327.07  4212.3  326.12  4222.3  326.65  4242.3  325.27  4292.4  324.14
  4326.5  321.83  4332.4  320.57  4342.5  320.53  4372.5  318.22  4382.5   318.5
  4432.6  315.75  4502.4  313.48  4622.9  307.04    4673  305.89  4688.4  304.14
    4733  302.54  4773.1  298.87  4783.1  298.93  4793.1  297.65  4833.2  295.68
  4894.9  292.29    5065  292.33  5075.4  291.76    5164  292.32  5258.4  295.62
  5364.4  295.87  5571.3  298.07  5831.4  301.83  6050.6  307.48  6178.8  312.08
#Mann= 4 ,-1 , 0
  4178.8      .1       0  4833.2     .05       0  5258.4      .1       0
  5571.3     .05       0
Bank Sta=4833.2,5258.4
XS Rating Curve= 0 ,0
Exp/Cntr=0.3,0.1

Type RM Length L Ch R = 1 ,7879    ,67,67,67
BEGIN DESCRIPTION:
Mapping XS f8f7d116
END DESCRIPTION:
XS GIS Cut Line= 6
      2240328.57     13244310.88      2239703.55     13244287.44
      2239586.36     13244279.62      2239406.67     13244386.39
      2239367.61     13244485.35      2238704.22     13245182.56
#Sta/Elev= 30
  4151.5  325.35  4292.5  321.19  4302.5   319.4  4472.6  312.36  4532.6  308.55
  4572.6  307.69  4672.7  301.65  4782.8  296.82  4832.9  295.67    4853  294.74
    4873  295.81  4894.4  295.15  4904.5  297.19  4927.7  296.65  4935.7  295.41
    4951   296.7  4957.2  295.97  5021.4   295.9  5031.2  296.93  5111.7  297.79
  5117.5  297.01  5171.2  297.68  5217.9  294.68  5260.3  296.49  5274.5  295.61
  5300.5  296.01  5377.9   296.2  5639.9  298.94  5868.6  303.16  6172.2  312.19
#Mann= 6 ,-1 , 0
  4151.5      .1       0  4832.9     .05       0  5117.5      .1       0
  5300.5     .05       0  5377.9      .1       0  5639.9     .05       0
Bank Sta=4904.5,5031.2
XS Rating Curve= 0 ,0
Exp/Cntr=0.3,0.1

Type RM Length L Ch R = 1 ,7812    ,330,330,330
BEGIN DESCRIPTION:
UNT 023 IN RACR 14.0
END DESCRIPTION:
XS GIS Cut Line= 4
      2240151.47     13244256.19      2239526.46     13244250.98
       2239424.9     13244290.04      2238751.55     13244807.41
#Sta/Elev= 30
  4314.3  318.09    4328     317    4348  317.34    4408  314.86    4458  314.07
  4518.1  311.78  4688.1  302.05  4708.1  300.15  4718.1  300.28  4868.1  291.87
  4906.2  290.67  4942.6  290.43  4967.2   288.5  4972.5   289.5  4996.9  286.88
  5002.5  287.57  5057.3  289.18  5065.5  289.86  5144.4  293.44  5254.5  294.98
  5293.6  295.17  5417.6   295.8    5547  297.24  5573.6  297.99  5642.8  299.16
  5673.7  300.55  5729.6  302.25  5800.3  305.01  5885.7  308.32  5897.3   308.6
#Mann= 12 ,-1 , 0
  4314.3      .1       0  4906.2     .05       0  5065.5     .05       0
  5254.5      .1       0  5293.6     .05       0  5417.6      .1       0
    5547     .08       0  5573.6     .05       0  5673.7     .08       0
  5729.6      .1       0  5800.3     .08       0  5885.7     .05       0
Bank Sta=4972.5,5057.3
XS Rating Curve= 0 ,0
Exp/Cntr=0.3,0.1

Type RM Length L Ch R = 1 ,7482    ,514,514,514
BEGIN DESCRIPTION:
UNT 023 IN RACR 13.0
END DESCRIPTION:
XS GIS Cut Line= 3
      2240187.54     13244013.01      2239137.72     13243921.85
      2238418.86     13244002.15
#Sta/Elev= 30
  4302.9  313.26  4352.9  310.78  4613.9  303.17  4704.2  297.05  4734.3  296.13
  4764.4  293.57  4834.7  290.49    4925  288.71  4945.1  287.01  4975.2   287.6
  5004.8  284.22  5008.1  284.72  5010.1  286.67  5015.4  287.47  5035.5  286.55
  5055.5  287.13  5065.6  289.05  5074.9  289.43  5115.8   290.8  5128.1  292.05
  5241.1   291.2    5407  292.67  5539.8  295.61    5568  297.31  5698.8  301.48
  5720.5  301.37  5819.5   305.6  5839.7  305.54  6000.6   311.6    6080  315.46
#Mann= 4 ,-1 , 0
  4302.9      .1       0    4925     .07       0  5065.6     .08       0
  5074.9      .1       0
Bank Sta=4925,5065.6
XS Rating Curve= 0 ,0
Exp/Cntr=0.3,0.1

Type RM Length L Ch R = 1 ,6968    ,442,442,442
BEGIN DESCRIPTION:
UNT 023 IN RACR 12.0
END DESCRIPTION:
XS GIS Cut Line= 4
      2240263.45     13243709.17       2239905.4     13243513.87
      2238896.28     13243318.56      2238158.46     13243546.42
#Sta/Elev= 30
  4299.5  312.36  4454.1     305  4460.4  303.68  4482.2  303.89  4607.5  299.07
  4636.4  296.78  4651.2   296.8  4659.1  295.13  4681.9  295.47  4703.2  294.02
  4719.1  294.27  4725.4  292.47  4755.9  292.32  4874.4  287.41  4879.5  286.57
  4898.5  285.39    4978   285.8  4990.2  284.55  5000.1  282.39  5020.7  285.94
  5058.4  285.74  5081.6  286.54  5138.4   288.1  5224.4  286.85  5462.6  288.11
    5562  289.28  5742.6  293.38  6052.1  302.86  6445.4  319.47  6507.4  323.16
#Mann= 5 ,-1 , 0
  4299.5      .1       0  4874.4     .07       0  5058.4      .1       0
  5462.6     .05       0    5562      .1       0
#XS Ineff= 1 ,-1
  5137.5 5614.58     288
Permanent Ineff=
       T
Bank Sta=4879.5,5081.6
XS Rating Curve= 0 ,0
Exp/Cntr=0.3,0.1

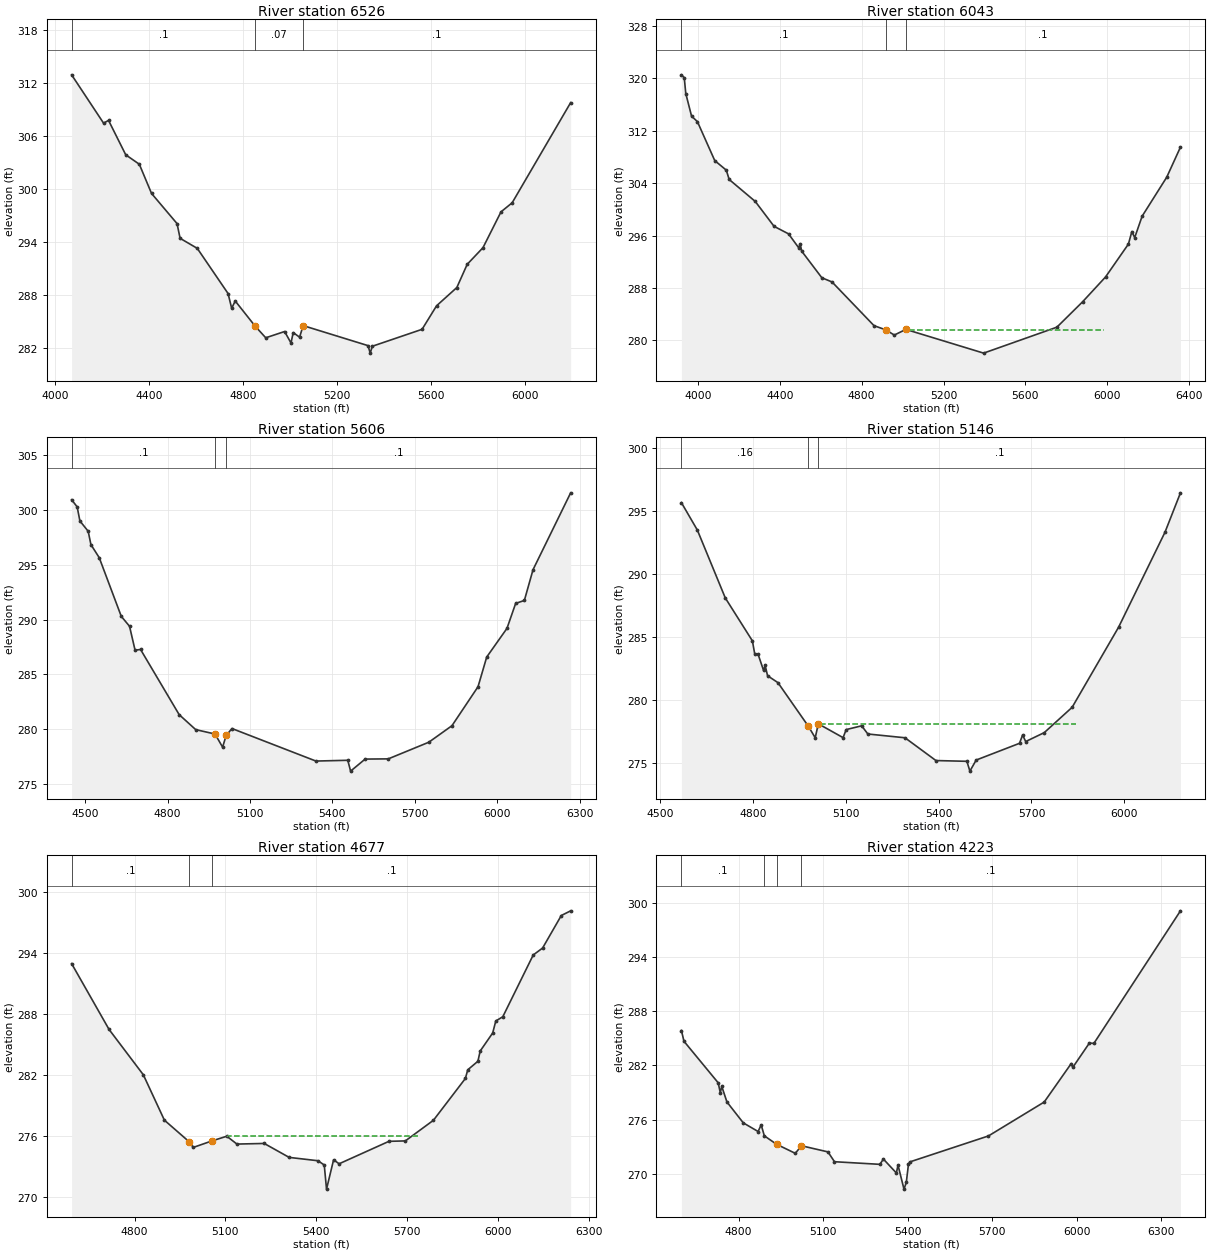
Type RM Length L Ch R = 1 ,6526    ,483,483,483
BEGIN DESCRIPTION:
UNT 023 IN RACR 11.0
END DESCRIPTION:
XS GIS Cut Line= 3
      2240447.94     13243513.88      2239406.27     13242862.83
      2238582.13     13242515.83
#Sta/Elev= 30
  4071.9  312.95  4207.8  307.47    4229  307.78  4302.1  303.88  4359.9  302.81
  4411.8   299.5  4520.3  296.08  4533.3  294.41  4606.4  293.27  4737.3  288.15
  4752.6  286.48  4767.9   287.3  4852.8  284.44  4897.6  283.13  4977.8  283.84
    5005  282.54  5014.4  283.72  5041.5   283.2  5056.8  284.51  5332.6  282.24
  5341.9  281.39  5350.9  282.17  5562.5  284.09  5624.2  286.76  5710.4  288.83
  5754.4  291.46  5821.6  293.35  5898.2  297.41  5945.7  298.44  6194.5   309.8
#Mann= 3 , 0 , 0
  4071.9      .1       0  4852.8     .07       0  5056.8      .1       0
#XS Ineff= 1 ,-1
 5064.24 5664.93  284.35
Permanent Ineff=
       T
Bank Sta=4852.8,5056.8
XS Rating Curve= 0 ,0
Exp/Cntr=0.3,0.1

Type RM Length L Ch R = 1 ,6043    ,437,437,437
BEGIN DESCRIPTION:
UNT 023 IN RACR 10.0
END DESCRIPTION:
XS GIS Cut Line= 3
      2240687.73     13243346.86      2239887.72     13242596.85
      2238687.76     13241996.87
#Sta/Elev= 30
  3919.4  320.54  3933.3   320.1  3940.7  317.69    3969  314.23  3997.3  313.41
  4082.3  307.45  4138.7  305.99  4152.7  304.57  4280.1  301.22    4372  297.42
  4442.8  296.27  4492.6  294.14  4499.5  294.77  4506.8  293.64  4605.5  289.57
  4655.3  288.93  4860.4  282.26  4917.1  281.63  4959.6  280.83    5016  281.69
  5395.9  278.07  5753.9  282.03  5879.7  285.91  5991.5  289.69  6103.3  294.71
  6120.1  296.62    6134   295.7  6170.4  298.97  6290.6  304.92  6357.6  309.51
#Mann= 3 , 0 , 0
  3919.4      .1       0  4917.1     .07       0    5016      .1       0
#XS Ineff= 1 ,-1
 5031.25 5985.42  281.63
Permanent Ineff=
       T
Bank Sta=4917.1,5016
XS Rating Curve= 0 ,0
Exp/Cntr=0.3,0.1

Type RM Length L Ch R = 1 ,5606    ,460,460,460
BEGIN DESCRIPTION:
UNT 023 IN RACR 9.0
END DESCRIPTION:
XS GIS Cut Line= 3
      2240587.76     13242196.85      2240037.72     13242246.85
      2238837.74     13241846.86
#Sta/Elev= 30
  4450.5  300.95  4470.6   300.3  4480.7  299.01  4510.8  298.07  4520.8  296.85
    4551  295.66  4631.3   290.3  4661.4  289.39  4681.5  287.21  4701.6  287.27
  4842.1  281.32  4902.4  279.95  4972.7  279.55  5000.3  278.35  5013.3  279.42
  5034.4  280.05  5340.1  277.08  5456.1  277.15  5466.4  276.16  5519.3  277.26
  5603.6  277.28  5751.2   278.8  5835.5  280.31  5930.4  283.87    5962  286.58
  6035.8   289.2  6067.4  291.48  6099.1  291.75  6130.7  294.56  6267.7  301.58
#Mann= 3 , 0 , 0
  4450.5      .1       0  4972.7     .07       0  5013.3      .1       0
#XS Ineff= 1 ,-1
 5034.72 5883.68  279.89
Permanent Ineff=
       T
Bank Sta=4972.7,5013.3
XS Rating Curve= 0 ,0
Exp/Cntr=0.3,0.1

Type RM Length L Ch R = 1 ,5146    ,469,469,469
BEGIN DESCRIPTION:
UNT 023 IN RACR 8.0
END DESCRIPTION:
XS GIS Cut Line= 3
      2240537.67     13241896.84      2240137.72     13241796.85
      2238937.68     13241796.85
#Sta/Elev= 30
  4569.1  295.67  4620.6  293.49  4710.8   288.1  4798.4  284.69  4806.1  283.63
  4816.4  283.65  4834.5  282.34  4839.6  282.74  4847.4  281.92  4880.9  281.37
  4978.8  277.92  5001.4  276.99  5011.4   278.1  5091.4     277  5101.4  277.64
  5151.4  277.94  5171.4  277.29  5291.4  276.99  5391.4  275.18  5491.4  275.12
  5501.1  274.34  5521.4  275.22  5661.4  276.55  5671.4  277.21  5681.4  276.69
  5741.4   277.4  5831.4  279.41  5981.4  285.77  6131.4  293.32  6181.4  296.45
#Mann= 3 , 0 , 0
  4569.1     .16       0  4978.8     .07       0  5011.4      .1       0
#XS Ineff= 1 ,-1
  5022.5  5842.5  278.09
Permanent Ineff=
       T
Bank Sta=4978.8,5011.4
XS Rating Curve= 0 ,0
Exp/Cntr=0.3,0.1

Type RM Length L Ch R = 1 ,4677    ,454,454,454
BEGIN DESCRIPTION:
UNT 023 IN RACR 7.0
END DESCRIPTION:
XS GIS Cut Line= 3
      2240487.69     13241496.85      2240087.72     13241396.85
      2238887.73     13241696.85
#Sta/Elev= 30
  4591.8  292.98  4715.5  286.51  4828.8  282.05  4898.4  277.59  4980.9  275.45
  4993.8  274.91  5055.6  275.55  5104.6  276.01  5138.1  275.24  5228.3   275.3
  5310.7  273.93  5406.1   273.6  5426.7  273.18  5434.2  270.81  5457.6   273.7
  5475.7   273.3  5640.6  275.51  5694.7  275.55  5787.5  277.58  5893.1  281.69
  5900.9  282.54  5934.4  283.38  5942.1  284.39  5983.3  286.16  5993.6  287.34
  6016.8  287.76  6117.3  293.83  6148.2  294.51  6210.1  297.71    6241  298.17
#Mann= 3 , 0 , 0
  4591.8      .1       0  4980.9     .07       0  5055.6      .1       0
#XS Ineff= 1 ,-1
 5106.94 5741.67  276.06
Permanent Ineff=
       T
Bank Sta=4980.9,5055.6
XS Rating Curve= 0 ,0
Exp/Cntr=0.3,0.1

Type RM Length L Ch R = 1 ,4223    ,465,465,465
BEGIN DESCRIPTION:
UNT 023 IN RACR 6.0
END DESCRIPTION:
XS GIS Cut Line= 3
      2240437.71     13240796.86      2240087.72     13240946.85
      2238887.74     13241646.84
#Sta/Elev= 30
  4597.3  285.87  4606.4  284.68  4727.8  280.07  4735.1  278.98  4740.5  279.67
  4758.7  277.95  4816.7  275.63  4869.3  274.67  4880.2  275.41  4891.4  274.19
  4934.6  273.26  5001.2  272.25  5023.1  273.09    5117  272.41  5140.2  271.32
    5301  271.03  5313.8  271.61  5359.7  270.07  5365.5  270.94  5386.7  268.28
  5394.9  269.02  5402.7  271.07  5408.5  271.31  5686.3  274.18    5884  277.94
  5979.9  282.21  5985.7   281.8  6044.4  284.49  6060.1  284.44  6367.3  299.15
#Mann= 4 ,-1 , 0
  4597.3      .1       0  4891.4     .05       0  4934.6     .07       0
  5023.1      .1       0
#XS Ineff= 1 ,-1
 5029.17 5616.67   272.8
Permanent Ineff=
       T
Bank Sta=4934.6,5023.1
XS Rating Curve= 0 ,0
Exp/Cntr=0.3,0.1

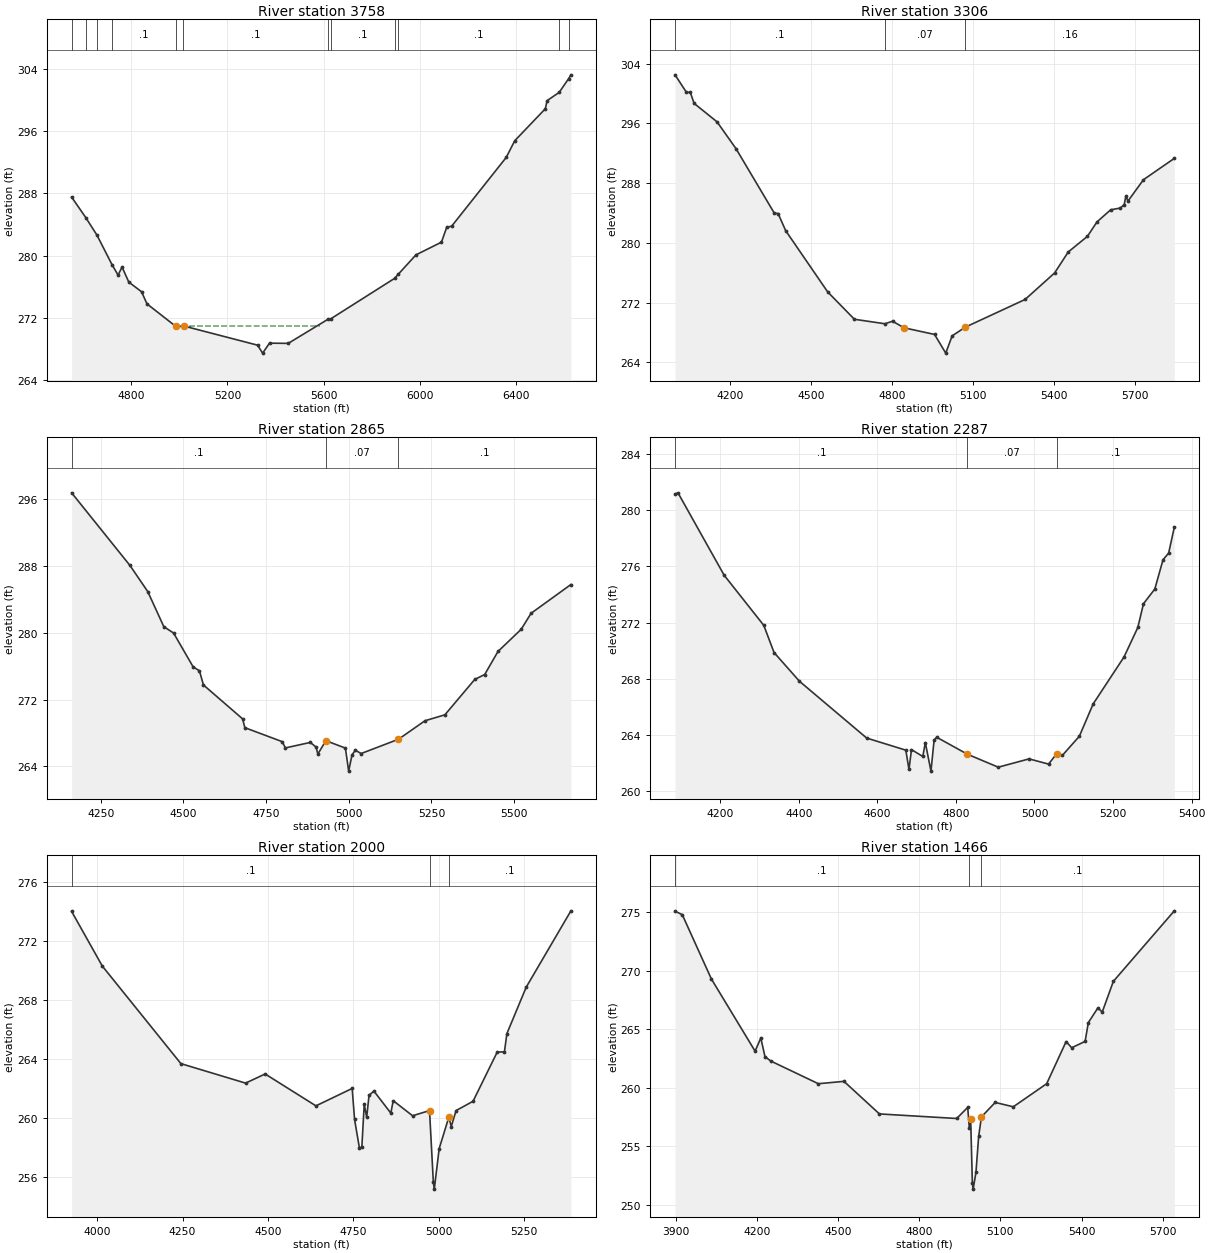
Type RM Length L Ch R = 1 ,3758    ,452,452,452
BEGIN DESCRIPTION:
UNT 023 IN RACR 5.0
END DESCRIPTION:
XS GIS Cut Line= 3
      2240187.73     13240146.84      2239987.72     13240546.85
      2238787.73     13241646.85
#Sta/Elev= 30
  4552.5  287.52  4611.3  284.89  4657.8  282.64  4720.1  278.87  4745.4  277.52
  4762.1  278.55  4790.1  276.62  4843.2  275.38  4865.6  273.83  4985.8  270.93
    5021  270.97  5325.3  268.53  5346.3  267.51  5374.9  268.79  5452.6  268.76
  5617.8  271.85  5630.1  271.92  5894.4  277.09  5909.9  277.62  5983.5  280.11
  6089.6  281.74  6111.2  283.64  6132.2   283.8  6358.5   292.6  6394.2  294.75
  6521.2  298.85  6528.6  299.89  6578.9  300.95  6617.7  302.69  6627.6   303.2
#Mann= 12 ,-1 , 0
  4552.5     .05       0  4611.3      .1       0  4657.8     .05       0
  4720.1      .1       0  4985.8     .07       0  5013.6      .1       0
  5617.8     .08       0  5630.1      .1       0  5894.4     .08       0
  5909.9      .1       0  6578.9     .05       0  6617.7      .1       0
#XS Ineff= 1 ,-1
 5042.42 5583.22  270.98
Permanent Ineff=
       T
Bank Sta=4985.8,5021
XS Rating Curve= 0 ,0
Exp/Cntr=0.3,0.1

Type RM Length L Ch R = 1 ,3306    ,441,441,441
BEGIN DESCRIPTION:
UNT 023 IN RACR 4.0
END DESCRIPTION:
XS GIS Cut Line= 3
      2240337.74     13239896.84      2239637.72     13240596.85
      2238937.72     13241096.85
#Sta/Elev= 30
  3996.7  302.49  4039.1  300.14  4053.3  300.15  4067.4  298.67  4152.3   296.2
    4223  292.59  4364.4  283.99  4378.6  283.93  4406.8  281.63  4562.4  273.44
  4661.4  269.78  4774.5  269.18  4802.8  269.52  4845.3  268.64  4958.4  267.75
  4999.9  265.25  5023.5  267.56  5072.7  268.73  5293.9  272.43  5403.3  275.98
  5453.7  278.78  5524.9  280.88  5560.6  282.82    5611  284.43  5646.6  284.66
  5661.3  285.13  5667.5  286.31  5674.9  285.59  5732.6  288.46  5846.9  291.31
#Mann= 3 ,-1 , 0
  3996.7      .1       0  4774.5     .07       0  5072.7     .16       0
Bank Sta=4845.3,5072.7
XS Rating Curve= 0 ,0
Exp/Cntr=0.3,0.1

Type RM Length L Ch R = 1 ,2865    ,578,578,578
BEGIN DESCRIPTION:
UNT 023 IN RACR 3.0
END DESCRIPTION:
XS GIS Cut Line= 3
      2240187.72     13239946.86      2239437.72     13240246.85
      2238737.68     13240296.86
#Sta/Elev= 30
  4162.1  296.78  4338.5  288.07  4392.3  284.94  4440.8  280.74  4470.4  279.97
  4529.6  275.91  4548.5  275.45  4560.6  273.75  4679.1  269.68  4685.8  268.63
  4798.9  266.95  4808.3   266.2  4883.7  266.86  4901.2   266.3  4906.6  265.47
  4930.8  267.07  4989.9  266.18  4999.7  263.42    5010  265.39    5020  265.92
  5037.5  265.53  5150.3  267.24  5230.5  269.46  5290.7  270.17  5380.9  274.41
    5411     275  5451.1  277.76  5521.3  280.42  5551.3  282.34  5671.7  285.79
#Mann= 3 , 0 , 0
  4162.1      .1       0  4930.8     .07       0  5150.3      .1       0
Bank Sta=4930.8,5150.3
XS Rating Curve= 0 ,0
Exp/Cntr=0.3,0.1

Type RM Length L Ch R = 1 ,2287    ,287,287,287
BEGIN DESCRIPTION:
UNT 023 IN RACR 2.0
END DESCRIPTION:
XS GIS Cut Line= 3
      2239881.94     13239692.54      2239328.94     13239624.95
      2238772.24     13240071.53
#Sta/Elev= 30
  4085.1  281.14  4092.6  281.22  4210.2  275.36    4311   271.8  4337.1  269.87
  4401.7  267.83  4572.9  263.79  4672.5  262.93  4680.5  261.56  4686.9  262.97
  4715.7  262.48  4722.1  263.47  4736.5  261.44  4744.5  263.65  4750.9  263.85
  4829.4  262.64  4907.8  261.72  4986.2  262.31  5035.8  261.94  5056.6  262.68
    5071  262.56  5114.2  263.92  5149.4  266.22  5227.8  269.55    5263  271.65
  5277.4  273.34  5306.2  274.38  5327.1  276.46  5341.5  276.94  5355.9  278.78
#Mann= 3 , 0 , 0
  4085.1      .1       0  4829.4     .07       0  5056.6      .1       0
Bank Sta=4829.4,5056.6
XS Rating Curve= 0 ,0
Exp/Cntr=0.3,0.1

Type RM Length L Ch R = 1 ,2000    ,534,534,534
BEGIN DESCRIPTION:
Mapping XS 288f0455
END DESCRIPTION:
XS GIS Cut Line= 3
      2239746.34     13239541.44      2239301.91     13239256.73
      2238635.27     13239909.47
#Sta/Elev= 30
  3925.6     274  4015.3   270.3  4245.3  263.69  4434.6  262.37  4491.8  262.99
  4640.4  260.83  4746.4  262.01  4753.4  259.91  4767.5  257.99  4774.7  258.04
  4781.7  260.96  4788.8  260.05  4795.8  261.55    4810  261.83  4859.5  260.34
  4866.5  261.18  4923.1  260.16  4972.7  260.51  4983.8  255.69  4986.6  255.19
    5001  257.94  5029.3  260.07  5036.3  259.43  5050.4  260.51    5100  261.14
  5170.7  264.47  5191.9  264.49    5199  265.72  5255.6  268.87  5386.4  274.04
#Mann= 3 , 0 , 0
  3925.6      .1       0  4972.7     .07       0  5029.3      .1       0
Bank Sta=4972.7,5029.3
XS Rating Curve= 0 ,0
Exp/Cntr=0.3,0.1

Type RM Length L Ch R = 1 ,1466    ,480,480,480
BEGIN DESCRIPTION:
Mapping XS 0f27c88c
END DESCRIPTION:
XS GIS Cut Line= 4
      2239810.45     13239340.85      2239360.93      13239059.9
      2238708.31     13239180.92      2238557.05     13239816.22
#Sta/Elev= 30
  3896.4  275.09  3923.2  274.79  4030.9   269.3  4192.5  263.14  4213.7  264.26
    4229  262.68  4250.2   262.3  4426.5  260.36  4521.3  260.56  4652.5  257.78
  4938.3  257.39    4979  258.34  4984.9  256.61  4989.9  257.34  4996.3  251.86
  4999.1  251.36  5009.5  252.79  5019.6  255.88  5029.8  257.53  5080.7  258.76
  5147.7  258.39  5271.1  260.36  5343.1  263.96  5363.6  263.43  5413.2  263.97
  5425.3  265.58  5460.5  266.83  5476.7  266.48  5517.8   269.1  5743.3  275.12
#Mann= 3 ,-1 , 0
  3896.4      .1       0  4984.9     .07       0  5029.8      .1       0
Bank Sta=4989.9,5029.8
XS Rating Curve= 0 ,0
Exp/Cntr=0.3,0.1

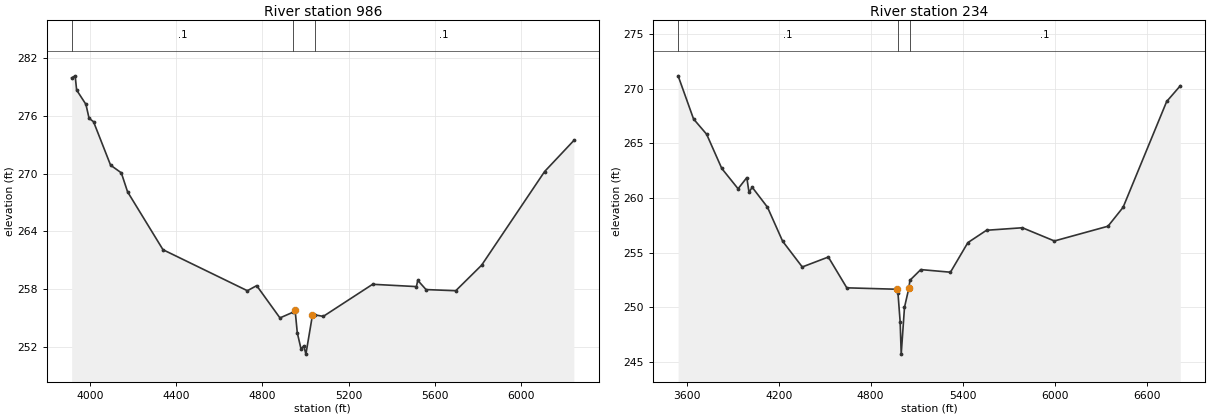
Type RM Length L Ch R = 1 ,986     ,752,752,752
BEGIN DESCRIPTION:
Mapping XS fad15e73
END DESCRIPTION:
XS GIS Cut Line= 4
      2239906.09     13239291.47      2239176.91     13238735.89
      2238788.02     13238777.56      2238496.35     13239756.71
#Sta/Elev= 30
  3915.6  279.97  3931.9  280.18  3938.7   278.7  3981.8  277.21  3996.4  275.76
  4017.2   275.4  4096.2  270.88    4146  270.08  4175.1   268.1  4339.3  262.08
  4730.7  257.81  4773.9  258.34  4881.8  254.98  4942.1  255.57  4952.2  255.78
  4962.2  253.44  4979.7  251.74  4992.4  252.07  5002.2  251.21  5032.6  255.27
  5042.7   255.3  5082.9  255.14  5311.7  258.48  5514.9  258.24  5521.1  258.89
  5559.5  257.93  5697.4  257.81  5817.4  260.47  6109.6  270.22  6245.1  273.45
#Mann= 3 ,-1 , 0
  3915.6      .1       0  4942.1     .07       0  5042.7      .1       0
Bank Sta=4952.2,5032.6
XS Rating Curve= 0 ,0
Exp/Cntr=0.3,0.1

Type RM Length L Ch R = 1 ,234     ,0,0,0
BEGIN DESCRIPTION:
UNT 023 IN RACR 1.0
END DESCRIPTION:
XS GIS Cut Line= 4
      2239889.06     13238817.54      2239071.57     13237885.97
      2238760.24     13238194.23      2238294.98     13239721.94
#Sta/Elev= 30
  3544.6  271.19  3645.2  267.24  3730.6  265.84  3829.3  262.71  3935.6  260.85
  3992.5  261.87  4006.8  260.53  4027.7  260.99  4127.3  259.16    4226  256.05
  4354.1  253.69    4524   254.6  4644.5  251.78  4971.2  251.65  4978.3  251.28
  4992.4  248.66  4999.3  245.71  5020.7     250    5049  251.74  5056.1  252.47
  5126.8  253.45  5320.4  253.21  5433.9  255.92  5555.5  257.05  5789.4  257.28
  5998.1  256.07  6347.5  257.42    6446  259.15  6730.2  268.84  6819.1  270.28
#Mann= 3 ,-1 , 0
  3544.6      .1       0  4978.3     .07       0  5056.1      .1       0
Bank Sta=4971.2,5049
XS Rating Curve= 0 ,0
Exp/Cntr=0.3,0.1

Chan Stop Cuts=-1
Use User Specified Reach Order=0
Composite Channel Slope=5