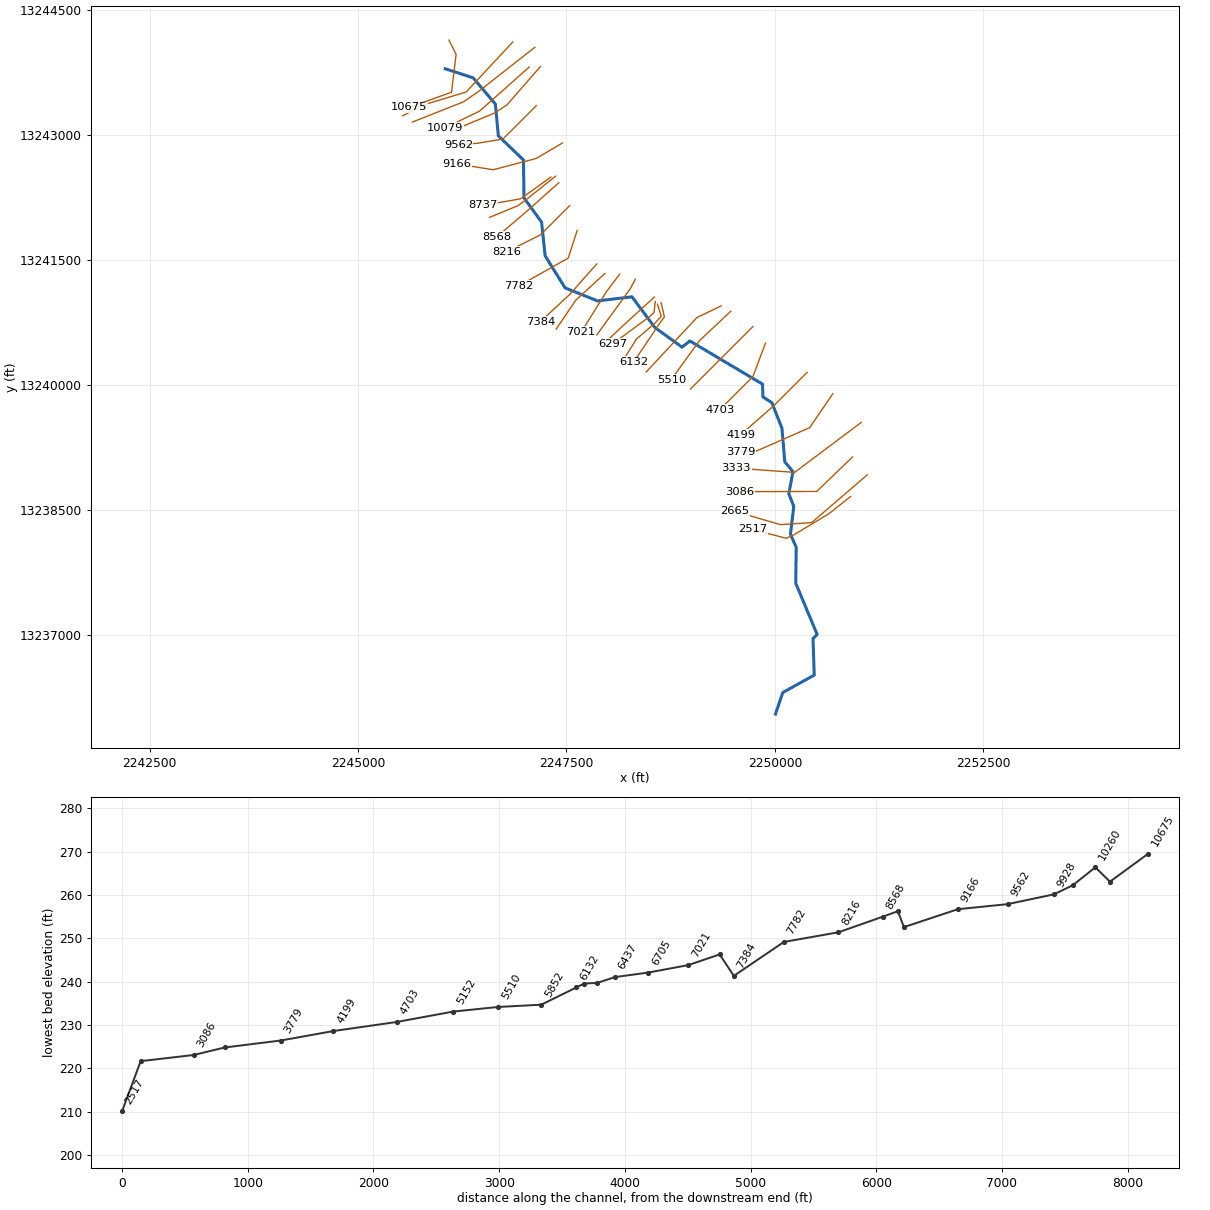
--- UNT 024 IN RACR.prj (project) ---

Proj Title=UNT 024 IN RACR Base Level Engineering
Current Plan=p01
Default Exp/Contr=0.3,0.1
English Units
Geom File=g01
Flow File=f01
Plan File=p01
Y Axis Title=Elevation
X Axis Title(PF)=Main Channel Distance
X Axis Title(XS)=Station
BEGIN DESCRIPTION:
UNT 024 IN RACR
END DESCRIPTION:
DSS Export Rating Curves= 0
DSS Export Rating Curve Sorted= 0
DSS Export Volume Flow Curves= 0
DXF OffsetX= 0
DXF OffsetY= 0
DXF ScaleX= 1
DXF ScaleY= 10

--- UNT 024 IN RACR.p01 (plan) ---

Plan Title=Multiple Run
Short Identifier=Multiple
Geom File=g01
Flow File=f01
Subcritical Flow
K Sum by GR= 0
Std Step Tol= 0.01
Critical Tol= 0.01
Num of Std Step Trials= 20
Max Error Tol= 0.3
Flow Tol Ratio= 0.001
Split Flow NTrial= 30
Split Flow Tol= 0.02
Split Flow Ratio= 0.02
Log Output Level= 0
Friction Slope Method= 1
Unsteady Friction Slope Method= 2
Unsteady Bridges Friction Slope Method= 1
Parabolic Critical Depth
Global Vel Dist=  1 , 1 , 1
Global Log Level= 0
CheckData=True
Encroach Param= -1, 0, 0, 0
BEGIN DESCRIPTION:
Multiple Run
END DESCRIPTION:

--- UNT 024 IN RACR.f01 (steady flow) ---

Flow Title=Multiple
Program Version=4.10
Number of Profiles= 7
Profile Names=10-year,25-year,50-year,1pct_min,100-year,1pct_plu,500-year
River Rch & RM=UNT 024 IN RACR,Reach-1         ,10675
     257     361     448     409     553     748     858
River Rch & RM=UNT 024 IN RACR,Reach-1         ,5852
     437     628     793     735     995    1345    1590
River Rch & RM=UNT 024 IN RACR,Reach-1         ,5510
     437     628     793     735     995    1345    1590
Boundary for River Rch & Prof#=UNT 024 IN RACR,Reach-1         , 1
Up Type= 0
Dn Type= 3
Dn Slope=0.0006
Boundary for River Rch & Prof#=UNT 024 IN RACR,Reach-1         , 2
Up Type= 0
Dn Type= 3
Dn Slope=0.0006
Boundary for River Rch & Prof#=UNT 024 IN RACR,Reach-1         , 3
Up Type= 0
Dn Type= 3
Dn Slope=0.0006
Boundary for River Rch & Prof#=UNT 024 IN RACR,Reach-1         , 4
Up Type= 0
Dn Type= 3
Dn Slope=0.0006
Boundary for River Rch & Prof#=UNT 024 IN RACR,Reach-1         , 5
Up Type= 0
Dn Type= 3
Dn Slope=0.0006
Boundary for River Rch & Prof#=UNT 024 IN RACR,Reach-1         , 6
Up Type= 0
Dn Type= 3
Dn Slope=0.0006
Boundary for River Rch & Prof#=UNT 024 IN RACR,Reach-1         , 7
Up Type= 0
Dn Type= 3
Dn Slope=0.0006
DSS Import GetInterval= 0
DSS Import GetPeak= 0
DSS Import FillOption= 0

--- UNT 024 IN RACR.g01 (geometry) ---

Geom Title=Existing Conditions
Program Version=4.10

River Reach=UNT 024 IN RACR ,Reach-1
Reach XY= 30
      2246045.48     13243790.05      2246380.31     13243680.78
      2246646.08     13243366.94      2246683.04     13242984.15
      2246984.09     13242695.35      2246989.93     13242240.48
      2247201.26     13241949.38      2247244.28     13241544.56
      2247483.17     13241160.53      2247873.45     13241004.28
      2248286.31     13241053.44      2248558.17     13240687.61
      2248885.95     13240449.42      2248980.93     13240523.59
      2249852.96     13240005.72      2249856.17     13239853.29
      2249965.15     13239782.68      2250085.37     13239476.35
      2250119.96     13239072.38      2250218.28      13238955.5
      2250167.76     13238690.13      2250227.67     13238537.62
       2250187.4     13238206.16      2250256.54      13238047.5
      2250250.83      13237617.1      2250507.78      13237002.2
       2250458.4     13236950.93      2250473.13     13236514.02
      2250095.73     13236304.84      2250007.72     13236046.85

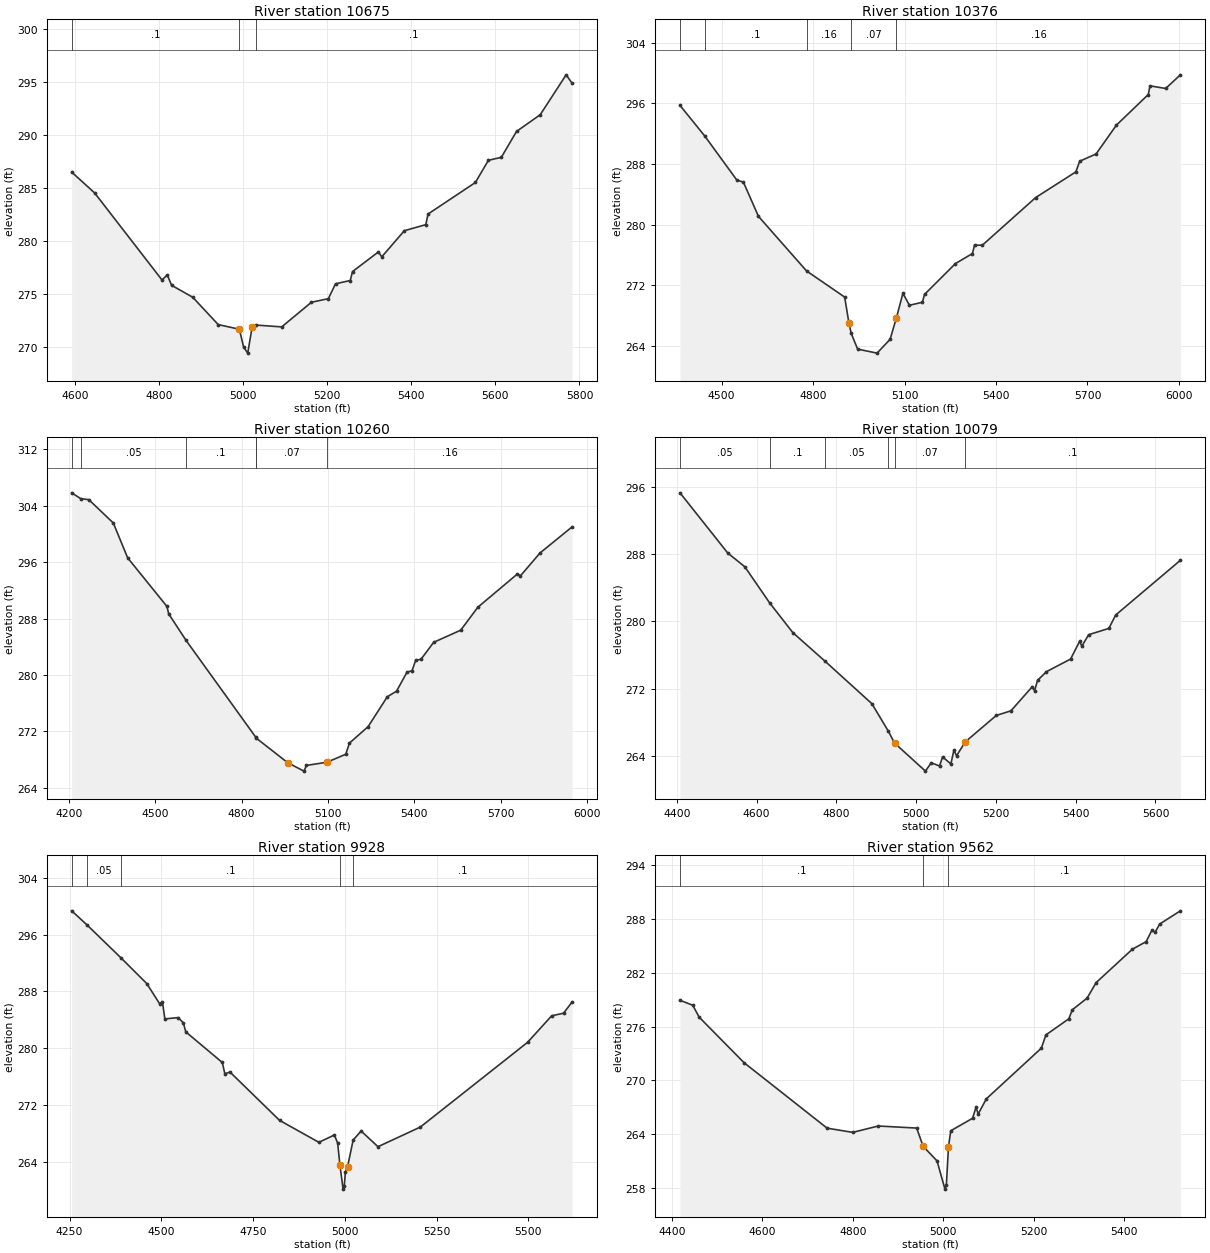
Type RM Length L Ch R = 1 ,10675   ,302,302,302
BEGIN DESCRIPTION:
UNT 024 IN RACR 21.0
END DESCRIPTION:
XS GIS Cut Line= 4
      2246089.94     13244133.77      2246175.77     13243962.09
      2246120.23     13243507.68      2245611.51     13243326.35
#Sta/Elev= 30
  4592.6   286.5  4647.1  284.54  4807.3  276.34    4820  276.81  4830.1  275.84
  4880.5  274.71  4940.9  272.14  4991.3   271.7  5001.4  270.02  5011.2  269.45
  5021.5  271.87  5031.6  272.09    5092  271.92  5162.6  274.24  5202.9  274.58
  5219.9  275.98    5255  276.29  5260.3  277.13  5321.9  278.98  5329.9  278.52
  5383.6  280.98  5434.6  281.55  5439.9  282.55  5552.5  285.52  5583.4  287.61
  5614.2  287.89  5650.3  290.33  5706.6   291.9  5768.3  295.66  5782.4  294.87
#Mann= 3 ,-1 , 0
  4592.6      .1       0  4991.3    .035       0  5031.6      .1       0
Bank Sta=4991.3,5021.5
XS Rating Curve= 0 ,0
Exp/Cntr=0.3,0.1

Type RM Length L Ch R = 1 ,10376   ,116,116,116
BEGIN DESCRIPTION:
Mapping XS 1074f457
END DESCRIPTION:
XS GIS Cut Line= 5
      2246856.23     13244112.15      2246297.21     13243511.46
      2245776.37     13243353.47      2245778.11     13243353.47
      2245535.04       13243225.
#Sta/Elev= 30
  4363.4  295.72    4445  291.66  4549.9  285.87  4571.4   285.6  4620.7  281.09
  4778.5  273.89  4903.6  270.44  4917.8  266.96  4925.1  265.65  4946.1  263.58
  5009.9  263.05  5052.6  264.87  5073.6  267.74  5094.6  270.93  5116.1  269.36
  5158.6  269.76  5165.5  270.79    5267  274.86  5322.5  276.18  5329.7  277.28
  5355.4  277.29  5530.3  283.57  5661.9  286.95  5674.6  288.36  5728.2  289.31
  5795.1  293.12  5899.5  297.15  5905.2   298.3  5956.6  297.95  6004.9  299.75
#Mann= 5 ,-1 , 0
  4363.4     .05       0    4445      .1       0  4778.5     .16       0
  4925.1     .07       0  5073.6     .16       0
Bank Sta=4917.8,5073.6
XS Rating Curve= 0 ,0
Exp/Cntr=0.3,0.1

Type RM Length L Ch R = 1 ,10260   ,181,181,181
BEGIN DESCRIPTION:
Mapping XS ff4db4bd
END DESCRIPTION:
XS GIS Cut Line= 4
      2247120.66     13244047.86      2246453.98     13243524.42
      2246266.48     13243394.21      2245651.01      13243150.1
#Sta/Elev= 30
  4210.1  305.83  4241.7     305  4269.7  304.86  4354.7  301.55  4404.5  296.61
  4540.9  289.72  4547.2  288.65  4607.6  284.89    4850  271.14  4851.1  271.04
  4961.2  267.53    5017  266.36  5025.3  267.17  5096.5  267.62    5162  268.75
  5174.9  270.34  5239.7  272.67  5306.2   276.9  5338.4   277.7  5374.9  280.41
  5392.2  280.59  5404.6  282.05  5423.6  282.24  5467.5  284.63  5561.3  286.35
  5620.7   289.6  5758.4  294.33  5768.8  294.06  5836.8   297.3  5948.1     301
#Mann= 6 ,-1 , 0
  4210.1     .08       0  4241.7     .05       0  4607.6      .1       0
    4850     .05       0  4851.1     .07       0  5096.5     .16       0
Bank Sta=4961.2,5096.5
XS Rating Curve= 0 ,0
Exp/Cntr=0.3,0.1

Type RM Length L Ch R = 1 ,10079   ,151,151,151
BEGIN DESCRIPTION:
Mapping XS 2622e549
END DESCRIPTION:
XS GIS Cut Line= 4
      2247052.94     13243810.88      2246581.58      13243391.6
      2246453.98     13243279.62      2246045.26     13243081.77
#Sta/Elev= 30
  4407.8  295.29  4527.6  288.13  4570.3   286.5  4632.8  282.19  4690.7  278.67
    4772  275.25  4888.9  270.22  4930.2  266.95  4945.7  265.54  5023.2   262.2
  5037.7  263.19  5058.6  262.81  5066.2  263.89    5087  263.06  5094.6  264.69
  5101.3  264.03  5123.1  265.68  5200.9  268.82  5237.6  269.37  5291.3  272.25
  5296.9  271.75  5304.3  272.99  5326.5  274.02  5387.2  275.53  5409.8  277.63
  5415.4  277.06  5432.4  278.42  5483.1  279.17  5500.2  280.76  5662.5  287.27
#Mann= 6 ,-1 , 0
  4407.8     .05       0  4632.8      .1       0    4772     .05       0
  4930.2      .1       0  4945.7     .07       0  5123.1      .1       0
Bank Sta=4945.7,5123.1
XS Rating Curve= 0 ,0
Exp/Cntr=0.3,0.1

Type RM Length L Ch R = 1 ,9928    ,366,366,366
BEGIN DESCRIPTION:
UNT 024 IN RACR 20.0
END DESCRIPTION:
XS GIS Cut Line= 4
      2247187.07      13243816.1      2246785.58     13243356.01
      2246640.18     13243260.53      2246106.37     13243037.02
#Sta/Elev= 30
  4255.7  299.34  4297.1  297.37    4391  292.66  4460.2  289.09  4495.3  286.24
  4502.9  286.49  4509.6   284.1  4545.7  284.29  4559.9  283.55  4566.5  282.28
  4666.1  277.96  4672.9  276.38  4687.1  276.61  4821.9  269.81  4929.1  266.71
  4971.4  267.74  4980.3  266.61  4986.3  263.58  4995.1  260.11  4998.4  260.61
  5001.4  262.51  5007.4  263.27  5022.5  267.03  5044.3   268.3  5090.2  266.09
  5205.6  268.86  5497.9  280.81  5563.3  284.54  5595.8  284.91    5619  286.49
#Mann= 5 ,-1 , 0
  4255.7      .1       0  4297.1     .05       0    4391      .1       0
  4986.3     .07       0  5022.5      .1       0
Bank Sta=4986.3,5007.4
XS Rating Curve= 0 ,0
Exp/Cntr=0.3,0.1

Type RM Length L Ch R = 1 ,9562    ,396,396,396
BEGIN DESCRIPTION:
UNT 024 IN RACR 19.0
END DESCRIPTION:
XS GIS Cut Line= 4
      2247137.69     13243346.82      2246737.72     13242946.85
      2246437.72     13242896.85      2246202.21     13242876.08
#Sta/Elev= 30
  4417.8  278.93    4446  278.38  4460.2  277.05  4559.2  271.98    4743  264.67
  4799.6   264.2  4856.2  264.91    4941  264.68  4955.2  262.65    4986  261.02
  5003.5  257.87  5006.7  258.37  5011.3   262.6  5016.4  264.38  5064.5  265.77
  5072.1  266.98  5077.2  266.26    5095  267.94  5216.6  273.59  5226.7  275.07
  5277.4  276.87    5285  277.87  5317.7  279.17  5337.8  280.91  5418.1  284.64
  5448.2  285.47  5460.8  286.72  5468.3  286.53  5478.3  287.44    5524  288.91
#Mann= 3 , 0 , 0
  4417.8      .1       0  4955.2     .07       0  5011.3      .1       0
Bank Sta=4955.2,5011.3
XS Rating Curve= 0 ,0
Exp/Cntr=0.3,0.1

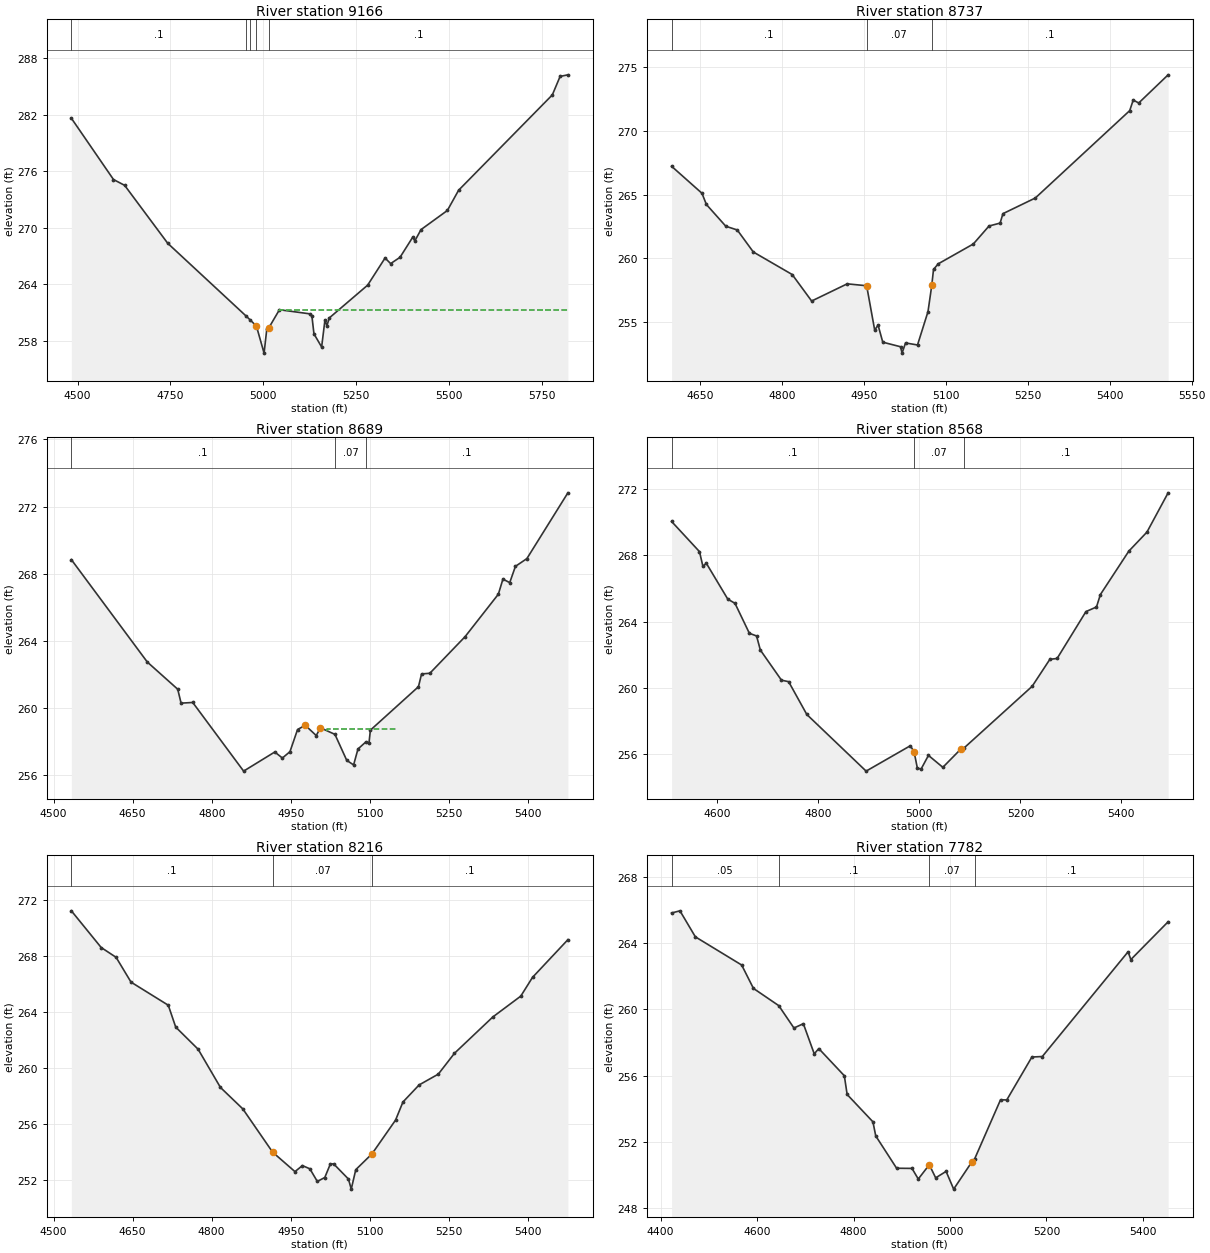
Type RM Length L Ch R = 1 ,9166    ,429,429,429
BEGIN DESCRIPTION:
UNT 024 IN RACR 18.0
END DESCRIPTION:
XS GIS Cut Line= 4
      2247451.47     13242898.85      2247135.34     13242712.89
      2246619.36     13242578.08      2246187.02     13242647.82
#Sta/Elev= 30
  4483.1  281.65  4596.6  275.14  4626.7  274.52  4742.7  268.37  4952.6  260.69
  4965.4  260.21  4981.8  259.57  5002.4   256.7  5009.9  259.31  5015.1  259.38
  5043.8  261.31  5126.1  260.87  5131.3  260.64  5136.8  258.75  5157.5  257.35
  5166.5  260.24  5171.7  259.61  5178.2  260.44  5281.5  263.92  5328.4   266.8
  5343.5  266.21  5368.8  266.88  5403.4  269.04  5408.5  268.61  5425.3  269.82
  5496.3  271.85  5526.6     274  5779.2  284.13  5800.1  286.09  5821.1  286.26
#Mann= 5 ,-1 , 0
  4483.1      .1       0  4952.6     .16       0  4965.4      .1       0
  4981.8     .07       0  5015.1      .1       0
#XS Ineff= 2 , 0
                         5042.22          261.33
Permanent Ineff=
       F       F
Bank Sta=4981.8,5015.1
XS Rating Curve= 0 ,0
Exp/Cntr=0.3,0.1

Type RM Length L Ch R = 1 ,8737    ,48,48,48
BEGIN DESCRIPTION:
Mapping XS 92c08119
END DESCRIPTION:
XS GIS Cut Line= 3
       2247312.9     13242490.11      2246950.51     13242229.71
      2246494.78     13242149.42
#Sta/Elev= 30
  4597.9  267.24  4653.5  265.12  4661.6  264.24  4697.2  262.53  4718.1  262.24
  4747.5  260.51  4818.7  258.74  4854.3  256.66  4919.4  258.01    4955  257.86
  4969.7  254.38  4975.9  254.77  4984.5  253.43  5017.1  253.07  5019.8  252.57
  5026.2  253.37  5048.1  253.21  5067.3  255.83 5074.17  257.88  5077.4  259.14
    5086  259.58  5150.3  261.14    5179  262.55  5199.3  262.78  5204.5  263.52
  5263.8  264.75  5436.6  271.61    5443  272.44  5453.1  272.21  5506.9  274.42
#Mann= 3 , 0 , 0
  4597.9      .1       0    4955     .07       0 5074.17      .1       0
Bank Sta=4955,5074.17
XS Rating Curve= 0 ,0
Exp/Cntr=0.3,0.1

Type RM Length L Ch R = 1 ,8689    ,121,121,121
BEGIN DESCRIPTION:
UNT 024 IN RACR 17.0
END DESCRIPTION:
XS GIS Cut Line= 4
      2247367.45     13242500.05      2247031.99     13242231.68
      2246920.99     13242148.74      2246575.79     13242006.02
#Sta/Elev= 30
  4533.8  268.84  4677.8  262.74  4735.5  261.12  4741.9  260.29    4764  260.33
  4860.5  256.24  4919.6  257.38    4934  257.02  4948.4   257.4  4962.8  258.72
  4977.4  258.97  4998.2  258.36  5006.2  258.82  5033.7  258.43  5056.1  256.88
  5069.1  256.61  5077.4  257.56    5092  257.97  5098.3  257.92  5100.9  258.68
  5192.1  261.27    5198  262.03  5213.7  262.07  5280.5  264.25  5343.6  266.78
  5352.3  267.68  5365.2  267.47    5376  268.44  5397.7   268.9  5475.5  272.82
#Mann= 3 ,-1 , 0
  4533.8      .1       0  5033.7     .07       0    5092      .1       0
#XS Ineff= 2 ,-1
    4775 4973.33  258.73 5019.17 5150.83  258.76
Permanent Ineff=
       T       T
Bank Sta=4977.4,5006.2
XS Rating Curve= 0 ,0
Exp/Cntr=0.3,0.1

Type RM Length L Ch R = 1 ,8568    ,352,352,352
BEGIN DESCRIPTION:
Mapping XS bfd83736
END DESCRIPTION:
XS GIS Cut Line= 3
       2247408.9      13242423.2      2247014.91      13242071.9
      2246668.49     13241776.71
#Sta/Elev= 30
  4509.5  270.04  4564.7  268.22  4571.5  267.33  4578.2  267.52  4620.8  265.35
    4635   265.1  4663.5  263.29  4677.7  263.13  4685.2  262.28    4727  260.46
  4741.2  260.37  4777.2  258.39  4894.6  254.97    4982   256.5  4989.5  256.15
  4996.2  255.13  5003.7  255.11    5018  255.92  5046.5   255.2  5081.7  256.29
  5088.2  256.36  5223.3  260.09  5258.4  261.72  5272.7  261.77  5329.8   264.6
  5350.7  264.88  5358.4  265.63  5414.7  268.25  5450.6   269.4  5492.5  271.77
#Mann= 3 ,-1 , 0
  4509.5      .1       0  4989.5     .07       0  5088.2      .1       0
Bank Sta=4989.5,5081.7
XS Rating Curve= 0 ,0
Exp/Cntr=0.3,0.1

Type RM Length L Ch R = 1 ,8216    ,434,434,434
BEGIN DESCRIPTION:
UNT 024 IN RACR 16.0
END DESCRIPTION:
XS GIS Cut Line= 3
      2247537.75     13242146.88      2247187.72     13241796.85
      2246787.74     13241596.87
#Sta/Elev= 30
  4533.8  271.25  4590.4  268.63  4618.7  267.93    4647  266.16  4717.7  264.51
  4731.8  262.95  4774.3  261.37  4816.7  258.64  4859.1  257.11  4915.7  254.02
  4958.1  252.63  4972.2  253.06  4986.4  252.83  5000.5  251.93  5014.7  252.21
  5025.3  253.18  5031.6  253.18  5059.6   252.1  5064.9  251.38  5073.5  252.77
  5104.3   253.9    5149  256.31    5163   257.6  5193.7  258.82  5230.1  259.59
  5260.8  261.08  5333.5  263.67  5386.6  265.16  5408.9   266.5    5476  269.19
#Mann= 3 , 0 , 0
  4533.8      .1       0  4915.7     .07       0  5104.3      .1       0
Bank Sta=4915.7,5104.3
XS Rating Curve= 0 ,0
Exp/Cntr=0.3,0.1

Type RM Length L Ch R = 1 ,7782    ,398,398,398
BEGIN DESCRIPTION:
UNT 024 IN RACR 15.0
END DESCRIPTION:
XS GIS Cut Line= 3
      2247628.06     13241848.25      2247521.16     13241518.24
      2246926.13     13241183.54
#Sta/Elev= 30
  4422.7  265.81    4440  265.94    4472  264.37    4568  262.67  4592.4  261.26
  4644.9  260.22  4676.4  258.87  4695.9  259.13  4718.5  257.31  4727.9  257.63
  4780.9  255.99  4786.7  254.86  4840.2  253.21    4846  252.36  4889.3  250.41
  4921.2   250.4  4934.2  249.76  4957.1  250.62  4970.3  249.83  4991.9  250.22
  5007.6  249.15  5045.5   250.8  5051.2  250.98  5104.8  254.54  5117.7  254.53
  5169.8  257.12  5191.4  257.15  5369.3  263.47    5375     263  5452.3  265.28
#Mann= 4 ,-1 , 0
  4422.7     .05       0  4644.9      .1       0  4957.1     .07       0
  5051.2      .1       0
Bank Sta=4957.1,5045.5
XS Rating Curve= 0 ,0
Exp/Cntr=0.3,0.1

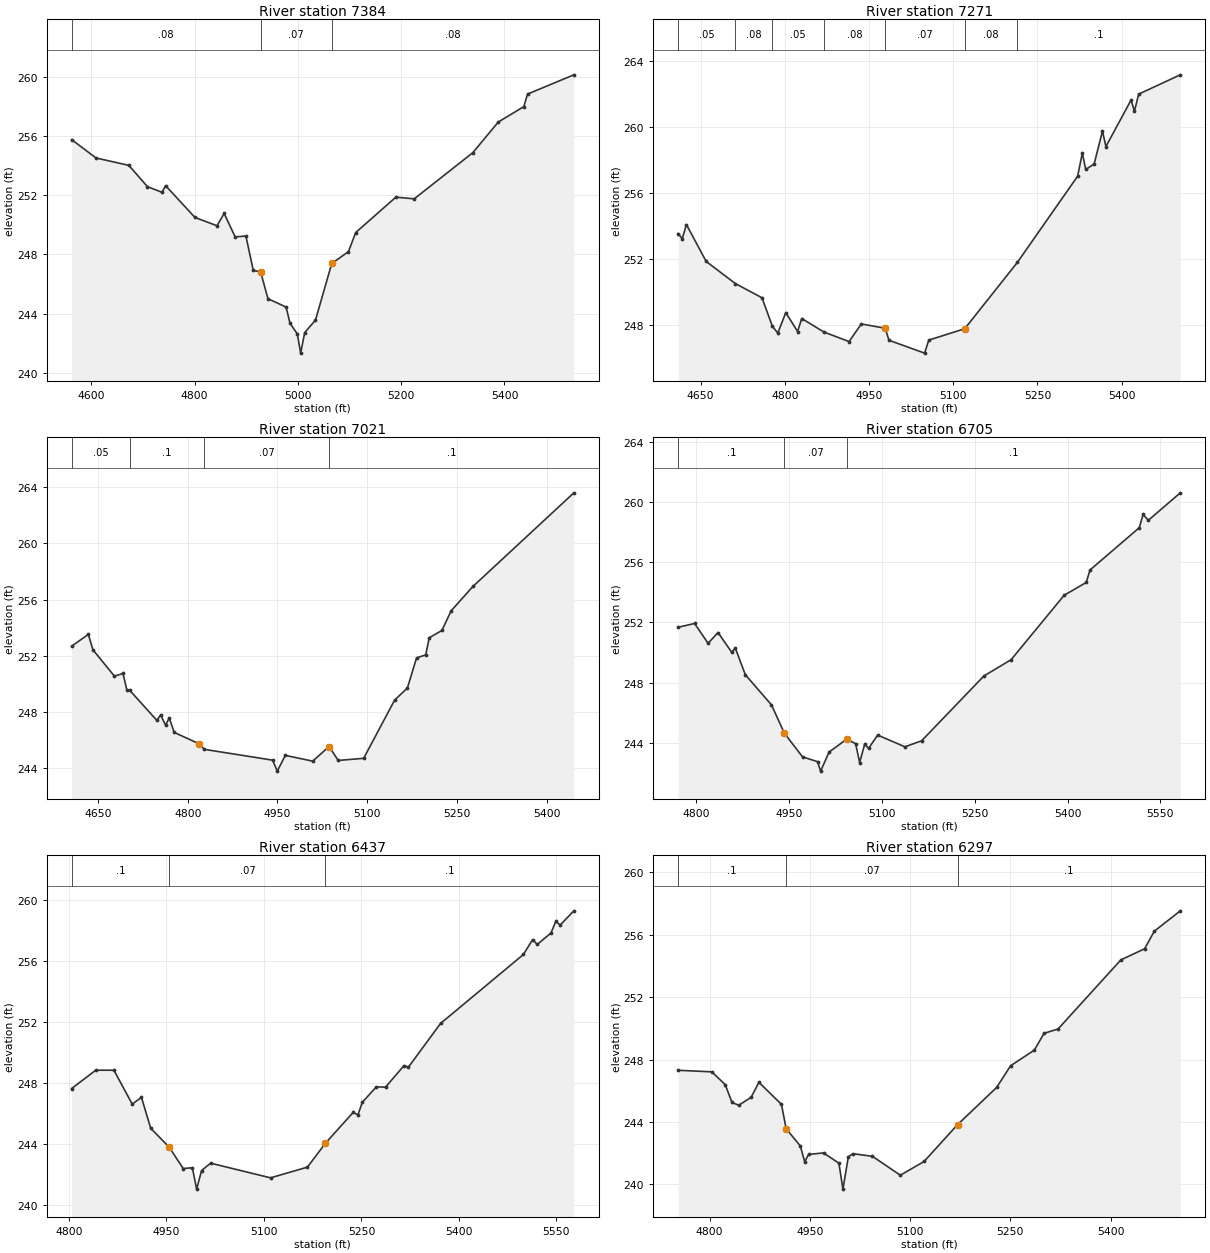
Type RM Length L Ch R = 1 ,7384    ,113,113,113
BEGIN DESCRIPTION:
Mapping XS 6fb32039
END DESCRIPTION:
XS GIS Cut Line= 3
      2247863.11      13241448.2      2247541.03     13241083.53
      2247184.35     13240753.47
#Sta/Elev= 30
  4561.9  255.76  4609.1  254.52  4672.7  254.02  4708.7  252.58  4737.1   252.2
  4743.8  252.65  4800.7   250.5  4843.4  249.94  4857.2  250.77  4878.5  249.19
  4899.4  249.24  4913.6  246.92  4927.8  246.83    4942  245.01  4977.3  244.44
  4984.7  243.35  4998.9  242.63  5005.4  241.33  5013.2  242.72  5034.1  243.56
  5065.6  247.39  5097.9  248.19    5112  249.48  5189.7  251.87  5225.4  251.76
  5338.8  254.88  5388.1  256.95  5437.5  257.99  5444.8  258.84  5534.4  260.14
#Mann= 3 , 0 , 0
  4561.9     .08       0  4927.8     .07       0  5065.6     .08       0
Bank Sta=4927.8,5065.6
XS Rating Curve= 0 ,0
Exp/Cntr=0.3,0.1

Type RM Length L Ch R = 1 ,7271    ,250,250,250
BEGIN DESCRIPTION:
UNT 024 IN RACR 14.0
END DESCRIPTION:
XS GIS Cut Line= 3
       2247961.6     13241333.75       2247612.9     13241014.32
      2247375.97     13240665.59
#Sta/Elev= 30
  4609.9  253.52  4617.3  253.21  4624.7  254.07  4659.9  251.83  4711.8  250.49
  4759.2  249.63  4777.9  247.89  4787.5  247.49  4801.7  248.73  4822.7  247.58
  4830.1  248.37  4869.6  247.55  4914.5  246.97  4936.1  248.04  4978.7  247.78
  4985.5  247.05  5048.9  246.27  5056.4  247.06  5120.4  247.75  5214.1  251.77
  5321.5     257  5329.9  258.41  5335.9  257.41  5350.9  257.74  5365.8  259.74
  5371.9   258.8  5416.7  261.62  5422.7  260.95  5430.3  261.98  5504.4  263.15
#Mann= 7 ,-1 , 0
  4609.9     .05       0  4711.8     .08       0  4777.9     .05       0
  4869.6     .08       0  4978.7     .07       0  5120.4     .08       0
  5214.1      .1       0
Bank Sta=4978.7,5120.4
XS Rating Curve= 0 ,0
Exp/Cntr=0.3,0.1

Type RM Length L Ch R = 1 ,7021    ,316,316,316
BEGIN DESCRIPTION:
Mapping XS 85dc38e4
END DESCRIPTION:
XS GIS Cut Line= 4
      2248138.64     13241325.28      2247981.85      13241118.1
       2247696.3     13240661.78      2247668.73     13240631.46
#Sta/Elev= 30
  4606.1  252.69    4634  253.53  4641.7  252.43  4677.6  250.56  4691.9  250.75
  4698.5  249.55  4702.8  249.57  4748.4  247.42  4754.7   247.8    4763  247.08
  4769.2  247.59  4777.5  246.56  4819.2  245.75  4827.5  245.36  4941.9  244.59
  4949.7  243.81  4963.1  244.93  5008.9  244.52  5036.2  245.56  5051.5  244.57
    5094  244.72  5145.8  248.86  5167.1  249.72  5182.4  251.86  5197.7  252.07
  5203.6  253.29  5224.8  253.81  5240.1   255.2  5276.7  256.94  5445.2  263.59
#Mann= 4 ,-1 , 0
  4606.1     .05       0  4702.8      .1       0  4827.5     .07       0
  5036.2      .1       0
Bank Sta=4819.2,5036.2
XS Rating Curve= 0 ,0
Exp/Cntr=0.3,0.1

Type RM Length L Ch R = 1 ,6705    ,268,268,268
BEGIN DESCRIPTION:
UNT 024 IN RACR 13.0
END DESCRIPTION:
XS GIS Cut Line= 3
      2248326.19     13241263.67       2248264.6      13241148.9
      2247864.29     13240597.42
#Sta/Elev= 30
  4770.5  251.68  4797.1  251.93    4819  250.61    4835  251.33  4857.2  250.01
  4862.9   250.3  4879.1  248.52  4921.4  246.51  4942.3  244.62  4971.6  243.05
  4995.9  242.73  5000.8   242.1  5014.5  243.37  5042.8  244.22  5057.4  243.93
  5063.9  242.67  5072.1   243.9  5078.3  243.61    5093   244.5  5137.1  243.72
  5164.1  244.12  5264.6  248.43  5308.7  249.52  5394.5  253.81  5430.1  254.66
  5436.2  255.49  5515.9  258.31    5522  259.19  5530.5   258.8  5582.2  260.63
#Mann= 3 , 0 , 0
  4770.5      .1       0  4942.3     .07       0  5042.8      .1       0
Bank Sta=4942.3,5042.8
XS Rating Curve= 0 ,0
Exp/Cntr=0.3,0.1

Type RM Length L Ch R = 1 ,6437    ,140,140,140
BEGIN DESCRIPTION:
UNT 024 IN RACR 12.0
END DESCRIPTION:
XS GIS Cut Line= 3
      2248555.72     13241050.89      2248205.81     13240731.77
      2247987.49     13240527.44
#Sta/Elev= 30
  4804.2  247.63  4841.3  248.83  4869.2  248.83  4897.4  246.61  4911.6  247.05
  4925.8  245.03  4954.2  243.79  4975.8  242.39  4989.9  242.44  4996.5  241.04
  5004.1  242.26    5018  242.74  5110.2  241.78  5166.9  242.48  5194.7  244.05
  5237.2  246.06  5244.7  245.91  5251.4  246.73    5273  247.74  5287.1  247.72
  5315.5  249.13  5322.3  249.03  5371.7  251.89  5499.2  256.41  5513.3  257.38
  5520.6  257.07  5541.7  257.82    5549  258.58  5555.8  258.34  5576.8  259.27
#Mann= 3 , 0 , 0
  4804.2      .1       0  4954.2     .07       0  5194.7      .1       0
Bank Sta=4954.2,5194.7
XS Rating Curve= 0 ,0
Exp/Cntr=0.3,0.1

Type RM Length L Ch R = 1 ,6297    ,104,104,104
BEGIN DESCRIPTION:
Mapping XS 7ddbe829
END DESCRIPTION:
XS GIS Cut Line= 4
      2248565.99     13240996.89      2248550.36     13240864.93
      2248505.36     13240821.35      2248057.98     13240491.41
#Sta/Elev= 30
    4753  247.31  4803.4  247.21  4823.5  246.39  4833.6  245.25  4843.7  245.07
  4862.3  245.58  4873.9  246.54  4907.6  245.13  4914.7  243.56  4935.8  242.47
  4942.4  241.45  4948.2  241.92  4970.6  242.02  4993.6  241.36  4999.6   239.7
  5007.7  241.77  5014.5  241.97  5043.8   241.8  5085.5  240.59    5121  241.47
  5171.1  243.83  5229.6  246.21  5250.5   247.6    5286   248.6  5300.6  249.68
  5321.4  249.95  5415.5  254.38    5451  255.09  5465.6  256.22  5504.4  257.52
#Mann= 3 ,-1 , 0
    4753      .1       0  4914.7     .07       0  5171.1      .1       0
Bank Sta=4914.7,5171.1
XS Rating Curve= 0 ,0
Exp/Cntr=0.3,0.1

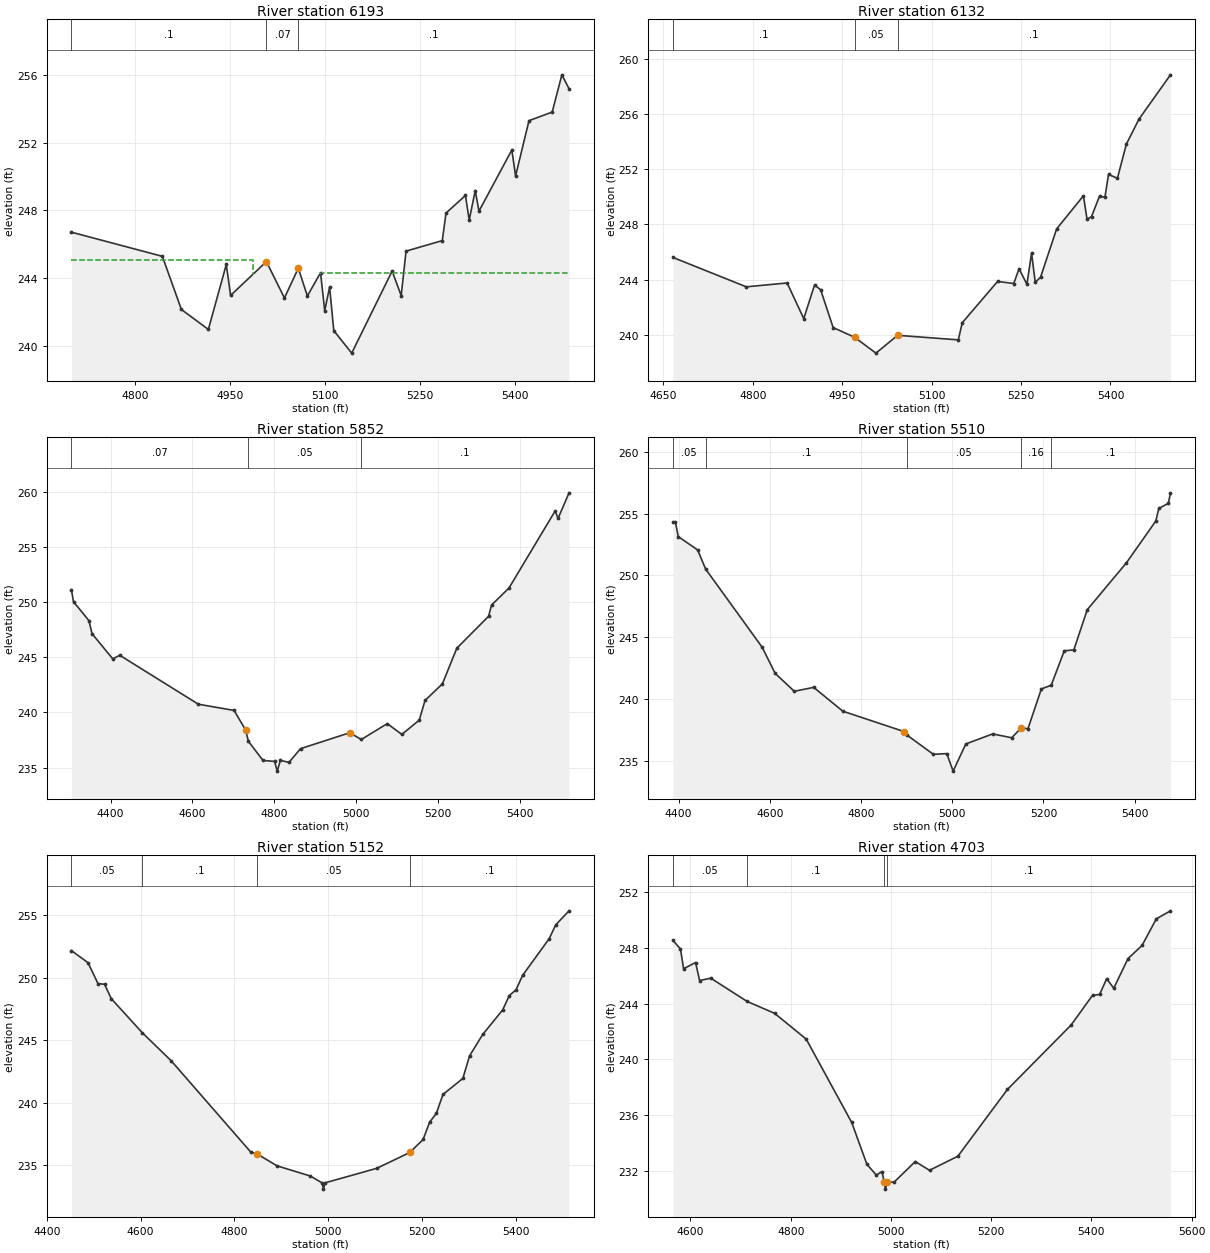
Type RM Length L Ch R = 1 ,6193    ,61,61,61
BEGIN DESCRIPTION:
Mapping XS 998a59e1
END DESCRIPTION:
XS GIS Cut Line= 5
      2248592.03     13240963.87      2248636.65     13240818.53
      2248558.55     13240734.57      2248337.39      13240544.2
      2248217.28     13240351.48
#Sta/Elev= 30
  4699.9  246.71  4843.5  245.28  4873.5  242.14  4916.1  240.96  4944.4   244.8
  4951.2  242.97  5007.7  244.97  5036.2  242.82  5058.1  244.58  5072.4  242.94
  5093.2  244.31  5099.8  242.06  5107.5  243.47  5114.1  240.89  5142.4  239.56
  5206.2  244.41  5220.5  242.96  5228.2  245.59  5285.4  246.21  5291.3  247.84
    5322  248.88  5327.9  247.42  5337.4  249.17  5343.3  247.95  5395.2  251.57
  5401.1  250.03  5422.3   253.3  5458.9  253.81  5474.2  256.01  5485.5  255.19
#Mann= 3 , 0 , 0
  4699.9      .1       0  5007.7     .07       0  5058.1      .1       0
#XS Ineff= 2 , 0
       0 4986.11  245.08 5091.98       0  244.32
Permanent Ineff=
       T       T
Bank Sta=5007.7,5058.1
XS Rating Curve= 0 ,0
Exp/Cntr=0.3,0.1

Type RM Length L Ch R = 1 ,6132    ,280,280,280
BEGIN DESCRIPTION:
Mapping XS cc9d7fb0
END DESCRIPTION:
XS GIS Cut Line= 4
      2248635.44     13240982.95      2248674.68     13240811.63
      2248636.93     13240762.56      2248303.77     13240267.01
#Sta/Elev= 30
  4665.9   245.6  4789.1  243.47  4857.6  243.75  4885.5  241.17  4903.6   243.6
  4913.8  243.26  4934.8  240.52  4970.8  239.82  5006.6  238.67    5043  239.96
  5144.8  239.63  5151.4  240.87  5210.7  243.86  5237.8  243.71  5246.7  244.78
  5259.9  243.65  5267.7  245.91  5273.8   243.8  5282.7  244.16  5309.8  247.67
  5354.7  250.06  5360.8  248.35  5368.3  248.56  5381.8  250.05  5390.7  249.94
  5396.8  251.61  5411.7  251.33  5426.7   253.8  5447.7   255.6  5500.7  258.82
#Mann= 3 , 0 , 0
  4665.9      .1       0  4970.8     .05       0    5043      .1       0
Bank Sta=4970.8,5043
XS Rating Curve= 0 ,0
Exp/Cntr=0.3,0.1

Type RM Length L Ch R = 1 ,5852    ,342,342,342
BEGIN DESCRIPTION:
UNT 024 IN RACR 11.0
END DESCRIPTION:
XS GIS Cut Line= 4
      2249356.37     13240944.51      2249065.26     13240804.56
      2248491.36     13240188.67      2248456.07     13240150.66
#Sta/Elev= 30
  4304.4  251.14  4309.5  250.05  4347.3  248.33  4354.8  247.15  4405.6  244.86
  4422.7  245.19  4614.8  240.75    4702  240.19  4730.3  238.42  4737.1  237.39
  4772.8  235.65  4801.1  235.56  4807.7  234.68  4815.3  235.66  4836.3  235.47
  4864.6  236.72  4984.8  238.16  5013.2  237.55  5076.7  238.99  5112.4  238.01
  5154.9  239.31    5169  241.09  5211.5   242.6  5246.7  245.83  5324.4  248.73
  5331.7  249.75  5374.2  251.29  5487.1  258.28  5494.4  257.62  5521.1  259.93
#Mann= 3 ,-1 , 0
  4304.4     .07       0  4737.1     .05       0  5013.2      .1       0
Bank Sta=4730.3,4984.8
XS Rating Curve= 0 ,0
Exp/Cntr=0.3,0.1

Type RM Length L Ch R = 1 ,5510    ,358,358,358
BEGIN DESCRIPTION:
UNT 024 IN RACR 10.0
END DESCRIPTION:
XS GIS Cut Line= 3
      2249471.17     13240880.12      2249093.25     13240524.61
      2248758.01     13240060.85
#Sta/Elev= 30
  4387.5   254.3  4393.3   254.3  4399.3  253.14  4441.8  252.06  4459.4  250.51
  4583.4  244.18  4611.8  242.07  4653.8  240.62  4696.3  240.94  4760.2  239.01
  4894.6  237.36  4901.1  237.07  4958.8  235.52  4988.2  235.58    5002  234.16
  5029.9  236.36  5088.7  237.17  5130.5  236.86  5151.4  237.66  5166.1  237.59
  5195.5  240.81  5217.1  241.11  5245.8   243.9  5266.7  243.97  5296.1  247.22
  5381.9  251.01  5446.5   254.4  5453.1  255.42    5474  255.83  5478.6  256.68
#Mann= 5 ,-1 , 0
  4387.5     .05       0  4459.4      .1       0  4901.1     .05       0
  5151.4     .16       0  5217.1      .1       0
Bank Sta=4894.6,5151.4
XS Rating Curve= 0 ,0
Exp/Cntr=0.3,0.1

Type RM Length L Ch R = 1 ,5152    ,449,449,449
BEGIN DESCRIPTION:
UNT 024 IN RACR 9.0
END DESCRIPTION:
XS GIS Cut Line= 3
      2249737.74     13240696.87      2249337.72     13240296.85
      2248987.71     13239946.85
#Sta/Elev= 30
  4452.5  252.17  4487.9   251.2  4509.1  249.53  4523.2  249.48  4537.4  248.33
  4603.4  245.61  4664.7  243.38  4834.4  236.08  4848.5  235.91  4890.9  234.96
  4961.6  234.15  4986.9   233.6  4989.7   233.1  4992.9   233.6  5103.1  234.76
  5173.8  236.03  5202.1  237.07  5216.2  238.46  5230.3  239.15  5244.5  240.67
  5286.9  241.95  5301.1  243.75  5329.3  245.47  5371.8  247.43  5385.9  248.58
  5400.1  249.03  5414.2  250.19  5470.8  253.12  5484.9  254.23  5513.2  255.35
#Mann= 4 ,-1 , 0
  4452.5     .05       0  4603.4      .1       0  4848.5     .05       0
  5173.8      .1       0
Bank Sta=4848.5,5173.8
XS Rating Curve= 0 ,0
Exp/Cntr=0.3,0.1

Type RM Length L Ch R = 1 ,4703    ,504,504,504
BEGIN DESCRIPTION:
UNT 024 IN RACR 8.0
END DESCRIPTION:
XS GIS Cut Line= 3
      2249887.73     13240496.88      2249737.72     13240096.85
      2249337.73     13239696.87
#Sta/Elev= 30
  4564.8  248.55    4580  247.92  4586.2  246.51  4610.2  246.95  4618.2  245.66
  4640.5  245.83    4713  244.16  4767.8  243.31  4830.9  241.46  4921.7  235.48
    4952  232.48  4970.7  231.71  4982.2  231.96  4986.4   231.2  4989.1   230.7
  4992.4   231.2  5006.2   231.2  5048.6  232.68  5076.9  232.05  5133.5  233.06
  5232.4  237.85  5359.7  242.48  5402.2   244.6  5416.3  244.66  5430.4  245.79
  5444.6  245.11  5472.9  247.23  5501.1  248.18  5529.4  250.08  5557.7  250.66
#Mann= 4 ,-1 , 0
  4564.8     .05       0    4713      .1       0  4986.4     .07       0
  4992.4      .1       0
Bank Sta=4986.4,4992.4
XS Rating Curve= 0 ,0
Exp/Cntr=0.3,0.1

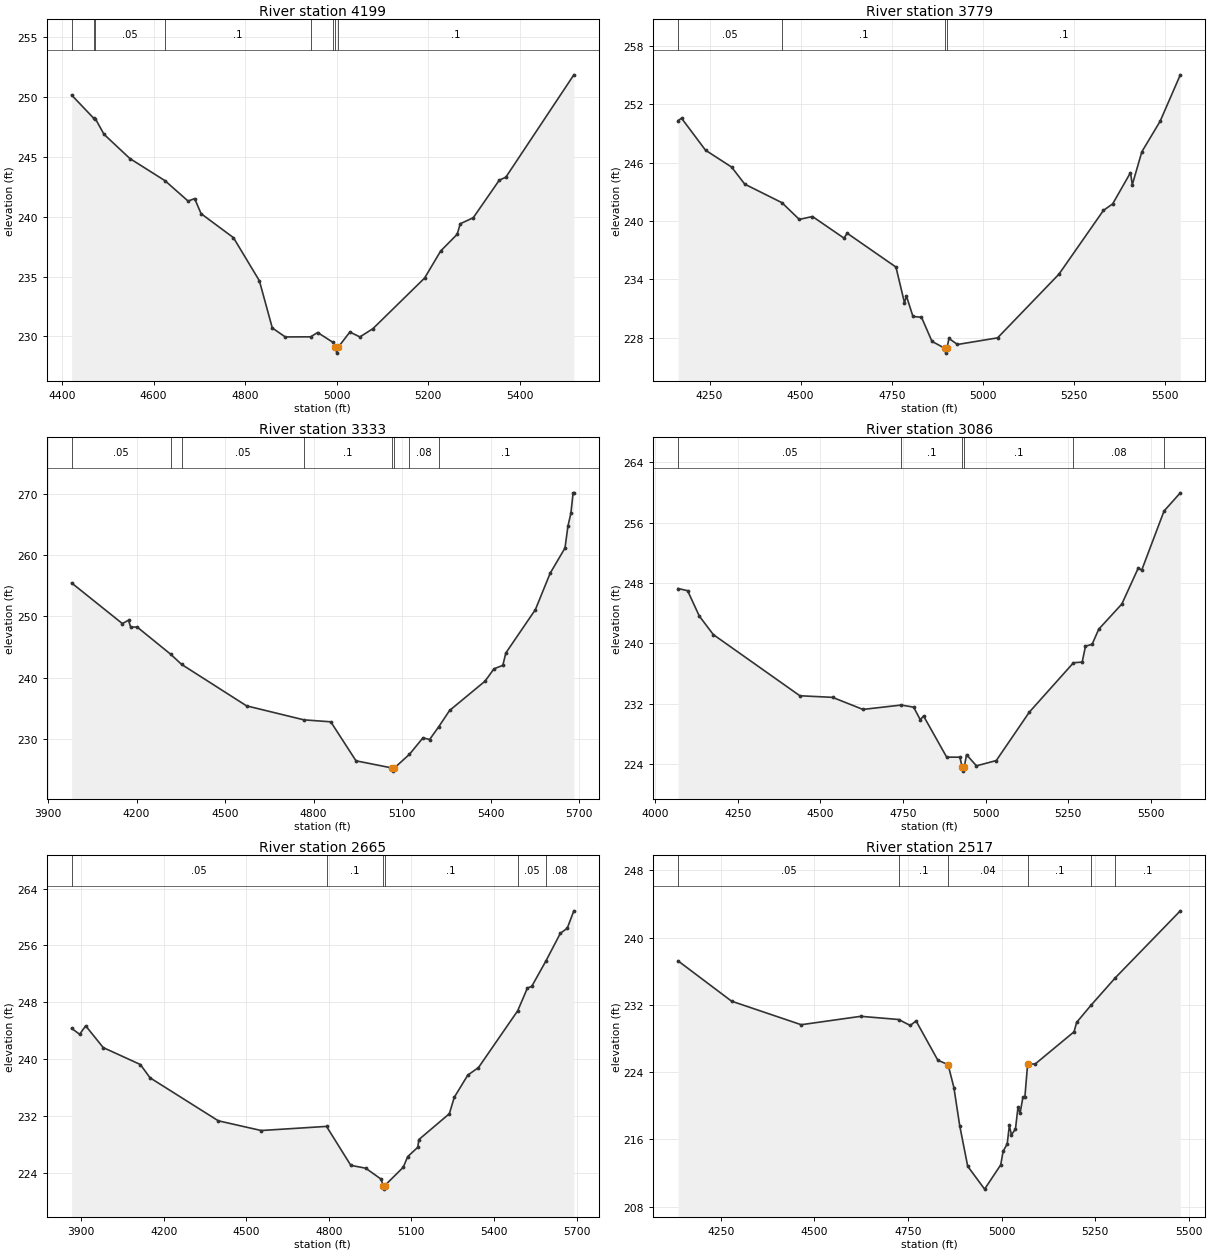
Type RM Length L Ch R = 1 ,4199    ,420,420,420
BEGIN DESCRIPTION:
UNT 024 IN RACR 7.0
END DESCRIPTION:
XS GIS Cut Line= 3
       2250387.7     13240146.83      2249987.72     13239746.85
      2249587.69     13239396.83
#Sta/Elev= 30
  4420.8  250.13  4469.2  248.19  4472.6  248.16  4491.5  246.86    4548  244.84
  4624.8  242.99  4675.3  241.29  4689.5   241.5  4703.6  240.24  4774.3  238.24
  4830.9  234.65  4859.2  230.71  4887.5  229.96    4943  229.97  4958.2  230.33
  4990.9  229.53  4997.2  229.11    5000  228.61  5003.2  229.11  5028.7  230.37
  5050.5  229.96    5079  230.65  5191.9  234.87  5227.1  237.13  5263.1  238.52
  5269.8   239.4  5298.2   239.9  5355.2  243.04  5369.4  243.28    5518  251.82
#Mann= 8 ,-1 , 0
  4420.8     .05       0  4469.2      .1       0  4472.6     .05       0
  4624.8      .1       0    4943     .16       0  4990.9      .1       0
  4997.2     .07       0  5003.2      .1       0
Bank Sta=4997.2,5003.2
XS Rating Curve= 0 ,0
Exp/Cntr=0.3,0.1

Type RM Length L Ch R = 1 ,3779    ,446,446,446
BEGIN DESCRIPTION:
UNT 024 IN RACR 6.0
END DESCRIPTION:
XS GIS Cut Line= 4
      2250696.57     13239891.78      2250418.79     13239483.78
      2249787.28     13239206.01      2249592.39     13239193.01
#Sta/Elev= 30
  4163.5  250.34  4172.9  250.58  4238.7  247.29  4310.5  245.55  4346.4   243.8
  4448.6  241.89  4496.2  240.17  4532.4  240.47  4618.8  238.25  4627.7  238.75
  4761.6  235.27    4785   231.6  4790.4  232.29  4808.3  230.19  4831.7  230.11
  4860.5  227.63  4895.6  226.92  4898.3  226.42  4901.6  226.92  4907.1  227.93
  4930.5  227.31  5040.6  227.99  5209.1  234.54  5331.3   241.1  5356.6  241.77
  5405.5  244.98  5410.5  243.74  5436.7  247.13  5486.8  250.26  5542.3  255.04
#Mann= 4 ,-1 , 0
  4163.5     .05       0  4448.6      .1       0  4895.6     .07       0
  4901.6      .1       0
Bank Sta=4895.6,4901.6
XS Rating Curve= 0 ,0
Exp/Cntr=0.3,0.1

Type RM Length L Ch R = 1 ,3333    ,247,247,247
BEGIN DESCRIPTION:
UNT 024 IN RACR 5.0
END DESCRIPTION:
XS GIS Cut Line= 3
      2251037.68     13239546.83      2250237.72     13238946.85
      2249537.76     13238996.85
#Sta/Elev= 30
  3980.2  255.45    4152  248.84  4172.9  249.38  4180.2  248.26    4202  248.28
  4316.1  243.83  4352.5   242.2  4572.9  235.44  4767.2  233.16  4858.3  232.84
  4943.7  226.49  5067.4  225.31  5070.1  224.81  5073.4  225.31  5124.9  227.55
  5170.6  230.23  5193.2  229.96  5223.5     232  5260.9  234.69  5381.2  239.47
  5411.2  241.47  5441.3  242.04  5451.4  244.05  5551.6  251.11  5601.7  257.04
  5651.9  261.14  5661.9   264.7  5671.9  266.81  5679.4  270.13  5681.9  270.13
#Mann= 8 ,-1 , 0
  3980.2     .05       0  4316.1      .1       0  4352.5     .05       0
  4767.2      .1       0  5067.4     .07       0  5073.4      .1       0
  5124.9     .08       0  5223.5      .1       0
Bank Sta=5067.4,5073.4
XS Rating Curve= 0 ,0
Exp/Cntr=0.3,0.1

Type RM Length L Ch R = 1 ,3086    ,421,421,421
BEGIN DESCRIPTION:
UNT 024 IN RACR 4.0
END DESCRIPTION:
XS GIS Cut Line= 3
      2250933.09      13239132.2      2250503.42     13238717.73
      2249580.82     13238715.56
#Sta/Elev= 30
  4069.6  247.26  4098.4  246.97  4133.6  243.62  4176.1  241.16    4438  233.06
  4536.8  232.85  4628.9  231.25  4744.9  231.83  4782.3  231.55  4802.3  229.89
  4812.3  230.38  4882.3  224.93  4922.3  224.93  4929.3  223.58    4932  223.08
  4935.3  223.58  4942.3  225.26  4972.3  223.78  5032.3  224.48  5132.3  230.89
  5265.9  237.43  5292.3  237.52  5302.3  239.63  5322.3  239.87  5342.3  241.87
  5412.3  245.21  5462.3     250  5472.3  249.68    5540  257.52  5589.2  259.93
#Mann= 6 ,-1 , 0
  4069.6     .05       0  4744.9      .1       0  4929.3     .07       0
  4935.3      .1       0  5265.9     .08       0    5540      .1       0
Bank Sta=4929.3,4935.3
XS Rating Curve= 0 ,0
Exp/Cntr=0.3,0.1

Type RM Length L Ch R = 1 ,2665    ,148,148,148
BEGIN DESCRIPTION:
Mapping XS e2067751
END DESCRIPTION:
XS GIS Cut Line= 4
      2251109.17     13238916.93      2250442.52     13238344.03
      2250067.52     13238319.73       2249520.8      13238478.9
#Sta/Elev= 30
  3865.8  244.32  3894.8  243.48  3916.7  244.68  3980.4  241.61  4115.4  239.22
  4150.5  237.35  4398.5  231.29  4554.3  229.92  4791.6   230.5  4879.9  225.01
    4934  224.61  4990.1  223.06  4997.1  222.16  4999.9  221.66  5003.1  222.16
  5070.3  224.74  5086.5  226.24  5123.1  227.56  5126.9  228.64  5237.8  232.29
  5255.8  234.61  5304.8  237.73  5343.6  238.79  5486.1   246.8  5521.5  250.01
    5537  250.23  5589.2  253.86  5641.1  257.72    5666  258.42    5690  260.88
#Mann= 6 ,-1 , 0
  3865.8     .05       0  4791.6      .1       0  4997.1     .07       0
  5003.1      .1       0  5486.1     .05       0  5589.2     .08       0
Bank Sta=4997.1,5003.1
XS Rating Curve= 0 ,0
Exp/Cntr=0.3,0.1

Type RM Length L Ch R = 1 ,2517    ,63,63,63
BEGIN DESCRIPTION:
Mapping XS 14670b18
END DESCRIPTION:
XS GIS Cut Line= 5
      2250909.24     13238656.96      2250646.65     13238448.63
      2250232.16     13238199.06      2250136.67     13238155.66
      2249733.34     13238261.91
#Sta/Elev= 30
    4136  237.24  4278.8  232.45  4464.7  229.65  4623.8  230.65  4725.1  230.27
  4755.8  229.56  4771.4   230.1  4829.6  225.42  4856.8  224.91  4872.4  222.18
  4887.9  217.65  4909.3  212.81  4954.4  210.09  4997.5  212.98  5003.8  214.59
  5014.8  215.47  5020.5  217.67    5026  216.56  5036.8  217.23  5043.6  219.84
  5049.1   219.1  5056.6     221  5061.9     221  5069.2  224.94  5089.8  224.99
  5193.3  228.81  5200.2  229.93  5238.4  231.96  5303.8  235.25    5477   243.2
#Mann= 6 ,-1 , 0
    4136     .05       0  4725.1      .1       0  4856.8     .04       0
  5069.2      .1       0  5238.4     .05       0  5303.8      .1       0
Bank Sta=4856.8,5069.2
XS Rating Curve= 0 ,0
Exp/Cntr=0.3,0.1