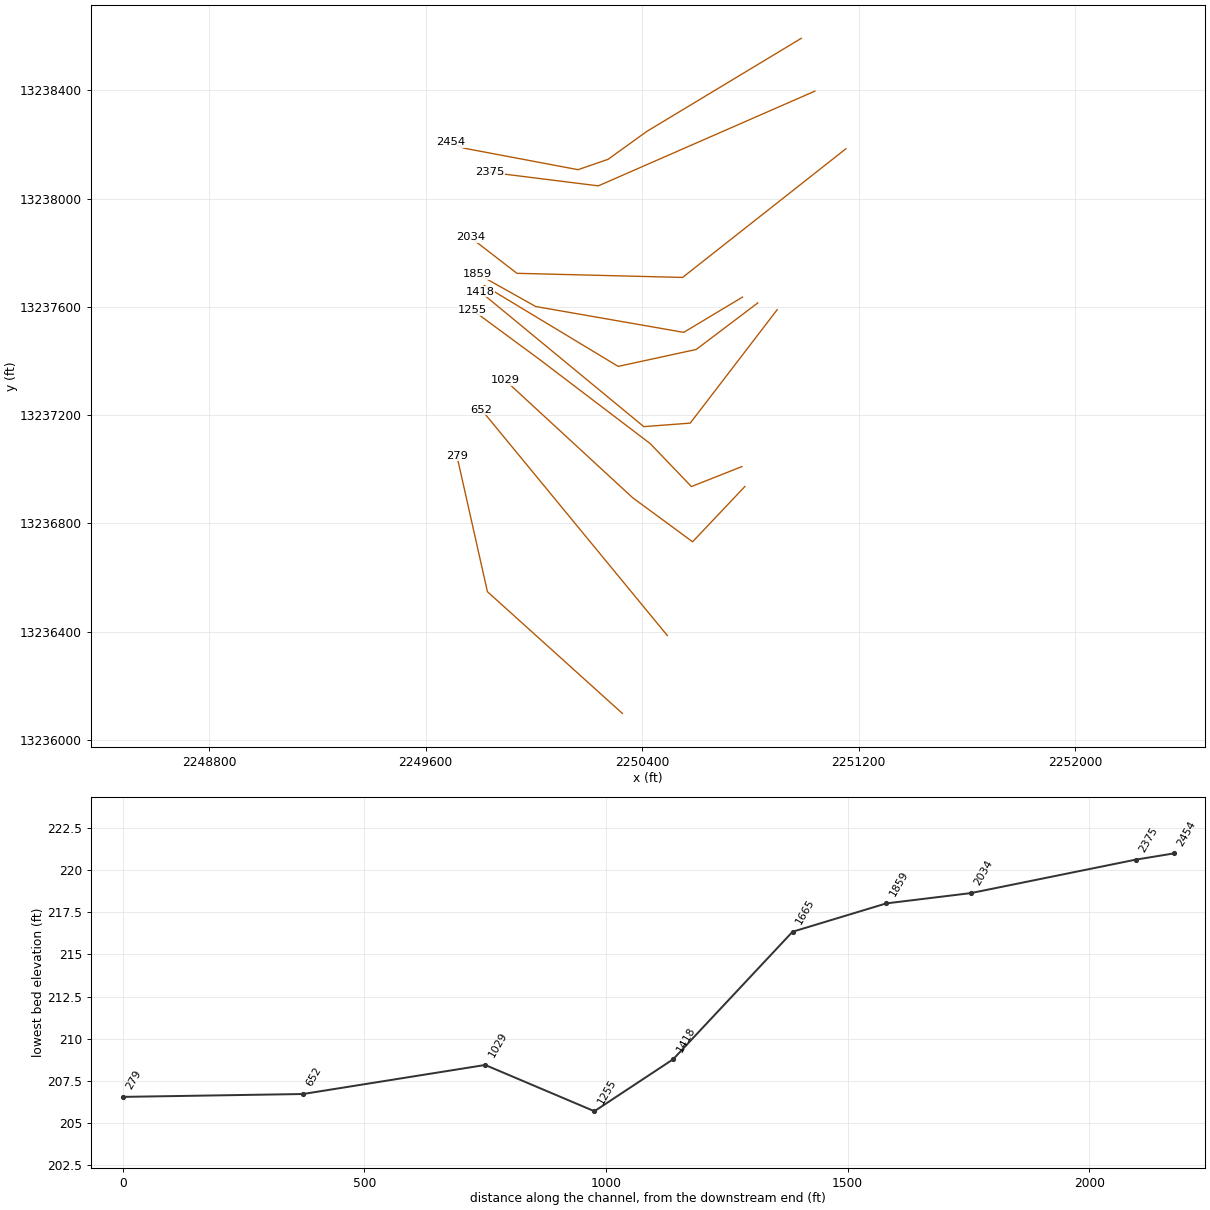
HEC-RAS study UNT 024 IN RACR.prj: UNT 024 IN RACR Base Level Engineering

--- UNT 024 IN RACR.g01 (geometry) --- (continued)

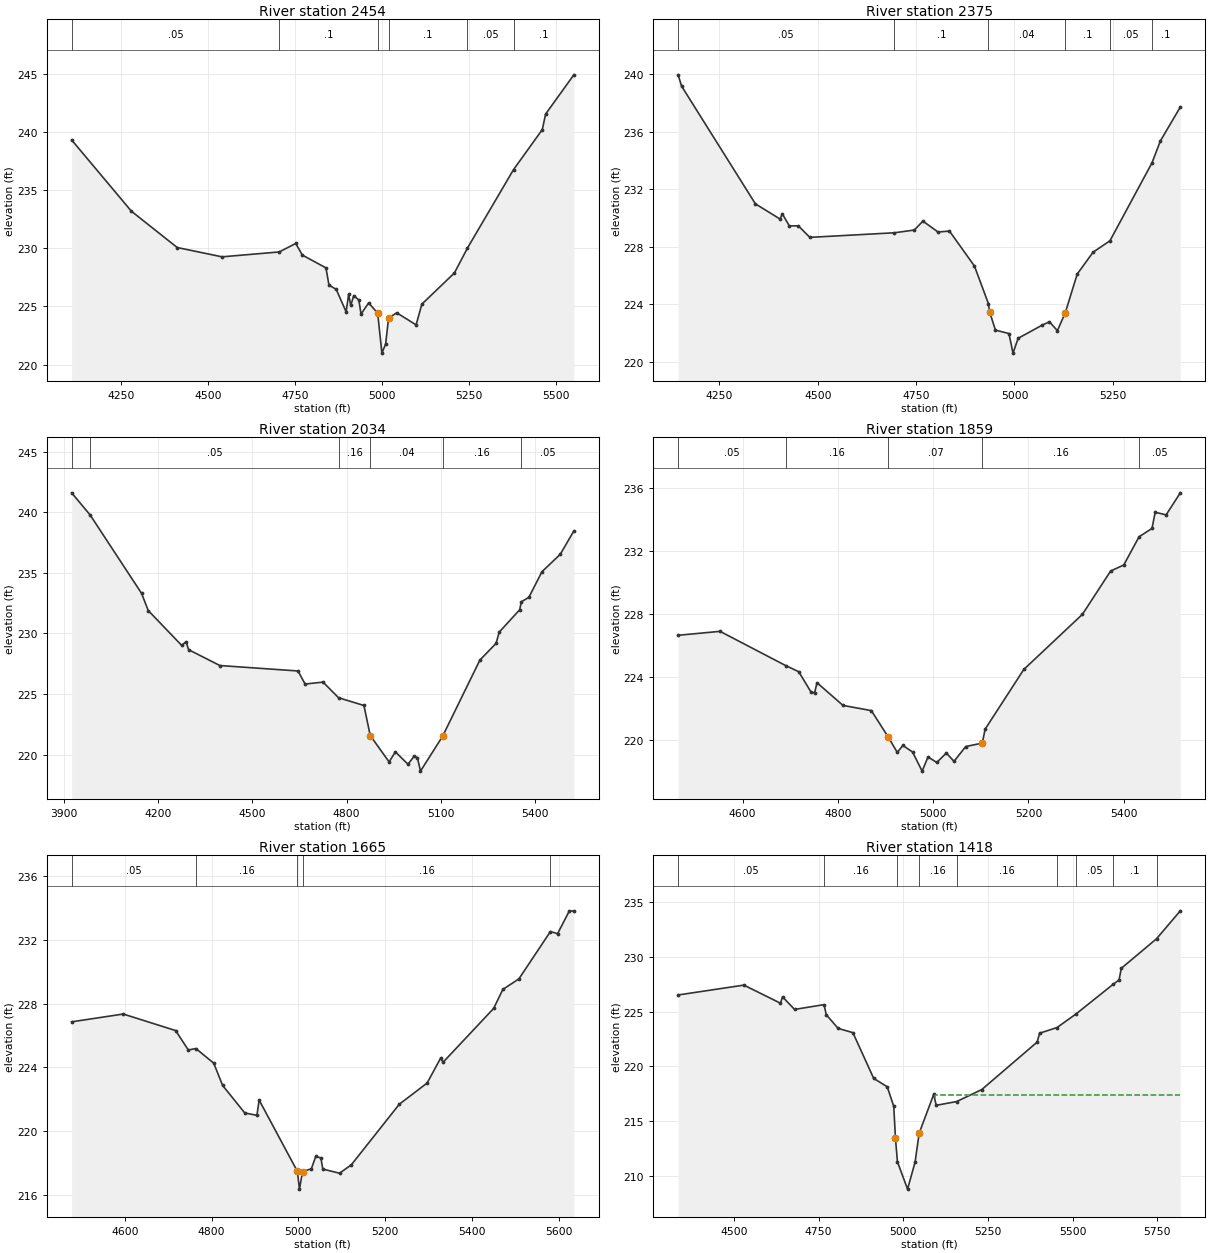
Type RM Length L Ch R = 1 ,2454    ,79,79,79
BEGIN DESCRIPTION:
Mapping XS e1c145bb
END DESCRIPTION:
XS GIS Cut Line= 6
      2250987.39     13238591.87      2250416.88     13238248.05
      2250273.55     13238144.86      2250162.71     13238106.63
       2249741.7     13238186.04      2249692.27     13238207.53
#Sta/Elev= 30
  4107.9  239.31  4279.6  233.18  4411.1  230.06  4539.8  229.26  4704.1  229.68
  4751.4  230.41  4770.6  229.41  4838.3  228.31  4846.9  226.83  4867.8  226.46
  4896.2  224.53  4903.4  226.03  4909.5  225.08  4918.1  225.93  4932.8  225.54
    4939  224.34  4960.9   225.3  4986.9  224.41  4998.9  220.98  5009.7  221.77
  5018.1  223.99  5041.4  224.45  5097.2  223.41  5113.7  225.19  5207.1  227.87
  5244.6  230.01    5377  236.76  5459.6   240.2  5469.2  241.54  5550.2  244.91
#Mann= 6 ,-1 , 0
  4107.9     .05       0  4704.1      .1       0  4986.9     .04       0
  5018.1      .1       0  5244.6     .05       0    5377      .1       0
Bank Sta=4986.9,5018.1
XS Rating Curve= 0 ,0
Exp/Cntr=0.3,0.1

Type RM Length L Ch R = 1 ,2375    ,341,341,341
BEGIN DESCRIPTION:
UNT 024 IN RACR 3.0
END DESCRIPTION:
XS GIS Cut Line= 3
      2251037.69     13238396.84      2250237.72     13238046.85
      2249837.71     13238096.86
#Sta/Elev= 30
  4145.2  239.94  4154.1  239.15  4341.6  230.98  4404.4  229.92  4409.9  230.29
  4427.8  229.45  4450.8  229.45    4480  228.65  4695.1  228.97  4745.5  229.16
  4767.3  229.78  4805.9  229.02  4834.8  229.09  4898.3  226.66  4933.8  224.05
 4936.65  223.49  4951.7  222.21    4986  221.97  4996.3  220.61  5009.4  221.64
  5068.8  222.53  5088.9  222.79  5109.1  222.17  5129.2  223.42  5159.5   226.1
  5199.8  227.62  5242.6  228.41  5349.4  233.82  5371.1  235.36  5421.5   237.7
#Mann= 6 ,-1 , 0
  4145.2     .05       0  4695.1      .1       0  4933.8     .04       0
  5129.2      .1       0  5242.6     .05       0  5349.4      .1       0
Bank Sta=4936.65,5129.2
XS Rating Curve= 0 ,0
Exp/Cntr=0.3,0.1

Type RM Length L Ch R = 1 ,2034    ,175,175,175
BEGIN DESCRIPTION:
UNT 024 IN RACR 2.0
END DESCRIPTION:
XS GIS Cut Line= 4
      2251152.33      13238183.9        2250549.     13237708.61
      2249937.02      13237723.8       2249765.6     13237856.16
#Sta/Elev= 30
  3925.6  241.61  3984.4  239.78  4147.9  233.31  4169.1  231.89  4275.2  229.02
  4289.4  229.31  4297.4  228.66  4396.8  227.35  4645.3   226.9  4667.9  225.82
  4724.9  225.98  4774.3  224.69    4855  224.05    4875  221.57    4935  219.39
    4955  220.22    4995   219.2    5015  219.87    5025  219.74  5034.8  218.63
  5105.1  221.51  5223.7   227.8  5275.1  229.18  5285.1  230.11  5350.4  231.96
  5355.2  232.61  5379.4  232.98  5421.1   235.1  5479.1  236.53  5522.4  238.46
#Mann= 6 ,-1 , 0
  3925.6      .1       0  3984.4     .05       0  4774.3     .16       0
    4875     .04       0  5105.1     .16       0  5355.2     .05       0
Bank Sta=4875,5105.1
XS Rating Curve= 0 ,0
Exp/Cntr=0.3,0.1

Type RM Length L Ch R = 1 ,1859    ,194,194,194
BEGIN DESCRIPTION:
Mapping XS f3964ba7
END DESCRIPTION:
XS GIS Cut Line= 4
      2250770.26     13237635.88      2250553.26     13237505.67
      2250006.38     13237601.16      2249791.76     13237721.35
#Sta/Elev= 30
  4464.6  226.64  4552.6  226.89  4690.3  224.72  4717.7  224.33  4743.6  223.04
  4751.1  222.99  4756.2  223.63  4810.7  222.19  4870.2  221.86    4906  220.17
  4924.6  219.21  4936.5  219.65  4956.8  219.23  4976.8  218.02  4989.2  218.92
  5007.5  218.57  5027.8  219.17  5043.7  218.64  5068.4  219.58  5103.2   219.8
    5109  220.68  5190.2  224.47  5313.3  227.97  5372.6  230.72  5400.1   231.1
  5432.2  232.89  5459.4  233.42  5466.1  234.45    5489  234.28  5518.8  235.68
#Mann= 5 ,-1 , 0
  4464.6     .05       0  4690.3     .16       0    4906     .07       0
  5103.2     .16       0  5432.2     .05       0
Bank Sta=4906,5103.2
XS Rating Curve= 0 ,0
Exp/Cntr=0.3,0.1

Type RM Length L Ch R = 1 ,1665    ,247,247,247
BEGIN DESCRIPTION:
Mapping XS dd6a5caa
END DESCRIPTION:
XS GIS Cut Line= 4
      2250826.71     13237614.35      2250599.27     13237442.47
      2250311.08     13237379.97      2249816.28     13237678.58
#Sta/Elev= 30
  4477.2  226.86  4596.2  227.35    4717  226.31  4746.1  225.09  4763.7  225.18
  4804.8  224.26  4825.3  222.86  4876.4  221.13  4904.4  220.98  4909.5  221.94
  4997.6  217.46  5002.5  216.34  5009.5  217.44  5029.9  217.62  5040.1   218.4
  5051.9   218.3  5056.3   217.6  5094.9  217.34  5122.1  217.87  5232.7  221.68
  5296.8  223.01  5327.8  224.57  5333.7  224.32  5450.1   227.7  5471.5   228.9
  5508.4  229.56  5581.2  232.54  5597.6   232.4  5624.8  233.84  5635.1  233.82
#Mann= 5 ,-1 , 0
  4477.2     .05       0  4763.7     .16       0  4997.6     .07       0
  5009.5     .16       0  5581.2     .05       0
Bank Sta=4997.6,5009.5
XS Rating Curve= 0 ,0
Exp/Cntr=0.3,0.1

Type RM Length L Ch R = 1 ,1418    ,163,163,163
BEGIN DESCRIPTION:
Mapping XS 37400b07
END DESCRIPTION:
XS GIS Cut Line= 4
      2250898.38     13237589.24      2250577.21     13237170.42
      2250405.77      13237157.4      2249801.54     13237655.51
#Sta/Elev= 30
  4335.4  226.51  4529.6  227.41  4637.5  225.76  4643.8  226.34  4679.2  225.19
  4766.5  225.63  4772.6  224.72  4807.9  223.46  4851.5  223.07  4912.8   218.9
  4952.9  218.13  4972.1  216.35  4977.1  213.45    4983  211.28  5012.9  208.79
  5035.1  211.26  5047.1  213.89  5090.1  217.44  5097.4  216.44  5157.6  216.78
  5232.1  217.88  5395.5  222.21  5402.8  223.02  5454.3  223.54  5509.6  224.76
  5620.5   227.5  5637.4  227.88  5643.9  228.94    5748  231.64  5818.2  234.19
#Mann= 9 ,-1 , 0
  4335.4     .05       0  4766.5     .16       0    4983     .07       0
  5047.1     .16       0  5157.6     .16       0  5454.3      .1       0
  5509.6     .05       0  5620.5      .1       0    5748     .05       0
#XS Ineff= 2 , 0
       0                 5092.54       0  217.38
Permanent Ineff=
       F       T
Bank Sta=4977.1,5047.1
XS Rating Curve= 0 ,0
Exp/Cntr=0.3,0.1

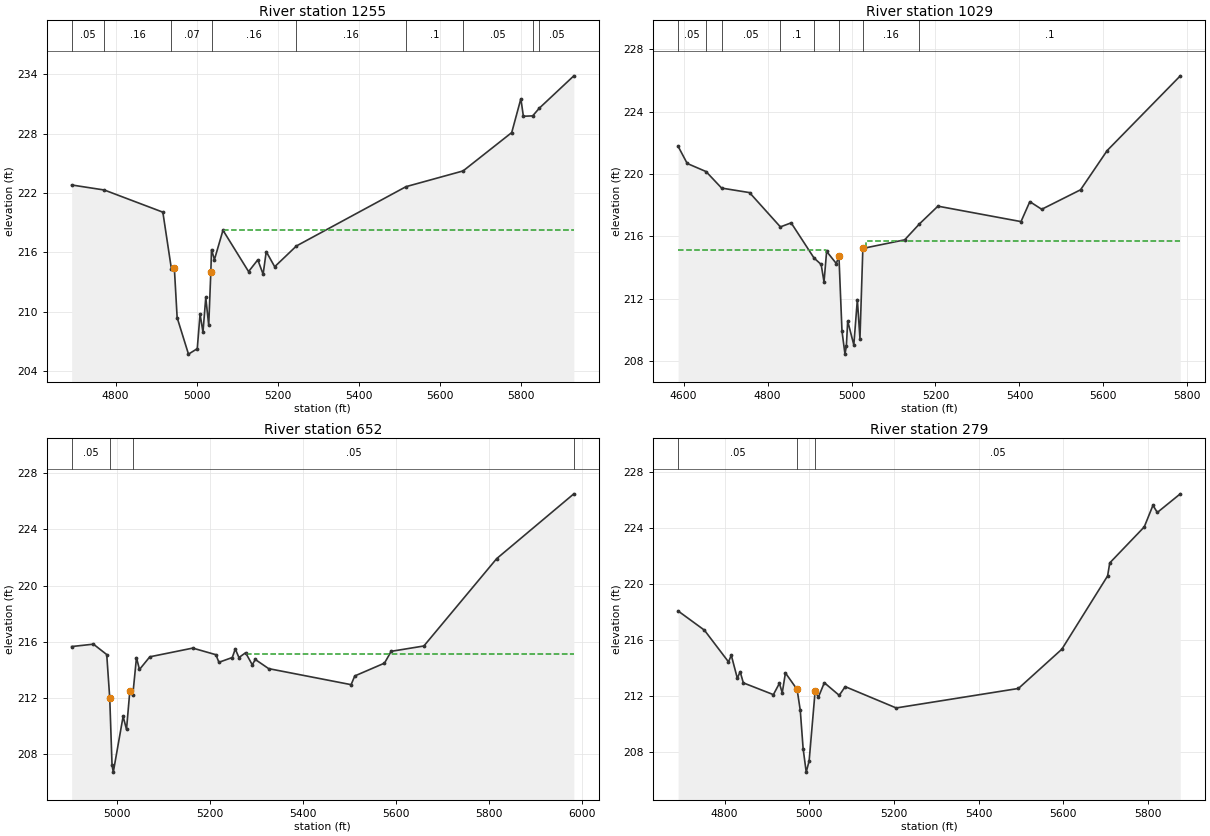
Type RM Length L Ch R = 1 ,1255    ,226,226,226
BEGIN DESCRIPTION:
Mapping XS 8e69ba73
END DESCRIPTION:
XS GIS Cut Line= 5
      2250768.19     13237009.83      2250581.55     13236936.04
      2250429.64     13237094.46      2250021.65     13237404.79
      2249774.24     13237587.09
#Sta/Elev= 30
  4691.6  222.82  4772.3  222.31  4916.8  220.07  4937.9  214.34  4945.2  214.41
  4952.1   209.4  4980.1  205.71  5001.8  206.26  5008.7  209.78  5015.9  207.93
  5022.8  211.44  5030.1  208.62 5035.32  214.06    5037  216.28  5044.2  215.27
  5065.3  218.24  5128.5  214.06  5151.3  215.25  5164.4  213.79  5172.1  216.08
    5193  214.55  5246.6  216.65  5517.3  222.65  5658.2  224.24  5778.3  228.12
  5800.9  231.54  5807.1  229.77  5830.1  229.81  5846.2  230.58  5931.7  233.86
#Mann= 9 ,-1 , 0
  4691.6     .05       0  4772.3     .16       0  4937.9     .07       0
    5037     .16       0  5246.6     .16       0  5517.3      .1       0
  5658.2     .05       0  5830.1      .1       0  5846.2     .05       0
#XS Ineff= 2 , 0
       0                 5066.67       0  218.31
Permanent Ineff=
       F       T
Bank Sta=4945.2,5035.32
XS Rating Curve= 0 ,0
Exp/Cntr=0.3,0.1

Type RM Length L Ch R = 1 ,1029    ,377,377,377
BEGIN DESCRIPTION:
Mapping XS 12a5a270
END DESCRIPTION:
XS GIS Cut Line= 4
      2250779.02     13236936.03      2250585.89     13236732.05
      2250364.53     13236894.81      2249893.61     13237328.84
#Sta/Elev= 30
    4587  221.78  4608.6  220.68  4653.5  220.16  4690.6   219.1  4757.1  218.81
  4830.6  216.61  4856.2  216.87  4910.6  214.62  4927.7   214.2  4934.5  213.08
  4940.7  215.04  4963.8  214.26    4970  214.75  4977.3  209.93  4984.4  208.45
  4987.7  208.95  4990.9  210.57  5005.5  209.04  5013.9  211.95  5020.1  209.45
    5027  215.23  5126.6  215.78  5161.7   216.8  5205.8  217.94  5403.7  216.95
  5424.7  218.23    5453  217.74  5545.5  218.99    5609  221.51  5783.1   226.3
#Mann= 8 ,-1 , 0
    4587     .05       0  4653.5      .1       0  4690.6     .05       0
  4830.6      .1       0  4910.6     .16       0    4970     .07       0
    5027     .16       0  5161.7      .1       0
#XS Ineff= 2 , 0
       0 4940.39  215.13 5033.64       0  215.71
Permanent Ineff=
       T       T
Bank Sta=4970,5027
XS Rating Curve= 0 ,0
Exp/Cntr=0.3,0.1

Type RM Length L Ch R = 1 ,652     ,373,373,373
BEGIN DESCRIPTION:
Mapping XS 01568f34
END DESCRIPTION:
XS GIS Cut Line= 2
      2250492.52     13236385.85       2249806.7     13237219.25
#Sta/Elev= 30
  4902.9  215.66  4949.7  215.83  4978.3  215.09  4984.8  211.97  4989.7  207.23
  4992.4  206.73  5013.5  210.69  5020.8  209.77  5027.9  212.48  5034.3  212.21
  5042.2  214.87  5048.7  214.03  5070.9  214.93  5163.2  215.55  5212.9  215.08
  5219.4  214.54  5248.1  214.88  5254.6  215.49  5262.4  214.88  5276.8  215.22
  5291.1  214.36  5297.6  214.74  5326.3  214.09  5503.5  212.95  5511.4  213.57
  5575.2  214.48  5589.6  215.32  5659.9   215.7  5816.3  221.91  5982.2  226.52
#Mann= 4 ,-1 , 0
  4902.9     .05       0  4984.8     .07       0  5034.3     .05       0
  5982.2      .1       0
#XS Ineff= 2 , 0
                         5278.61          215.16
Permanent Ineff=
       F       F
Bank Sta=4984.8,5027.9
XS Rating Curve= 0 ,0
Exp/Cntr=0.3,0.1

Type RM Length L Ch R = 1 ,279     ,0,0,0
BEGIN DESCRIPTION:
UNT 024 IN RACR 1.0
END DESCRIPTION:
XS GIS Cut Line= 3
      2250326.42     13236098.13      2249828.02     13236547.66
      2249715.17     13237049.86
#Sta/Elev= 30
  4690.3  218.06  4752.4  216.69  4809.2  214.43  4815.9   214.9  4830.1  213.26
  4836.8  213.73  4844.3  212.93  4915.3  212.09  4929.5   212.9  4936.2  212.22
  4943.7  213.64  4971.3  212.46  4978.8  210.96  4985.5  208.24  4992.8  206.56
  4999.7  207.36  5013.9  212.36  5021.4   211.9  5035.6  212.94  5070.7  212.04
  5084.9  212.66  5205.3  211.14  5493.9  212.53  5596.4  215.33  5704.5  220.56
  5709.6  221.49  5791.1  224.06  5811.6   225.6  5821.9  225.09  5876.2  226.42
#Mann= 3 , 0 , 0
  4690.3     .05       0  4971.3    .035       0  5013.9     .05       0
Bank Sta=4971.3,5013.9
XS Rating Curve= 0 ,0
Exp/Cntr=0.3,0.1
Stream Node=UNT 024 IN RACR ,Reach-1         , 0 , 0 ,Upstream end
Stream Node=UNT 024 IN RACR ,Reach-1         , 0 , 1 ,Downstream end

Chan Stop Cuts=-1
Use User Specified Reach Order=0
Composite Channel Slope=5