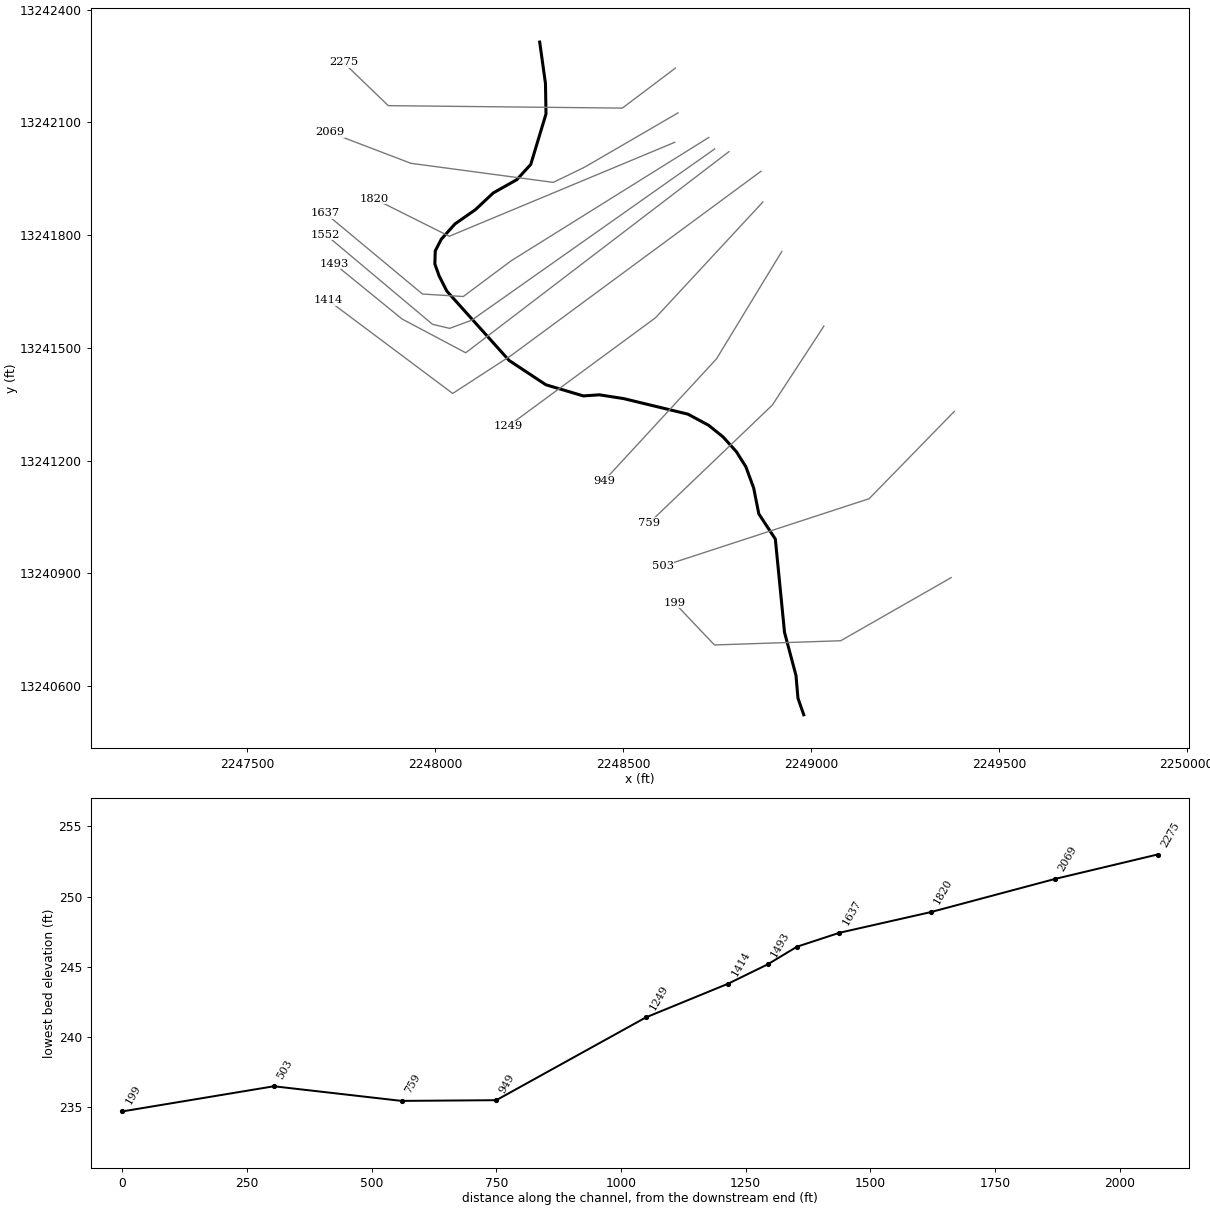
--- UNT 025 IN RACR.prj (project) ---

Proj Title=UNT 025 IN RACR Base Level Engineering
Current Plan=p01
Default Exp/Contr=0.3,0.1
English Units
Geom File=g01
Flow File=f01
Plan File=p01
Y Axis Title=Elevation
X Axis Title(PF)=Main Channel Distance
X Axis Title(XS)=Station
BEGIN DESCRIPTION:
UNT 025 IN RACR
END DESCRIPTION:
DSS Export Rating Curves= 0
DSS Export Rating Curve Sorted= 0
DSS Export Volume Flow Curves= 0
DXF OffsetX= 0
DXF OffsetY= 0
DXF ScaleX= 1
DXF ScaleY= 10

--- UNT 025 IN RACR.p01 (plan) ---

Plan Title=Multiple Run
Short Identifier=Multiple
Geom File=g01
Flow File=f01
Subcritical Flow
K Sum by GR= 0
Std Step Tol= 0.01
Critical Tol= 0.01
Num of Std Step Trials= 20
Max Error Tol= 0.3
Flow Tol Ratio= 0.001
Split Flow NTrial= 30
Split Flow Tol= 0.02
Split Flow Ratio= 0.02
Log Output Level= 0
Friction Slope Method= 1
Unsteady Friction Slope Method= 2
Unsteady Bridges Friction Slope Method= 1
Parabolic Critical Depth
Global Vel Dist=  1 , 1 , 1
Global Log Level= 0
CheckData=True
Encroach Param= -1, 0, 0, 0
BEGIN DESCRIPTION:
Multiple Run
END DESCRIPTION:

--- UNT 025 IN RACR.f01 (steady flow) ---

Flow Title=Multiple
Number of Profiles=7
Profile Names=10-year,25-year,50-year,1pct_min,100-year,1pct_plu,500-year
River Rch & RM= UNT 025 IN RACR,Reach-1,2275
     234     327     404     368     498     674     768
Boundary for River Rch & Prof#=UNT 025 IN RACR,Reach-1,1
Up Type=0
Dn Type=3
Dn Slope=0.005
Boundary for River Rch & Prof#=UNT 025 IN RACR,Reach-1,2
Up Type=0
Dn Type=3
Dn Slope=0.005
Boundary for River Rch & Prof#=UNT 025 IN RACR,Reach-1,3
Up Type=0
Dn Type=3
Dn Slope=0.005
Boundary for River Rch & Prof#=UNT 025 IN RACR,Reach-1,4
Up Type=0
Dn Type=3
Dn Slope=0.005
Boundary for River Rch & Prof#=UNT 025 IN RACR,Reach-1,5
Up Type=0
Dn Type=3
Dn Slope=0.005
Boundary for River Rch & Prof#=UNT 025 IN RACR,Reach-1,6
Up Type=0
Dn Type=3
Dn Slope=0.005
Boundary for River Rch & Prof#=UNT 025 IN RACR,Reach-1,7
Up Type=0
Dn Type=3
Dn Slope=0.005

--- UNT 025 IN RACR.g01 (geometry) ---

Geom Title=Existing Conditions
Program Version=4.10

River Reach=UNT 025 IN RACR ,Reach-1
Reach XY= 30
      2248278.33     13242313.52      2248293.68     13242203.42
      2248295.11     13242122.43      2248254.55     13241988.05
      2248217.63     13241947.59      2248154.87     13241912.22
      2248107.29     13241867.66        2248053.     13241829.73
      2248016.54     13241789.11      2248000.39     13241757.86
      2247999.35     13241722.96      2248010.81     13241691.19
      2248031.12     13241651.09      2248196.99     13241466.32
      2248294.89     13241401.63      2248394.47     13241372.02
       2248437.3     13241374.96      2248501.85     13241364.86
      2248672.79     13241323.48        2248728.      13241293.8
      2248766.02     13241263.07      2248801.43       13241224.
      2248826.95     13241183.38      2248847.72     13241126.85
      2248861.29     13241058.33      2248905.31     13240991.15
      2248929.79     13240742.71      2248960.29     13240628.17
       2248965.5     13240567.75      2248980.93     13240523.59

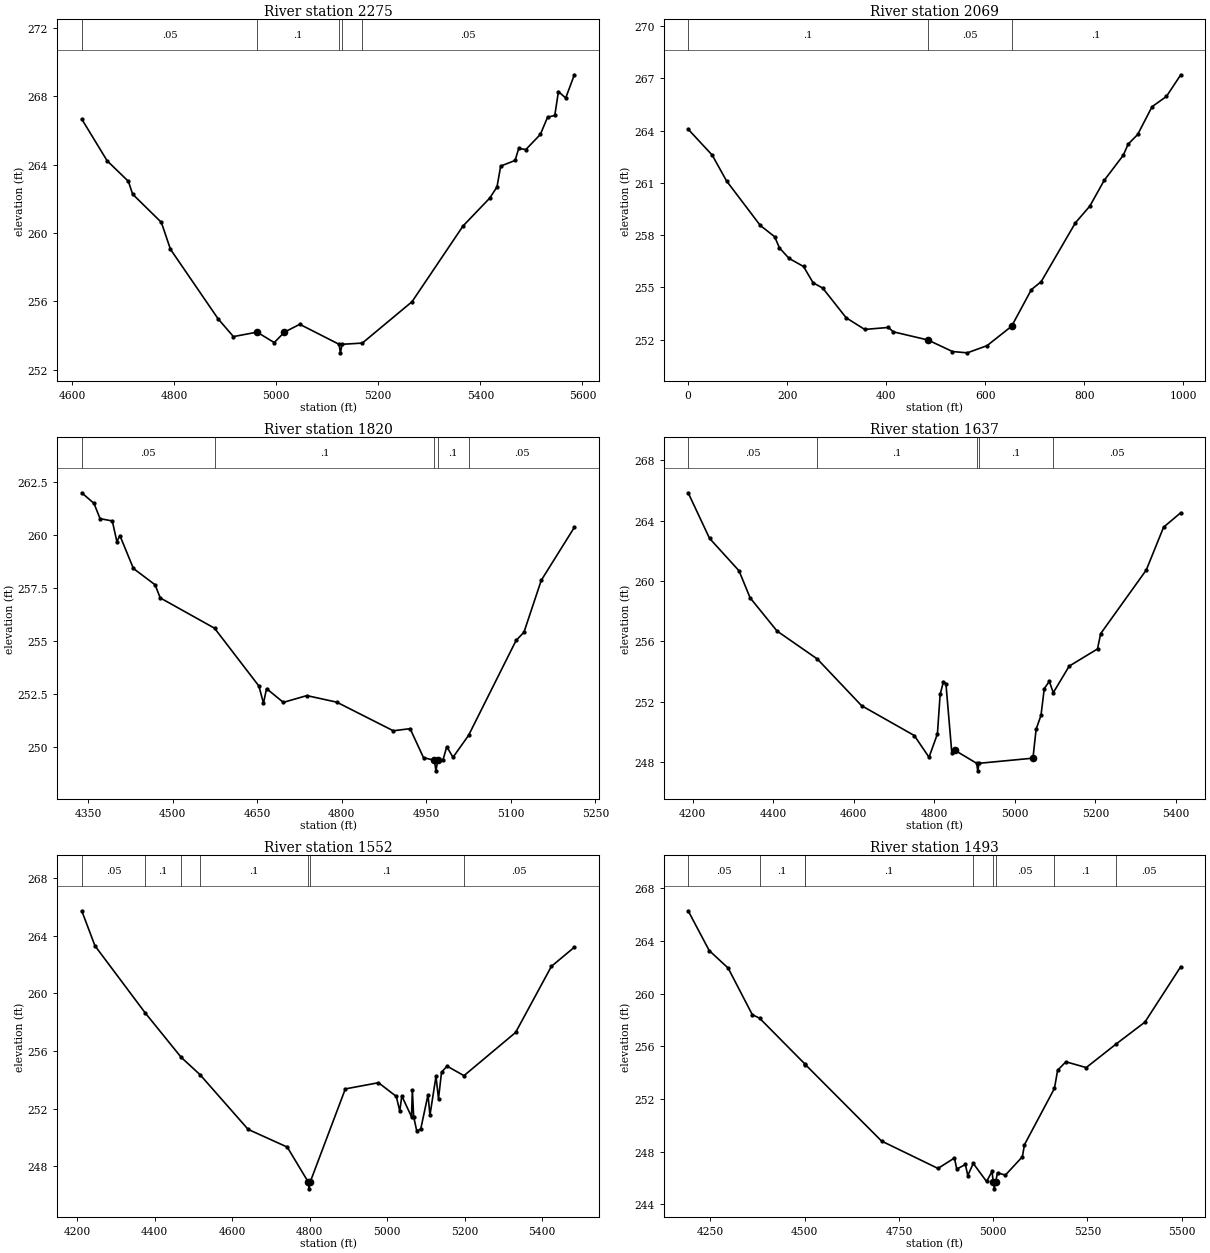
Type RM Length L Ch R = 1 ,2275    ,206,206,206
BEGIN DESCRIPTION:
UNT 025 IN RACR 4.0
END DESCRIPTION:
XS GIS Cut Line= 4
      2248639.28     13242244.21      2248498.21     13242137.86
      2247875.39     13242144.37      2247756.01     13242259.41
#Sta/Elev= 30
    4619  266.66  4668.8  264.22  4710.4  263.02  4718.7  262.27    4775  260.62
  4792.8  259.05  4886.2  254.98  4916.2  253.94  4962.6   254.2  4996.2  253.59
  5016.2   254.2  5046.2  254.66  5123.2  253.49  5125.9  252.99  5129.2  253.49
  5168.8  253.56  5266.2  255.98  5366.2  260.41  5418.5  262.04  5432.7  262.69
  5439.9  263.91  5468.2  264.24  5475.2  264.94  5489.3  264.88  5517.6  265.76
  5531.8  266.77  5545.9  266.87  5553.1  268.27  5567.3  267.89  5584.3  269.25
#Mann= 5 ,-1 , 0
    4619     .05       0  4962.6      .1       0  5123.2     .07       0
  5129.2      .1       0  5168.8     .05       0
#XS Ineff= 1 ,-1
 5042.61 5238.64  254.51
Permanent Ineff=
       T
Bank Sta=4962.6,5016.2
XS Rating Curve= 0 ,0
Exp/Cntr=0.3,0.1

Type RM Length L Ch R = 1 ,2069    ,249,249,249
BEGIN DESCRIPTION:
Mapping XS 5b352f12
END DESCRIPTION:
XS GIS Cut Line= 5
     2248646.403    13242125.119     2248397.706    13241980.588
     2248314.372    13241940.223     2247935.466    13241991.005
     2247720.622    13242073.036
#Sta/Elev= 30
       0264.0873   48.53262.6018   77.66261.1116   145.6258.5649  174.72257.9136
  184.43257.2695  203.84256.6699  232.97 256.206  252.38255.2703  271.79254.9651
  319.21253.2582  356.55252.5924  404.47252.7054  414.42252.4543   484.1251.9869
  533.87251.3237  563.73251.2482  603.55251.6585  653.32252.7762  693.13254.8758
  713.04255.3357  782.15258.7149  811.17259.6699  840.18261.1463  878.87262.5953
  888.54 263.225  907.89263.7848   936.9265.3786  965.92265.9675  994.93267.2115
#Mann= 3 , 0 , 0
       0      .1       0   484.1     .05       0  653.32      .1       0
Bank Sta=484.1,653.32
XS Rating Curve= 0 ,0
Exp/Cntr=0.3,0.1

Type RM Length L Ch R = 1 ,1820    ,183,183,183
BEGIN DESCRIPTION:
UNT 025 IN RACR 3.0
END DESCRIPTION:
XS GIS Cut Line= 3
      2248637.74     13242046.86      2248037.72     13241796.85
      2247837.74     13241896.84
#Sta/Elev= 30
    4339  262.01  4360.7  261.51  4371.5  260.79  4393.2  260.68  4401.3  259.71
  4406.7  259.99  4430.6  258.44    4469  257.67  4478.2  257.05  4574.5  255.62
  4653.2  252.89  4661.3  252.08  4666.7  252.77  4696.5  252.12  4738.2  252.44
  4791.3  252.13  4891.5  250.78  4921.3  250.88  4945.1  249.51  4964.4  249.39
  4967.1  248.89  4970.4  249.39  4979.8  249.42  4986.3  250.03  4997.4  249.53
  5024.9  250.56  5109.2  255.04  5123.2  255.43  5153.9  257.88  5212.6  260.38
#Mann= 5 ,-1 , 0
    4339     .05       0  4574.5      .1       0  4964.4     .07       0
  4970.4      .1       0  5024.9     .05       0
Bank Sta=4964.4,4970.4
XS Rating Curve= 0 ,0
Exp/Cntr=0.3,0.1

Type RM Length L Ch R = 1 ,1637    ,85,85,85
BEGIN DESCRIPTION:
Mapping XS 6bd27e47
END DESCRIPTION:
XS GIS Cut Line= 5
      2248728.22     13242059.72      2248203.08     13241732.05
      2248075.04     13241636.56      2247966.53     13241643.07
      2247708.31     13241857.89
#Sta/Elev= 30
  4188.6  265.85  4241.7  262.83  4314.9  260.68  4342.4  258.89  4409.2  256.69
  4509.5  254.83  4619.2  251.74  4750.2  249.76  4786.7  248.32  4807.6  249.87
  4814.3  252.48  4822.6  253.34  4828.8  253.17  4843.4  248.59  4851.7  248.77
    4905  247.92  4907.8  247.42    4911  247.92  5044.8  248.26  5052.7  250.18
  5064.8   251.1  5072.9  252.87  5085.4  253.35  5095.3   252.6  5134.8  254.36
  5205.1   255.5  5212.9  256.51  5326.2  260.73  5369.2  263.57  5411.9  264.53
#Mann= 5 ,-1 , 0
  4188.6     .05       0  4509.5      .1       0    4905     .07       0
    4911      .1       0  5095.3     .05       0
Bank Sta=4851.7,5044.8
XS Rating Curve= 0 ,0
Exp/Cntr=0.3,0.1

Type RM Length L Ch R = 1 ,1552    ,59,59,59
BEGIN DESCRIPTION:
Mapping XS c5c5325e
END DESCRIPTION:
XS GIS Cut Line= 5
      2248743.87     13242029.16      2248097.21     13241573.46
      2248038.62     13241551.76      2247993.04     13241562.61
      2247708.79      13241801.3
#Sta/Elev= 30
  4211.6  265.74  4245.7  263.31  4375.1  258.66  4468.4  255.56  4516.9  254.36
  4641.1  250.56  4742.1  249.33  4795.7  246.93  4798.4  246.43  4801.7  246.93
    4892  253.37  4977.6   253.8  5023.5  252.85  5032.5  251.83  5037.8  252.88
  5062.9  251.43    5065  253.31  5068.4  251.43  5076.4  250.45  5086.7  250.59
  5105.4  252.96  5110.4  251.54    5126  254.24  5132.5  252.69  5140.3  254.53
  5154.6  254.95  5198.3  254.29  5331.5  257.29  5423.9  261.88  5483.2  263.21
#Mann= 7 ,-1 , 0
  4211.6     .05       0  4375.1      .1       0  4468.4     .05       0
  4516.9      .1       0  4795.7     .07       0  4801.7      .1       0
  5198.3     .05       0
Bank Sta=4795.7,4801.7
XS Rating Curve= 0 ,0
Exp/Cntr=0.3,0.1

Type RM Length L Ch R = 1 ,1493    ,79,79,79
BEGIN DESCRIPTION:
Mapping XS 85cc623e
END DESCRIPTION:
XS GIS Cut Line= 4
      2248781.93     13242021.98      2248081.55     13241486.82
      2247912.14     13241576.67       2247731.3     13241723.92
#Sta/Elev= 30
    4191  266.29  4246.8  263.27    4297  261.94  4361.1   258.4  4380.5  258.13
  4500.7  254.65  4501.8  254.61  4703.9   248.8  4853.5  246.72  4897.1  247.51
  4903.4  246.67  4926.2  247.02  4932.5  246.18  4947.1   247.1  4982.3  245.73
  4996.9  246.49  5000.1  245.67  5002.9  245.17  5006.1  245.67  5011.4  246.39
  5032.2  246.21  5077.4  247.61  5082.8  248.52  5162.4   252.8  5170.8  254.18
  5192.8  254.82  5246.6  254.38  5326.8  256.19  5402.2  257.83  5497.4  262.05
#Mann= 9 ,-1 , 0
    4191     .05       0  4380.5      .1       0  4500.7     .05       0
  4501.8      .1       0  4947.1     .05       0  5000.1    .035       0
  5006.1     .05       0  5162.4      .1       0  5326.8     .05       0
Bank Sta=5000.1,5006.1
XS Rating Curve= 0 ,0
Exp/Cntr=0.3,0.1

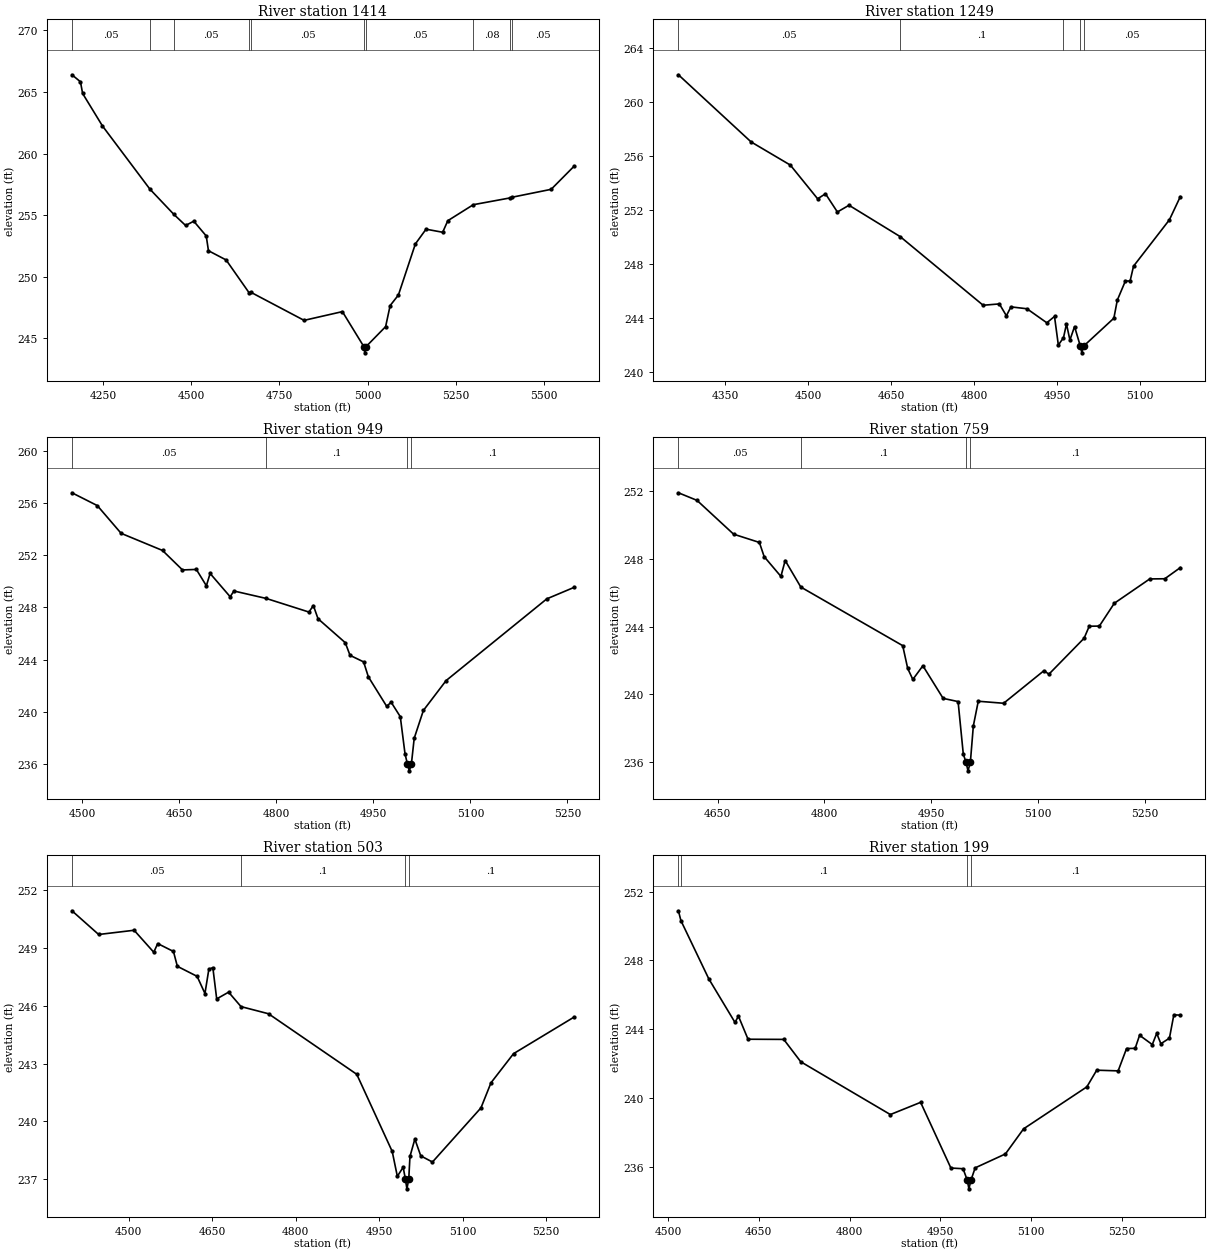
Type RM Length L Ch R = 1 ,1414    ,165,165,165
BEGIN DESCRIPTION:
UNT 025 IN RACR 2.0
END DESCRIPTION:
XS GIS Cut Line= 4
      2248867.18     13241969.74      2248203.11     13241480.14
      2248046.86     13241378.58      2247716.15     13241625.97
#Sta/Elev= 30
    4161   266.4  4185.1  265.83  4191.3  264.88  4247.6  262.24  4382.1  257.11
    4450  255.06  4483.6  254.15  4506.7   254.5  4542.1   253.3  4548.4   252.1
  4598.5  251.35  4663.3   248.7  4668.9  248.72  4819.8  246.44  4928.5  247.15
  4989.5   244.3  4992.2   243.8  4995.5   244.3  5051.2  245.93    5064  247.64
  5087.5   248.5  5135.6  252.65  5165.9  253.85  5213.1   253.6  5227.7  254.54
    5300  255.84  5404.1  256.39  5408.8  256.44    5521  257.09  5585.4  258.95
#Mann= 10 ,-1 , 0
    4161     .05       0  4382.1      .1       0    4450     .05       0
  4663.3      .1       0  4668.9     .05       0  4989.5    .035       0
  4995.5     .05       0    5300     .08       0  5404.1      .1       0
  5408.8     .05       0
Bank Sta=4989.5,4995.5
XS Rating Curve= 0 ,0
Exp/Cntr=0.3,0.1

Type RM Length L Ch R = 1 ,1249    ,300,300,300
BEGIN DESCRIPTION:
Mapping XS 7db5a39a
END DESCRIPTION:
XS GIS Cut Line= 3
      2248872.07     13241887.95      2248586.54     13241580.02
       2248194.7     13241291.74
#Sta/Elev= 30
  4265.9  262.03  4397.1  257.05    4468  255.33  4517.3  252.83  4531.5   253.2
    4553  251.85    4574  252.35  4666.5  250.02  4816.2  244.93  4845.5  245.03
  4858.2  244.15  4866.4  244.81  4895.4  244.67  4931.2  243.63  4945.1   244.1
    4952  241.98  4961.3  242.52  4966.7  243.54  4972.9  242.35  4981.3  243.35
  4991.7   241.9  4994.5   241.4  4997.7   241.9  5052.3  243.97  5058.5  245.31
  5073.1  246.73  5081.6  246.73  5087.8  247.83  5152.6  251.27  5172.3  252.99
#Mann= 5 ,-1 , 0
  4265.9     .05       0  4666.5      .1       0  4961.3     .05       0
  4991.7    .035       0  4997.7     .05       0
Bank Sta=4991.7,4997.7
XS Rating Curve= 0 ,0
Exp/Cntr=0.3,0.1

Type RM Length L Ch R = 1 ,949     ,190,190,190
BEGIN DESCRIPTION:
Mapping XS 6e3d440f
END DESCRIPTION:
XS GIS Cut Line= 3
      2248922.47     13241756.36      2248748.92     13241470.84
      2248449.39     13241146.12
#Sta/Elev= 30
    4484  256.77  4523.2  255.79    4560  253.67    4624  252.36  4654.9  250.87
  4676.3  250.91  4691.8  249.66  4697.6   250.6  4728.6  248.82  4734.4  249.26
  4784.4  248.69  4850.4  247.65  4857.2  248.15  4864.4  247.14  4906.5  245.31
  4913.9  244.34  4934.9  243.84  4942.2   242.7  4970.6  240.44  4977.4  240.76
  4991.6  239.65  4998.9  236.81  5002.7  236.01  5005.5  235.51  5008.7  236.01
  5013.1     238  5027.3  240.13  5062.4  242.41  5218.1  248.66  5259.9  249.53
#Mann= 4 ,-1 , 0
    4484     .05       0  4784.4      .1       0  5002.7     .07       0
  5008.7      .1       0
Bank Sta=5002.7,5008.7
XS Rating Curve= 0 ,0
Exp/Cntr=0.3,0.1

Type RM Length L Ch R = 1 ,759     ,256,256,256
BEGIN DESCRIPTION:
Mapping XS 8b55353b
END DESCRIPTION:
XS GIS Cut Line= 3
      2249034.45      13241557.6      2248897.29     13241347.66
      2248569.74     13241034.11
#Sta/Elev= 30
  4595.1  251.92  4621.2  251.47  4672.5  249.47  4708.7  248.98  4715.4  248.14
  4738.9  246.97  4744.9  247.91  4766.8  246.34  4909.8  242.87  4916.8  241.52
    4924  240.87  4938.1  241.68  4966.5  239.75  4987.5  239.56  4994.8  236.45
  4998.7  235.96  5001.4  235.46  5004.7  235.96  5008.9  238.12  5015.8  239.58
  5051.4  239.46    5108  241.39  5114.9  241.18  5164.3  243.31  5171.5  244.02
  5185.7  244.03  5206.7  245.38  5256.4  246.82  5277.5  246.83  5299.3  247.49
#Mann= 4 ,-1 , 0
  4595.1     .05       0  4766.8      .1       0  4998.7     .07       0
  5004.7      .1       0
Bank Sta=4998.7,5004.7
XS Rating Curve= 0 ,0
Exp/Cntr=0.3,0.1

Type RM Length L Ch R = 1 ,503     ,304,304,304
BEGIN DESCRIPTION:
Mapping XS 7c767308
END DESCRIPTION:
XS GIS Cut Line= 3
      2249381.63     13241330.89      2249154.84      13241098.5
      2248606.16     13240919.34
#Sta/Elev= 30
  4398.1  250.92  4446.1  249.69  4509.8  249.91  4545.1  248.77  4552.2  249.22
  4580.5  248.81  4587.5  248.04    4623  247.52  4637.1  246.63  4644.1  247.89
  4651.3  247.97  4658.2  246.35  4679.6   246.7  4701.9  245.95  4751.3  245.58
  4909.9  242.44  4973.6  238.44  4982.8  237.15  4993.3  237.62  4997.3     237
    5000   236.5  5003.3     237  5005.5  238.18  5014.3  239.08  5024.9  238.21
  5045.9  237.89  5133.1   240.7  5151.1     242  5191.6  243.51    5300   245.4
#Mann= 4 ,-1 , 0
  4398.1     .05       0  4701.9      .1       0  4997.3     .07       0
  5003.3      .1       0
Bank Sta=4997.3,5003.3
XS Rating Curve= 0 ,0
Exp/Cntr=0.3,0.1

Type RM Length L Ch R = 1 ,199     ,0,0,0
BEGIN DESCRIPTION:
UNT 025 IN RACR 1.0
END DESCRIPTION:
XS GIS Cut Line= 4
       2249373.2     13240888.54      2249079.26     13240720.57
      2248743.32     13240709.37      2248636.96     13240821.33
#Sta/Elev= 30
  4517.1  250.88  4521.2  250.31  4567.3  246.92  4610.5  244.39  4616.3  244.75
  4632.1  243.41  4691.1   243.4  4719.2   242.1  4867.2  239.03  4917.2  239.74
  4967.2  235.92  4987.3  235.88  4994.3  235.21    4997  234.71  5000.3  235.21
  5007.3  235.93  5057.3  236.74  5087.3   238.2  5191.8  240.64  5208.1  241.61
  5243.5  241.57  5257.4  242.87  5271.6  242.88  5278.9  243.64  5299.9   243.1
  5307.2  243.75  5314.1  243.15  5328.2  243.47  5335.5  244.83  5346.2  244.81
#Mann= 4 ,-1 , 0
  4517.1     .05       0  4521.2      .1       0  4994.3     .07       0
  5000.3      .1       0
Bank Sta=4994.3,5000.3
XS Rating Curve= 0 ,0
Exp/Cntr=0.3,0.1

Chan Stop Cuts=-1
Use User Specified Reach Order=0
Composite Channel Slope=5