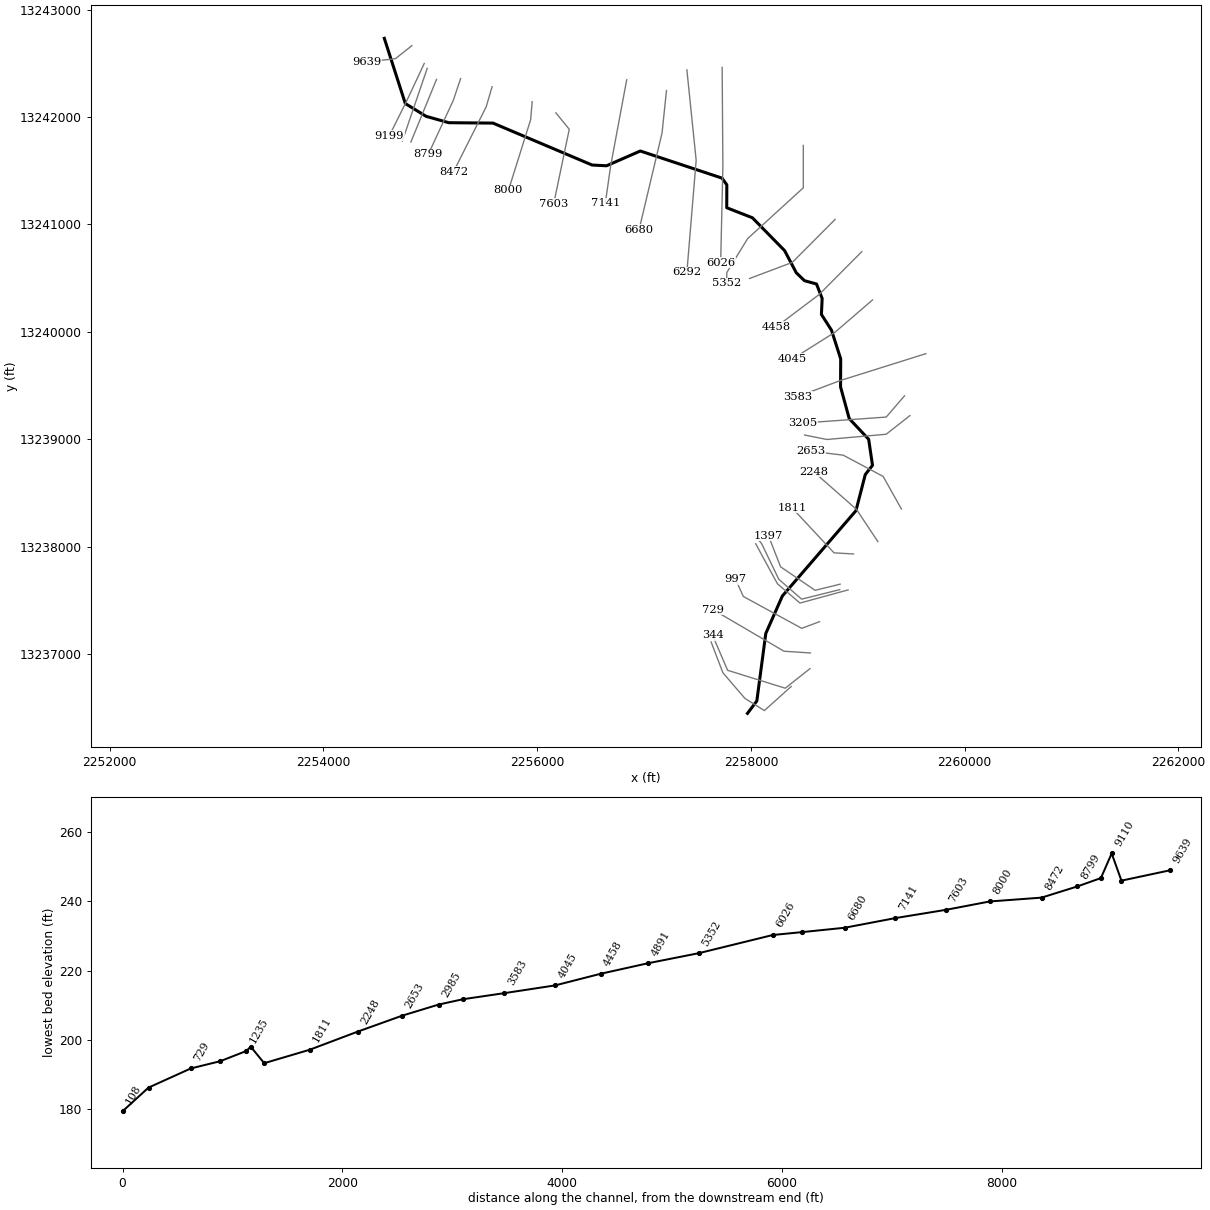
--- UNT 026 IN RACR.prj (project) ---

Proj Title=UNT 026 IN RACR Base Level Engineering
Current Plan=p01
Default Exp/Contr=0.3,0.1
English Units
Geom File=g01
Flow File=f01
Plan File=p01
Y Axis Title=Elevation
X Axis Title(PF)=Main Channel Distance
X Axis Title(XS)=Station
BEGIN DESCRIPTION:
UNT 026 IN RACR
END DESCRIPTION:
DSS Export Rating Curves= 0
DSS Export Rating Curve Sorted= 0
DSS Export Volume Flow Curves= 0
DXF OffsetX= 0
DXF OffsetY= 0
DXF ScaleX= 1
DXF ScaleY= 10

--- UNT 026 IN RACR.p01 (plan) ---

Plan Title=Multiple Run
Short Identifier=Multiple
Geom File=g01
Flow File=f01
Subcritical Flow
K Sum by GR= 0
Std Step Tol= 0.01
Critical Tol= 0.01
Num of Std Step Trials= 20
Max Error Tol= 0.3
Flow Tol Ratio= 0.001
Split Flow NTrial= 30
Split Flow Tol= 0.02
Split Flow Ratio= 0.02
Log Output Level= 0
Friction Slope Method= 1
Unsteady Friction Slope Method= 2
Unsteady Bridges Friction Slope Method= 1
Parabolic Critical Depth
Global Vel Dist=  1 , 1 , 1
Global Log Level= 0
CheckData=True
Encroach Param= -1, 0, 0, 0
BEGIN DESCRIPTION:
Multiple Run
END DESCRIPTION:

--- UNT 026 IN RACR.f01 (steady flow) ---

Flow Title=Multiple
Program Version=4.10
Number of Profiles= 7
Profile Names=10-year,25-year,50-year,1pct_min,100-year,1pct_plu,500-year
River Rch & RM=UNT 026 IN RACR,Reach-1         ,9639
     245     342     423     385     521     704     802
River Rch & RM=UNT 026 IN RACR,Reach-1         ,6026
     330     468     585     538     728     985    1145
Boundary for River Rch & Prof#=UNT 026 IN RACR,Reach-1         , 1
Up Type= 0
Dn Type= 3
Dn Slope=0.029
Boundary for River Rch & Prof#=UNT 026 IN RACR,Reach-1         , 2
Up Type= 0
Dn Type= 3
Dn Slope=0.029
Boundary for River Rch & Prof#=UNT 026 IN RACR,Reach-1         , 3
Up Type= 0
Dn Type= 3
Dn Slope=0.029
Boundary for River Rch & Prof#=UNT 026 IN RACR,Reach-1         , 4
Up Type= 0
Dn Type= 3
Dn Slope=0.029
Boundary for River Rch & Prof#=UNT 026 IN RACR,Reach-1         , 5
Up Type= 0
Dn Type= 3
Dn Slope=0.029
Boundary for River Rch & Prof#=UNT 026 IN RACR,Reach-1         , 6
Up Type= 0
Dn Type= 3
Dn Slope=0.029
Boundary for River Rch & Prof#=UNT 026 IN RACR,Reach-1         , 7
Up Type= 0
Dn Type= 3
Dn Slope=0.029
DSS Import GetInterval= 0
DSS Import GetPeak= 0
DSS Import FillOption= 0

--- UNT 026 IN RACR.g01 (geometry) ---

Geom Title=Existing Conditions
Program Version=4.10

River Reach=UNT 026 IN RACR ,Reach-1
Reach XY= 30
      2254569.82     13242733.29      2254766.13     13242125.91
      2254961.01     13242006.94      2255173.02     13241947.57
      2255586.62     13241943.95      2256513.78     13241553.47
       2256649.2     13241546.52      2256965.17     13241684.02
       2257729.8     13241431.54      2257774.69     13241368.95
      2257773.79     13241155.86      2258013.88     13241062.29
      2258315.49     13240756.29      2258424.54     13240550.16
       2258501.1     13240476.39      2258613.95     13240445.47
      2258666.68     13240310.86      2258659.83     13240162.15
      2258754.04     13240015.36       2258840.2     13239748.27
        2258839.     13239486.69      2258920.01     13239192.14
       2259101.9     13238999.43      2259137.72     13238756.86
      2259070.11     13238670.54      2258982.78     13238334.07
      2258294.32     13237539.76      2258139.28     13237191.07
      2258055.45     13236562.53      2257967.72     13236446.86

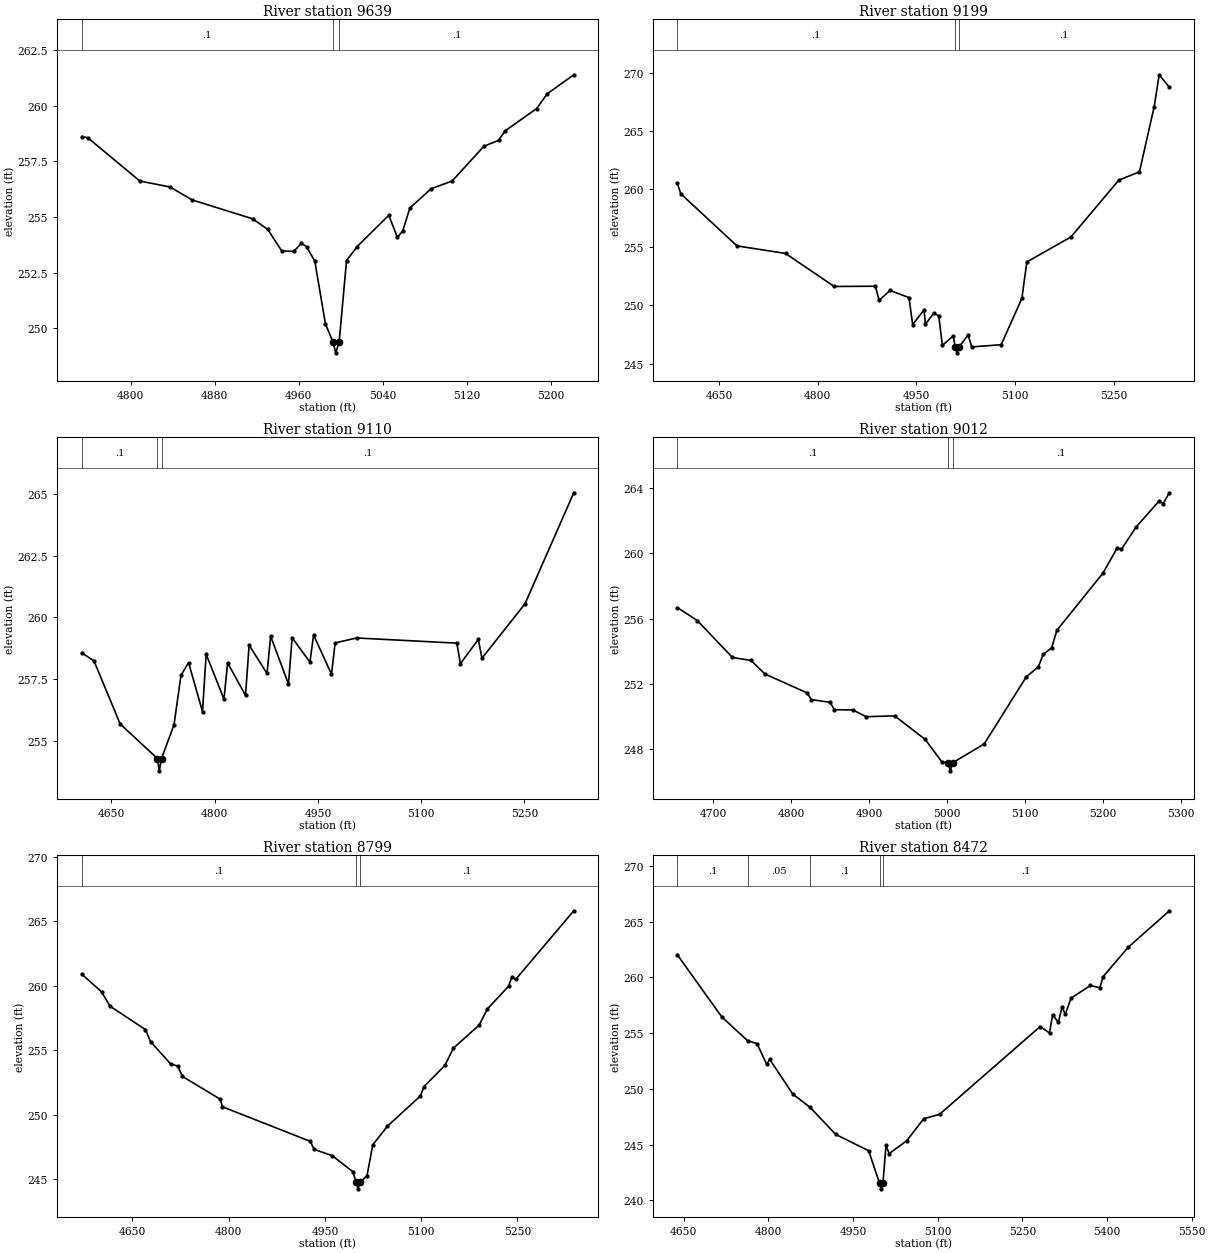
Type RM Length L Ch R = 1 ,9639    ,440,440,440
BEGIN DESCRIPTION:
UNT 026 IN RACR 21.0
END DESCRIPTION:
XS GIS Cut Line= 3
      2254827.65       13242665.      2254673.11     13242543.46
      2254402.52     13242513.97
#Sta/Elev= 30
  4753.3  258.62    4759  258.57  4808.7  256.62  4837.6  256.35  4858.4  255.77
  4916.2  254.92  4930.6  254.44  4943.8  253.48  4955.3  253.45  4962.5  253.82
  4967.6  253.66  4975.4  253.01  4985.5  250.19  4992.6  249.39  4995.3  248.89
  4998.6  249.39  5005.6  253.04  5015.7  253.67  5045.9  255.08    5054  254.09
    5059  254.36    5066  255.41  5086.1  256.27  5106.2  256.62  5136.4  258.18
  5150.4  258.45  5156.5  258.87  5186.7  259.88  5196.7  260.54  5222.1   261.4
#Mann= 3 ,-1 , 0
  4753.3      .1       0  4992.6     .07       0  4998.6      .1       0
Bank Sta=4992.6,4998.6
XS Rating Curve= 0 ,0
Exp/Cntr=0.3,0.1

Type RM Length L Ch R = 1 ,9199    ,89,89,89
BEGIN DESCRIPTION:
Mapping XS 2e99b944
END DESCRIPTION:
XS GIS Cut Line= 3
      2254943.42     13242499.54      2254782.52     13242157.84
      2254616.64     13241826.08
#Sta/Elev= 30
  4586.4  260.51  4591.5  259.61  4677.1  255.12    4751  254.47  4824.9  251.63
  4887.7  251.65  4893.3  250.43  4909.9  251.29  4938.8  250.67  4944.4  248.35
  4961.6  249.61  4963.9  248.38  4976.4  249.33    4984   249.1  4989.6  246.56
  5006.3  247.38  5008.9  246.42  5011.7  245.92  5014.9  246.42  5028.7  247.46
  5034.3  246.43    5079  246.62  5110.5   250.6  5118.1  253.74  5185.2  255.89
  5257.9  260.77  5289.4  261.49  5311.8   267.1  5319.4  269.84    5335  268.76
#Mann= 3 ,-1 , 0
  4586.4      .1       0  5008.9     .07       0  5014.9      .1       0
Bank Sta=5008.9,5014.9
XS Rating Curve= 0 ,0
Exp/Cntr=0.3,0.1

Type RM Length L Ch R = 1 ,9110    ,98,98,98
BEGIN DESCRIPTION:
Mapping XS ccf6ee5e
END DESCRIPTION:
XS GIS Cut Line= 2
      2254971.25     13242453.68      2254738.61     13241777.69
#Sta/Elev= 30
  4606.8  258.56  4624.6  258.23  4662.7  255.67  4716.8  254.27  4719.5  253.77
  4722.8  254.27  4740.9  255.64  4751.1  257.65  4762.1  258.16  4782.3  256.17
  4787.6   258.5  4813.5  256.68  4818.8  258.15  4844.8  256.83    4850  258.87
    4876  257.72  4881.3  259.23  4907.2  257.29  4912.5  259.17  4938.4  258.18
  4943.7  259.28  4969.7  257.69    4975  258.96  5006.2  259.16  5151.8  258.95
    5157  258.12    5183   259.1  5188.3  258.34  5250.7  260.54  5321.7  265.05
#Mann= 3 ,-1 , 0
  4606.8      .1       0  4716.8     .07       0  4722.8      .1       0
Bank Sta=4716.8,4722.8
XS Rating Curve= 0 ,0
Exp/Cntr=0.3,0.1

Type RM Length L Ch R = 1 ,9012    ,213,213,213
BEGIN DESCRIPTION:
Mapping XS b1c3215f
END DESCRIPTION:
XS GIS Cut Line= 2
      2255058.07     13242350.65      2254818.46     13241767.24
#Sta/Elev= 30
  4654.3  256.67    4680  255.87  4724.9  253.61  4748.8  253.43  4766.5   252.6
  4820.6  251.44  4826.1  251.03  4850.1  250.86  4855.5  250.41  4879.5  250.39
  4896.2  249.98  4932.8  250.03  4971.9  248.59  4993.5   247.2  5001.3  247.16
  5004.1  246.66  5007.3  247.16  5047.6  248.31  5101.6  252.43  5116.9  253.03
  5123.3   253.8  5134.1  254.21  5140.8  255.28  5199.6  258.77  5218.1  260.33
  5223.5  260.24  5242.1   261.6  5271.5  263.19  5276.9  263.05    5285  263.71
#Mann= 3 ,-1 , 0
  4654.3      .1       0  5001.3     .07       0  5007.3      .1       0
Bank Sta=5001.3,5007.3
XS Rating Curve= 0 ,0
Exp/Cntr=0.3,0.1

Type RM Length L Ch R = 1 ,8799    ,327,327,327
BEGIN DESCRIPTION:
UNT 026 IN RACR 20.0
END DESCRIPTION:
XS GIS Cut Line= 3
      2255283.46     13242358.56      2255215.45     13242156.18
      2254982.14     13241654.81
#Sta/Elev= 30
  4571.2  260.91  4602.1  259.54  4615.2  258.43  4670.5  256.61  4678.5  255.67
  4710.1  253.93  4720.7  253.79  4728.2  252.98  4787.1  251.21  4790.3  250.63
  4927.3  247.95  4933.1  247.33  4961.5  246.84  4993.5   245.6  4998.8  244.77
  5001.5  244.27  5004.8  244.77  5015.6  245.28  5024.6  247.68  5047.5  249.13
  5098.8  251.47  5104.3  252.19  5136.9  253.83  5150.1  255.17  5190.3  256.96
  5203.1  258.21  5236.1  259.97  5241.6  260.72  5247.2   260.5  5337.7  265.82
#Mann= 3 ,-1 , 0
  4571.2      .1       0  4998.8     .07       0  5004.8      .1       0
Bank Sta=4998.8,5004.8
XS Rating Curve= 0 ,0
Exp/Cntr=0.3,0.1

Type RM Length L Ch R = 1 ,8472    ,472,472,472
BEGIN DESCRIPTION:
UNT 026 IN RACR 19.0
END DESCRIPTION:
XS GIS Cut Line= 3
      2255578.12     13242282.29      2255522.56     13242094.77
      2255217.33     13241491.25
#Sta/Elev= 30
  4638.7  262.02  4717.4  256.45    4763  254.32    4780  254.05  4797.1  252.19
  4802.3  252.65  4843.2  249.53  4874.1  248.33  4919.3  245.91  4977.6  244.45
    4997  241.53  4999.8  241.03    5003  241.53  5008.4  244.92    5014  244.19
  5044.9  245.33  5075.3  247.32  5103.2  247.71  5281.4  255.58  5298.1  255.02
  5303.7  256.65  5313.8  255.95  5320.4  257.38    5326  256.67  5336.2  258.13
  5370.6  259.27  5387.3  259.06  5392.9  260.05  5437.4  262.69  5510.6  265.97
#Mann= 5 ,-1 , 0
  4638.7      .1       0    4763     .05       0  4874.1      .1       0
    4997     .07       0    5003      .1       0
Bank Sta=4997,5003
XS Rating Curve= 0 ,0
Exp/Cntr=0.3,0.1

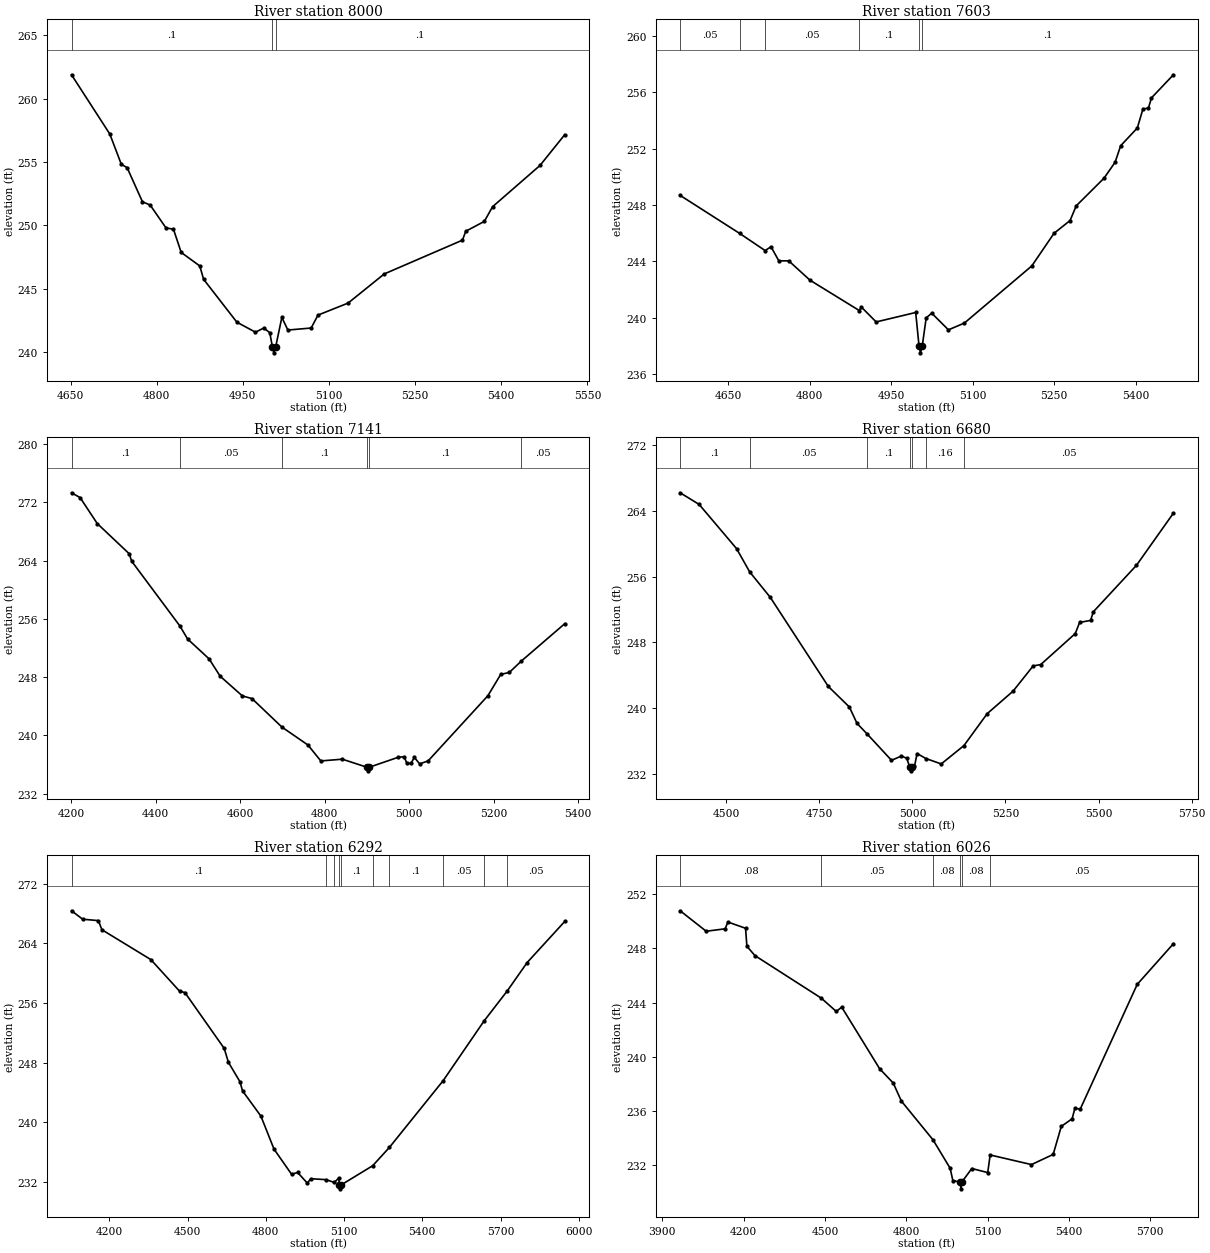
Type RM Length L Ch R = 1 ,8000    ,397,397,397
BEGIN DESCRIPTION:
UNT 026 IN RACR 18.0
END DESCRIPTION:
XS GIS Cut Line= 3
      2255953.11     13242143.34      2255939.22     13241976.72
       2255730.9     13241317.03
#Sta/Elev= 30
  4651.6  261.88  4718.3   257.2  4738.4   254.8  4748.4  254.55  4775.1  251.85
  4788.6  251.59  4816.2  249.78  4829.1  249.69  4842.6  247.85    4875  246.78
  4881.6  245.73  4939.6  242.34    4972  241.55  4986.4  241.88  4996.9  241.51
  5001.3  240.42  5004.1  239.92  5007.3  240.42  5017.9  242.72  5028.4  241.72
    5069  241.88  5080.8   242.9  5133.3  243.85  5196.2  246.15  5332.5  248.82
  5338.1  249.52  5370.5   250.3  5384.9  251.46  5467.5  254.72  5510.6  257.15
#Mann= 3 ,-1 , 0
  4651.6      .1       0  5001.3     .07       0  5007.3      .1       0
Bank Sta=5001.3,5007.3
XS Rating Curve= 0 ,0
Exp/Cntr=0.3,0.1

Type RM Length L Ch R = 1 ,7603    ,462,462,462
BEGIN DESCRIPTION:
UNT 026 IN RACR 17.0
END DESCRIPTION:
XS GIS Cut Line= 3
      2256175.35     13242039.21      2256300.34     13241886.44
       2256154.5     13241191.97
#Sta/Elev= 30
  4562.1  248.68  4671.7  245.98  4718.3  244.77  4729.2  245.04  4743.5  244.04
  4761.8  244.04  4800.8  242.67  4891.4  240.52  4895.4  240.76  4922.5  239.71
  4995.2  240.38  5001.3  238.02    5004  237.52  5007.3  238.02  5014.5     240
  5024.7  240.33  5055.4  239.15  5084.7  239.63  5208.7  243.68  5249.5  245.99
  5279.1   246.9  5290.4  247.94  5341.5   249.9  5361.9  251.03  5372.1   252.2
  5402.8  253.46    5413   254.8  5423.2  254.87  5428.7  255.59  5469.1  257.23
#Mann= 6 ,-1 , 0
  4562.1     .05       0  4671.7      .1       0  4718.3     .05       0
  4891.4      .1       0  5001.3     .07       0  5007.3      .1       0
Bank Sta=5001.3,5007.3
XS Rating Curve= 0 ,0
Exp/Cntr=0.3,0.1

Type RM Length L Ch R = 1 ,7141    ,461,461,461
BEGIN DESCRIPTION:
UNT 026 IN RACR 16.0
END DESCRIPTION:
XS GIS Cut Line= 3
      2256837.72     13242346.84      2256687.72     13241546.85
      2256637.72     13241196.83
#Sta/Elev= 30
  4200.5  273.32  4220.8  272.66  4261.5  269.09    4337  264.95  4342.9  263.92
  4457.1  255.02  4475.2  253.24  4526.1  250.51  4552.3  248.13  4604.9  245.42
  4627.8  245.05  4698.5  241.14  4760.1  238.68  4790.6  236.49  4841.5  236.73
  4899.5  235.63  4902.3  235.13  4905.5  235.63  4973.7  236.99  4988.1  237.07
  4994.1  236.17  5004.2  236.15  5011.9  236.99  5024.5  236.08  5044.7   236.5
  5186.1  245.45  5216.5  248.38  5236.7  248.64  5265.3  250.21    5368  255.34
#Mann= 6 ,-1 , 0
  4200.5      .1       0  4457.1     .05       0  4698.5      .1       0
  4899.5     .07       0  4905.5      .1       0  5265.3     .05       0
Bank Sta=4899.5,4905.5
XS Rating Curve= 0 ,0
Exp/Cntr=0.3,0.1

Type RM Length L Ch R = 1 ,6680    ,388,388,388
BEGIN DESCRIPTION:
UNT 026 IN RACR 15.0
END DESCRIPTION:
XS GIS Cut Line= 3
      2257210.06     13242247.54      2257168.39     13241851.72
      2256953.46      13240950.4
#Sta/Elev= 30
  4376.4   266.2  4427.4  264.78  4527.9   259.4  4563.2  256.56  4618.4  253.47
  4774.3  242.62  4830.8  240.12  4851.4  238.12  4879.3   236.8  4943.9  233.63
  4970.5  234.15    4985  233.88  4992.3  232.85  4995.1  232.35  4998.3  232.85
  5005.6  232.88  5012.6  234.46  5036.3  233.85  5077.5  233.19  5138.6  235.43
  5200.9  239.31  5270.4  242.05  5324.3  245.12  5344.8  245.29  5437.4  249.06
  5449.2  250.42  5478.5  250.66  5486.1  251.72  5601.8  257.37    5701  263.72
#Mann= 7 ,-1 , 0
  4376.4      .1       0  4563.2     .05       0  4879.3      .1       0
  4992.3     .07       0  4998.3      .1       0  5036.3     .16       0
  5138.6     .05       0
Bank Sta=4992.3,4998.3
XS Rating Curve= 0 ,0
Exp/Cntr=0.3,0.1

Type RM Length L Ch R = 1 ,6292    ,266,266,266
BEGIN DESCRIPTION:
UNT 026 IN RACR 14.0
END DESCRIPTION:
XS GIS Cut Line= 3
      2257400.94     13242439.44      2257487.75     13241597.43
      2257400.94     13240555.71
#Sta/Elev= 30
  4054.6  268.36  4097.4  267.23  4157.7  267.04  4171.1  265.82  4358.8  261.82
  4469.4  257.57  4489.5   257.4  4640.3  249.91  4656.2  248.06  4700.6  245.45
  4710.6  244.22    4781  240.84  4831.3  236.41  4898.9  233.03  4921.7  233.29
  4959.2  231.85  4971.9  232.45  5030.8  232.32  5062.6  231.95  5079.6  232.54
  5081.6  231.59  5084.4  231.09  5087.6  231.59  5209.8  234.19    5274  236.65
    5480  245.59  5636.9  253.59  5726.1  257.63  5802.1  261.42  5946.4  266.93
#Mann= 10 ,-1 , 0
  4054.6      .1       0  5030.8     .16       0  5062.6      .1       0
  5081.6     .07       0  5087.6      .1       0  5209.8     .16       0
    5274      .1       0    5480     .05       0  5636.9      .1       0
  5726.1     .05       0
Bank Sta=5081.6,5087.6
XS Rating Curve= 0 ,0
Exp/Cntr=0.3,0.1

Type RM Length L Ch R = 1 ,6026    ,674,674,674
BEGIN DESCRIPTION:
UNT 026 IN RACR 13.0
END DESCRIPTION:
XS GIS Cut Line= 3
      2257730.89     13242462.83      2257737.84     13241546.16
        2257717.      13240643.4
#Sta/Elev= 30
  3965.9  250.78  4061.9  249.27  4131.9  249.45  4141.9  249.95  4207.1  249.49
  4212.1  248.16  4241.9  247.47  4486.7  244.33  4541.9  243.35  4561.9  243.67
  4701.9  239.12  4751.9  238.07  4781.9  236.74  4898.6  233.88  4961.9  231.78
  4971.9  230.87  4998.9  230.76  5001.7  230.26  5004.9  230.76  5041.9  231.76
  5100.6  231.46  5109.5  232.76    5262  232.05    5342   232.8    5372  234.87
    5412  235.43    5422   236.2    5442  236.15  5652.1  245.35  5785.6  248.35
#Mann= 6 ,-1 , 0
  3965.9     .08       0  4486.7     .05       0  4898.6     .08       0
  4998.9     .07       0  5004.9     .08       0  5109.5     .05       0
Bank Sta=4998.9,5004.9
XS Rating Curve= 0 ,0
Exp/Cntr=0.3,0.1

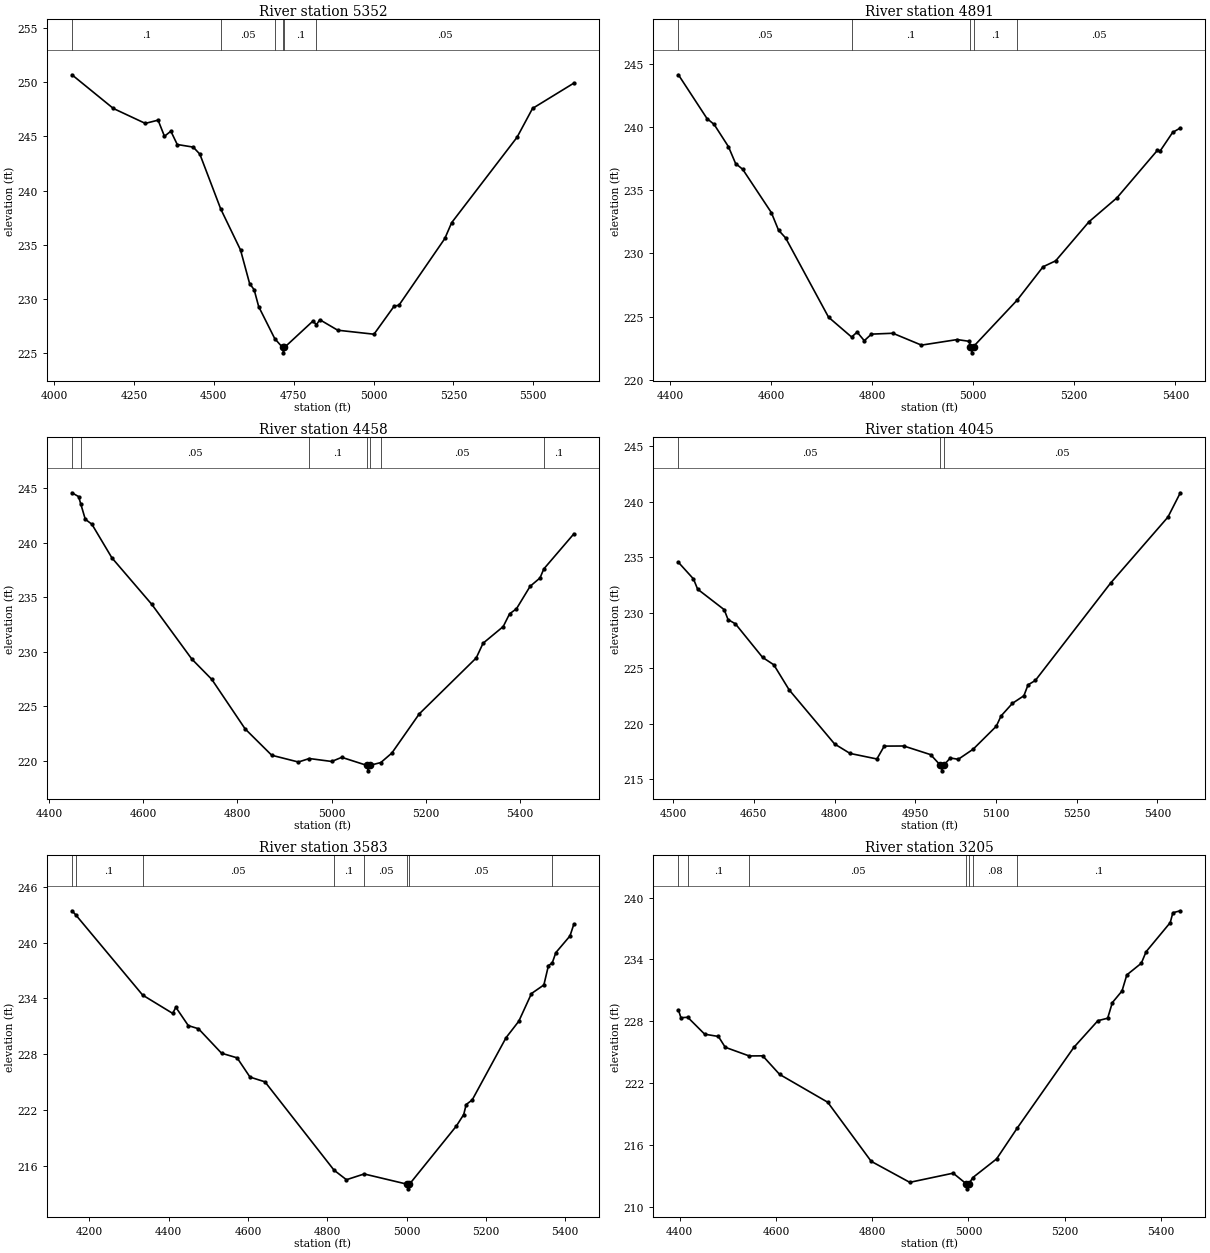
Type RM Length L Ch R = 1 ,5352    ,461,461,461
BEGIN DESCRIPTION:
UNT 026 IN RACR 12.0
END DESCRIPTION:
XS GIS Cut Line= 5
      2258490.35     13241736.36      2258490.35     13241341.35
      2257969.52     13240868.26       2257774.2     13240551.42
       2257774.2     13240451.75
#Sta/Elev= 30
  4056.3   250.7  4185.8  247.59  4285.8  246.21  4325.8  246.51  4345.8  245.02
  4365.8  245.49  4385.8  244.26  4435.8  244.02  4456.5  243.37  4521.8  238.31
  4583.8  234.52  4612.2  231.42  4626.4  230.85  4640.6  229.29  4690.9  226.33
  4715.3  225.52    4718  225.02  4721.3  225.52  4810.2  227.95  4821.5  227.62
  4831.8  228.08  4887.9  227.11  5001.4  226.74  5064.9  229.35  5079.1   229.4
  5223.1  235.58  5244.4  237.04  5449.1  244.93  5497.5  247.59  5626.8  249.93
#Mann= 6 ,-1 , 0
  4056.3      .1       0  4521.8     .05       0  4690.9      .1       0
  4715.3     .03       0  4721.3      .1       0  4821.5     .05       0
Bank Sta=4715.3,4721.3
XS Rating Curve= 0 ,0
Exp/Cntr=0.3,0.1

Type RM Length L Ch R = 1 ,4891    ,433,433,433
BEGIN DESCRIPTION:
UNT 026 IN RACR 11.0
END DESCRIPTION:
XS GIS Cut Line= 3
       2258787.7     13241046.83      2258387.72     13240646.85
      2257987.68     13240496.84
#Sta/Elev= 30
  4416.9  244.13  4473.4  240.67  4487.6   240.2  4515.9  238.44    4530  237.11
  4544.1  236.65  4600.7  233.23  4614.9  231.84    4629  231.22  4713.9  224.95
  4759.5  223.38  4770.4  223.77  4784.6  223.09  4798.7  223.61  4841.1  223.68
  4897.7  222.74  4968.4  223.18  4992.3  223.04  4994.7  222.63  4997.4  222.13
  5000.7  222.63    5087   226.3  5138.3  228.94  5163.2  229.41  5229.1   232.5
  5284.3  234.39  5364.4  238.15  5369.7  238.09  5394.6  239.57  5409.8  239.92
#Mann= 5 ,-1 , 0
  4416.9     .05       0  4759.5      .1       0  4994.7     .07       0
  5000.7      .1       0    5087     .05       0
Bank Sta=4994.7,5000.7
XS Rating Curve= 0 ,0
Exp/Cntr=0.3,0.1

Type RM Length L Ch R = 1 ,4458    ,413,413,413
BEGIN DESCRIPTION:
UNT 026 IN RACR 10.0
END DESCRIPTION:
XS GIS Cut Line= 3
       2259037.7     13240746.83      2258637.72     13240346.85
      2258237.68     13240046.83
#Sta/Elev= 30
  4448.6   244.6  4462.7  244.25  4467.3  243.58  4476.9  242.17    4491  241.71
  4533.4  238.63  4618.3  234.35  4703.1  229.34  4745.6  227.47  4816.3  222.93
  4872.8  220.51  4929.4  219.89  4952.6  220.21  5000.1  219.94  5021.5  220.32
  5074.8  219.58  5077.5  219.08  5080.8  219.58  5104.4  219.84  5127.8  220.71
  5186.1  224.31    5307  229.44  5321.5  230.79  5364.3  232.32  5377.8  233.49
  5392.4  233.95  5421.5  236.02  5442.4  236.78  5450.5  237.61  5514.3  240.83
#Mann= 7 ,-1 , 0
  4448.6      .1       0  4467.3     .05       0  4952.6      .1       0
  5074.8     .07       0  5080.8      .1       0  5104.4     .05       0
  5450.5      .1       0
Bank Sta=5074.8,5080.8
XS Rating Curve= 0 ,0
Exp/Cntr=0.3,0.1

Type RM Length L Ch R = 1 ,4045    ,462,462,462
BEGIN DESCRIPTION:
UNT 026 IN RACR 9.0
END DESCRIPTION:
XS GIS Cut Line= 3
      2259137.75     13240296.88      2258787.72     13239996.85
      2258387.73     13239746.86
#Sta/Elev= 30
  4509.9  234.54  4537.9  233.04  4545.6  232.12    4595  230.27  4602.1  229.38
  4615.9  228.99  4666.3  225.97  4687.2   225.3  4715.7  223.04  4800.2  218.16
  4828.8  217.31  4878.7  216.81  4892.4  217.97  4928.7  217.98  4978.6   217.2
  4996.8  216.24  4999.6  215.74  5002.8  216.24  5015.1   216.9  5029.9  216.78
  5057.6  217.69  5100.6  219.76  5109.5  220.69  5130.7  221.83  5151.9  222.51
  5159.6  223.49  5173.2  223.89  5312.9  232.66  5419.6  238.62  5442.6  240.81
#Mann= 3 ,-1 , 0
  4509.9     .05       0  4996.8     .03       0  5002.8     .05       0
Bank Sta=4996.8,5002.8
XS Rating Curve= 0 ,0
Exp/Cntr=0.3,0.1

Type RM Length L Ch R = 1 ,3583    ,378,378,378
BEGIN DESCRIPTION:
UNT 026 IN RACR 8.0
END DESCRIPTION:
XS GIS Cut Line= 3
       2259637.7     13239796.85      2258837.72     13239546.85
      2258437.75     13239396.86
#Sta/Elev= 30
  4156.3  243.42  4165.3  243.01  4334.6  234.35  4410.3  232.38  4418.2  233.04
  4449.6  231.07  4475.3  230.73  4533.4   228.1  4572.7   227.6  4605.2  225.53
  4642.9  225.02    4817  215.52  4848.3  214.49    4893  215.11  5001.2  214.01
    5004  213.51  5007.2  214.01  5125.3  220.26  5143.9   221.5  5150.2  222.58
  5165.3  223.07  5250.7  229.77  5282.8  231.54  5314.8  234.52    5346  235.44
  5357.5  237.52  5367.1  237.81  5376.2  238.92  5411.8  240.71  5421.6  241.98
#Mann= 8 ,-1 , 0
  4156.3     .05       0  4165.3      .1       0  4334.6     .05       0
    4817      .1       0    4893     .05       0  5001.2    .035       0
  5007.2     .05       0  5367.1      .1       0
Bank Sta=5001.2,5007.2
XS Rating Curve= 0 ,0
Exp/Cntr=0.3,0.1

Type RM Length L Ch R = 1 ,3205    ,220,220,220
BEGIN DESCRIPTION:
UNT 026 IN RACR 7.0
END DESCRIPTION:
XS GIS Cut Line= 3
      2259437.55     13239404.14      2259266.25     13239206.29
      2258486.82     13239150.79
#Sta/Elev= 30
  4397.2  229.11  4402.4  228.35  4416.6  228.39  4451.8  226.75  4480.3  226.53
  4494.5  225.48  4544.3  224.64  4572.4  224.65  4607.5  222.85  4707.5  220.15
  4797.8  214.42    4878  212.38  4968.2  213.27  4995.1  212.25  4997.9  211.75
  5001.1  212.25    5009  212.84  5058.4  214.65    5101  217.62  5218.8  225.46
    5269  228.06  5289.3   228.3    5299  229.81  5319.1  230.94  5329.1   232.5
  5359.2  233.63  5369.2  234.75  5419.3  237.57  5424.8  238.53  5440.3  238.72
#Mann= 7 ,-1 , 0
  4397.2     .05       0  4416.6      .1       0  4544.3     .05       0
  4995.1     .03       0  5001.1     .05       0    5009     .08       0
    5101      .1       0
Bank Sta=4995.1,5001.1
XS Rating Curve= 0 ,0
Exp/Cntr=0.3,0.1

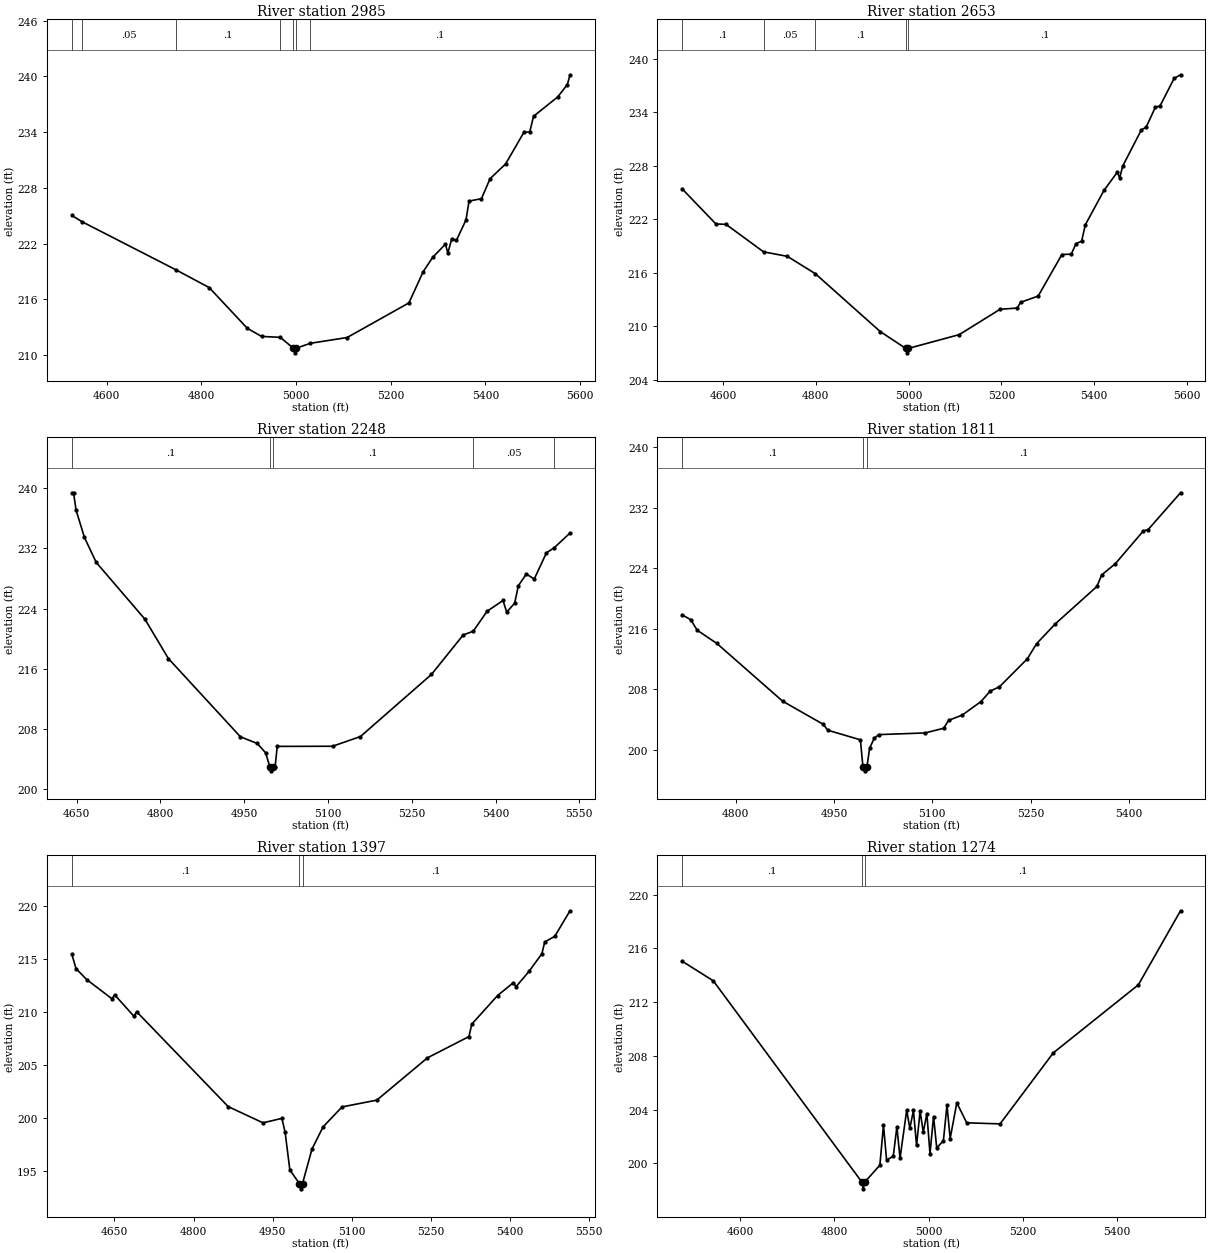
Type RM Length L Ch R = 1 ,2985    ,332,332,332
BEGIN DESCRIPTION:
Mapping XS a5da237a
END DESCRIPTION:
XS GIS Cut Line= 4
      2259487.84     13239219.78      2259265.61     13239046.16
      2258710.06     13238997.55      2258502.26     13239039.11
#Sta/Elev= 30
  4526.9  225.02    4549  224.33  4747.1  219.15  4816.8  217.25  4897.1  212.87
  4927.3  211.99  4966.7  211.89  4994.5  210.72  4997.3  210.22  5000.5  210.72
  5030.5  211.25  5107.9  211.87  5238.4   215.6  5268.6  218.97  5288.6  220.51
  5315.5  221.93  5320.5  220.98  5328.8  222.49  5338.8  222.36  5358.9  224.54
  5365.3  226.57  5391.5  226.83  5409.8  228.99  5442.5  230.57  5481.1  233.98
  5493.5  234.02  5501.5  235.71  5552.5  237.79  5572.9  239.13  5578.5  240.18
#Mann= 7 ,-1 , 0
  4526.9      .1       0    4549     .05       0  4747.1      .1       0
  4966.7     .08       0  4994.5     .07       0  5000.5     .08       0
  5030.5      .1       0
Bank Sta=4994.5,5000.5
XS Rating Curve= 0 ,0
Exp/Cntr=0.3,0.1

Type RM Length L Ch R = 1 ,2653    ,405,405,405
BEGIN DESCRIPTION:
UNT 026 IN RACR 6.0
END DESCRIPTION:
XS GIS Cut Line= 4
      2259408.64     13238349.64      2259237.29     13238653.71
      2258863.27     13238851.58      2258564.02     13238887.78
#Sta/Elev= 30
  4512.6  225.37  4584.9  221.46  4606.6  221.42  4687.5  218.34    4739  217.83
  4799.1  215.89  4938.9  209.41  4993.9  207.52  4996.7  207.02  4999.9  207.52
  5109.3  209.06  5197.3   211.9  5234.5  212.04  5241.4  212.68  5279.4  213.38
  5330.6  218.04  5350.8  218.08  5360.9  219.25  5373.1  219.53    5381  221.36
  5421.3  225.23    5450  227.26  5455.1  226.62  5461.6  227.95  5501.9  232.01
    5512   232.3    5532  234.54  5542.2   234.7  5572.4  237.77  5586.2  238.18
#Mann= 5 ,-1 , 0
  4512.6      .1       0  4687.5     .05       0  4799.1      .1       0
  4993.9     .07       0  4999.9      .1       0
Bank Sta=4993.9,4999.9
XS Rating Curve= 0 ,0
Exp/Cntr=0.3,0.1

Type RM Length L Ch R = 1 ,2248    ,437,437,437
BEGIN DESCRIPTION:
UNT 026 IN RACR 5.0
END DESCRIPTION:
XS GIS Cut Line= 3
      2259187.71     13238046.87      2258987.72     13238346.85
      2258587.76     13238696.82
#Sta/Elev= 30
  4641.4  239.39  4644.4  239.39  4648.9  237.08  4663.9  233.45    4685  230.13
  4772.1  222.59  4814.2  217.35  4943.3  206.94  4973.4  206.06  4988.4  204.81
  4995.9  202.92  4998.7  202.42  5001.9  202.92  5005.3  202.92  5009.1  205.67
  5108.2  205.69  5158.1  206.98  5285.3  215.24  5342.2  220.49  5360.1  220.98
  5384.9  223.64  5413.4  225.07    5420  223.52  5434.3  224.72  5440.9  227.03
  5455.1  228.58  5469.4  227.93  5491.2  231.41  5505.2  232.09  5533.4  234.04
#Mann= 5 ,-1 , 0
  4641.4      .1       0  4995.9     .07       0  5001.9      .1       0
  5360.1     .05       0  5505.2      .1       0
Bank Sta=4995.9,5001.9
XS Rating Curve= 0 ,0
Exp/Cntr=0.3,0.1

Type RM Length L Ch R = 1 ,1811    ,414,414,414
BEGIN DESCRIPTION:
UNT 026 IN RACR 4.0
END DESCRIPTION:
XS GIS Cut Line= 3
      2258960.24     13237931.41      2258777.92     13237941.83
      2258383.27     13238362.45
#Sta/Elev= 30
    4719   217.8  4731.7  217.19  4741.6  215.79  4771.6  214.04  4871.8  206.41
  4933.8  203.35  4940.6  202.57  4990.4   201.3  4994.3   197.7    4997   197.2
  5000.3   197.7  5004.5   200.2  5011.4  201.49  5018.3  201.99  5089.1  202.21
  5117.4  202.83  5124.8  203.87  5145.8  204.58  5174.1  206.35  5188.3  207.74
  5202.4  208.31  5244.9  212.01  5259.1  214.02  5287.4  216.62  5350.9  221.57
  5358.2  223.09  5379.2   224.6  5421.7  228.91    5429  229.09  5478.4  233.96
#Mann= 3 ,-1 , 0
    4719      .1       0  4994.3     .07       0  5000.3      .1       0
Bank Sta=4994.3,5000.3
XS Rating Curve= 0 ,0
Exp/Cntr=0.3,0.1

Type RM Length L Ch R = 1 ,1397    ,123,123,123
BEGIN DESCRIPTION:
UNT 026 IN RACR 3.0
END DESCRIPTION:
XS GIS Cut Line= 4
      2258835.25     13237650.17      2258600.84     13237592.87
      2258277.92     13237811.62      2258163.64     13238102.53
#Sta/Elev= 30
  4569.5  215.45  4577.3   214.1  4597.8  213.06  4645.4  211.26  4650.5  211.63
    4687  209.61  4692.2  210.04  4865.7  201.08  4931.6  199.55  4967.5  199.97
  4973.6  198.64  4982.5  195.11  5000.5  193.82  5003.2  193.32  5006.5  193.82
  5024.5  197.08  5045.5  199.17  5081.4  201.05  5147.3  201.69  5243.2  205.68
  5321.9  207.69  5327.2  208.86  5376.1  211.56  5405.9  212.77  5411.2   212.4
  5435.7  213.84  5460.1  215.51  5465.5  216.62  5484.5  217.15  5513.4  219.56
#Mann= 3 ,-1 , 0
  4569.5      .1       0  5000.5     .07       0  5006.5      .1       0
Bank Sta=5000.5,5006.5
XS Rating Curve= 0 ,0
Exp/Cntr=0.3,0.1

Type RM Length L Ch R = 1 ,1274    ,39,39,39
BEGIN DESCRIPTION:
Mapping XS 22d8ec30
END DESCRIPTION:
XS GIS Cut Line= 5
      2258831.48     13237599.16      2258474.72     13237510.62
      2258261.18     13237695.52      2258099.72     13238028.85
      2258076.31     13238057.47
#Sta/Elev= 30
  4477.5  215.04  4543.2  213.59  4858.6  198.59  4861.4  198.09  4864.6  198.59
  4896.7  199.85  4904.4  202.83    4911  200.23  4925.2  200.53  4932.9  202.72
  4939.5  200.37  4953.7  203.95  4960.3   202.6    4968  203.93  4974.6  201.33
  4982.2   203.9  4988.8   202.3  4996.5   203.7  5003.1  200.71  5010.7  203.48
  5017.4  201.14  5031.6  201.68  5039.2  204.34  5045.9  201.84  5060.1   204.5
    5081  203.01  5151.9  202.93  5264.8  208.22  5445.4  213.29  5534.9  218.81
#Mann= 3 ,-1 , 0
  4477.5      .1       0  4858.6     .07       0  4864.6      .1       0
Bank Sta=4858.6,4864.6
XS Rating Curve= 0 ,0
Exp/Cntr=0.3,0.1

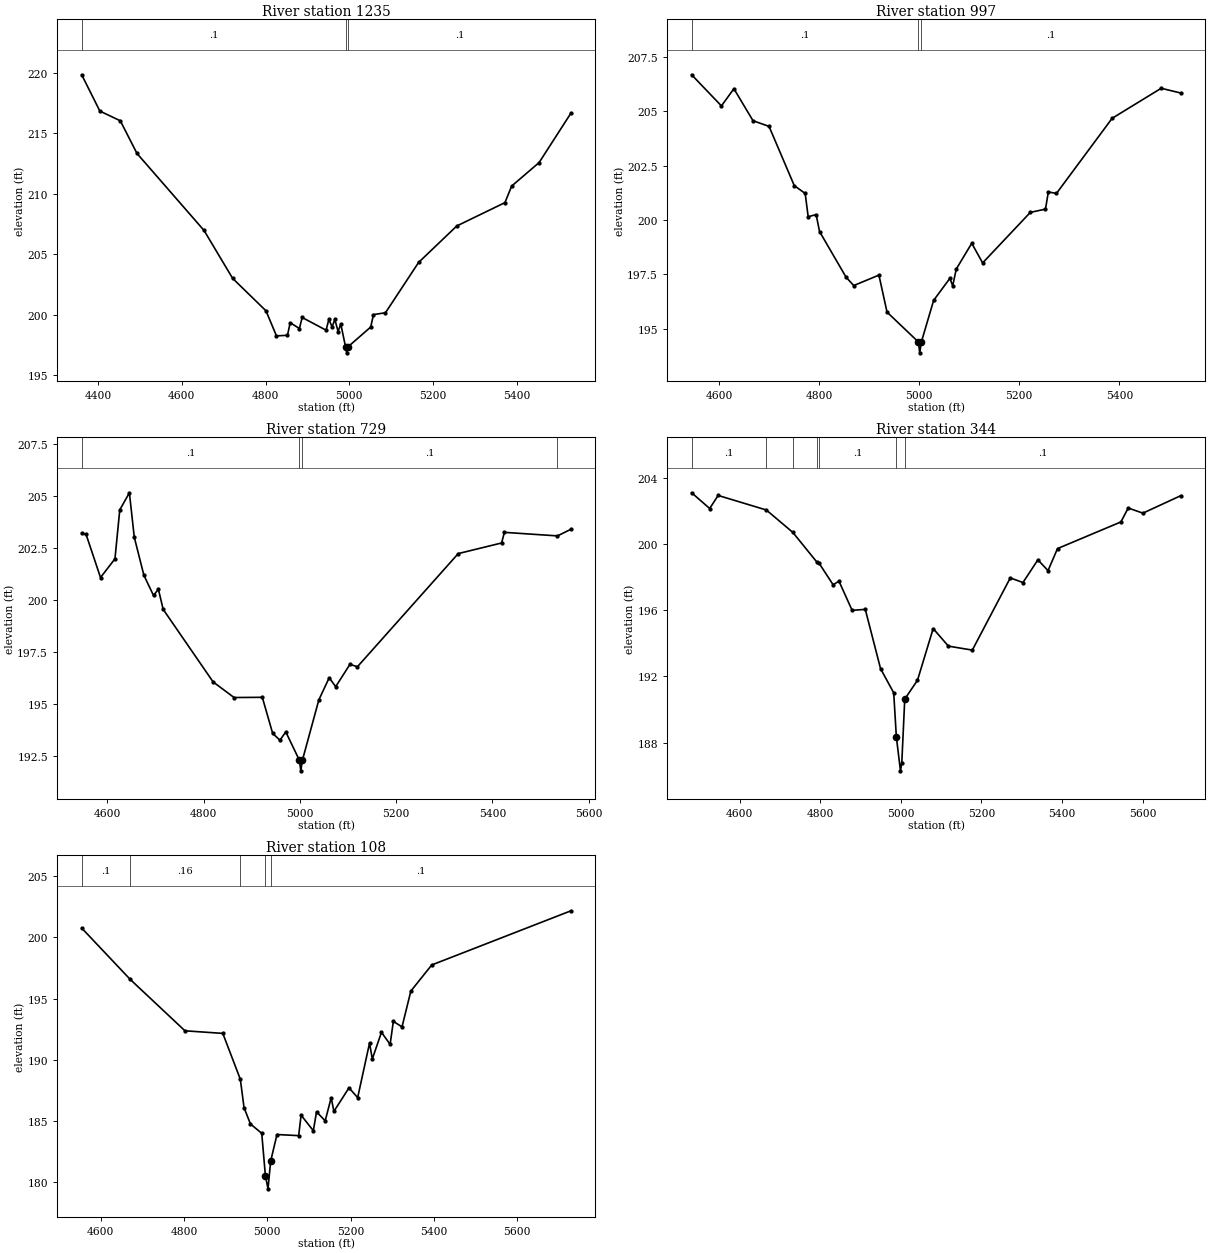
Type RM Length L Ch R = 1 ,1235    ,238,238,238
BEGIN DESCRIPTION:
Mapping XS f9733e44
END DESCRIPTION:
XS GIS Cut Line= 4
      2258909.65     13237596.57       2258459.1     13237474.16
      2258248.16     13237653.85      2258045.02     13238026.27
#Sta/Elev= 30
    4361  219.82  4404.4  216.82  4453.2  216.02    4493  213.32  4653.1  206.96
  4721.4     203    4801  200.32    4826  198.25  4852.3   198.3  4858.8  199.34
  4880.8  198.86  4887.4  199.77  4944.5  198.72  4951.1  199.62  4958.8  198.99
  4965.4  199.61  4973.1  198.61  4979.6  199.23  4990.9  197.35  4993.7  196.85
  4996.9  197.35    5051  198.98  5057.6  200.01  5086.2  200.16  5165.4  204.32
  5256.5  207.33  5371.5  209.26  5387.6  210.63  5453.1  212.57  5529.2  216.66
#Mann= 3 ,-1 , 0
    4361      .1       0  4990.9     .07       0  4996.9      .1       0
Bank Sta=4990.9,4996.9
XS Rating Curve= 0 ,0
Exp/Cntr=0.3,0.1

Type RM Length L Ch R = 1 ,997     ,268,268,268
BEGIN DESCRIPTION:
UNT 026 IN RACR 2.0
END DESCRIPTION:
XS GIS Cut Line= 4
      2258642.52     13237301.21      2258475.84      13237238.7
      2257928.96     13237535.58      2257856.06       13237697.
#Sta/Elev= 30
  4545.6  206.67  4605.1  205.24    4630  206.03  4668.2  204.56  4700.2   204.3
  4750.6  201.58  4772.4  201.22  4778.4  200.15  4794.3  200.25  4801.1  199.47
  4854.2  197.37  4869.4  196.99  4919.7  197.47  4935.9  195.77  4998.5   194.4
  5001.2   193.9  5004.5   194.4    5029  196.31  5061.4  197.32  5067.1  196.98
  5074.2  197.75  5105.1  198.93  5126.9  198.03  5222.1  200.35  5252.4   200.5
  5258.1  201.29  5274.3  201.22  5385.5  204.67  5483.5  206.05    5523  205.83
#Mann= 3 ,-1 , 0
  4545.6      .1       0  4998.5     .07       0  5004.5      .1       0
Bank Sta=4998.5,5004.5
XS Rating Curve= 0 ,0
Exp/Cntr=0.3,0.1

Type RM Length L Ch R = 1 ,729     ,385,385,385
BEGIN DESCRIPTION:
Mapping XS daa609f6
END DESCRIPTION:
XS GIS Cut Line= 3
      2258556.67     13237009.68      2258310.03     13237025.43
      2257645.28     13237412.76
#Sta/Elev= 30
  4546.8  203.22  4555.8  203.17  4585.9  201.09  4615.9  201.99  4625.9  204.34
  4645.9  205.16    4656  203.03    4676   201.2    4696  200.23  4706.1  200.53
  4716.1  199.56  4819.8  196.08  4863.3  195.33    4922  195.34  4943.5  193.61
  4958.6  193.28  4970.8  193.68  4999.2  192.31    5002  191.81  5005.2  192.31
  5039.5  195.22    5061  196.28  5074.4  195.85    5104  196.92  5119.7  196.81
    5329  202.24  5419.1  202.75  5424.9  203.26  5535.2  203.09  5563.3  203.41
#Mann= 4 ,-1 , 0
  4546.8      .1       0  4999.2     .07       0  5005.2      .1       0
  5535.2     .08       0
Bank Sta=4999.2,5005.2
XS Rating Curve= 0 ,0
Exp/Cntr=0.3,0.1

Type RM Length L Ch R = 1 ,344     ,236,236,236
BEGIN DESCRIPTION:
Mapping XS 41105f3c
END DESCRIPTION:
XS GIS Cut Line= 4
      2258552.94     13236863.57      2258321.21      13236681.3
      2257782.15     13236847.97      2257641.51     13237173.53
#Sta/Elev= 30
  4481.1  203.08  4525.9  202.13  4546.8  202.92  4666.4  202.04    4732  200.69
  4791.6   198.9  4797.4  198.82  4831.9  197.53  4846.6  197.74  4879.2  195.98
  4911.8  196.04  4949.7  192.46  4982.3     191  4988.9  188.33  4999.1  186.29
  5002.4  186.79  5009.7  190.62  5041.3  191.76  5080.2  194.88    5118  193.82
  5177.3  193.58  5271.5  197.94  5302.9  197.66  5339.9  199.03  5365.1  198.38
  5388.6  199.71  5545.9  201.32    5564  202.16  5600.4  201.85  5694.8  202.91
#Mann= 7 ,-1 , 0
  4481.1      .1       0  4666.4     .16       0    4732      .1       0
  4791.6     .16       0  4797.4      .1       0  4988.9     .05       0
  5009.7      .1       0
Bank Sta=4988.9,5009.7
XS Rating Curve= 0 ,0
Exp/Cntr=0.3,0.1

Type RM Length L Ch R = 1 ,108     ,0,0,0
BEGIN DESCRIPTION:
UNT 026 IN RACR 1.0
END DESCRIPTION:
XS GIS Cut Line= 5
      2258377.11     13236697.38      2258126.24     13236472.99
      2257943.95     13236586.27      2257738.22     13236824.55
      2257627.62     13237112.11
#Sta/Elev= 30
  4554.7  200.75  4670.9  196.57  4802.5  192.37  4893.3  192.16  4935.4  188.41
  4944.2  186.11  4959.6  184.77  4986.7  184.01  4995.5  180.55  5001.8  179.48
    5008  181.72  5023.3  183.91  5075.3  183.82  5081.2  185.49  5110.5  184.22
  5118.2  185.76    5139  185.03  5153.3  186.91  5159.9   185.8  5196.1  187.72
  5216.9  186.92  5245.4  191.37    5252  190.07    5274  192.25  5294.8  191.26
  5302.5  193.14  5323.3  192.69  5344.5  195.61  5394.6  197.74  5728.8  202.16
#Mann= 5 ,-1 , 0
  4554.7      .1       0  4670.9     .16       0  4935.4      .1       0
  4995.5     .07       0    5008      .1       0
Bank Sta=4995.5,5008
XS Rating Curve= 0 ,0
Exp/Cntr=0.3,0.1

Chan Stop Cuts=-1
Use User Specified Reach Order=0
Composite Channel Slope=5