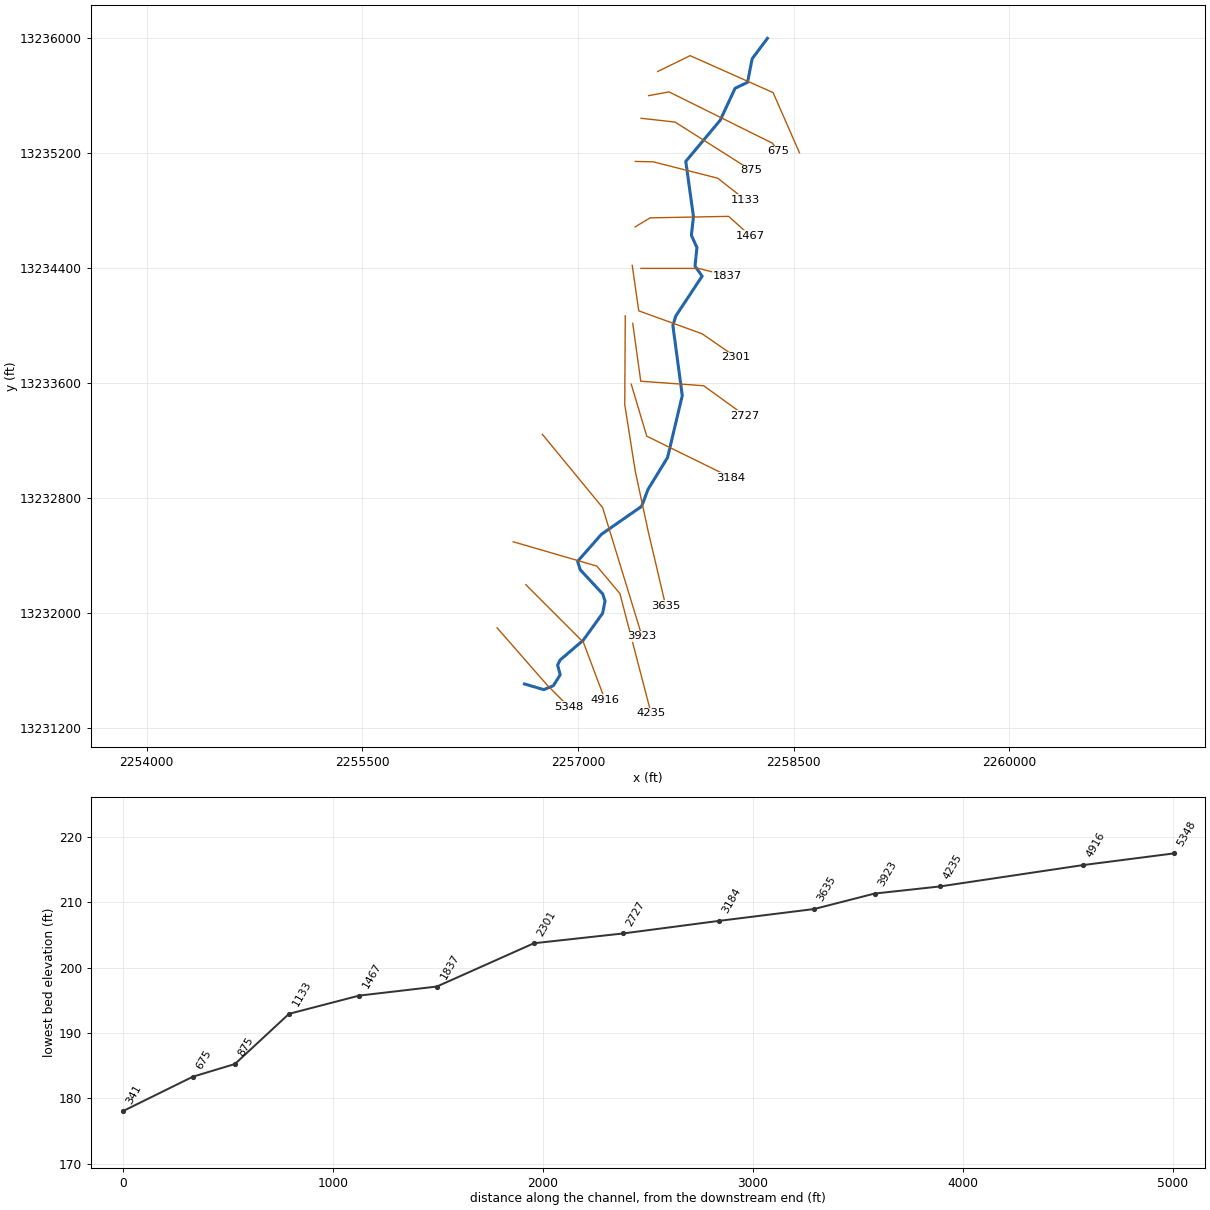
--- UNT 027 IN RACR.prj (project) ---

Proj Title=UNT 027 IN RACR Base Level Engineering
Current Plan=p01
Default Exp/Contr=0.3,0.1
English Units
Geom File=g01
Flow File=f01
Plan File=p01
Y Axis Title=Elevation
X Axis Title(PF)=Main Channel Distance
X Axis Title(XS)=Station
BEGIN DESCRIPTION:
UNT 027 IN RACR
END DESCRIPTION:
DSS Export Rating Curves= 0
DSS Export Rating Curve Sorted= 0
DSS Export Volume Flow Curves= 0
DXF OffsetX= 0
DXF OffsetY= 0
DXF ScaleX= 1
DXF ScaleY= 10

--- UNT 027 IN RACR.p01 (plan) ---

Plan Title=Multiple Run
Short Identifier=Multiple
Geom File=g01
Flow File=f01
Subcritical Flow
K Sum by GR= 0
Std Step Tol= 0.01
Critical Tol= 0.01
Num of Std Step Trials= 20
Max Error Tol= 0.3
Flow Tol Ratio= 0.001
Split Flow NTrial= 30
Split Flow Tol= 0.02
Split Flow Ratio= 0.02
Log Output Level= 0
Friction Slope Method= 1
Unsteady Friction Slope Method= 2
Unsteady Bridges Friction Slope Method= 1
Parabolic Critical Depth
Global Vel Dist=  1 , 1 , 1
Global Log Level= 0
CheckData=True
Encroach Param= -1, 0, 0, 0
BEGIN DESCRIPTION:
Multiple Run
END DESCRIPTION:

--- UNT 027 IN RACR.f01 (steady flow) ---

Flow Title=Multiple
Program Version=4.10
Number of Profiles= 7
Profile Names=10-year,25-year,50-year,1pct_min,100-year,1pct_plu,500-year
River Rch & RM=UNT 027 IN RACR,Reach-1         ,5348
     225     311     383     348     470     636     718
River Rch & RM=UNT 027 IN RACR,Reach-1         ,3635
     289     407     506     463     626     847     974
Boundary for River Rch & Prof#=UNT 027 IN RACR,Reach-1         , 1
Up Type= 0
Dn Type= 3
Dn Slope=0.005
Boundary for River Rch & Prof#=UNT 027 IN RACR,Reach-1         , 2
Up Type= 0
Dn Type= 3
Dn Slope=0.005
Boundary for River Rch & Prof#=UNT 027 IN RACR,Reach-1         , 3
Up Type= 0
Dn Type= 3
Dn Slope=0.005
Boundary for River Rch & Prof#=UNT 027 IN RACR,Reach-1         , 4
Up Type= 0
Dn Type= 3
Dn Slope=0.005
Boundary for River Rch & Prof#=UNT 027 IN RACR,Reach-1         , 5
Up Type= 0
Dn Type= 3
Dn Slope=0.005
Boundary for River Rch & Prof#=UNT 027 IN RACR,Reach-1         , 6
Up Type= 0
Dn Type= 3
Dn Slope=0.005
Boundary for River Rch & Prof#=UNT 027 IN RACR,Reach-1         , 7
Up Type= 0
Dn Type= 3
Dn Slope=0.005
DSS Import GetInterval= 0
DSS Import GetPeak= 0
DSS Import FillOption= 0

--- UNT 027 IN RACR.g01 (geometry) ---

Geom Title=Existing Conditions
Program Version=4.10

River Reach=UNT 027 IN RACR ,Reach-1
Reach XY= 30
      2256627.72     13231506.86      2256763.15     13231467.18
      2256829.52     13231495.35      2256876.39     13231570.87
      2256858.16     13231638.58      2256875.83     13231673.43
      2257036.98     13231811.33      2257171.53     13231998.83
      2257188.02     13232083.03       2257172.4     13232132.51
      2257015.28     13232301.78       2256997.7     13232359.94
      2257162.85     13232547.44      2257442.36     13232741.88
       2257487.5     13232860.81      2257622.92     13233081.29
      2257725.35     13233512.72      2257659.93     13234000.68
       2257680.3     13234065.75      2257863.43     13234342.73
      2257813.82     13234412.98      2257827.36     13234541.59
      2257788.73     13234627.31      2257803.24     13234756.28
       2257749.8     13235141.05      2257989.12      13235427.2
      2258092.57     13235649.45      2258179.08     13235690.84
      2258211.63     13235855.24      2258317.72     13235996.85

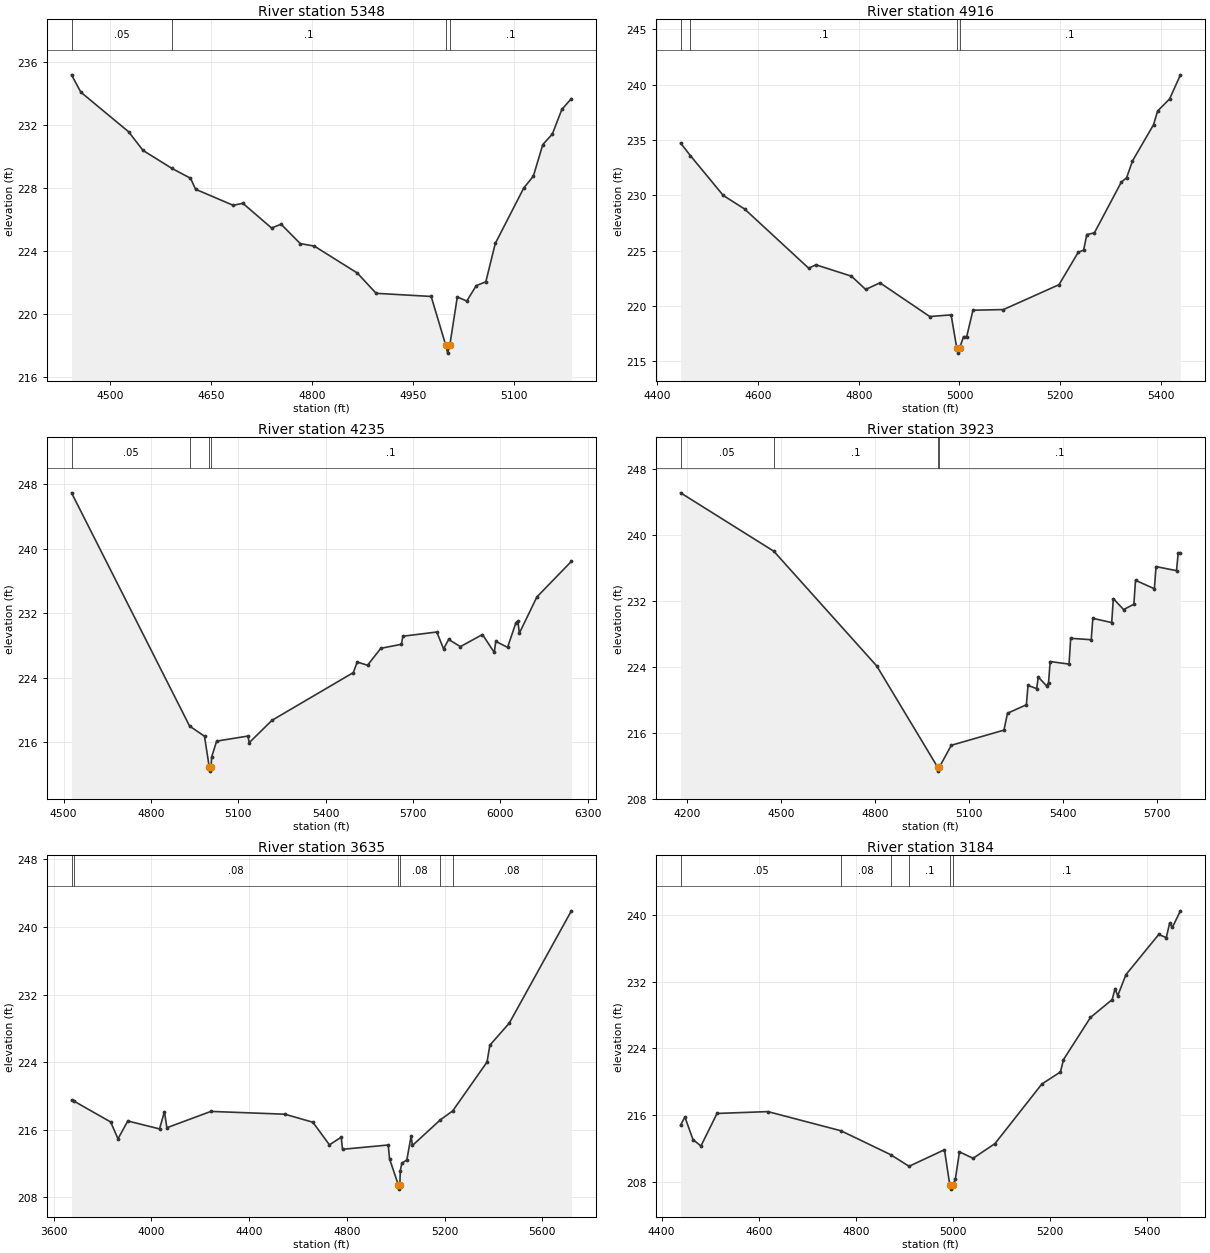
Type RM Length L Ch R = 1 ,5348    ,433,433,433
BEGIN DESCRIPTION:
UNT 027 IN RACR 12.0
END DESCRIPTION:
XS GIS Cut Line= 3
      2256437.71     13231896.87      2256787.72     13231496.85
      2256937.75     13231346.83
#Sta/Elev= 30
  4442.2  235.19    4456  234.09  4527.2  231.57  4548.5  230.39  4591.4  229.25
  4619.2  228.62  4626.8  227.92  4682.8   226.9  4697.1  227.03  4739.8  225.46
    4754   225.7  4782.5  224.47  4803.4  224.31  4867.4   222.6  4895.4  221.31
  4977.3  221.11    4999  218.01  5001.8  217.51    5005  218.01  5016.2  221.08
  5030.3  220.82  5044.4   221.8  5058.6  222.04  5072.7  224.48  5115.2  228.01
  5129.3  228.75  5143.4  230.76  5157.6  231.43  5171.7  232.99  5185.9  233.68
#Mann= 4 ,-1 , 0
  4442.2     .05       0  4591.4      .1       0    4999     .07       0
    5005      .1       0
Bank Sta=4999,5005
XS Rating Curve= 0 ,0
Exp/Cntr=0.3,0.1

Type RM Length L Ch R = 1 ,4916    ,681,681,681
BEGIN DESCRIPTION:
UNT 027 IN RACR 11.0
END DESCRIPTION:
XS GIS Cut Line= 3
      2256637.74     13232196.84      2257037.72     13231796.85
      2257187.73     13231396.82
#Sta/Elev= 30
    4446  234.72  4465.5  233.58  4530.8  229.98  4573.3  228.75  4700.5   223.4
  4714.7  223.71  4785.4  222.68  4813.7  221.48    4842  222.08    4941  219.03
  4983.4  219.18  4994.5  216.22  4997.3  215.72  5000.5  216.22  5008.1  217.21
  5014.3  217.21  5026.8   219.6  5087.3  219.66  5197.7  221.91  5235.9  224.84
  5246.6  225.04  5252.9  226.44    5268   226.6  5321.4  231.18  5332.1  231.59
  5343.6   233.1  5385.5  236.38  5393.5  237.61  5417.5  238.72  5438.9  240.89
#Mann= 4 ,-1 , 0
    4446     .05       0  4465.5      .1       0  4994.5     .07       0
  5000.5      .1       0
Bank Sta=4994.5,5000.5
XS Rating Curve= 0 ,0
Exp/Cntr=0.3,0.1

Type RM Length L Ch R = 1 ,4235    ,311,311,311
BEGIN DESCRIPTION:
UNT 027 IN RACR 10.0
END DESCRIPTION:
XS GIS Cut Line= 4
      2256549.34     13232495.88      2257130.97     13232326.59
      2257291.56     13232135.62      2257508.57      13231302.3
#Sta/Elev= 30
  4527.3  246.96  4932.7  218.04  4983.9  216.78  5000.2  212.95  5002.9  212.45
  5006.2  212.95  5008.4  214.19  5025.5  216.17  5133.1   216.8  5137.5  215.98
  5215.6  218.75    5495  224.67  5508.3  225.98  5543.7  225.58  5589.4  227.68
    5660  228.18  5665.2  229.18  5781.6   229.7    5805   227.6  5822.1  228.78
  5862.6  227.89  5938.4  229.39  5978.9  227.17  5984.1  228.54  6024.6   227.8
    6053  230.83    6060  231.07  6065.1  229.56  6125.3  234.05  6243.7  238.46
#Mann= 4 ,-1 , 0
  4527.3     .05       0  4932.7      .1       0  5000.2     .07       0
  5006.2      .1       0
Bank Sta=5000.2,5006.2
XS Rating Curve= 0 ,0
Exp/Cntr=0.3,0.1

Type RM Length L Ch R = 1 ,3923    ,288,288,288
BEGIN DESCRIPTION:
UNT 027 IN RACR 9.0
END DESCRIPTION:
XS GIS Cut Line= 3
      2256752.11      13233243.2      2257171.41     13232733.58
      2257445.71     13231837.78
#Sta/Elev= 30
  4179.4  245.16  4477.2  238.07  4806.3  224.12  5000.3  211.86    5003  211.36
  5006.3  211.86  5044.3   214.5  5212.4  216.34  5223.8  218.39  5284.1  219.42
  5289.3  221.77  5316.9  221.38  5322.1  222.79  5348.4  221.72  5354.9  222.12
  5360.1  224.67  5420.4  224.36  5425.6  227.49  5491.2  227.32  5496.4  229.92
  5556.7   229.4  5561.9  232.31  5594.7  230.98  5627.5  231.63  5632.7  234.54
    5693  233.51  5698.2   236.2  5763.7  235.71    5769  237.82  5776.2   237.8
#Mann= 4 ,-1 , 0
  4179.4     .05       0  4477.2      .1       0  5000.3     .07       0
  5006.3      .1       0
Bank Sta=5000.3,5006.3
XS Rating Curve= 0 ,0
Exp/Cntr=0.3,0.1

Type RM Length L Ch R = 1 ,3635    ,452,452,452
BEGIN DESCRIPTION:
UNT 027 IN RACR 8.0
END DESCRIPTION:
XS GIS Cut Line= 5
      2257328.89     13234067.02      2257325.42     13233448.99
      2257398.34     13232987.18      2257488.61     13232567.04
      2257609.88     13232050.79
#Sta/Elev= 30
  3673.4  219.52  3683.1   219.4  3833.6  216.93  3863.6  214.94  3903.6  217.05
  4033.6  216.11  4053.6  218.15  4063.6  216.25  4243.6  218.18  4546.7  217.85
    4661   216.9  4728.9  214.23  4777.2  215.13  4782.4   213.7  4969.6  214.21
  4974.7  212.58  5010.9  209.49  5013.6  208.99  5016.9  209.49    5019  211.19
  5025.2  212.05  5045.7  212.45  5063.2  215.29  5068.4  214.15    5183  217.19
  5233.3  218.24  5373.8  224.02  5385.4  226.01  5465.1  228.63    5719   241.9
#Mann= 6 ,-1 , 0
  3673.4      .1       0  3683.1     .08       0  5010.9     .07       0
  5016.9     .08       0    5183     .05       0  5233.3     .08       0
Bank Sta=5010.9,5016.9
XS Rating Curve= 0 ,0
Exp/Cntr=0.3,0.1

Type RM Length L Ch R = 1 ,3184    ,457,457,457
BEGIN DESCRIPTION:
UNT 027 IN RACR 7.0
END DESCRIPTION:
XS GIS Cut Line= 3
      2257370.55     13233591.38       2257478.2     13233230.24
      2258063.83     13232942.62
#Sta/Elev= 30
    4439  214.83  4447.8  215.81  4464.6   213.1  4480.9  212.34  4514.1  216.23
  4618.8  216.45  4769.2  214.16  4871.3  211.31  4909.5  209.91  4982.4  211.89
  4993.4  207.68  4996.1  207.18  4999.4  207.68  5004.7  208.34  5013.3  211.63
  5041.4  210.87  5086.3  212.62    5183  219.75  5221.2  221.19  5227.5  222.67
  5283.1  227.71  5327.8  229.85  5333.6  231.16  5339.2  230.31  5356.1  232.83
  5423.6  237.63  5439.2  237.26  5446.1     239  5451.6  238.47  5468.3  240.46
#Mann= 6 ,-1 , 0
    4439     .05       0  4769.2     .08       0  4871.3     .05       0
  4909.5      .1       0  4993.4     .07       0  4999.4      .1       0
Bank Sta=4993.4,4999.4
XS Rating Curve= 0 ,0
Exp/Cntr=0.3,0.1

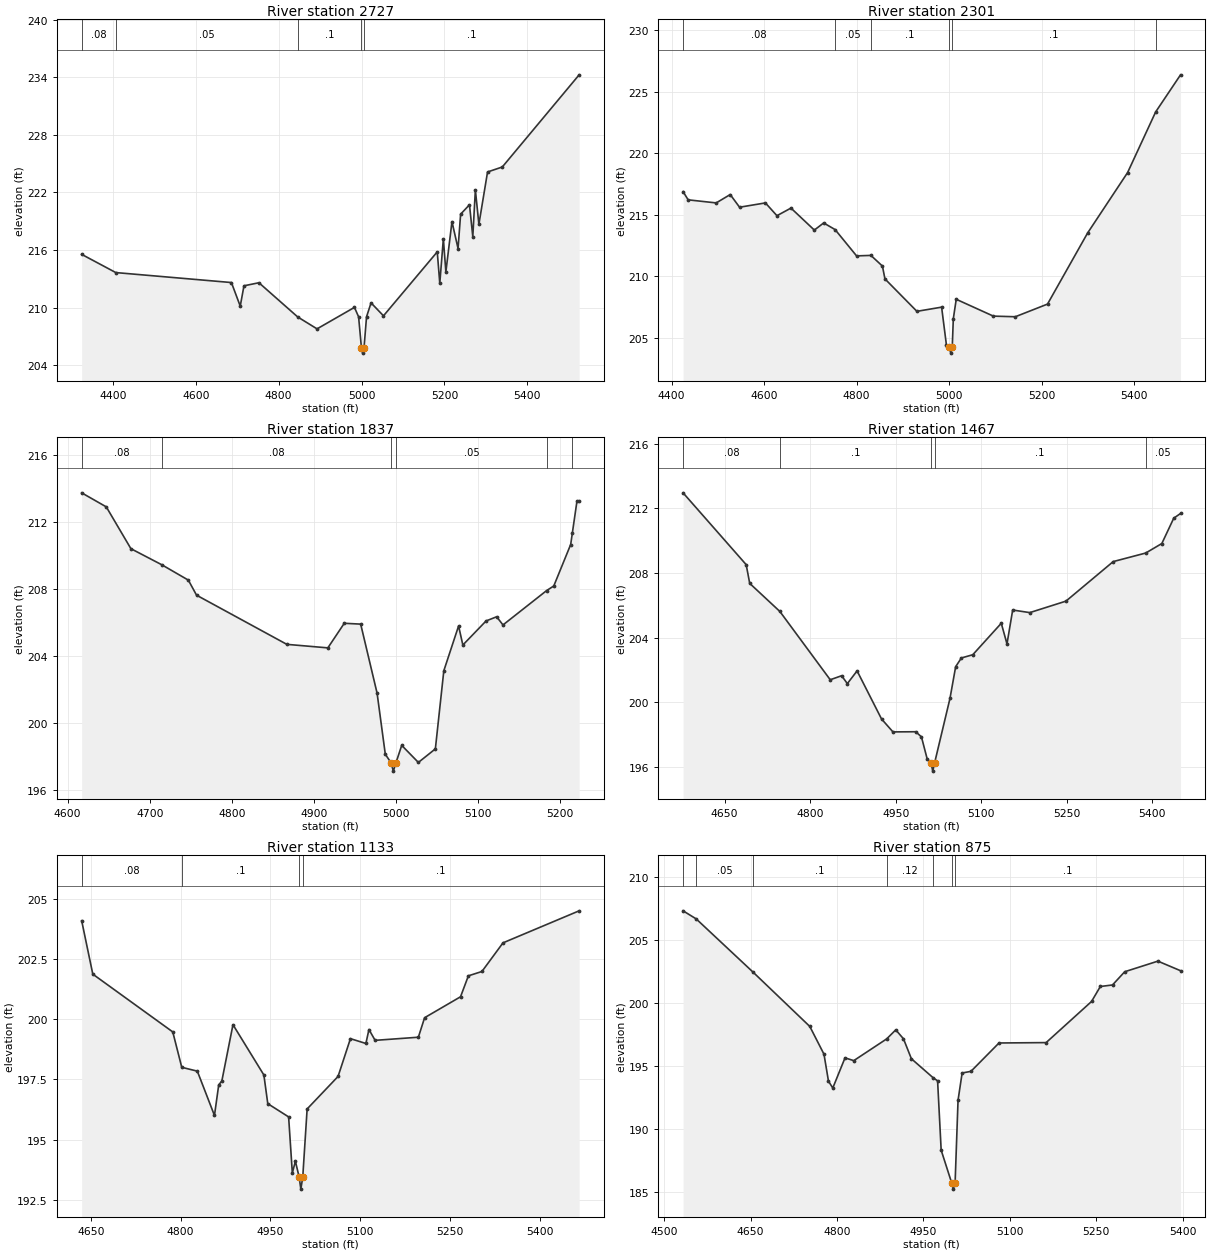
Type RM Length L Ch R = 1 ,2727    ,425,425,425
BEGIN DESCRIPTION:
UNT 027 IN RACR 6.0
END DESCRIPTION:
XS GIS Cut Line= 4
      2257380.97       13234015.      2257436.53     13233612.18
      2257874.03     13233580.93      2258162.26     13233372.58
#Sta/Elev= 30
  4324.4  215.55  4406.8  213.65  4685.9  212.61  4707.2  210.15  4716.2  212.27
  4752.3  212.59    4846  209.02  4892.6  207.78  4982.9  210.02  4992.9  209.04
  4999.9  205.75  5002.7  205.25  5005.9  205.75  5012.1  209.04    5023  210.49
    5053  209.14  5182.8  215.81  5188.9  212.53  5197.5  217.16  5203.6  213.72
  5218.3  218.96    5233  216.16  5239.2  219.74  5260.6  220.72  5268.6  217.39
  5274.8  222.27  5283.3  218.68  5304.2  224.14  5339.8  224.66  5525.3  234.27
#Mann= 5 ,-1 , 0
  4324.4     .08       0  4406.8     .05       0    4846      .1       0
  4999.9     .07       0  5005.9      .1       0
Bank Sta=4999.9,5005.9
XS Rating Curve= 0 ,0
Exp/Cntr=0.3,0.1

Type RM Length L Ch R = 1 ,2301    ,462,462,462
BEGIN DESCRIPTION:
UNT 027 IN RACR 5.0
END DESCRIPTION:
XS GIS Cut Line= 4
      2257377.51     13234417.71      2257422.64     13234101.77
      2257863.61     13233942.04      2258099.74     13233778.84
#Sta/Elev= 30
  4424.9  216.89  4435.9  216.22  4496.5  215.97  4526.8  216.65    4547  215.62
  4602.9  215.97  4627.8  214.93  4658.1  215.55  4708.6  213.76  4728.8  214.34
  4753.5   213.8  4799.9  211.66  4830.9   211.7  4855.8  210.83  4861.2  209.79
  4930.3  207.15  4983.7  207.49  4994.1  204.41  5000.7  204.25  5003.5  203.75
  5006.7  204.25    5009  206.55  5015.3  208.13  5095.6  206.76    5143  206.71
  5212.6  207.74  5299.2  213.52  5385.7  218.44  5446.3  223.37  5500.1  226.39
#Mann= 6 ,-1 , 0
  4424.9     .08       0  4753.5     .05       0  4830.9      .1       0
  5000.7     .07       0  5006.7      .1       0  5446.3     .05       0
Bank Sta=5000.7,5006.7
XS Rating Curve= 0 ,0
Exp/Cntr=0.3,0.1

Type RM Length L Ch R = 1 ,1837    ,370,370,370
BEGIN DESCRIPTION:
UNT 027 IN RACR 4.0
END DESCRIPTION:
XS GIS Cut Line= 3
      2257437.68     13234396.85      2257837.72     13234396.85
      2258037.73     13234346.85
#Sta/Elev= 30
  4617.1  213.76  4647.1  212.92  4677.1  210.42  4714.7  209.46  4747.1  208.54
  4757.1  207.64  4867.1   204.7  4917.1  204.49  4937.1  205.96  4957.1  205.91
  4977.1  201.78  4987.1  198.13  4994.1  197.62  4996.9  197.12  5000.1  197.62
  5007.1  198.66  5027.4  197.64  5048.1  198.45  5058.4  203.12  5076.4   205.8
  5081.6  204.66  5109.9   206.1  5122.8  206.35  5130.5  205.86  5183.8  207.92
  5192.4  208.19    5213  210.67  5215.1  211.38  5220.7  213.28  5223.3  213.28
#Mann= 6 ,-1 , 0
  4617.1     .08       0  4714.7     .08       0  4994.1     .07       0
  5000.1     .05       0  5183.8     .05       0  5215.1      .1       0
Bank Sta=4994.1,5000.1
XS Rating Curve= 0 ,0
Exp/Cntr=0.3,0.1

Type RM Length L Ch R = 1 ,1467    ,334,334,334
BEGIN DESCRIPTION:
UNT 027 IN RACR 3.0
END DESCRIPTION:
XS GIS Cut Line= 4
      2257397.11     13234685.35      2257502.02      13234748.3
      2258047.69     13234758.79      2258199.87     13234622.36
#Sta/Elev= 30
  4577.1  212.97  4687.8  208.52    4694  207.36  4746.9  205.62  4835.2  201.39
  4855.2  201.64  4865.2  201.15  4882.3  201.94  4925.2  198.96  4945.2  198.16
  4985.2  198.17  4995.2  197.85  5005.2  196.49  5012.2  196.23    5015  195.73
  5018.2  196.23  5045.2  200.23  5055.2   202.2  5065.2  202.74  5085.2  202.94
  5135.2  204.89  5145.2  203.61  5155.2  205.71  5185.2  205.55  5248.6  206.26
  5331.5  208.71  5388.5  209.24  5416.8  209.83  5437.7   211.4  5449.6  211.69
#Mann= 5 ,-1 , 0
  4577.1     .08       0  4746.9      .1       0  5012.2     .07       0
  5018.2      .1       0  5388.5     .05       0
Bank Sta=5012.2,5018.2
XS Rating Curve= 0 ,0
Exp/Cntr=0.3,0.1

Type RM Length L Ch R = 1 ,1133    ,258,258,258
BEGIN DESCRIPTION:
Mapping XS fdd35097
END DESCRIPTION:
XS GIS Cut Line= 4
      2257399.09     13235140.62      2257522.99     13235138.19
      2257972.29     13235024.04      2258163.45     13234874.02
#Sta/Elev= 30
  4634.9  204.09  4653.5  201.87    4787  199.47    4802     198    4828  197.84
  4856.6     196  4863.7  197.27  4868.9  197.43  4887.5  199.77  4939.1  197.68
  4945.6  196.49  4980.4  195.94  4986.6  193.61  4991.7   194.1    4998  193.44
  5000.8  192.94    5004  193.44  5011.3  196.27  5062.9  197.62  5083.6  199.19
  5109.4  198.99  5114.5  199.57  5124.8  199.12    5197  199.25  5207.4  200.06
  5267.4  200.93  5280.5   201.8  5303.1  201.98  5338.3  203.17  5465.4   204.5
#Mann= 4 ,-1 , 0
  4634.9     .08       0    4802      .1       0    4998     .07       0
    5004      .1       0
Bank Sta=4998,5004
XS Rating Curve= 0 ,0
Exp/Cntr=0.3,0.1

Type RM Length L Ch R = 1 ,875     ,200,200,200
BEGIN DESCRIPTION:
UNT 027 IN RACR 2.0
END DESCRIPTION:
XS GIS Cut Line= 3
      2257439.09     13235440.88      2257675.17     13235414.65
      2258203.92      13235079.6
#Sta/Elev= 30
  4532.8  207.32  4555.6  206.68  4654.7  202.44  4752.8  198.15  4777.4  195.95
  4785.2  193.81  4792.7  193.27  4813.9  195.66  4829.1  195.44  4886.1  197.16
    4902  197.88  4915.4  197.17  4929.1  195.59  4966.9  194.08  4974.6  193.84
  4980.8  188.34    4999  185.75  5001.7  185.25    5005  185.75  5010.1   192.3
  5017.2  194.46  5032.5  194.59  5081.2  196.84    5163  196.87  5241.8  200.13
  5257.1  201.32  5278.2  201.44  5299.4  202.49    5357  203.33  5396.3  202.57
#Mann= 7 ,-1 , 0
  4532.8     .08       0  4555.6     .05       0  4654.7      .1       0
  4886.1     .12       0  4966.9      .1       0    4999     .07       0
    5005      .1       0
Bank Sta=4999,5005
XS Rating Curve= 0 ,0
Exp/Cntr=0.3,0.1

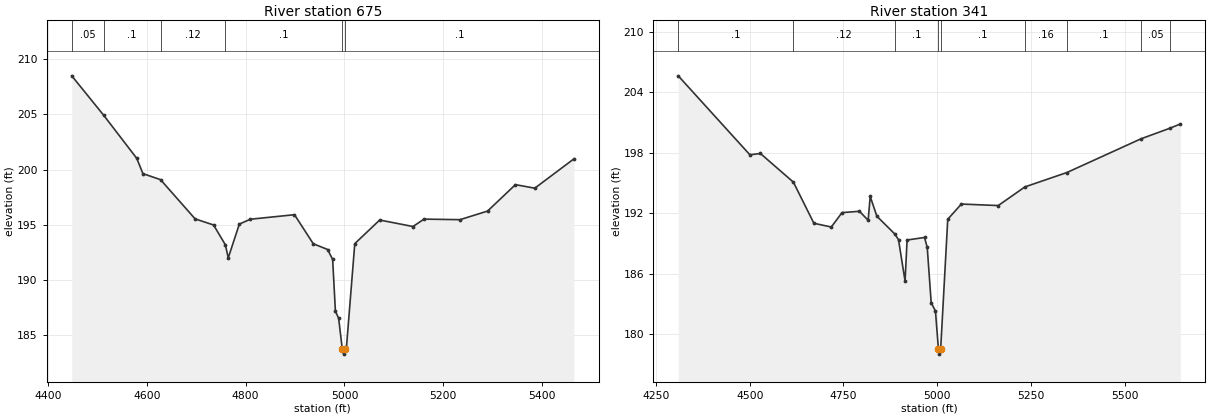
Type RM Length L Ch R = 1 ,675     ,334,334,334
BEGIN DESCRIPTION:
Mapping XS 169a002f
END DESCRIPTION:
XS GIS Cut Line= 4
      2257491.49     13235598.28      2257633.19     13235624.52
      2258352.01     13235267.74      2258392.71     13235211.78
#Sta/Elev= 30
  4448.3   208.5  4512.7  204.94  4579.8  201.03  4592.2  199.65  4627.9   199.1
  4697.9  195.55  4735.2     195  4759.1   193.2  4764.9  192.02  4787.3  195.08
  4809.6  195.52  4898.9  195.93  4936.9   193.3  4965.9  192.78  4976.1  191.88
  4981.7  187.19  4988.2  186.56  4995.5  183.81  4998.3  183.31  5001.5  183.81
  5004.1  183.96  5020.9  193.31  5071.3  195.45  5138.6  194.86    5161  195.53
  5233.8  195.48  5289.6  196.26  5345.9  198.65  5385.1  198.33  5464.1  200.98
#Mann= 6 ,-1 , 0
  4448.3     .05       0  4512.7      .1       0  4627.9     .12       0
  4759.1      .1       0  4995.5     .07       0  5001.5      .1       0
Bank Sta=4995.5,5001.5
XS Rating Curve= 0 ,0
Exp/Cntr=0.3,0.1

Type RM Length L Ch R = 1 ,341     ,0,0,0
BEGIN DESCRIPTION:
UNT 027 IN RACR 1.0
END DESCRIPTION:
XS GIS Cut Line= 4
      2257554.49     13235766.18       2257780.1     13235876.37
      2258357.26     13235619.27      2258540.39     13235200.69
#Sta/Elev= 30
  4309.1  205.65  4500.3  197.81  4528.4  197.94  4616.5  195.09  4671.1  191.01
  4717.5  190.64  4746.2  192.07  4792.7   192.2  4815.9  191.31  4821.4  193.67
  4839.2  191.71  4887.2  189.94  4896.9  189.38  4914.4  185.27  4919.8  189.35
  4966.3   189.6  4973.6  188.61  4984.1  183.12  4995.5   182.3  5003.4  178.52
  5006.2  178.02  5009.4  178.52  5028.3  191.41  5064.7  192.92  5163.1  192.77
  5234.1  194.62  5346.3  196.05  5543.5  199.39    5622  200.46  5648.9  200.87
#Mann= 9 ,-1 , 0
  4309.1      .1       0  4616.5     .12       0  4887.2      .1       0
  5003.4     .07       0  5009.4      .1       0  5234.1     .16       0
  5346.3      .1       0  5543.5     .05       0    5622      .1       0
Bank Sta=5003.4,5009.4
XS Rating Curve= 0 ,0
Exp/Cntr=0.3,0.1
Stream Node=UNT 027 IN RACR ,Reach-1         , 0 , 0 ,Upstream end
Stream Node=UNT 027 IN RACR ,Reach-1         , 0 , 1 ,Downstream end

Chan Stop Cuts=-1
Use User Specified Reach Order=0
Composite Channel Slope=5