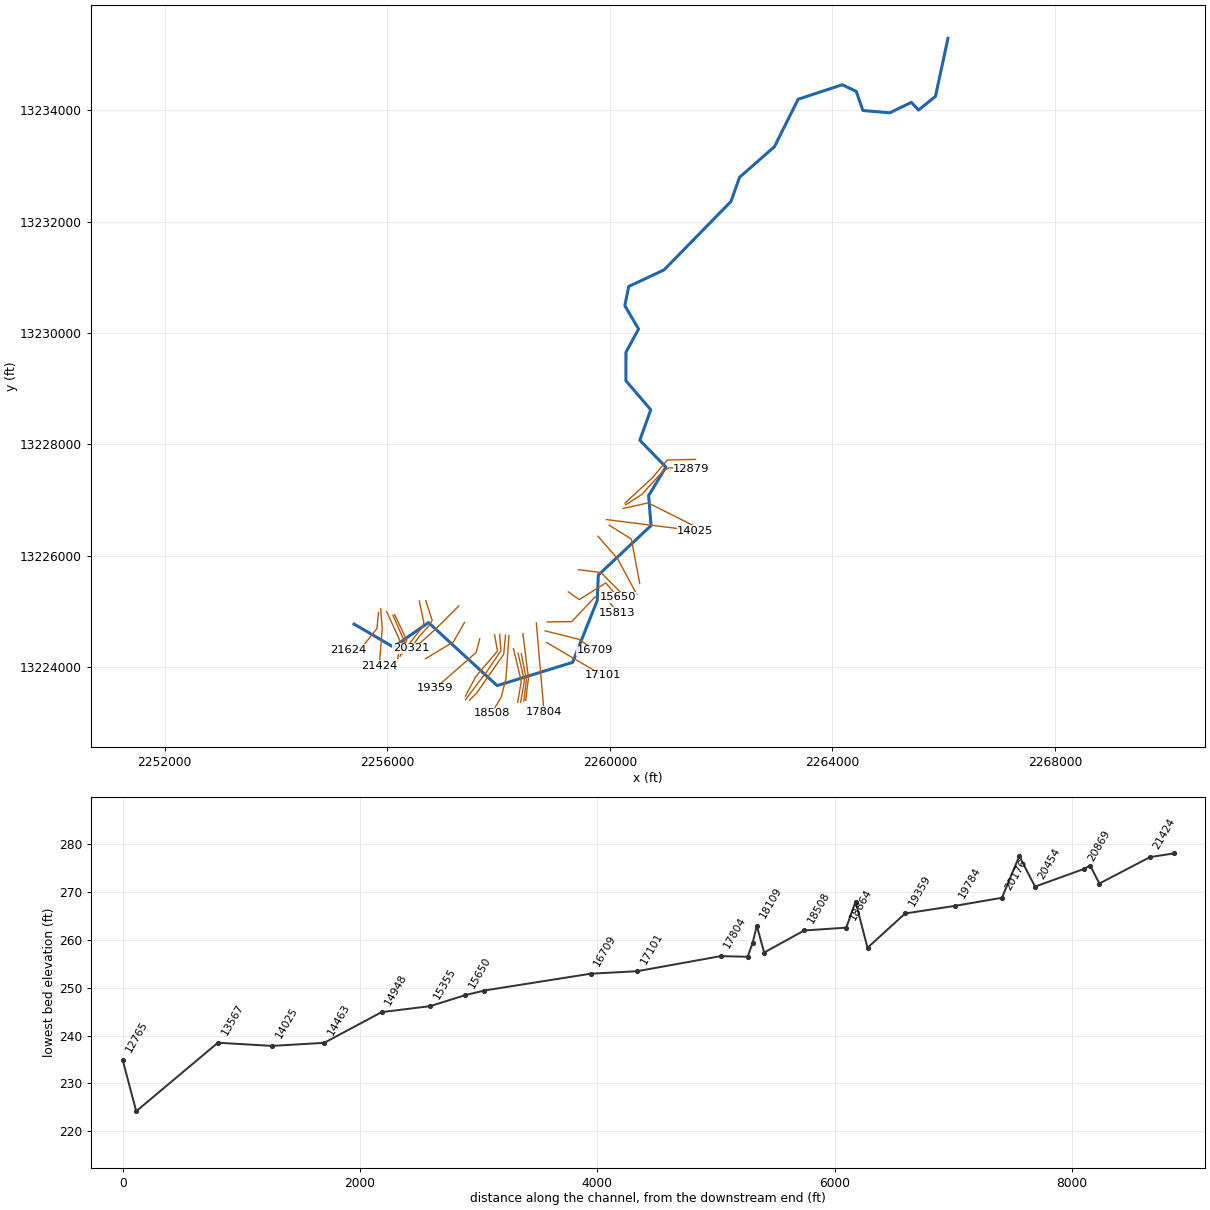
--- UNT 028 IN RACR.prj (project) ---

Proj Title=UNT 028 IN RACR Base Level Engineering
Current Plan=p01
Default Exp/Contr=0.3,0.1
English Units
Geom File=g01
Flow File=f01
Plan File=p01
Y Axis Title=Elevation
X Axis Title(PF)=Main Channel Distance
X Axis Title(XS)=Station
BEGIN DESCRIPTION:
UNT 028 IN RACR
END DESCRIPTION:
DSS Export Rating Curves= 0
DSS Export Rating Curve Sorted= 0
DSS Export Volume Flow Curves= 0
DXF OffsetX= 0
DXF OffsetY= 0
DXF ScaleX= 1
DXF ScaleY= 10

--- UNT 028 IN RACR.p01 (plan) ---

Plan Title=Multiple Run
Short Identifier=Multiple
Geom File=g01
Flow File=f01
Subcritical Flow
K Sum by GR= 0
Std Step Tol= 0.01
Critical Tol= 0.01
Num of Std Step Trials= 20
Max Error Tol= 0.3
Flow Tol Ratio= 0.001
Split Flow NTrial= 30
Split Flow Tol= 0.02
Split Flow Ratio= 0.02
Log Output Level= 0
Friction Slope Method= 1
Unsteady Friction Slope Method= 2
Unsteady Bridges Friction Slope Method= 1
Parabolic Critical Depth
Global Vel Dist=  1 , 1 , 1
Global Log Level= 0
CheckData=True
Encroach Param= -1, 0, 0, 0
BEGIN DESCRIPTION:
Multiple Run
END DESCRIPTION:

--- UNT 028 IN RACR.f01 (steady flow) ---

Flow Title=Multiple
Program Version=4.10
Number of Profiles= 7
Profile Names=10-year,25-year,50-year,1pct_min,100-year,1pct_plu,500-year
River Rch & RM=UNT 028 IN RACR,Reach-1         ,21624
     171     232     280     250     338     457     498
River Rch & RM=UNT 028 IN RACR,Reach-1         ,21424
     216     295     360     322     436     590     650
River Rch & RM=UNT 028 IN RACR,Reach-1         ,17804
     377     530     658     600     812    1098    1254
River Rch & RM=UNT 028 IN RACR,Reach-1         ,1350
     491     698     874     804    1087    1470    1705
Boundary for River Rch & Prof#=UNT 028 IN RACR,Reach-1         , 1
Up Type= 0
Dn Type= 3
Dn Slope=0.005
Boundary for River Rch & Prof#=UNT 028 IN RACR,Reach-1         , 2
Up Type= 0
Dn Type= 3
Dn Slope=0.005
Boundary for River Rch & Prof#=UNT 028 IN RACR,Reach-1         , 3
Up Type= 0
Dn Type= 3
Dn Slope=0.005
Boundary for River Rch & Prof#=UNT 028 IN RACR,Reach-1         , 4
Up Type= 0
Dn Type= 3
Dn Slope=0.005
Boundary for River Rch & Prof#=UNT 028 IN RACR,Reach-1         , 5
Up Type= 0
Dn Type= 3
Dn Slope=0.005
Boundary for River Rch & Prof#=UNT 028 IN RACR,Reach-1         , 6
Up Type= 0
Dn Type= 3
Dn Slope=0.005
Boundary for River Rch & Prof#=UNT 028 IN RACR,Reach-1         , 7
Up Type= 0
Dn Type= 3
Dn Slope=0.005
DSS Import GetInterval= 0
DSS Import GetPeak= 0
DSS Import FillOption= 0

--- UNT 028 IN RACR.g01 (geometry) ---

Geom Title=Existing Conditions
Program Version=4.10

River Reach=UNT 028 IN RACR ,Reach-1
Reach XY= 30
      2255403.12     13224769.05      2256110.51     13224355.91
      2256741.34     13224795.75      2257974.25      13223663.1
        2259331.     13224080.49      2259774.31      13225193.5
      2259793.07     13225650.54       2260740.9     13226538.96
      2260697.62      13227076.9       2261008.1     13227590.45
       2260539.5      13228073.4      2260735.79      13228620.9
      2260289.67     13229142.67      2260290.51      13229655.7
      2260517.07     13230071.97       2260269.5     13230492.33
      2260340.01     13230836.47       2260974.2      13231134.7
       2262177.1     13232363.55      2262332.68     13232799.74
      2262959.79     13233350.16      2263384.87     13234202.02
      2264177.05     13234462.69      2264429.76     13234343.63
      2264548.61     13233999.72      2265032.14      13233958.6
      2265420.93     13234145.95      2265547.72     13234006.85
      2265853.27     13234253.96      2266077.72     13235296.86

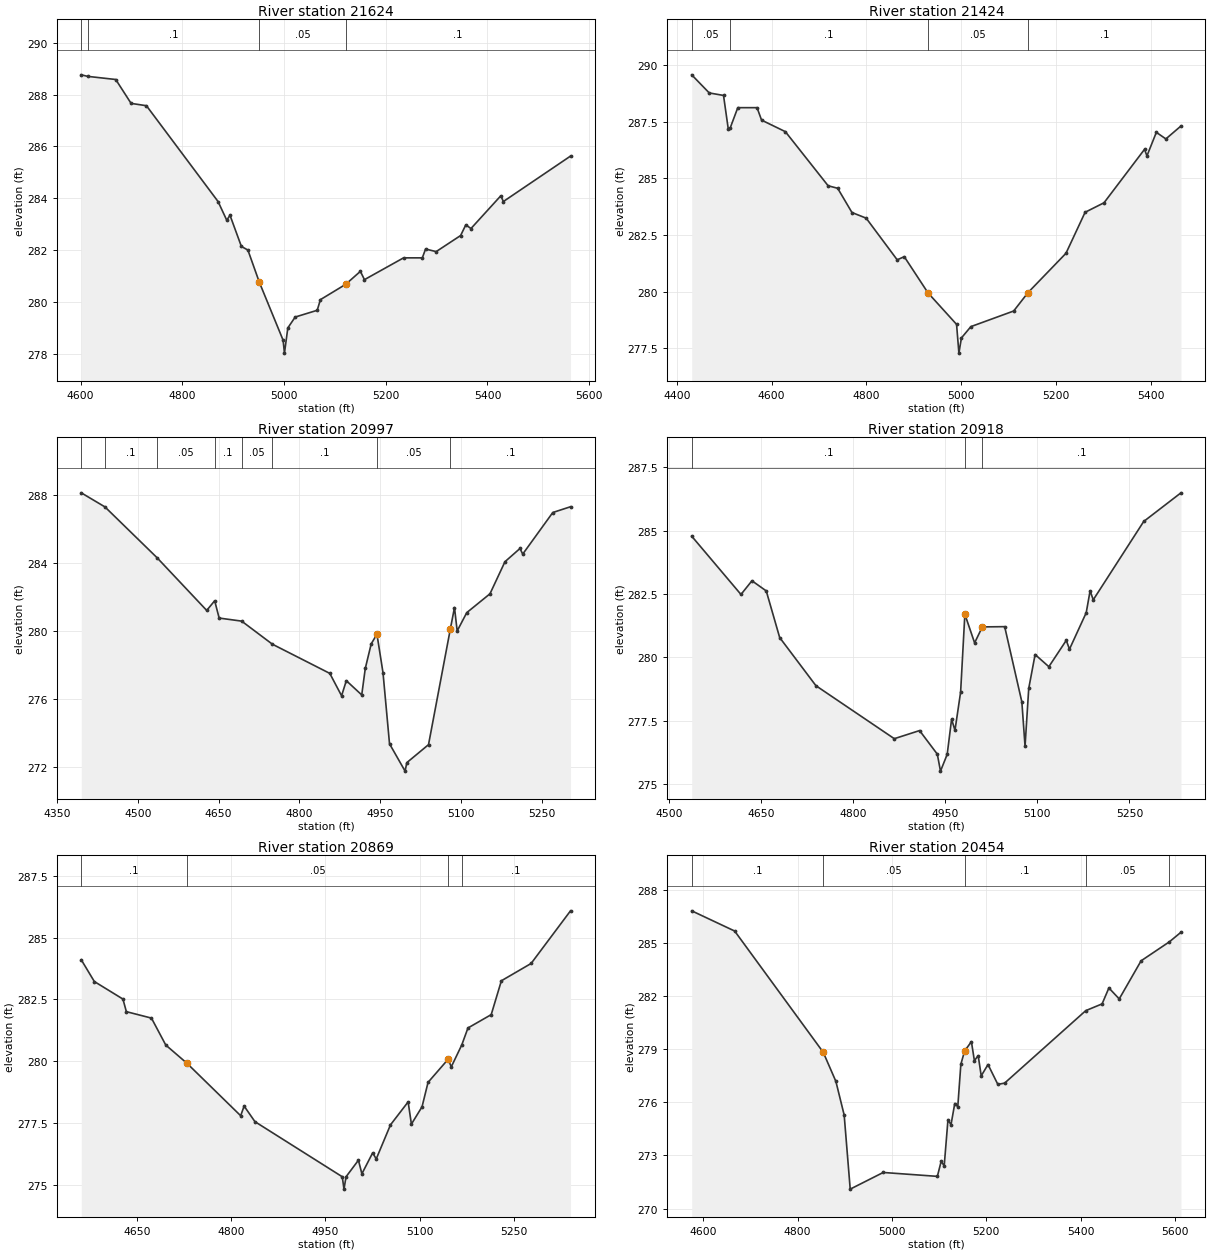
Type RM Length L Ch R = 1 ,21624   ,200,200,200
BEGIN DESCRIPTION:
UNT 028 IN RACR 45.0
END DESCRIPTION:
XS GIS Cut Line= 4
      2255843.82     13224974.31      2255813.44     13224687.85
      2255548.68     13224353.65      2255305.66     13224305.91
#Sta/Elev= 30
  4601.2  288.76  4614.1   288.7    4669  288.58  4699.2  287.66  4729.4  287.57
  4870.2  283.88  4887.3  283.16  4893.7  283.35  4916.1  282.15  4928.9  282.01
  4951.4  280.77  4998.1  278.54  5000.8  278.04  5007.4  279.01  5021.9  279.43
  5065.2  279.69  5071.5   280.1  5121.2  280.69  5150.1  281.19  5158.1  280.87
    5235  281.71  5271.9  281.71  5278.3  282.05  5299.1  281.95  5347.2  282.57
  5357.4  282.98  5367.6  282.84  5426.2   284.1  5431.3  283.88  5563.3  285.63
#Mann= 4 ,-1 , 0
  4601.2     .05       0  4614.1      .1       0  4951.4     .05       0
  5121.2      .1       0
Bank Sta=4951.4,5121.2
XS Rating Curve= 0 ,0
Exp/Cntr=0.3,0.1

Type RM Length L Ch R = 1 ,21424   ,428,428,428
BEGIN DESCRIPTION:
Mapping XS 88c0a332
END DESCRIPTION:
XS GIS Cut Line= 3
      2255882.88     13225043.79      2255908.93     13224692.19
      2255856.85     13224015.16
#Sta/Elev= 30
  4431.5  289.57  4468.5  288.77  4498.6  288.66  4508.6  287.18  4512.6  287.22
  4528.7  288.12  4569.3  288.12  4578.8  287.57    4629  287.06  4719.2  284.67
  4739.3  284.56  4769.4  283.49  4799.4  283.24  4864.8   281.4  4879.7  281.54
  4929.8  279.94    4990  278.55  4994.9  277.28  5000.2  277.95  5020.1  278.45
  5110.4  279.14  5140.5  279.95  5220.7  281.69    5261   283.5  5300.9  283.92
  5386.3  286.28  5391.4  285.99  5411.2  287.03  5431.3  286.74  5463.1  287.31
#Mann= 4 ,-1 , 0
  4431.5     .05       0  4512.6      .1       0  4929.8     .05       0
  5140.5      .1       0
Bank Sta=4929.8,5140.5
XS Rating Curve= 0 ,0
Exp/Cntr=0.3,0.1

Type RM Length L Ch R = 1 ,20997   ,78,78,78
BEGIN DESCRIPTION:
UNT 028 IN RACR 44.0
END DESCRIPTION:
XS GIS Cut Line= 3
      2255987.72     13224996.86      2256237.72     13224446.85
      2256187.72     13224146.86
#Sta/Elev= 30
  4394.9  288.15  4438.9  287.32  4535.5  284.33  4627.8  281.22  4642.6  281.79
  4650.9  280.77  4692.7  280.59  4749.7  279.23  4856.3  277.51  4878.2  276.19
    4887  277.08  4915.6  276.24  4922.2   277.8  4933.2  279.25 4943.86  279.82
  4955.1  277.55  4967.2  273.36  4996.1  271.75  4999.3  272.25  5039.6  273.31
  5080.2  280.14  5087.8  281.39  5092.8  280.01  5110.6  281.09  5153.7   282.2
  5181.5  284.09  5209.4  284.87  5214.5  284.54  5270.3  286.99  5303.2  287.33
#Mann= 8 ,-1 , 0
  4394.9     .05       0  4438.9      .1       0  4535.5     .05       0
  4642.6      .1       0  4692.7     .05       0  4749.7      .1       0
 4943.86     .05       0  5080.2      .1       0
Bank Sta=4943.86,5080.2
XS Rating Curve= 0 ,0
Exp/Cntr=0.3,0.1

Type RM Length L Ch R = 1 ,20918   ,49,49,49
BEGIN DESCRIPTION:
Mapping XS 463194dc
END DESCRIPTION:
XS GIS Cut Line= 4
       2256101.6      13224928.1      2256281.28     13224519.27
      2256312.53     13224467.19       2256231.8     13224188.56
#Sta/Elev= 30
  4536.6  284.78  4616.9  282.48  4634.8  283.02  4658.1  282.62    4680  280.78
  4739.1  278.88  4866.8  276.79    4908  277.11  4936.9  276.18  4942.1  275.51
    4953  276.17  4960.2  277.56  4965.7  277.12  4974.9  278.63  4981.8   281.7
  4997.7  280.57  5010.3   281.2  5046.7  281.21  5074.7  278.24  5079.9  276.49
  5085.9  278.77  5096.3  280.11  5118.7  279.63  5147.1  280.67  5152.3  280.32
  5179.6  281.76  5185.9  282.62  5191.1  282.27  5273.3  285.36    5334  286.49
#Mann= 3 , 0 , 0
  4536.6      .1       0  4981.8     .05       0  5010.3      .1       0
#XS Ineff= 2 ,-1
 4655.11 4980.68  281.14 5043.75 5196.59  281.03
Permanent Ineff=
       T       T
Bank Sta=4981.8,5010.3
XS Rating Curve= 0 ,0
Exp/Cntr=0.3,0.1

Type RM Length L Ch R = 1 ,20869   ,415,415,415
BEGIN DESCRIPTION:
Mapping XS aac9e85e
END DESCRIPTION:
XS GIS Cut Line= 3
      2256132.83     13224938.56      2256348.98     13224482.82
      2256263.06     13224222.44
#Sta/Elev= 30
  4561.6   284.1  4582.4  283.22  4627.9  282.51  4633.4     282  4673.3  281.74
  4696.1  280.65  4729.9  279.91  4815.3  277.79  4820.8  278.18    4838  277.55
    4977  275.32  4979.7  274.82    4983  275.32  5002.7  275.99  5008.2  275.44
  5025.4  276.29    5031  276.04  5053.7  277.42  5081.8  278.35    5087  277.45
  5103.9  278.15  5113.5  279.14  5145.3  280.07  5150.5  279.77  5167.1  280.65
    5177  281.34    5214  281.88  5230.2  283.25  5277.5  283.95  5340.2  286.08
#Mann= 4 ,-1 , 0
  4561.6      .1       0  4729.9     .05       0  5145.3      .1       0
  5167.1      .1       0
Bank Sta=4729.9,5145.3
XS Rating Curve= 0 ,0
Exp/Cntr=0.3,0.1

Type RM Length L Ch R = 1 ,20454   ,133,133,133
BEGIN DESCRIPTION:
Mapping XS e938f20f
END DESCRIPTION:
XS GIS Cut Line= 5
      2256575.54     13225185.96      2256656.28     13224803.13
      2256640.65       13224725.      2256369.82     13224383.86
        2256323.     13224261.62
#Sta/Elev= 30
  4575.3   286.8  4666.4  285.66  4854.2  278.82    4881  277.18  4898.6  275.28
  4911.4   271.1  4981.4  272.04  5096.2  271.82  5104.3  272.67  5110.7  272.41
  5118.7  275.02  5125.1  274.73  5133.1  275.93  5139.5  275.75    5146  278.14
  5153.9  278.89  5168.4  279.42  5174.7  278.35  5182.8  278.63  5189.2  277.49
  5203.6  278.13  5224.4  277.01  5238.8  277.08  5410.9  281.17  5445.5  281.55
  5459.9  282.45  5481.8  281.83  5528.2  283.98  5588.1  285.05  5612.7  285.59
#Mann= 5 ,-1 , 0
  4575.3      .1       0  4854.2     .05       0  5153.9      .1       0
  5410.9     .05       0  5588.1      .1       0
Bank Sta=4854.2,5153.9
XS Rating Curve= 0 ,0
Exp/Cntr=0.3,0.1

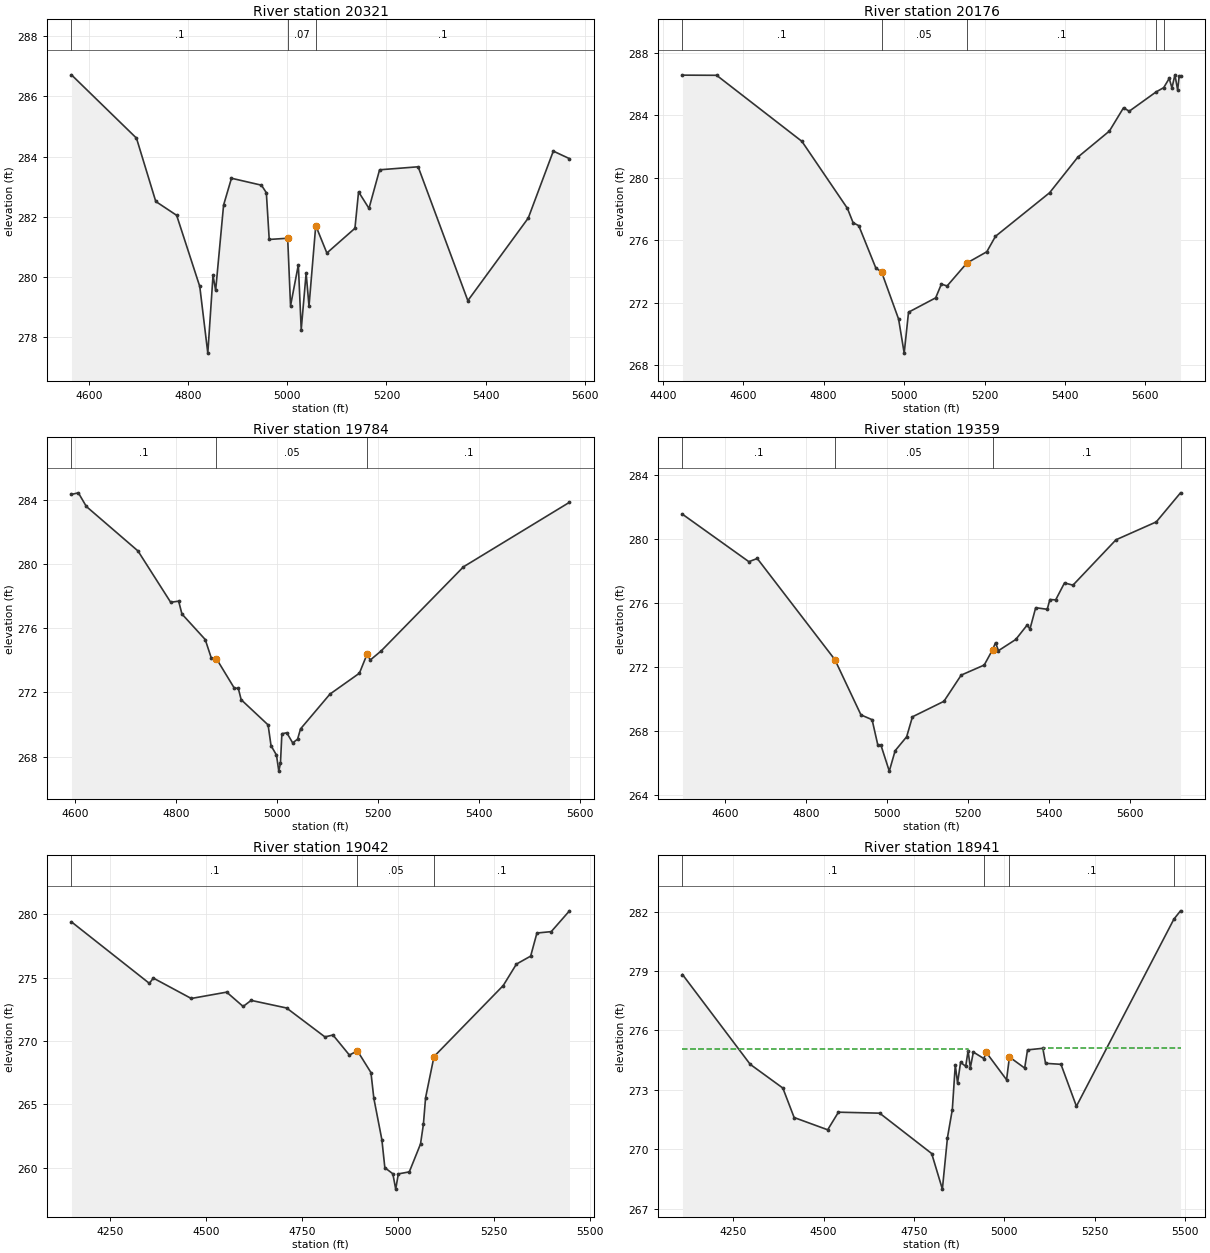
Type RM Length L Ch R = 1 ,20321   ,146,146,146
BEGIN DESCRIPTION:
Mapping XS 2378894c
END DESCRIPTION:
XS GIS Cut Line= 5
      2256692.75      13225188.5      2256807.32     13224836.98
      2256744.82     13224730.21      2256588.57     13224566.15
      2256424.48     13224334.35
#Sta/Elev= 30
  4565.1  286.71  4696.2  284.61  4735.1  282.51  4777.2  282.05  4823.8  279.69
    4840  277.48  4850.5  280.06  4855.8  279.56  4871.8  282.39  4887.7  283.28
  4948.1  283.05    4958   282.8  4963.8  281.25    5001  281.29  5006.8  279.05
  5022.5  280.41  5028.3  278.26  5038.2  280.13    5044  279.04  5057.6  281.71
    5080   280.8  5136.6  281.62  5143.9  282.83  5164.9  282.28  5186.3  283.56
    5264  283.66  5364.2  279.22    5486  281.96  5536.5  284.18  5569.1  283.93
#Mann= 3 , 0 , 0
  4565.1      .1       0    5001     .07       0  5057.6      .1       0
Bank Sta=5001,5057.6
XS Rating Curve= 0 ,0
Exp/Cntr=0.3,0.1

Type RM Length L Ch R = 1 ,20176   ,392,392,392
BEGIN DESCRIPTION:
UNT 028 IN RACR 43.0
END DESCRIPTION:
XS GIS Cut Line= 3
      2257287.72     13225096.85      2256887.72     13224696.85
      2256387.69     13224246.83
#Sta/Elev= 30
  4448.9  286.57  4533.8  286.56  4745.9  282.33    4859  278.04  4873.2  277.12
  4887.3  276.93  4929.7  274.22  4943.9  273.97  4986.3  270.95  5000.2  268.77
    5011  271.39  5078.5  272.31  5092.7  273.19  5106.9  273.07  5156.2  274.54
  5205.6  275.26  5227.2  276.25  5361.8  279.04    5432  281.32  5510.5  282.99
  5545.6  284.48  5559.8  284.26  5626.3  285.49  5645.5  285.77  5659.2  286.36
    5666  285.75  5673.4  286.59  5680.2  285.61  5683.9   286.5  5687.3   286.5
#Mann= 5 ,-1 , 0
  4448.9      .1       0  4943.9     .05       0  5156.2      .1       0
  5626.3     .05       0  5645.5      .1       0
Bank Sta=4943.9,5156.2
XS Rating Curve= 0 ,0
Exp/Cntr=0.3,0.1

Type RM Length L Ch R = 1 ,19784   ,424,424,424
BEGIN DESCRIPTION:
UNT 028 IN RACR 42.0
END DESCRIPTION:
XS GIS Cut Line= 3
      2257387.71     13224796.83      2257187.72     13224446.85
      2256687.71     13224146.85
#Sta/Elev= 30
  4592.9  284.34  4606.6  284.44  4622.4  283.59  4724.6  280.82  4789.4  277.62
  4805.2  277.69  4811.7  276.89  4857.8   275.3    4870  274.13  4880.1   274.1
  4915.4  272.27  4923.3  272.26    4929  271.55  4982.3  269.98  4988.1  268.69
  4998.9   268.1  5003.5   267.1  5006.8   267.6  5009.6  269.43  5019.3  269.49
    5031  268.86  5040.7  269.09  5046.5  269.73  5104.8   271.9  5163.1   273.2
  5178.7  274.42  5184.5  274.02  5205.9  274.58  5369.2  279.83  5579.1  283.85
#Mann= 3 , 0 , 0
  4592.9      .1       0  4880.1     .05       0  5178.7      .1       0
Bank Sta=4880.1,5178.7
XS Rating Curve= 0 ,0
Exp/Cntr=0.3,0.1

Type RM Length L Ch R = 1 ,19359   ,317,317,317
BEGIN DESCRIPTION:
UNT 028 IN RACR 41.0
END DESCRIPTION:
XS GIS Cut Line= 3
      2257662.39     13224505.54      2257597.29     13224258.16
       2256863.8     13223615.81
#Sta/Elev= 30
  4495.2  281.57  4659.3   278.6    4680   278.8  4871.8  272.47  4936.3  269.01
  4963.8  268.71  4978.1  267.11  4985.6  267.12  5006.3  265.49  5020.8  266.77
  5049.2  267.64  5063.5  268.89  5141.3  269.86    5184   271.5  5240.9  272.13
  5261.8   273.1  5268.8  273.53  5276.1  273.03  5318.8  273.73  5347.2  274.64
  5353.9  274.38  5368.1  275.72  5396.6  275.62  5403.2  276.23  5417.5  276.21
  5439.3  277.27  5460.2  277.13  5566.5  279.97  5666.1  281.09    5726  282.91
#Mann= 4 ,-1 , 0
  4495.2      .1       0  4871.8     .05       0  5261.8      .1       0
    5726     .05       0
Bank Sta=4871.8,5261.8
XS Rating Curve= 0 ,0
Exp/Cntr=0.3,0.1

Type RM Length L Ch R = 1 ,19042   ,101,101,101
BEGIN DESCRIPTION:
Mapping XS 6df1adf7
END DESCRIPTION:
XS GIS Cut Line= 4
      2257927.75     13224576.39      2257981.89     13224285.33
      2257593.78     13223829.17      2257403.69     13223475.04
#Sta/Elev= 30
  4150.3  279.39  4353.3  274.54  4363.4  274.96  4462.3  273.35  4554.5  273.85
  4597.4  272.72  4618.2   273.2  4710.5   272.6  4810.4  270.32  4831.3  270.47
  4874.1  268.89    4895  269.22  4930.2  267.51  4937.8  265.47  4958.7  262.21
  4966.4  260.01  4987.2  259.53  4994.7  258.32  5001.5  259.52  5030.1  259.68
  5059.3  261.88  5066.8  263.43  5072.5  265.53  5094.4  268.77  5274.7  274.37
    5309  276.06  5346.1  276.69  5362.4  278.51  5399.7  278.62  5447.2  280.26
#Mann= 3 , 0 , 0
  4150.3      .1       0    4895     .05       0  5094.4      .1       0
Bank Sta=4895,5094.4
XS Rating Curve= 0 ,0
Exp/Cntr=0.3,0.1

Type RM Length L Ch R = 1 ,18941   ,78,78,78
BEGIN DESCRIPTION:
Mapping XS 18ca8b35
END DESCRIPTION:
XS GIS Cut Line= 4
      2258020.29     13224583.56      2258043.43      13224290.4
      2257793.96     13223922.62      2257408.14     13223413.34
#Sta/Elev= 30
  4109.7  278.83    4297  274.29  4387.3  273.09  4418.5   271.6  4511.3  270.98
    4541  271.87  4655.1  271.82  4798.9  269.78  4828.5  267.98  4842.6  270.59
    4856     272  4864.2  274.26  4870.5  273.34  4878.8  274.39    4893  274.19
  4899.6  274.97  4905.9  274.12  4914.2  274.91  4943.2  274.58  4949.5   274.9
    5006  273.51    5014  274.66  5056.1   274.1    5064  275.02  5106.3   275.1
  5113.9  274.34  5156.5  274.29  5199.2  272.17  5468.8  281.63  5487.1  282.05
#Mann= 4 ,-1 , 0
  4109.7      .1       0  4943.2     .05       0    5014      .1       0
  5468.8     .05       0
#XS Ineff= 2 , 0
       0    4899  275.04 5107.69       0  275.12
Permanent Ineff=
       T       T
Bank Sta=4949.5,5014
XS Rating Curve= 0 ,0
Exp/Cntr=0.3,0.1

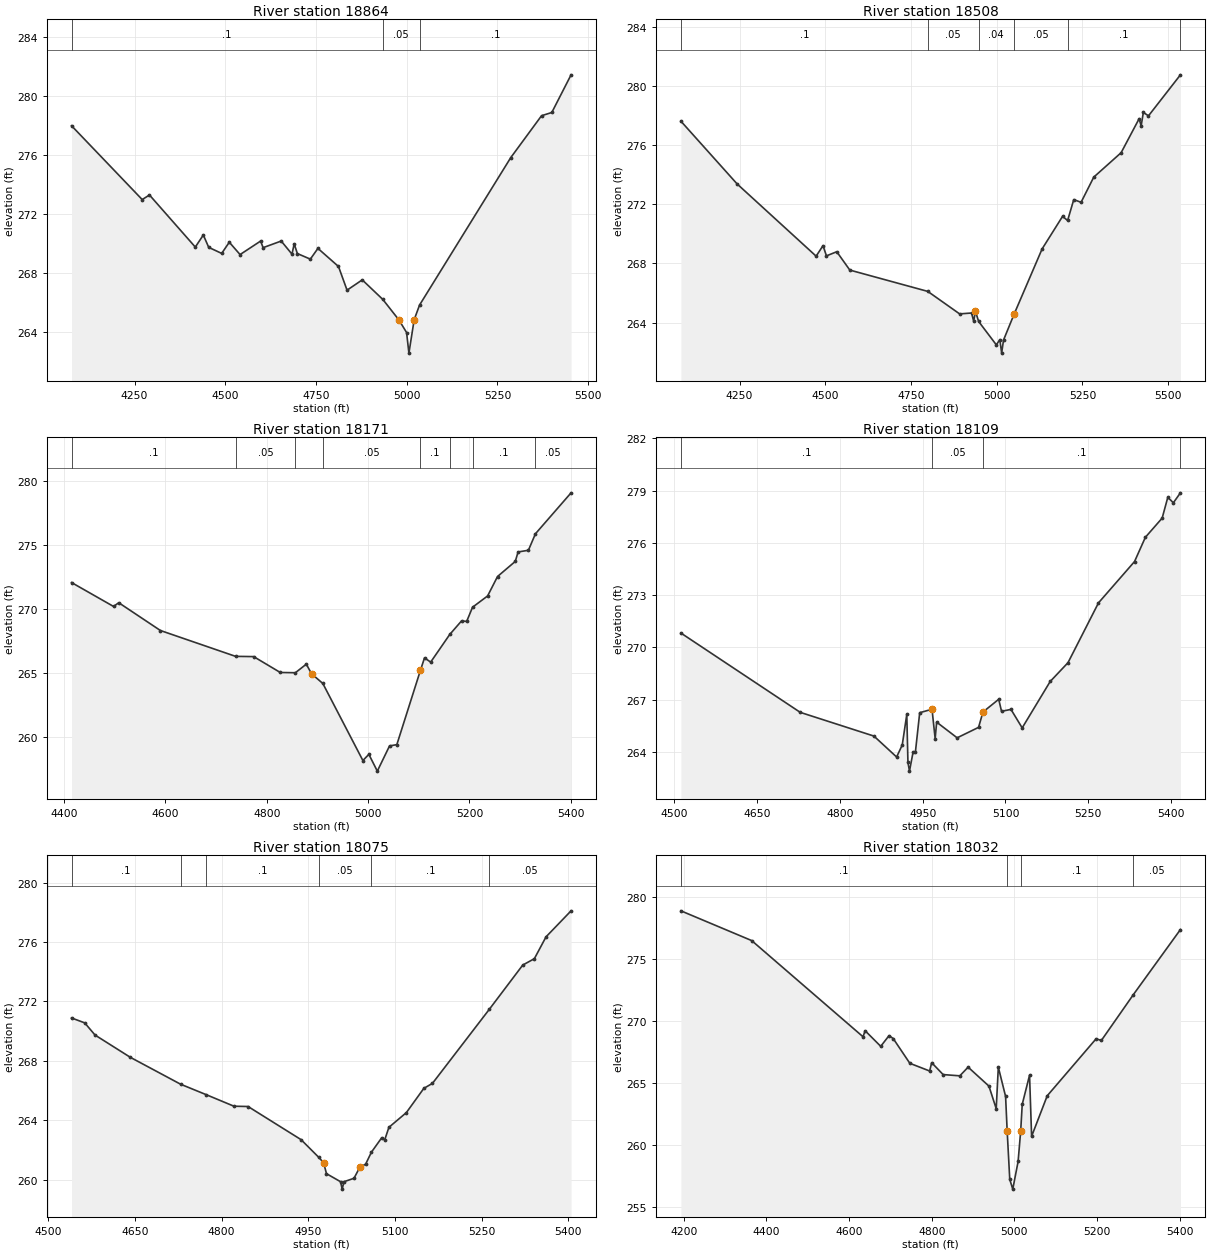
Type RM Length L Ch R = 1 ,18864   ,355,355,355
BEGIN DESCRIPTION:
UNT 028 IN RACR 40.0
END DESCRIPTION:
XS GIS Cut Line= 4
      2258125.73     13224570.74       2258092.3      13224226.1
      2257608.78     13223531.69      2257478.27     13223401.18
#Sta/Elev= 30
  4076.1  277.99  4270.9  272.97    4291  273.28  4417.3  269.74  4439.4  270.56
  4454.3  269.72    4490  269.31    4511  270.07  4540.7  269.23  4597.4  270.15
  4604.2   269.7  4654.1  270.15  4683.8  269.26  4689.9  269.96  4698.6   269.3
  4734.4  268.92  4755.3  269.65    4812  268.42  4835.6  266.81  4877.5  267.51
  4934.2  266.18  4978.8  264.78  4999.7  263.93  5006.1  262.53  5020.6   264.8
  5035.5   265.8  5286.8  275.82  5371.7  278.67    5400  278.89  5453.1  281.45
#Mann= 3 ,-1 , 0
  4076.1      .1       0  4934.2     .05       0  5035.5      .1       0
Bank Sta=4978.8,5020.6
XS Rating Curve= 0 ,0
Exp/Cntr=0.3,0.1

Type RM Length L Ch R = 1 ,18508   ,337,337,337
BEGIN DESCRIPTION:
Mapping XS b088e5c9
END DESCRIPTION:
XS GIS Cut Line= 4
      2258187.46     13224560.43      2258133.45     13223791.45
      2258048.57      13223457.1       2257873.7     13223163.92
#Sta/Elev= 30
  4078.8  277.61  4242.8  273.37  4473.3  268.49  4493.4   269.2  4503.4  268.51
  4533.5  268.79  4571.6  267.55    4799  266.11  4891.9  264.59  4926.6  264.65
  4932.9   264.1    4938  264.77  4947.3  264.08  4998.9   262.5  5009.2  262.85
  5014.5  261.94  5019.9  262.82  5050.4  264.55  5132.5  268.98  5192.2  271.18
  5206.9   270.9  5224.8  272.31  5246.2  272.13  5283.2  273.83    5363  275.48
  5415.6  277.78  5421.4  277.29  5427.8   278.2  5442.8  277.97    5536  280.74
#Mann= 6 ,-1 , 0
  4078.8      .1       0    4799     .05       0  4947.3     .04       0
  5050.4     .05       0  5206.9      .1       0    5536     .05       0
Bank Sta=4938,5050.4
XS Rating Curve= 0 ,0
Exp/Cntr=0.3,0.1

Type RM Length L Ch R = 1 ,18171   ,62,62,62
BEGIN DESCRIPTION:
Mapping XS 9fc2041e
END DESCRIPTION:
XS GIS Cut Line= 3
      2258268.25     13224327.46      2258408.88     13223738.89
      2258343.78     13223363.94
#Sta/Elev= 30
  4414.9  272.07  4497.8   270.2  4508.1  270.49  4590.3  268.32  4738.6   266.3
  4774.3  266.28  4826.8  265.04  4856.6  265.02  4878.2  265.69  4888.5  264.94
  4910.8  264.18  4989.8  258.16  5001.6  258.64  5018.3  257.33  5042.4   259.3
  5056.8   259.4  5103.3   265.2  5111.4  266.18  5123.6  265.85  5161.2  268.01
  5184.5  269.07  5194.6  269.03  5206.2  270.14  5235.9  271.02  5255.5  272.54
  5290.5  273.72  5296.1  274.46  5316.4  274.59  5330.3  275.88  5400.6  279.08
#Mann= 8 ,-1 , 0
  4414.9      .1       0  4738.6     .05       0  4856.6      .1       0
  4910.8     .05       0  5103.3      .1       0  5161.2     .05       0
  5206.2      .1       0  5330.3     .05       0
Bank Sta=4888.5,5103.3
XS Rating Curve= 0 ,0
Exp/Cntr=0.3,0.1

Type RM Length L Ch R = 1 ,18109   ,35,35,35
BEGIN DESCRIPTION:
Mapping XS 96e678c9
END DESCRIPTION:
XS GIS Cut Line= 5
      2258350.29     13224247.57      2258445.54     13223833.64
       2258465.3     13223798.35      2258459.85     13223727.49
      2258398.02     13223364.28
#Sta/Elev= 30
  4512.2  270.83  4728.4  266.28  4861.8  264.92  4902.9  263.72  4913.1  264.41
  4921.3  266.16  4923.4  263.41  4926.2  262.91  4932.7     264  4936.9     264
  4944.7  266.26    4967  266.46  4972.7  264.77  4975.4  265.72  5012.5  264.82
  5051.3  265.42  5059.3   266.3  5087.8  267.03  5092.9  266.34    5110  266.45
  5130.3  265.39    5181  268.05  5213.3  269.13  5268.5  272.56  5333.8  274.93
  5353.4  276.32  5383.8  277.42    5394  278.61  5404.1   278.3  5416.9  278.87
#Mann= 4 ,-1 , 0
  4512.2      .1       0    4967     .05       0  5059.3      .1       0
  5416.9     .05       0
#XS Ineff= 2 ,-1
 4699.32  4947.5  266.01 5104.32 5186.14  266.23
Permanent Ineff=
       T       T
Bank Sta=4967,5059.3
XS Rating Curve= 0 ,0
Exp/Cntr=0.3,0.1

Type RM Length L Ch R = 1 ,18075   ,42,42,42
BEGIN DESCRIPTION:
Mapping XS 7152d1e4
END DESCRIPTION:
XS GIS Cut Line= 3
      2258408.87     13224236.76      2258500.03     13223767.97
      2258454.45     13223383.84
#Sta/Elev= 30
  4540.3  270.89  4563.1  270.56    4581  269.74  4642.1  268.24  4729.1  266.43
  4773.2  265.73  4821.4  264.95  4845.8  264.93  4937.5   262.7  4968.1  261.51
  4976.4  261.15  4981.5  260.41  5005.8  259.87  5008.6  259.37  5011.8  259.87
  5029.1   260.1  5039.1  260.84  5049.2  261.05  5059.3  261.86  5077.1  262.83
  5082.2  262.68  5089.5  263.53  5119.7  264.52  5149.9  266.15  5164.9  266.49
    5263  271.46  5321.1  274.45  5341.2  274.88  5361.4  276.35  5404.7   278.1
#Mann= 6 ,-1 , 0
  4540.3      .1       0  4729.1     .05       0  4773.2      .1       0
  4968.1     .05       0  5059.3      .1       0    5263     .05       0
Bank Sta=4976.4,5039.1
XS Rating Curve= 0 ,0
Exp/Cntr=0.3,0.1

Type RM Length L Ch R = 1 ,18032   ,228,228,228
BEGIN DESCRIPTION:
UNT 028 IN RACR 39.0
END DESCRIPTION:
XS GIS Cut Line= 3
      2258437.71      13224596.9      2258537.72     13223796.85
      2258487.72     13223396.84
#Sta/Elev= 30
  4192.8   278.9  4364.2   276.5  4633.8  268.74  4638.8  269.23  4676.6  267.97
  4696.7  268.83  4706.8   268.6  4747.1   266.6    4795  265.98    4800  266.65
  4827.7  265.69  4868.1  265.59  4888.2  266.29  4938.6  264.76  4956.2  262.94
  4961.3  266.29  4978.9  263.93 4982.73  261.14    4989  257.23  4996.3  256.45
  5009.2  258.68 5015.45  261.14  5019.2  263.29  5036.9  265.64  5041.9  260.71
  5079.7  263.98  5198.1  268.58  5210.7  268.44    5288  272.13  5402.2  277.39
#Mann= 4 ,-1 , 0
  4192.8      .1       0 4982.73     .05       0 5015.45      .1       0
    5288     .05       0
Bank Sta=4982.73,5015.45
XS Rating Curve= 0 ,0
Exp/Cntr=0.3,0.1

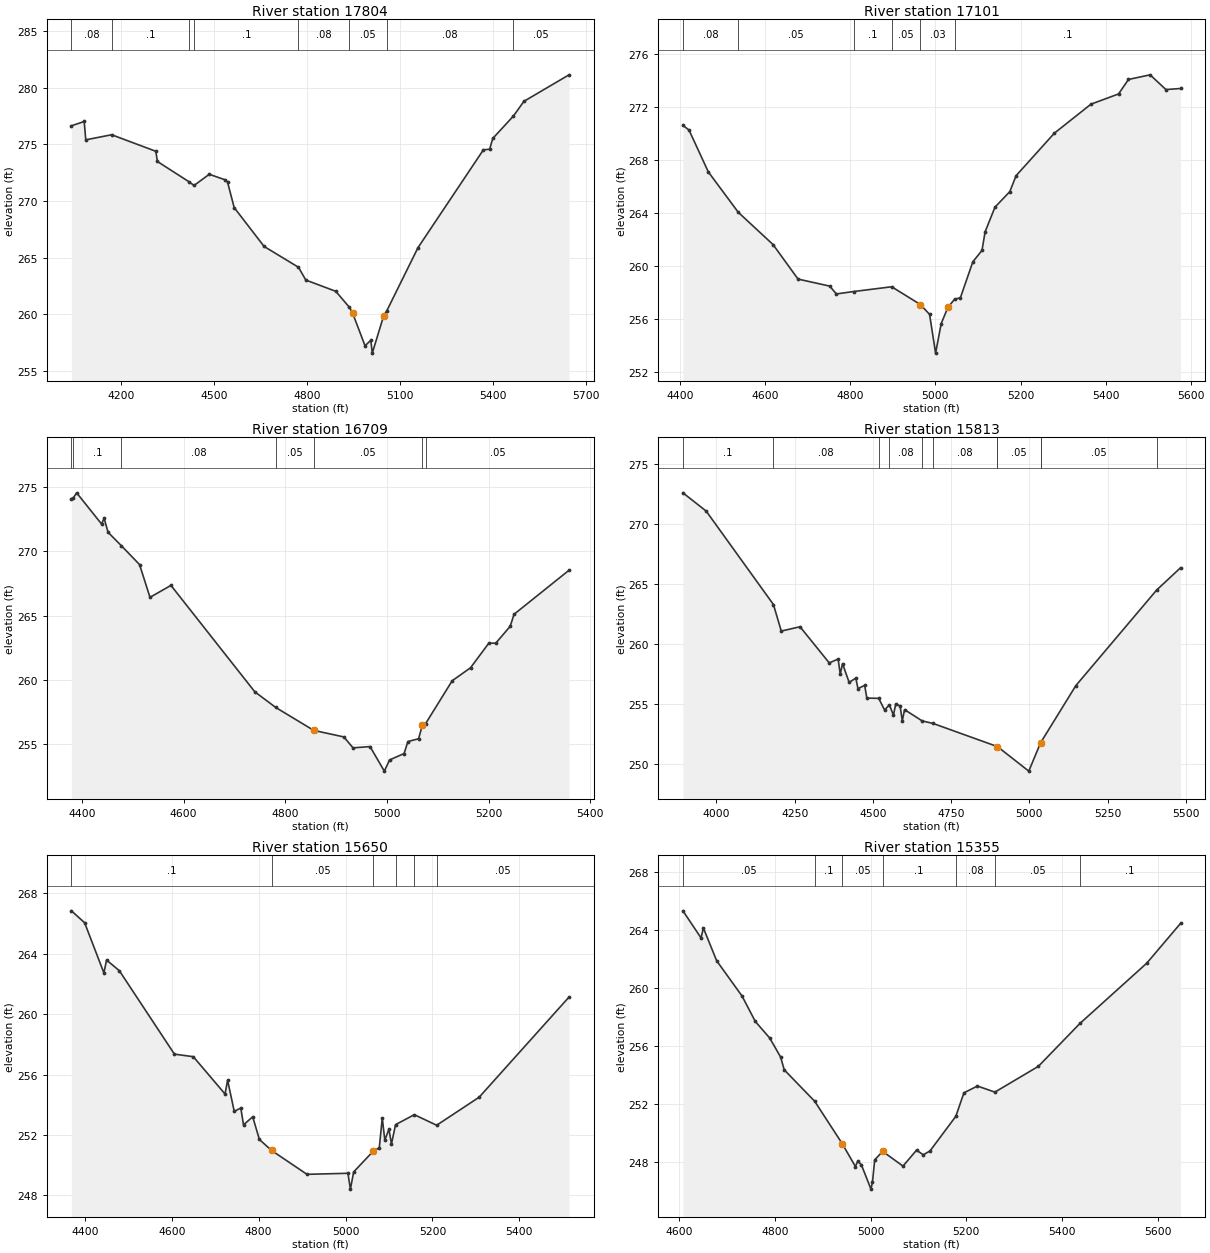
Type RM Length L Ch R = 1 ,17804   ,703,703,703
BEGIN DESCRIPTION:
UNT 028 IN RACR 38.0
END DESCRIPTION:
XS GIS Cut Line= 2
      2258678.84     13224789.27      2258817.74       13223192.
#Sta/Elev= 30
  4041.1  276.65  4082.3  277.03  4087.3  275.41  4170.7  275.86  4313.1   274.4
  4318.1   273.5  4420.4   271.7  4436.2  271.38  4485.2  272.37  4535.4  271.89
    4544  271.69  4565.5  269.43  4661.9     266  4772.7  264.16  4796.4  263.03
  4892.8  262.04  4936.9  260.62  4946.9  260.13  4987.1  257.23  5005.7  257.71
  5010.5  256.58  5047.3  259.89  5057.3  260.32  5157.7  265.89  5368.5  274.53
  5388.6  274.58  5398.6  275.53  5465.2  277.51    5499  278.81  5644.4  281.15
#Mann= 8 ,-1 , 0
  4041.1     .08       0  4170.7      .1       0  4420.4     .08       0
  4436.2      .1       0  4772.7     .08       0  4936.9     .05       0
  5057.3     .08       0  5465.2     .05       0
Bank Sta=4946.9,5047.3
XS Rating Curve= 0 ,0
Exp/Cntr=0.3,0.1

Type RM Length L Ch R = 1 ,17101   ,392,392,392
BEGIN DESCRIPTION:
UNT 028 IN RACR 37.0
END DESCRIPTION:
XS GIS Cut Line= 2
      2258866.44     13224436.77      2259873.05     13223844.94
#Sta/Elev= 30
  4407.5  270.59  4421.8  270.24    4467  267.09  4537.4  264.04    4619  261.61
  4677.6  259.01  4751.9  258.48  4767.6  257.89  4807.8  258.07  4897.4  258.43
  4964.8  257.09  4986.3  256.35  5000.4  253.43  5013.6  255.66  5029.2  256.87
  5044.9  257.49  5058.6   257.6  5087.8  260.31  5109.3  261.17  5116.6  262.57
  5139.8  264.43  5174.6   265.6  5189.3   266.8    5279     270  5365.1  272.19
  5429.8  272.96    5453  274.05  5503.8   274.4  5540.9  273.29  5575.2  273.37
#Mann= 6 ,-1 , 0
  4407.5     .08       0  4537.4     .05       0  4807.8      .1       0
  4897.4     .05       0  4964.8     .03       0  5044.9      .1       0
Bank Sta=4964.8,5029.2
XS Rating Curve= 0 ,0
Exp/Cntr=0.3,0.1

Type RM Length L Ch R = 1 ,16709   ,896,896,896
BEGIN DESCRIPTION:
UNT 028 IN RACR 36.0
END DESCRIPTION:
XS GIS Cut Line= 3
      2258837.74     13224646.85      2259437.72     13224496.85
      2259737.72     13224296.85
#Sta/Elev= 30
  4379.3  274.09  4383.3  274.18  4389.6  274.56  4438.5  272.14  4443.7  272.57
  4451.4  271.49  4477.7  270.44  4513.3  268.98  4533.9  266.43  4575.1  267.36
  4740.1  259.08  4781.4  257.86    4856  256.08  4915.3  255.57  4933.3  254.72
  4966.8  254.82  4994.9  252.91  5005.3  253.78  5033.8  254.28  5041.3  255.21
  5062.3  255.43  5069.9   256.5  5076.2  256.61  5128.4  259.94  5164.5  260.95
  5200.6  262.87  5214.1  262.86  5242.6  264.18  5250.1  265.11  5358.3  268.54
#Mann= 7 ,-1 , 0
  4379.3     .08       0  4383.3      .1       0  4477.7     .08       0
  4781.4     .05       0    4856     .05       0  5069.9      .1       0
  5076.2     .05       0
Bank Sta=4856,5069.9
XS Rating Curve= 0 ,0
Exp/Cntr=0.3,0.1

Type RM Length L Ch R = 1 ,15813   ,163,163,163
BEGIN DESCRIPTION:
UNT 028 IN RACR 35.0
END DESCRIPTION:
XS GIS Cut Line= 5
      2258873.44     13224807.99      2259316.17      13224813.2
      2259732.84     13225255.91      2259930.76      13225250.7
      2260133.28     13224975.48
#Sta/Elev= 30
  3892.7  272.57    3967  271.05    4182  263.27    4207  261.06    4267  261.42
  4360.3  258.41  4388.7  258.73  4395.5  257.48  4402.8  258.35  4423.9  256.79
  4445.3  257.14  4452.2  256.27  4473.6  256.54  4480.5  255.48  4518.5  255.46
  4537.2  254.49  4552.5  254.92  4565.5  254.06  4572.8  254.98  4586.9  254.83
  4593.8  253.58  4601.1  254.52  4657.4  253.58  4692.1  253.37  4898.1  251.44
  4998.1   249.4  5035.8  251.76  5148.5  256.52  5406.9  264.48  5483.1  266.33
#Mann= 11 ,-1 , 0
  3892.7      .1       0    4182     .08       0  4518.5     .05       0
  4552.5     .08       0  4657.4     .05       0  4692.1     .08       0
  4898.1     .05       0  4898.1     .05       0  5035.8     .08       0
  5035.8     .05       0  5406.9      .1       0
Bank Sta=4898.1,5035.8
XS Rating Curve= 0 ,0
Exp/Cntr=0.3,0.1

Type RM Length L Ch R = 1 ,15650   ,295,295,295
BEGIN DESCRIPTION:
Mapping XS f868475c
END DESCRIPTION:
XS GIS Cut Line= 4
      2259255.24      13225347.6      2259450.59     13225208.68
      2259928.02     13225508.16      2260149.39     13225247.73
#Sta/Elev= 30
  4369.2  266.84  4399.6  266.05  4443.9  262.73  4450.1  263.58  4479.6  262.87
  4606.2  257.35  4649.7  257.18  4722.7  254.71  4728.6  255.62  4743.9  253.56
    4759  253.78  4765.2  252.67  4786.4   253.2  4801.7   251.7  4829.8  250.97
  4911.3  249.39  5005.5  249.46  5011.2  248.41  5018.7  249.55  5063.3  250.91
  5077.7  251.15  5084.5  253.12  5090.4  251.65  5099.8  252.38  5105.7   251.4
  5115.1  252.68  5158.3  253.34  5209.7  252.64  5307.6   254.5  5514.3  261.13
#Mann= 6 ,-1 , 0
  4369.2      .1       0  4829.8     .05       0  5063.3     .08       0
  5115.1      .1       0  5158.3     .08       0  5209.7     .05       0
Bank Sta=4829.8,5063.3
XS Rating Curve= 0 ,0
Exp/Cntr=0.3,0.1

Type RM Length L Ch R = 1 ,15355   ,408,408,408
BEGIN DESCRIPTION:
UNT 028 IN RACR 33.0
END DESCRIPTION:
XS GIS Cut Line= 3
      2259437.73     13225746.85      2259837.72     13225696.85
      2260287.72     13225246.85
#Sta/Elev= 30
  4607.9  265.35  4645.7  263.48  4650.7  264.16  4678.4   261.9  4731.3  259.47
  4759.1  257.71  4789.3  256.56    4812  255.25  4819.5  254.37  4883.1   252.2
  4940.5  249.28  4968.2  247.69  4973.2  248.07  4980.8   247.8  5000.7  246.13
  5003.9  246.63  5008.5  248.15  5025.1  248.74  5067.6  247.72  5095.9  248.82
    5110   248.5  5124.1  248.77    5178  251.16  5194.9  252.78  5223.1  253.25
  5259.6  252.83  5350.4  254.61  5437.2  257.57  5576.7  261.73  5647.4  264.48
#Mann= 7 ,-1 , 0
  4607.9     .05       0  4883.1      .1       0  4940.5     .05       0
  5025.1      .1       0    5178     .08       0  5259.6     .05       0
  5437.2      .1       0
Bank Sta=4940.5,5025.1
XS Rating Curve= 0 ,0
Exp/Cntr=0.3,0.1

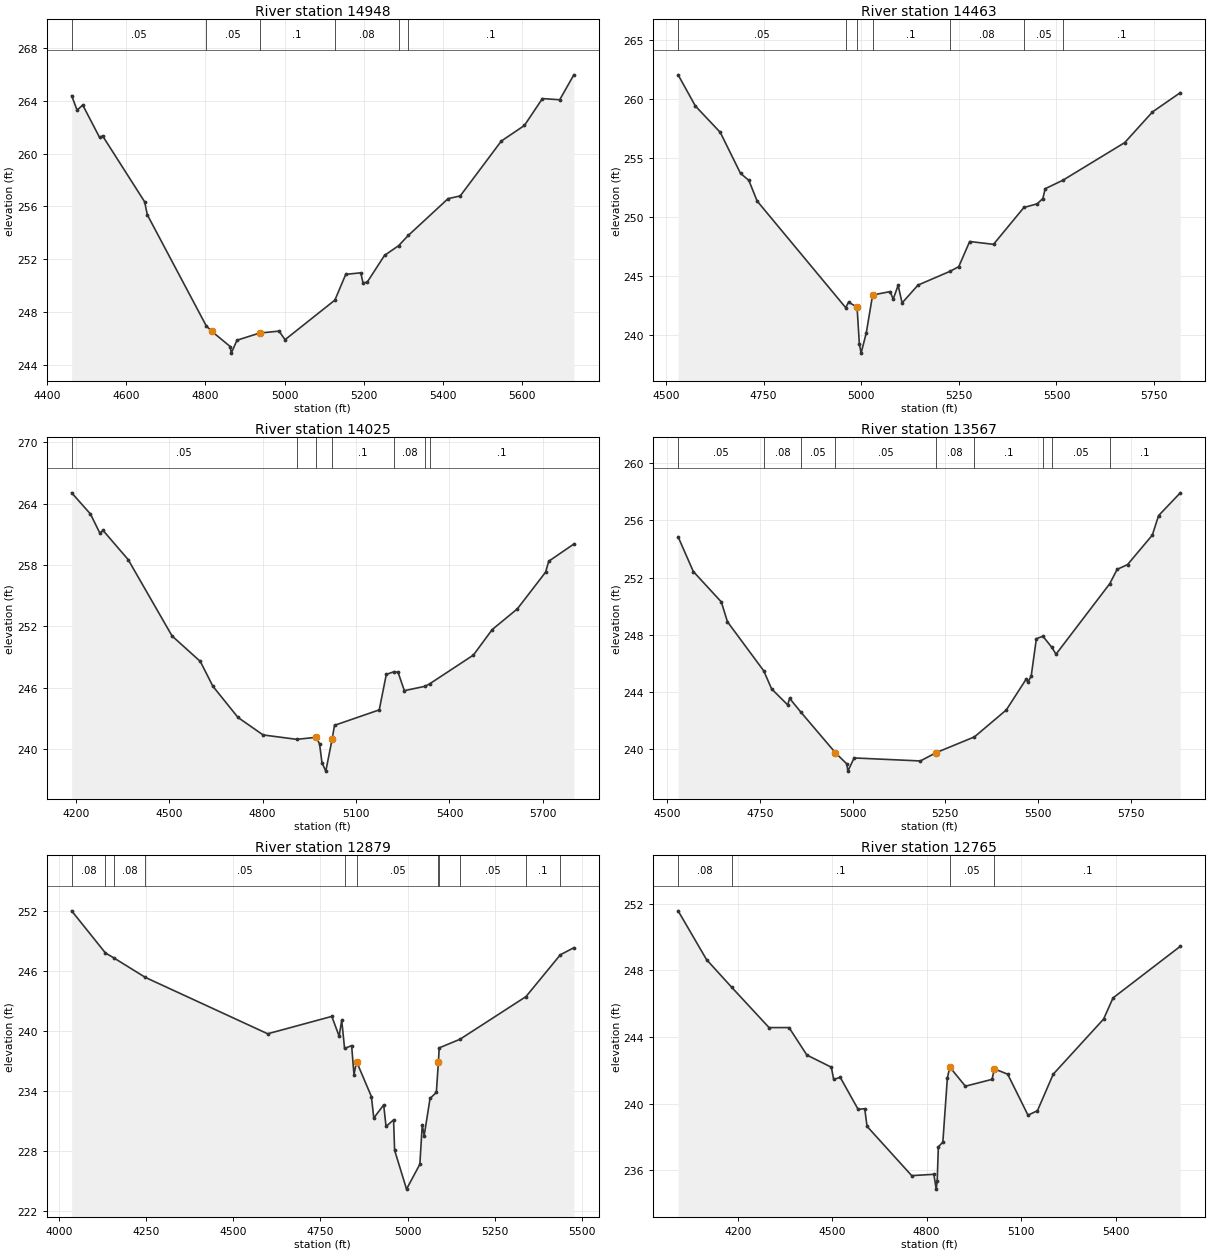
Type RM Length L Ch R = 1 ,14948   ,484,484,484
BEGIN DESCRIPTION:
UNT 028 IN RACR 32.0
END DESCRIPTION:
XS GIS Cut Line= 3
      2259787.71     13226346.86      2260137.72     13225946.85
      2260487.74     13225296.82
#Sta/Elev= 30
  4461.8   264.4  4475.6   263.3  4489.8  263.69  4532.5  261.23  4540.1  261.35
  4646.4  256.35  4653.1  255.37  4802.1  246.95  4816.3  246.53  4862.7  245.38
  4865.4  244.88  4879.9  245.86  4936.8   246.4  4986.2  246.55  5001.4   245.9
  5127.4   248.9  5154.8  250.85  5192.9  250.97  5198.6   250.2  5209.1  250.26
  5252.9  252.29  5288.3  253.02  5312.9   253.8  5413.5  256.59  5444.4   256.8
  5548.2  260.96  5606.6  262.14  5652.1  264.18  5695.9  264.09  5731.6  265.98
#Mann= 6 ,-1 , 0
  4461.8     .05       0  4802.1     .05       0  4936.8      .1       0
  5127.4     .08       0  5288.3     .05       0  5312.9      .1       0
Bank Sta=4816.3,4936.8
XS Rating Curve= 0 ,0
Exp/Cntr=0.3,0.1

Type RM Length L Ch R = 1 ,14463   ,439,439,439
BEGIN DESCRIPTION:
UNT 028 IN RACR 31.0
END DESCRIPTION:
XS GIS Cut Line= 3
      2259987.76     13226546.83      2260387.72     13226296.85
      2260537.72     13225496.85
#Sta/Elev= 30
  4531.4  262.03  4575.6  259.39  4639.3  257.16  4691.1  253.69  4712.4   253.1
  4733.6  251.35  4960.4  242.32  4967.7  242.78  4989.5  242.37  4995.4  239.24
  4999.9  238.47  5013.2   240.2  5029.3  243.39  5074.3  243.68  5081.9  243.03
  5094.6  244.21  5104.8  242.72  5145.5  244.23  5227.1  245.39  5249.8  245.79
  5277.8  247.92  5338.8  247.68  5416.6   250.8  5450.7  251.11  5465.1  251.56
  5471.1  252.39  5516.6  253.11  5674.6  256.29  5745.8  258.89    5817  260.52
#Mann= 7 ,-1 , 0
  4531.4     .05       0  4960.4      .1       0  4989.5     .05       0
  5029.3      .1       0  5227.1     .08       0  5416.6     .05       0
  5516.6      .1       0
Bank Sta=4989.5,5029.3
XS Rating Curve= 0 ,0
Exp/Cntr=0.3,0.1

Type RM Length L Ch R = 1 ,14025   ,457,457,457
BEGIN DESCRIPTION:
UNT 028 IN RACR 30.0
END DESCRIPTION:
XS GIS Cut Line= 3
      2259937.76     13226646.85      2260737.72     13226546.85
      2261537.71     13226446.86
#Sta/Elev= 30
    4187  265.05  4247.4  262.98  4277.7   261.1  4287.7  261.38  4368.4  258.52
  4509.4  251.05  4600.1  248.56  4640.5  246.13  4721.1  243.08  4801.7  241.37
  4909.4  240.94    4973  241.14  4983.1  240.47  4990.7  238.65    5003  237.83
  5023.4  240.97    5031  242.31  5174.6  243.82  5197.3  247.29  5222.8  247.56
  5235.1  247.49  5255.2   245.7    5322  246.13    5336  246.36  5476.9  249.18
  5537.4  251.68    5618   253.7  5708.7  257.29  5718.8  258.36  5799.4  260.04
#Mann= 7 ,-1 , 0
    4187     .05       0  4909.4      .1       0    4973     .05       0
  5023.4      .1       0  5222.8     .08       0    5322     .05       0
    5336      .1       0
Bank Sta=4973,5023.4
XS Rating Curve= 0 ,0
Exp/Cntr=0.3,0.1

Type RM Length L Ch R = 1 ,13567   ,688,688,688
BEGIN DESCRIPTION:
UNT 028 IN RACR 29.0
END DESCRIPTION:
XS GIS Cut Line= 3
      2260237.71     13226846.85      2260687.72     13226946.85
      2261487.71     13226546.86
#Sta/Elev= 30
    4529  254.84    4570  252.42  4645.5   250.3  4662.2  248.91  4760.3  245.48
  4781.3  244.23  4824.8  243.11  4829.9  243.57  4860.2  242.61 4953.64  239.77
  4984.4  238.99  4987.2  238.49    5004  239.41  5182.9   239.2 5224.55  239.77
  5328.8  240.88  5414.8  242.76  5467.9  244.89  5473.5  244.72  5481.9  245.11
  5495.9  247.73  5513.6   247.9  5537.3  247.14    5549  246.65    5694  251.57
  5713.9  252.57  5741.9   252.9  5808.9  254.96  5825.7  256.32  5884.4  257.91
#Mann= 9 ,-1 , 0
    4529     .05       0  4760.3     .08       0  4860.2     .05       0
 4953.64     .05       0 5224.55     .08       0  5328.8      .1       0
  5513.6     .08       0  5537.3     .05       0    5694      .1       0
Bank Sta=4953.64,5224.55
XS Rating Curve= 0 ,0
Exp/Cntr=0.3,0.1

Type RM Length L Ch R = 1 ,12879   ,114,114,114
BEGIN DESCRIPTION:
Mapping XS f00e8b6c
END DESCRIPTION:
XS GIS Cut Line= 5
      2260281.92     13226909.86      2260572.68     13227096.47
      2260963.31     13227526.16      2261067.91     13227578.24
      2261464.08     13227560.94
#Sta/Elev= 30
  4036.8  252.02  4133.7   247.8  4156.9  247.33  4248.1  245.36  4598.8  239.72
  4782.6  241.46  4803.6  239.48    4811  241.08  4819.2  238.25  4839.4  238.54
  4846.1  235.64  4853.6  236.93  4896.1  233.44  4902.9  231.29  4931.3  232.61
    4938  230.45  4959.7  231.11  4962.6  228.07  4996.8  224.18    5035  226.67
  5041.8   230.6  5047.4  229.54  5064.2  233.25  5082.3  233.86 5088.18   236.9
  5090.4  238.31  5149.9  239.17  5339.2  243.44  5437.6  247.62  5476.4  248.33
#Mann= 11 ,-1 , 0
  4036.8     .08       0  4133.7     .05       0  4156.9     .08       0
  4248.1     .05       0  4819.2      .1       0  4853.6     .05       0
 5088.18     .05       0  5090.4      .1       0  5149.9     .05       0
  5339.2      .1       0  5437.6     .05       0
Bank Sta=4853.6,5088.18
XS Rating Curve= 0 ,0
Exp/Cntr=0.3,0.1

Type RM Length L Ch R = 1 ,12765   ,95,95,95
BEGIN DESCRIPTION:
UNT 028 IN RACR 27.0
END DESCRIPTION:
XS GIS Cut Line= 4
      2260273.17     13226943.57      2260767.99     13227400.29
      2261032.75     13227717.13      2261541.33     13227729.04
#Sta/Elev= 30
  4010.6  251.58  4100.9  248.65  4180.3     247  4299.4  244.57  4362.9  244.57
  4419.6  242.92  4497.3  242.19  4504.6  241.46  4525.6  241.58  4582.3  239.66
  4603.3   239.7  4610.7  238.64  4752.5  235.68  4822.9  235.76  4830.3  234.87
  4833.5  235.37  4837.1  237.41  4851.4  237.69  4865.7  241.53 4873.41   242.2
  4922.9  241.05  5007.5  241.46  5015.3  242.09  5057.4  241.77  5121.9  239.31
  5151.9  239.58  5201.9  241.77  5361.9  245.08  5391.9  246.35  5605.6  249.45
#Mann= 4 ,-1 , 0
  4010.6     .08       0  4180.3      .1       0 4873.41     .05       0
  5015.3      .1       0
#XS Ineff= 2 ,-1
 4458.18 4874.43  241.17 5050.34  5605.6  241.81
Permanent Ineff=
       T       T
Bank Sta=4873.41,5015.3
XS Rating Curve= 0 ,0
Exp/Cntr=0.3,0.1