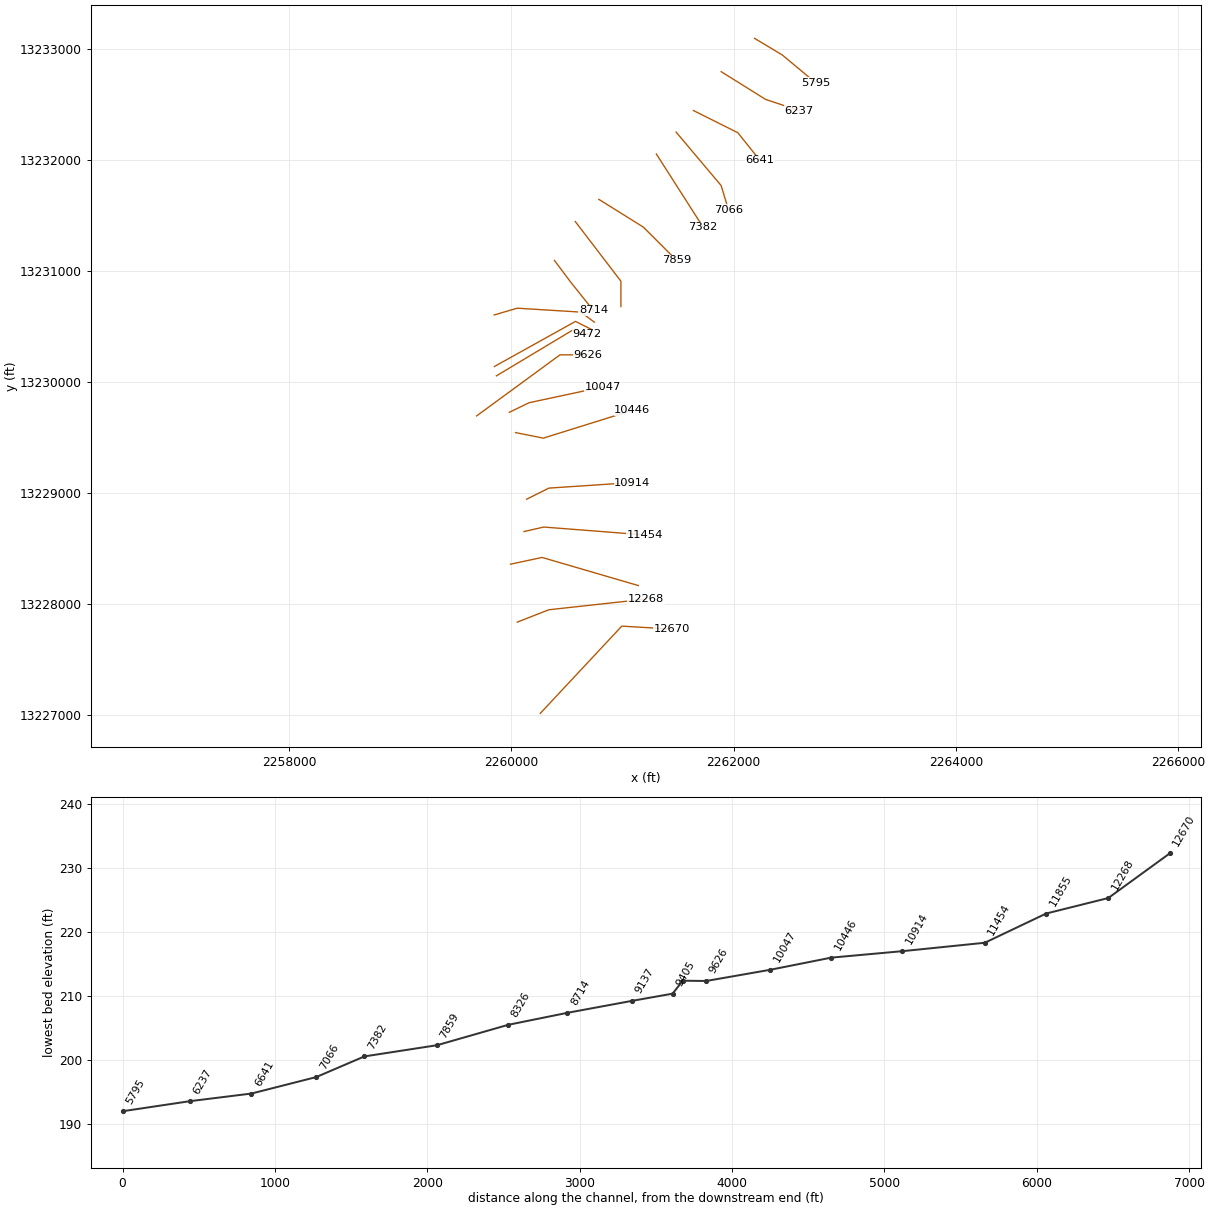
HEC-RAS study UNT 028 IN RACR.prj: UNT 028 IN RACR Base Level Engineering

--- UNT 028 IN RACR.g01 (geometry) --- (continued)

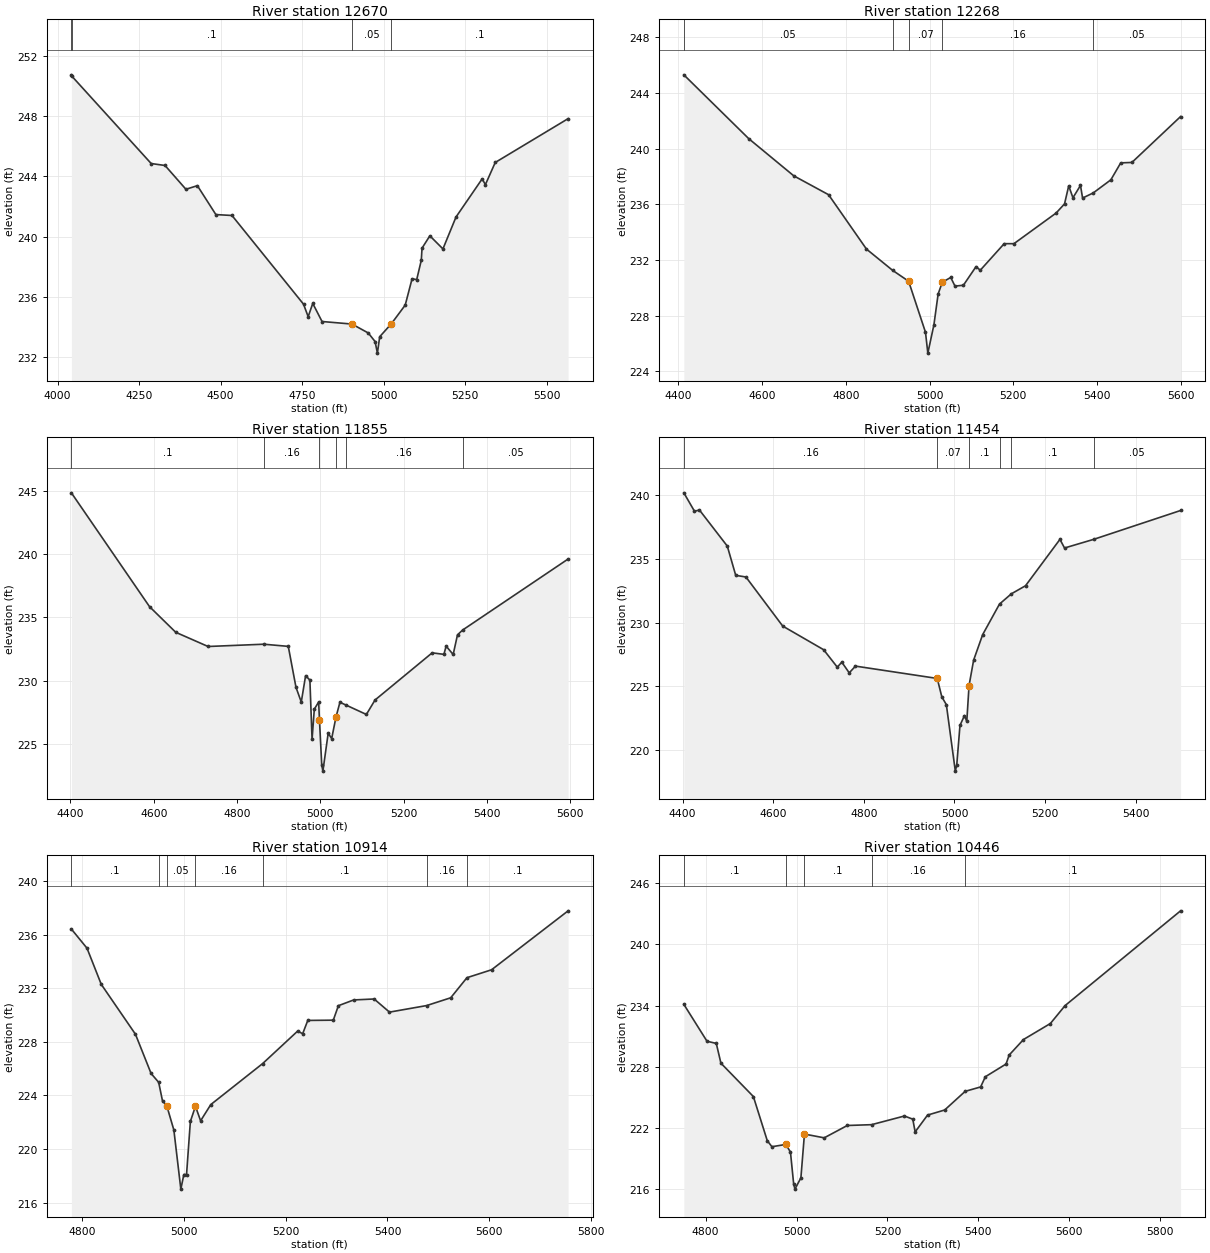
Type RM Length L Ch R = 1 ,12670   ,403,403,403
BEGIN DESCRIPTION:
UNT 028 IN RACR 28.0
END DESCRIPTION:
XS GIS Cut Line= 3
      2260260.21     13227018.38      2260993.69     13227803.94
      2261440.78     13227777.89
#Sta/Elev= 30
  4042.4  250.74  4044.7  250.63    4287  244.85  4329.5  244.72  4393.5  243.14
  4428.6  243.38  4485.3  241.46  4534.7   241.4    4754  235.51  4768.2  234.68
  4782.3  235.56  4810.7  234.36  4902.5  234.19  4952.3   233.6  4973.3  233.03
  4980.4  232.26  4987.5  233.35  5023.2  234.21  5065.7  235.45  5086.7   237.2
  5100.9  237.14    5115  238.43  5117.2  239.23  5141.2  240.05  5181.3  239.18
  5221.4   241.3  5301.5  243.83  5311.5  243.45  5341.6  244.92    5565  247.83
#Mann= 4 ,-1 , 0
  4042.4     .08       0  4044.7      .1       0  4902.5     .05       0
  5023.2      .1       0
Bank Sta=4902.5,5023.2
XS Rating Curve= 0 ,0
Exp/Cntr=0.3,0.1

Type RM Length L Ch R = 1 ,12268   ,408,408,408
BEGIN DESCRIPTION:
UNT 028 IN RACR 26.0
END DESCRIPTION:
XS GIS Cut Line= 3
      2260053.48     13227839.97      2260337.15     13227951.42
       2261213.2     13228047.63
#Sta/Elev= 30
  4413.2  245.31  4568.2  240.72  4675.6  238.05  4758.8  236.69  4849.3  232.78
  4911.8  231.25  4949.9  230.47  4990.2   226.8  4995.8   225.3  5010.3  227.33
  5020.4  229.55  5030.4   230.4  5050.5  230.74  5060.6  230.12  5080.7  230.18
  5110.9  231.52    5121  231.26  5178.1  233.17  5201.4  233.17    5302  235.37
  5322.2  236.03  5332.2  237.33  5342.3  236.47  5360.3  237.36  5365.3  236.45
  5390.8  236.82  5432.8  237.76  5456.4  238.98  5483.1  239.01  5599.3  242.31
#Mann= 5 ,-1 , 0
  4413.2     .05       0  4911.8     .16       0  4949.9     .07       0
  5030.4     .16       0  5390.8     .05       0
Bank Sta=4949.9,5030.4
XS Rating Curve= 0 ,0
Exp/Cntr=0.3,0.1

Type RM Length L Ch R = 1 ,11855   ,403,403,403
BEGIN DESCRIPTION:
UNT 028 IN RACR 25.0
END DESCRIPTION:
XS GIS Cut Line= 3
      2259992.66     13228361.79      2260276.36     13228422.58
      2261142.64     13228169.28
#Sta/Elev= 30
  4402.3  244.83    4590  235.85  4652.9  233.83  4730.5  232.71  4864.4  232.89
  4923.1  232.72  4941.6  229.49  4954.3  228.33  4964.7  230.41    4975  230.06
  4980.2  225.39  4985.6  227.77    4996  228.33 4997.95  226.94  5003.4  223.38
  5006.2  222.88  5018.9  225.87  5027.3  225.45  5037.7  227.15  5047.1  228.31
  5061.7  228.09  5110.6  227.35  5131.4  228.49  5268.6  232.21  5296.8  232.09
  5302.1  232.74    5319  232.08  5329.4  233.63  5341.8  234.01    5595  239.61
#Mann= 6 ,-1 , 0
  4402.3      .1       0  4864.4     .16       0 4997.95     .07       0
  5037.7     .16       0  5061.7     .16       0  5341.8     .05       0
#XS Ineff= 2 , 0
                         5046.77          228.26
Permanent Ineff=
       F       F
Bank Sta=4997.95,5037.7
XS Rating Curve= 0 ,0
Exp/Cntr=0.3,0.1

Type RM Length L Ch R = 1 ,11454   ,540,540,540
BEGIN DESCRIPTION:
UNT 028 IN RACR 24.0
END DESCRIPTION:
XS GIS Cut Line= 3
      2260114.21     13228655.62      2260291.56     13228696.16
      2261203.08     13228625.26
#Sta/Elev= 30
  4402.8  240.21  4426.3  238.76  4437.2  238.86  4498.7  236.02  4517.3  233.72
  4539.8  233.59    4621  229.73  4711.3  227.87  4741.4   226.5  4751.4  226.89
  4767.8  226.05  4781.5  226.58    4962  225.61  4972.1  224.16  4982.1  223.55
  5001.9  218.32  5005.1  218.82  5012.2  221.92  5022.1  222.69  5027.2  222.23
  5032.2  225.05  5042.3  227.05  5062.3  229.06  5099.4  231.46  5125.7  232.27
  5156.8   232.9  5232.8  236.55  5242.9  235.87  5307.2  236.55    5499  238.82
#Mann= 6 ,-1 , 0
  4402.8     .16       0    4962     .07       0  5032.2      .1       0
  5099.4     .05       0  5125.7      .1       0  5307.2     .05       0
Bank Sta=4962,5032.2
XS Rating Curve= 0 ,0
Exp/Cntr=0.3,0.1

Type RM Length L Ch R = 1 ,10914   ,468,468,468
BEGIN DESCRIPTION:
UNT 028 IN RACR 23.0
END DESCRIPTION:
XS GIS Cut Line= 3
      2260137.74     13228946.87      2260337.72     13229046.85
      2261087.67     13229096.85
#Sta/Elev= 30
  4779.5  236.42  4810.2  234.99  4838.2  232.29  4905.3  228.57    4936  225.64
  4950.9  224.98  4958.4  223.59  4966.7  223.24  4980.7  221.42  4994.4  217.01
  5000.3   218.1  5005.6   218.1  5013.1  222.06  5023.1  223.19  5033.2  222.11
  5053.2  223.32    5155  226.38  5223.6   228.8  5233.6  228.61  5243.6   229.6
  5293.7  229.62  5303.7   230.7  5333.8  231.13  5373.9   231.2    5404  230.22
    5477  230.71  5524.2  231.29  5556.1  232.79  5604.4  233.38  5754.7  237.78
#Mann= 7 ,-1 , 0
  4779.5      .1       0  4950.9     .16       0  4966.7     .05       0
  5023.1     .16       0    5155      .1       0    5477     .16       0
  5556.1      .1       0
Bank Sta=4966.7,5023.1
XS Rating Curve= 0 ,0
Exp/Cntr=0.3,0.1

Type RM Length L Ch R = 1 ,10446   ,399,399,399
BEGIN DESCRIPTION:
UNT 028 IN RACR 22.0
END DESCRIPTION:
XS GIS Cut Line= 3
      2260037.72     13229546.85      2260287.72     13229496.85
      2261087.72     13229746.85
#Sta/Elev= 30
    4752  234.12    4803   230.5  4823.4  230.29  4833.6  228.35    4905  225.08
  4935.6  220.75  4945.8  220.16  4976.4  220.38  4986.6  219.64  4993.7   216.5
  4996.5     216  5009.6  217.11  5017.4   221.4  5060.9  221.03  5111.7  222.24
  5165.1  222.32  5237.4  223.17  5255.8  222.86    5261  221.61  5288.3  223.26
    5326  223.76  5371.1  225.59  5405.1  226.02  5415.5  227.02  5461.1  228.27
  5467.9  229.15  5499.4  230.67  5558.6  232.24    5591     234  5845.1  243.29
#Mann= 5 ,-1 , 0
    4752      .1       0  4976.4     .05       0  5017.4      .1       0
  5165.1     .16       0  5371.1      .1       0
Bank Sta=4976.4,5017.4
XS Rating Curve= 0 ,0
Exp/Cntr=0.3,0.1

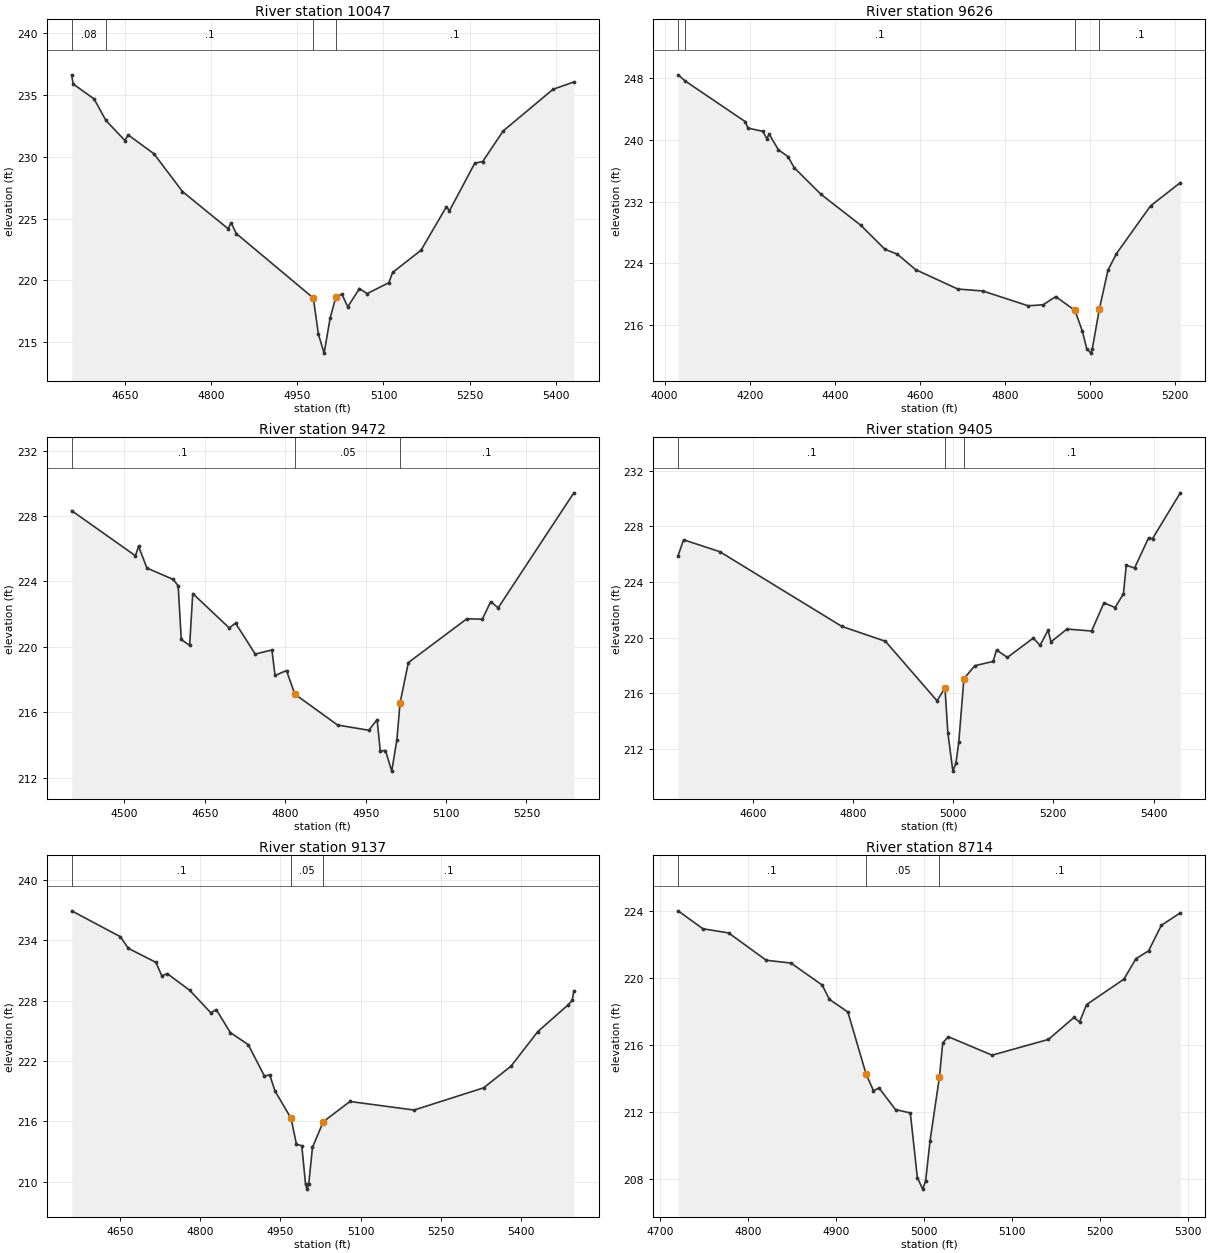
Type RM Length L Ch R = 1 ,10047   ,421,421,421
BEGIN DESCRIPTION:
UNT 028 IN RACR 21.0
END DESCRIPTION:
XS GIS Cut Line= 3
      2259982.51     13229729.68      2260159.83      13229815.8
      2260823.12     13229957.57
#Sta/Elev= 30
  4556.4  236.64    4559   235.9  4595.5  234.69  4616.1  232.95  4649.3  231.32
  4654.8  231.78  4699.9  230.25  4749.6  227.19  4829.2  224.18  4834.3  224.67
  4843.4  223.79  4977.7  218.57  4986.6  215.63  4996.5  214.11    5007  216.95
  5016.9  218.64  5027.5  218.88  5037.7  217.86  5058.1  219.34  5071.5  218.93
  5109.3  219.81  5115.9  220.64  5165.4  222.44  5209.7  225.96  5214.9  225.63
  5259.2  229.49  5272.9  229.62  5308.7   232.1  5395.6  235.47  5431.8  236.06
#Mann= 4 ,-1 , 0
  4556.4     .08       0  4616.1      .1       0  4977.7     .05       0
  5016.9      .1       0
Bank Sta=4977.7,5016.9
XS Rating Curve= 0 ,0
Exp/Cntr=0.3,0.1

Type RM Length L Ch R = 1 ,9626    ,154,154,154
BEGIN DESCRIPTION:
UNT 028 IN RACR 20.0
END DESCRIPTION:
XS GIS Cut Line= 3
      2259687.74     13229696.87      2260437.72     13230246.85
      2260687.69     13230246.85
#Sta/Elev= 30
  4031.7  248.45  4048.1  247.66  4189.5  242.38  4195.7  241.54  4231.2  241.12
  4239.7  240.19  4245.9  240.74  4267.3  238.73  4289.8  237.85  4304.5  236.41
  4367.1  232.97  4461.2  228.93  4517.6  225.83  4546.9  225.19  4589.7  223.19
  4688.9  220.67  4747.5  220.42  4854.1   218.5  4889.6  218.63  4918.9  219.69
  4964.2   217.9  4981.7  215.18  4991.7  212.96  5001.5  212.36  5004.7  212.86
  5021.7  218.13  5041.7  223.11  5061.7  225.27  5141.7  231.45  5211.7  234.47
#Mann= 4 ,-1 , 0
  4031.7     .08       0  4048.1      .1       0  4964.2     .05       0
  5021.7      .1       0
Bank Sta=4964.2,5021.7
XS Rating Curve= 0 ,0
Exp/Cntr=0.3,0.1

Type RM Length L Ch R = 1 ,9472    ,67,67,67
BEGIN DESCRIPTION:
Mapping XS 48244ee1
END DESCRIPTION:
XS GIS Cut Line= 3
      2259865.63     13230057.62      2260555.76     13230472.12
       2260681.6     13230433.07
#Sta/Elev= 30
  4401.6  228.33  4520.6  225.57  4526.4  226.15    4542  224.82  4590.7  224.13
  4600.3  223.74  4606.1  220.45  4621.7  220.09  4627.5  223.26  4695.5  221.16
  4707.3  221.45  4744.1  219.56  4775.2  219.81    4781  218.25  4802.4  218.55
  4817.9  217.11  4897.6  215.22  4955.9   214.9  4971.4  215.55  4977.3  213.64
    4987  213.66  4998.7   212.4  5008.3  214.32  5014.2  216.57  5029.7  219.04
  5138.9  221.72  5167.7  221.69  5183.2  222.76  5197.3  222.39  5338.4  229.42
#Mann= 3 , 0 , 0
  4401.6      .1       0  4817.9     .05       0  5014.2      .1       0
Bank Sta=4817.9,5014.2
XS Rating Curve= 0 ,0
Exp/Cntr=0.3,0.1

Type RM Length L Ch R = 1 ,9405    ,268,268,268
BEGIN DESCRIPTION:
UNT 028 IN RACR 19.0
END DESCRIPTION:
XS GIS Cut Line= 3
      2259848.27     13230142.25      2260577.46     13230548.08
      2260727.18     13230472.13
#Sta/Elev= 30
  4451.1   225.9  4461.9  227.04  4534.4  226.18    4778   220.8  4864.9  219.73
  4967.8  215.45  4983.8  216.36  4989.5  213.15  4999.5  210.38  5005.5  210.93
  5011.3  212.45  5021.5  217.03  5043.2  217.97  5079.9  218.28  5086.7   219.1
  5108.4  218.57    5160  219.96  5173.6  219.44  5189.6  220.53  5195.3  219.69
  5227.3  220.61  5276.5  220.47  5301.1   222.5  5323.3  222.16    5340  223.15
  5345.6   225.2  5362.2  225.01  5390.1  227.17    5398  227.12  5453.5  230.42
#Mann= 3 , 0 , 0
  4451.1      .1       0  4983.8     .05       0  5021.5      .1       0
Bank Sta=4983.8,5021.5
XS Rating Curve= 0 ,0
Exp/Cntr=0.3,0.1

Type RM Length L Ch R = 1 ,9137    ,423,423,423
BEGIN DESCRIPTION:
Mapping XS bbae23ad
END DESCRIPTION:
XS GIS Cut Line= 4
      2259845.76     13230606.15      2260053.44     13230666.94
      2260625.93     13230631.47       2260746.5     13230541.04
#Sta/Elev= 30
  4558.9  236.94    4650  234.37  4665.1  233.21  4716.8  231.81  4727.7  230.48
  4738.1  230.69  4779.9  229.04  4819.7  226.79  4829.7  227.12  4856.1  224.83
  4889.8  223.62  4919.9  220.51  4929.9  220.62  4939.9  219.01  4969.9   216.3
    4980  213.71    4990  213.57    4997  209.75  4999.8  209.25    5003  209.75
    5010   213.4  5030.1  215.95  5080.2  217.97  5200.4  217.12  5330.6  219.33
    5382  221.49    5432  224.92  5488.6  227.57  5496.6  228.03  5499.6  228.99
#Mann= 3 , 0 , 0
  4558.9      .1       0  4969.9     .05       0  5030.1      .1       0
Bank Sta=4969.9,5030.1
XS Rating Curve= 0 ,0
Exp/Cntr=0.3,0.1

Type RM Length L Ch R = 1 ,8714    ,388,388,388
BEGIN DESCRIPTION:
UNT 028 IN RACR 18.0
END DESCRIPTION:
XS GIS Cut Line= 3
      2260387.74     13231096.82      2260537.72     13230896.85
      2260737.71     13230646.87
#Sta/Elev= 30
  4720.7  224.01  4748.8  222.94    4778  222.69  4820.7  221.06  4848.8  220.89
  4884.2  219.58  4892.5  218.72  4913.4  217.97  4934.2  214.24  4942.5  213.27
  4948.8  213.43  4967.5  212.14  4984.3  211.94  4992.3  208.07  4998.4  207.39
  5001.7  207.89  5006.7  210.28 5017.39   214.1  5021.1  216.13  5027.5  216.49
  5077.1  215.39  5141.1  216.33    5170  217.64  5176.4  217.37  5184.4  218.41
  5226.8  219.93  5240.4  221.15  5254.8  221.62  5269.2  223.14  5290.8  223.89
#Mann= 3 , 0 , 0
  4720.7      .1       0  4934.2     .05       0 5017.39      .1       0
Bank Sta=4934.2,5017.39
XS Rating Curve= 0 ,0
Exp/Cntr=0.3,0.1

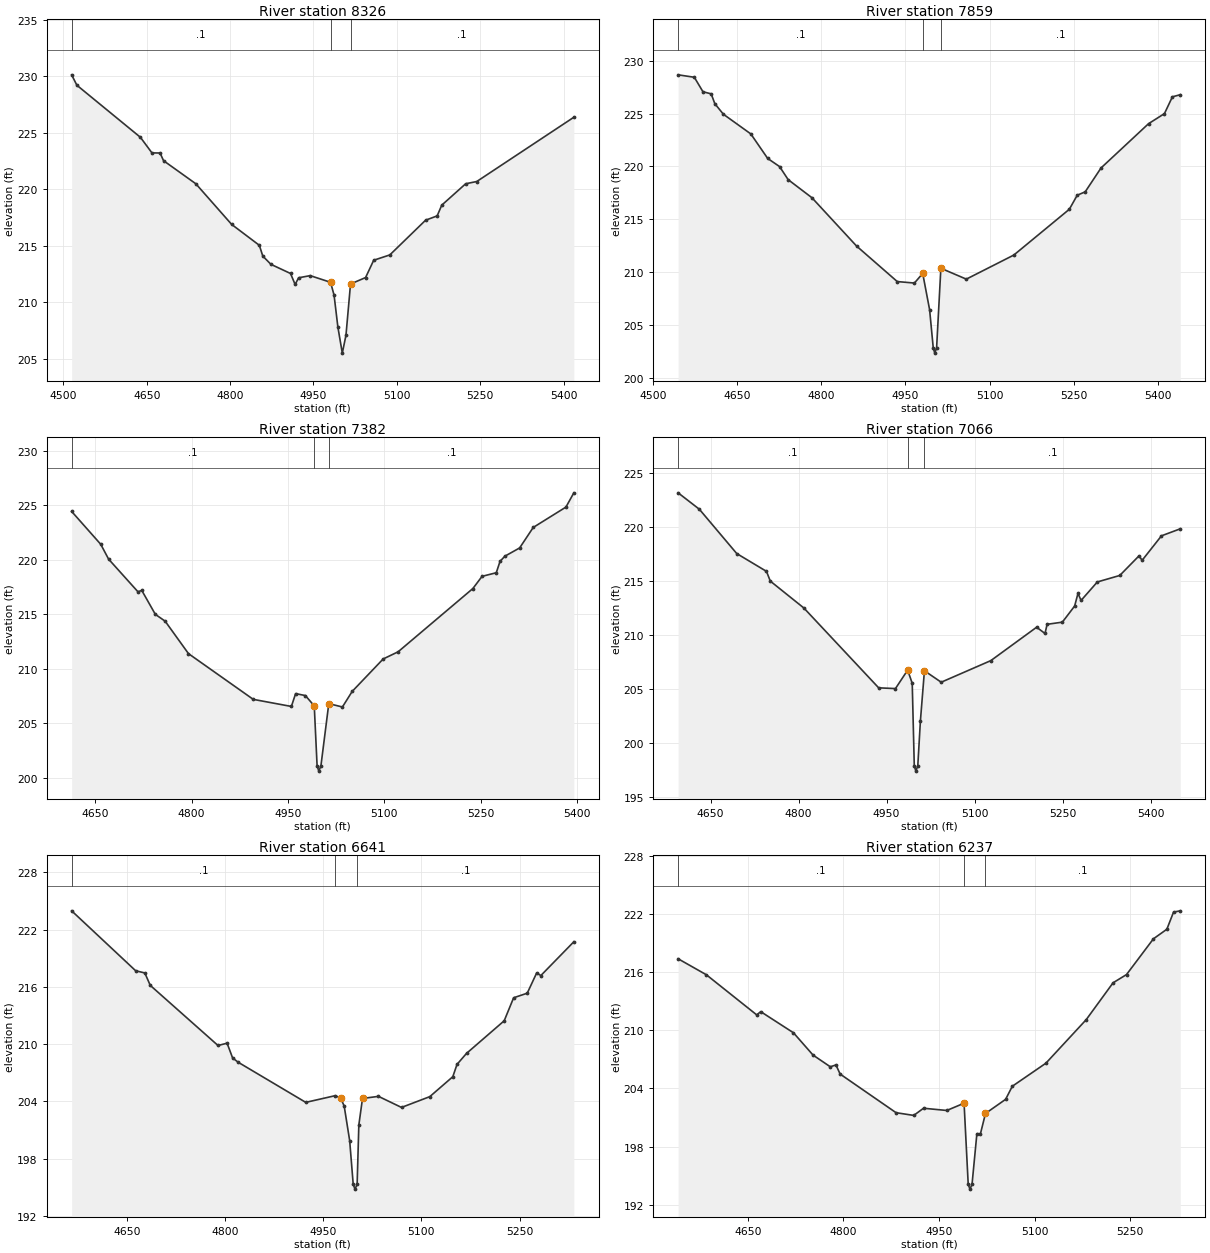
Type RM Length L Ch R = 1 ,8326    ,467,467,467
BEGIN DESCRIPTION:
UNT 028 IN RACR 17.0
END DESCRIPTION:
XS GIS Cut Line= 3
      2260575.28     13231447.13      2260985.63     13230910.12
      2260985.63     13230682.17
#Sta/Elev= 30
  4514.8  230.12  4524.2   229.2  4638.5   224.6  4659.3  223.22  4673.9  223.21
  4680.2  222.53  4738.3  220.49  4802.7   216.9  4852.6  215.05  4858.8   214.1
  4873.4  213.37  4908.7  212.56    4917  211.59  4923.3  212.18  4944.1  212.37
  4980.8  211.78  4987.1  210.64  4993.9  207.84  5001.9  205.52  5008.5   207.1
  5016.7  211.63  5043.8   212.2  5058.4  213.73  5087.4   214.2  5151.8  217.27
  5172.6  217.65  5180.9   218.6  5223.9  220.49  5243.9  220.69  5418.6  226.37
#Mann= 3 , 0 , 0
  4514.8      .1       0  4980.8     .05       0  5016.7      .1       0
Bank Sta=4980.8,5016.7
XS Rating Curve= 0 ,0
Exp/Cntr=0.3,0.1

Type RM Length L Ch R = 1 ,7859    ,477,477,477
BEGIN DESCRIPTION:
UNT 028 IN RACR 16.0
END DESCRIPTION:
XS GIS Cut Line= 3
       2260787.7     13231646.87      2261187.72     13231396.85
      2261487.73     13231096.85
#Sta/Elev= 30
  4544.4  228.67  4573.3  228.44  4588.7  227.07  4603.4  226.87  4609.9  225.94
  4625.2  224.94  4674.1  223.08  4704.2  220.76  4725.4  219.99  4740.8  218.75
  4783.2  217.04  4862.8  212.47  4935.4  209.11    4966  208.97  4980.8  209.88
  4993.1  206.45  4999.6  202.84  5002.3  202.34  5005.6  202.84  5013.2  210.37
  5058.6  209.34  5143.4  211.62  5242.4  215.95  5256.5  217.28  5270.7   217.6
    5299  219.86  5383.8  224.05  5412.1     225  5426.3  226.59  5440.4  226.79
#Mann= 3 , 0 , 0
  4544.4      .1       0  4980.8     .05       0  5013.2      .1       0
Bank Sta=4980.8,5013.2
XS Rating Curve= 0 ,0
Exp/Cntr=0.3,0.1

Type RM Length L Ch R = 1 ,7382    ,316,316,316
BEGIN DESCRIPTION:
UNT 028 IN RACR 15.0
END DESCRIPTION:
XS GIS Cut Line= 2
      2261304.83     13232055.07      2261725.32     13231396.46
#Sta/Elev= 30
  4613.5  224.44  4658.8  221.42    4671  220.06  4716.7  217.06  4722.6  217.19
  4743.7  214.99    4759  214.36  4795.3  211.38  4896.1  207.18  4955.4  206.53
    4962  207.71  4977.2  207.53    4991  206.58  4995.4  201.09  4998.1  200.59
  5001.4  201.09  5013.6  206.79  5034.8  206.48    5050  207.91  5098.2  210.89
  5121.5  211.55  5237.8  217.36  5252.1  218.48  5274.2  218.81  5280.1  219.86
  5287.6  220.33  5310.6  221.09  5331.7  222.97  5382.6  224.84  5394.9  226.15
#Mann= 3 , 0 , 0
  4613.5      .1       0    4991     .05       0  5013.6      .1       0
Bank Sta=4991,5013.6
XS Rating Curve= 0 ,0
Exp/Cntr=0.3,0.1

Type RM Length L Ch R = 1 ,7066    ,425,425,425
BEGIN DESCRIPTION:
UNT 028 IN RACR 14.0
END DESCRIPTION:
XS GIS Cut Line= 3
      2261482.11     13232252.71      2261887.43     13231771.38
      2261953.02     13231554.43
#Sta/Elev= 30
  4594.8  223.13    4631  221.61  4694.7  217.51  4745.4  215.86  4751.9  214.96
  4809.1  212.47  4936.6  205.08  4965.2  205.01    4986  206.72  4993.8   205.5
  4997.3  197.87    5000  197.37  5003.3  197.87  5007.7  201.99  5014.6  206.66
  5043.2   205.6  5127.8   207.6  5205.8  210.69  5220.1  210.11  5223.7  210.96
  5249.7  211.16  5270.6  212.65  5276.3  213.82  5281.6  213.17  5309.3  214.88
  5347.5  215.48  5380.4   217.3  5385.6  216.88  5418.6  219.15  5450.7   219.8
#Mann= 3 ,-1 , 0
  4594.8      .1       0    4986     .05       0  5014.6      .1       0
Bank Sta=4986,5014.6
XS Rating Curve= 0 ,0
Exp/Cntr=0.3,0.1

Type RM Length L Ch R = 1 ,6641    ,404,404,404
BEGIN DESCRIPTION:
UNT 028 IN RACR 13.0
END DESCRIPTION:
XS GIS Cut Line= 3
      2261637.76     13232446.84      2262037.72     13232246.85
       2262237.7     13231996.88
#Sta/Elev= 30
  4565.7  223.96  4663.5  217.68  4677.5  217.45  4685.8  216.15  4789.3  209.85
  4803.2  210.09  4811.6  208.55    4820   208.1  4923.4  203.89  4968.2  204.59
  4976.5  204.37  4982.1  203.51  4990.5  199.88  4995.9   195.3  4998.6   194.8
  5001.9   195.3  5004.5  201.52  5010.1   204.3  5034.5  204.52  5069.7  203.36
  5112.9  204.49  5148.1  206.58  5154.5  207.87    5169  209.02  5226.6  212.44
    5241  214.85  5261.8  215.33  5276.2  217.45  5282.6  217.18    5333  220.72
#Mann= 3 ,-1 , 0
  4565.7      .1       0  4968.2     .05       0  5001.9      .1       0
Bank Sta=4976.5,5010.1
XS Rating Curve= 0 ,0
Exp/Cntr=0.3,0.1

Type RM Length L Ch R = 1 ,6237    ,442,442,442
BEGIN DESCRIPTION:
UNT 028 IN RACR 12.0
END DESCRIPTION:
XS GIS Cut Line= 3
      2261887.69     13232796.87      2262287.72     13232546.85
      2262587.76     13232446.84
#Sta/Elev= 30
  4540.5  217.39  4584.8  215.74  4663.8   211.6  4670.2  211.93  4721.5  209.75
  4752.2  207.45  4779.3  206.24  4788.2  206.43  4794.7  205.49  4882.5   201.5
  4910.2  201.22  4925.6  201.96  4962.1  201.73  4989.2  202.48  4995.7  194.11
  4998.4  193.61  5001.7  194.11  5009.3  199.33  5014.9  199.33  5022.8  201.42
  5054.4  202.88  5064.9  204.23  5117.6  206.61  5180.9  211.11    5223  214.91
  5244.1  215.76  5286.3  219.45  5307.4  220.44  5317.9  222.21  5328.5  222.34
#Mann= 3 ,-1 , 0
  4540.5      .1       0  4989.2     .05       0  5022.8      .1       0
Bank Sta=4989.2,5022.8
XS Rating Curve= 0 ,0
Exp/Cntr=0.3,0.1

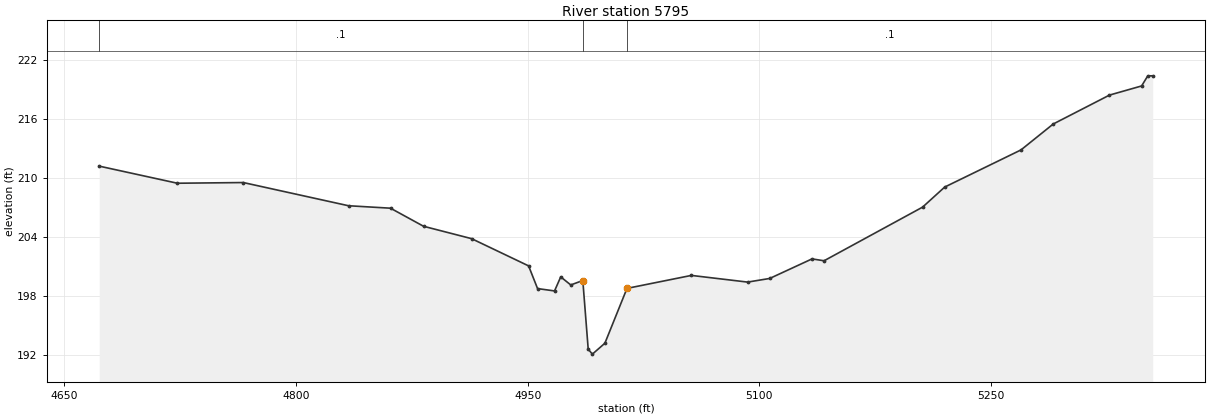
Type RM Length L Ch R = 1 ,5795    ,427,427,427
BEGIN DESCRIPTION:
UNT 028 IN RACR 11.0
END DESCRIPTION:
XS GIS Cut Line= 3
      2262187.68     13233096.88      2262437.72     13232946.85
      2262737.72     13232696.86
#Sta/Elev= 30
  4672.6  211.17  4723.2  209.43  4765.9   209.5    4834  207.14  4861.2  206.89
  4882.6  205.05  4913.7  203.79  4950.6  201.02  4956.4  198.71  4967.4  198.47
  4971.4   199.9  4977.9  199.08  4985.7  199.53  4989.2  192.54  4991.9  192.04
    5000  193.15  5014.3  198.73    5056  200.05  5092.4  199.37  5106.7  199.74
  5134.1  201.73  5141.9  201.54  5205.7     207    5220  209.04  5269.4  212.82
  5290.3  215.46  5326.7   218.4  5347.5  219.33  5351.5  220.36  5354.7  220.36
#Mann= 3 , 0 , 0
  4672.6      .1       0  4985.7     .05       0  5014.3      .1       0
Bank Sta=4985.7,5014.3
XS Rating Curve= 0 ,0
Exp/Cntr=0.3,0.1