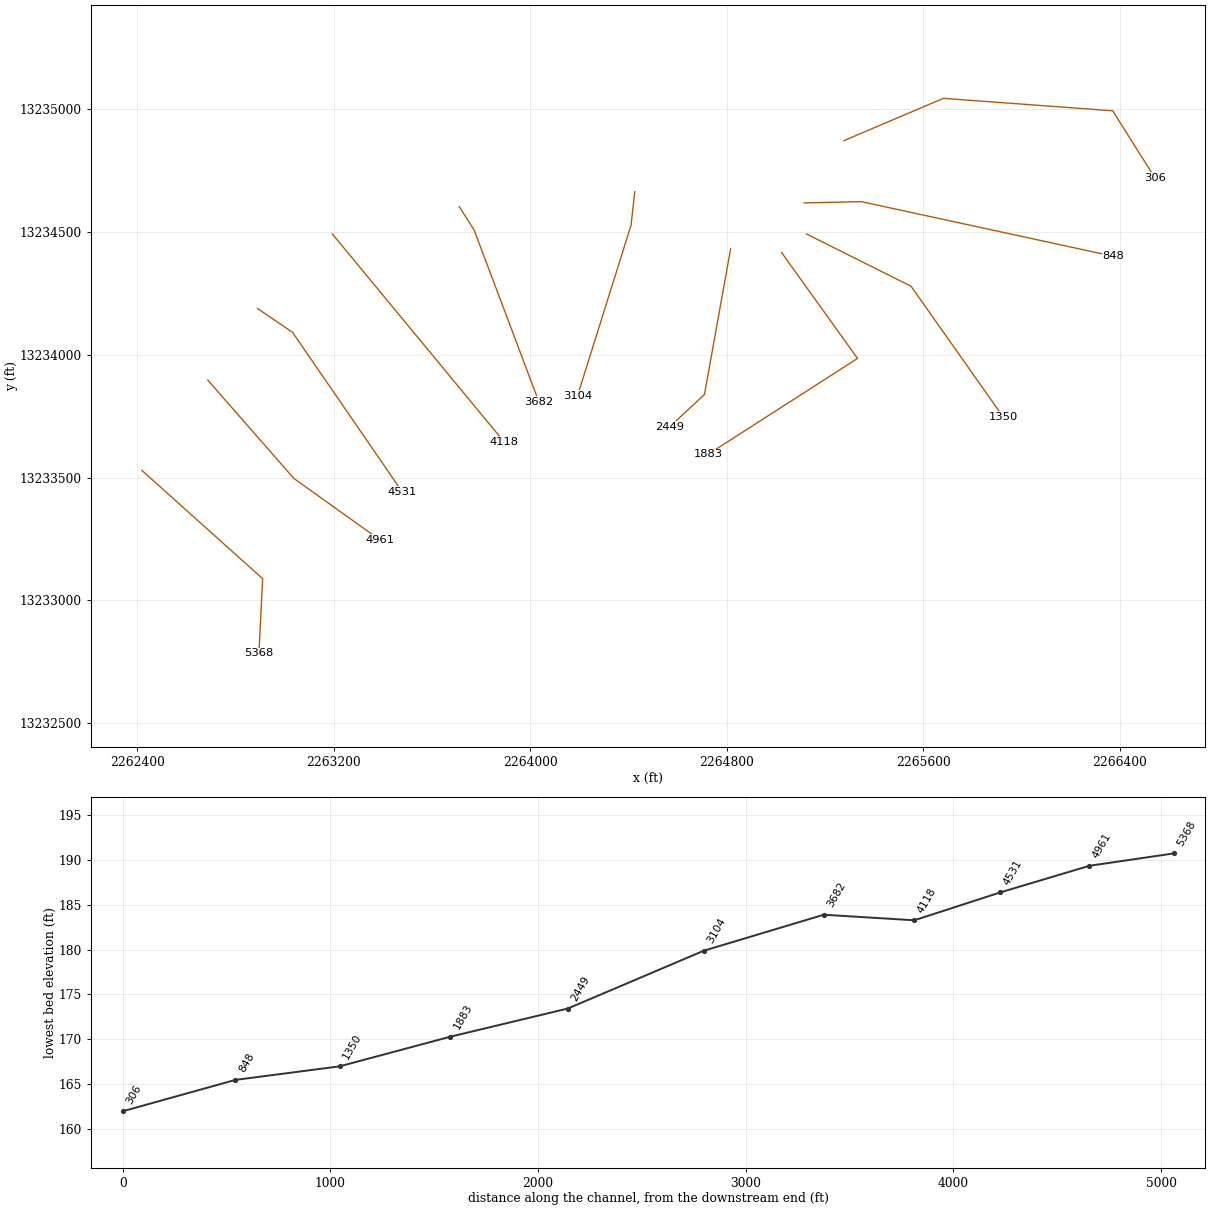
HEC-RAS study UNT 028 IN RACR.prj: UNT 028 IN RACR Base Level Engineering

--- UNT 028 IN RACR.g01 (geometry) --- (continued)

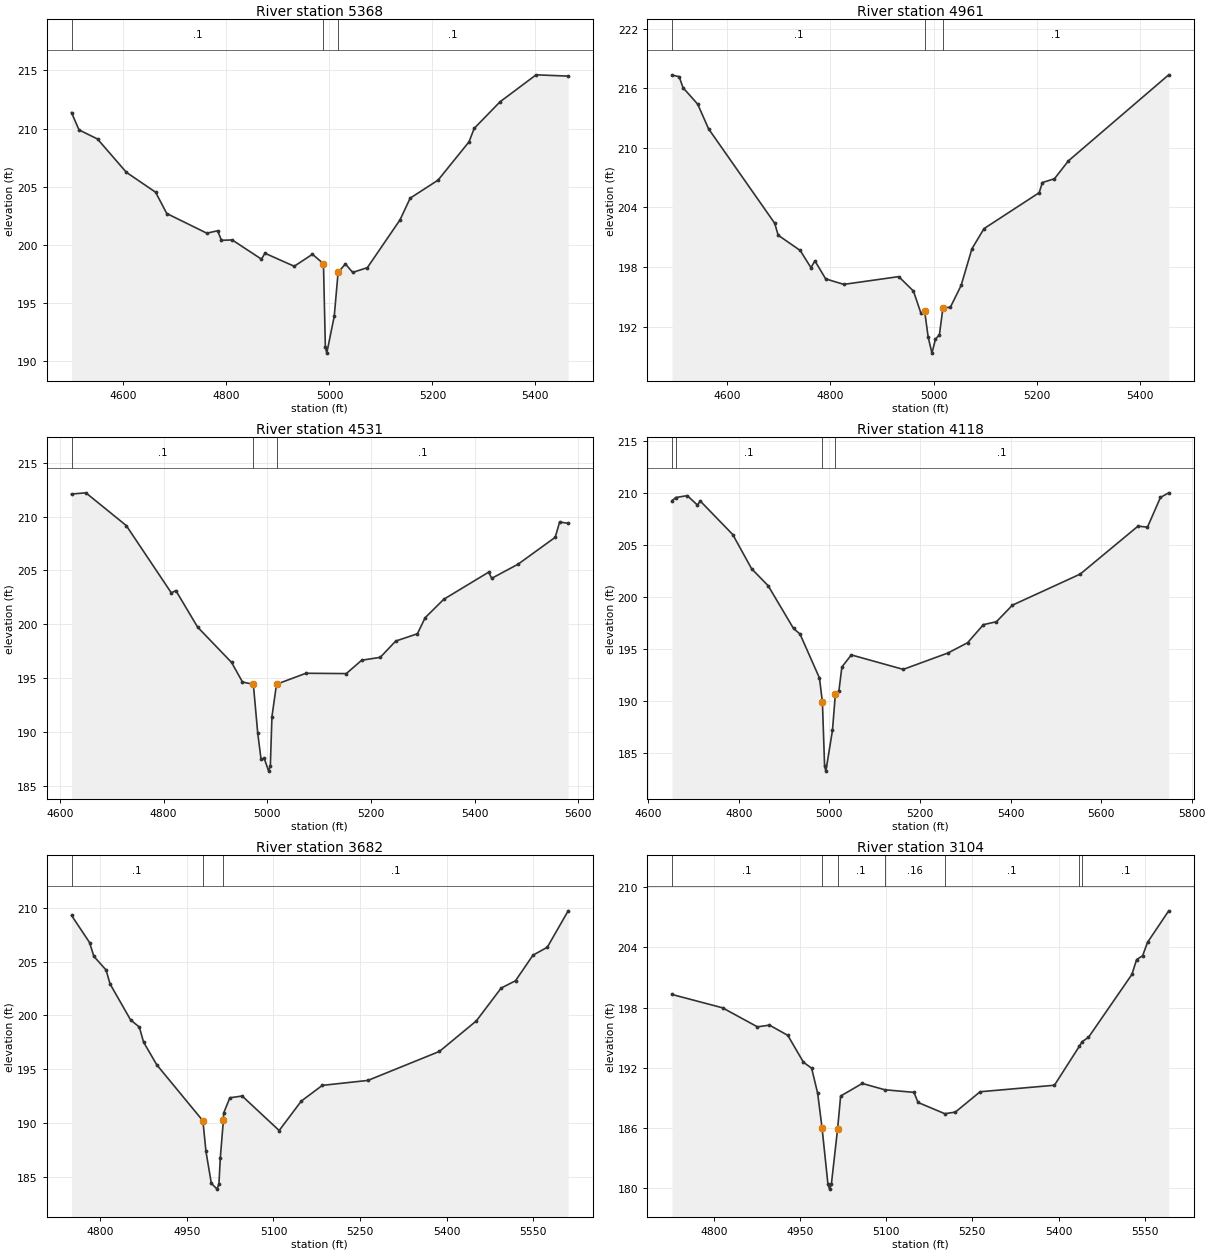
Type RM Length L Ch R = 1 ,5368    ,407,407,407
BEGIN DESCRIPTION:
UNT 028 IN RACR 10.0
END DESCRIPTION:
XS GIS Cut Line= 3
      2262419.41     13233529.36      2262910.82     13233088.61
      2262895.62      13232784.6
#Sta/Elev= 30
  4499.1  211.37  4513.7  209.88  4549.6   209.1  4605.6  206.24  4662.4  204.53
  4684.1   202.7  4761.9  201.01  4782.8  201.22  4790.3   200.4  4811.2  200.43
    4868  198.78  4874.7  199.29  4931.6  198.17    4967   199.2  4988.4  198.39
  4992.1  191.21  4994.8  190.71  5009.3  193.87  5016.8  197.64    5031  198.37
  5045.2  197.64  5073.6  198.05  5137.1  202.16  5156.8  204.02    5211  205.57
  5271.1  208.86  5281.1  210.01  5331.2  212.29  5401.3  214.61  5463.6   214.5
#Mann= 3 , 0 , 0
  4499.1      .1       0  4988.4     .05       0  5016.8      .1       0
Bank Sta=4988.4,5016.8
XS Rating Curve= 0 ,0
Exp/Cntr=0.3,0.1

Type RM Length L Ch R = 1 ,4961    ,430,430,430
BEGIN DESCRIPTION:
UNT 028 IN RACR 9.0
END DESCRIPTION:
XS GIS Cut Line= 3
      2262687.74     13233896.83      2263037.72     13233496.85
      2263387.72     13233246.85
#Sta/Elev= 30
  4493.5  217.31  4507.2  217.16  4514.8  216.05  4543.3  214.38  4564.2  211.91
  4692.3   202.4    4699   201.2  4741.7  199.66  4762.5  197.93  4770.1  198.62
    4791   196.8  4826.1  196.25  4932.4  197.03  4960.9  195.58  4975.2  193.38
  4982.7  193.52  4989.4  190.95  4996.7  189.33  5003.6  190.75  5011.2  191.17
  5017.9  193.86  5032.4  193.95  5053.2  196.14  5074.1  199.83  5097.5  201.86
  5204.4  205.48  5210.5   206.5  5233.9  206.88  5260.9  208.68  5455.1  217.34
#Mann= 3 , 0 , 0
  4493.5      .1       0  4982.7     .05       0  5017.9      .1       0
Bank Sta=4982.7,5017.9
XS Rating Curve= 0 ,0
Exp/Cntr=0.3,0.1

Type RM Length L Ch R = 1 ,4531    ,413,413,413
BEGIN DESCRIPTION:
UNT 028 IN RACR 8.0
END DESCRIPTION:
XS GIS Cut Line= 3
      2262890.55     13234187.99      2263032.41     13234091.73
      2263478.25     13233443.24
#Sta/Elev= 30
  4622.2   212.1    4650  212.21  4727.9  209.17  4814.8  202.92  4823.6  203.13
  4865.5  199.74  4931.2  196.45  4952.1  194.64  4973.1  194.42  4981.6  189.87
    4988  187.45  4994.1  187.54  5002.6  186.36  5005.9  186.86    5009  191.42
  5017.8  194.43  5074.6  195.45  5152.4  195.42  5182.2  196.66    5218  196.93
  5247.8  198.44  5289.7  199.12  5304.6  200.61  5340.5  202.32  5427.1  204.84
  5433.1  204.27  5483.9  205.58  5555.6  208.08  5564.1   209.5  5580.6  209.38
#Mann= 3 , 0 , 0
  4622.2      .1       0  4973.1     .05       0  5017.8      .1       0
Bank Sta=4973.1,5017.8
XS Rating Curve= 0 ,0
Exp/Cntr=0.3,0.1

Type RM Length L Ch R = 1 ,4118    ,436,436,436
BEGIN DESCRIPTION:
UNT 028 IN RACR 7.0
END DESCRIPTION:
XS GIS Cut Line= 2
      2263194.56     13234491.93      2263893.22     13233646.45
#Sta/Elev= 30
  4652.5  209.25  4660.7  209.56  4686.3  209.74  4708.4  208.84  4714.9  209.22
  4786.6     206  4828.3  202.71  4864.8  201.08  4920.8  196.97  4935.1  196.44
  4978.1  192.21  4984.6  189.89  4989.4  183.76  4992.2  183.26  5006.8  187.18
  5013.3  190.72  5021.1     191  5027.6  193.27  5048.4  194.43  5163.1  193.04
  5262.1  194.62  5305.1   195.6  5340.2  197.34  5368.9  197.62  5404.1  199.21
  5553.9   202.2  5681.6  206.81  5702.4  206.71  5731.1  209.57  5749.3  210.01
#Mann= 4 ,-1 , 0
  4652.5     .16       0  4660.7      .1       0  4984.6     .05       0
  5013.3      .1       0
Bank Sta=4984.6,5013.3
XS Rating Curve= 0 ,0
Exp/Cntr=0.3,0.1

Type RM Length L Ch R = 1 ,3682    ,578,578,578
BEGIN DESCRIPTION:
UNT 028 IN RACR 6.0
END DESCRIPTION:
XS GIS Cut Line= 3
      2263711.28     13234603.43      2263772.08     13234507.17
      2264035.53     13233808.01
#Sta/Elev= 30
  4749.9  209.29  4781.3  206.76  4788.6  205.49  4809.8  204.22  4816.8  202.92
  4852.3  199.59  4867.5  198.92  4874.8  197.53  4897.7  195.42  4977.7  190.22
    4983  187.38  4992.3  184.42  5002.3  183.88  5005.5  184.38  5007.9  186.81
 5013.18  190.26  5013.7  190.94  5024.4  192.36  5045.8  192.52  5109.9  189.32
  5148.2  192.05  5184.7  193.51  5263.7  193.97  5387.7  196.66  5451.8   199.5
  5494.7  202.54  5519.6  203.22  5549.8  205.59  5574.7  206.33  5610.9  209.71
#Mann= 3 , 0 , 0
  4749.9      .1       0  4977.7     .05       0 5013.18      .1       0
Bank Sta=4977.7,5013.18
XS Rating Curve= 0 ,0
Exp/Cntr=0.3,0.1

Type RM Length L Ch R = 1 ,3104    ,655,655,655
BEGIN DESCRIPTION:
UNT 028 IN RACR 5.0
END DESCRIPTION:
XS GIS Cut Line= 3
      2264425.63     13234664.24      2264410.43     13234527.43
      2264192.65     13233833.56
#Sta/Elev= 30
    4727   199.3  4814.9  197.97  4875.7  196.07  4896.7  196.24  4928.6  195.22
  4955.8  192.54  4970.1  191.94  4980.6  189.44  4988.2  186.01  4998.5  180.37
  5001.3  179.87  5004.5  180.37 5015.34  185.89  5020.6  189.16  5058.3  190.42
  5097.4  189.79  5148.2  189.53  5155.5  188.52    5202   187.4  5220.4  187.56
  5263.5  189.59  5392.9  190.24  5436.4  194.14  5441.1  194.59  5452.2  195.02
  5527.8   201.3    5536  202.78  5546.5  203.17    5555   204.5  5591.9  207.65
#Mann= 7 ,-1 , 0
    4727      .1       0  4988.2     .05       0 5015.34      .1       0
  5097.4     .16       0    5202      .1       0  5436.4     .16       0
  5441.1      .1       0
Bank Sta=4988.2,5015.34
XS Rating Curve= 0 ,0
Exp/Cntr=0.3,0.1

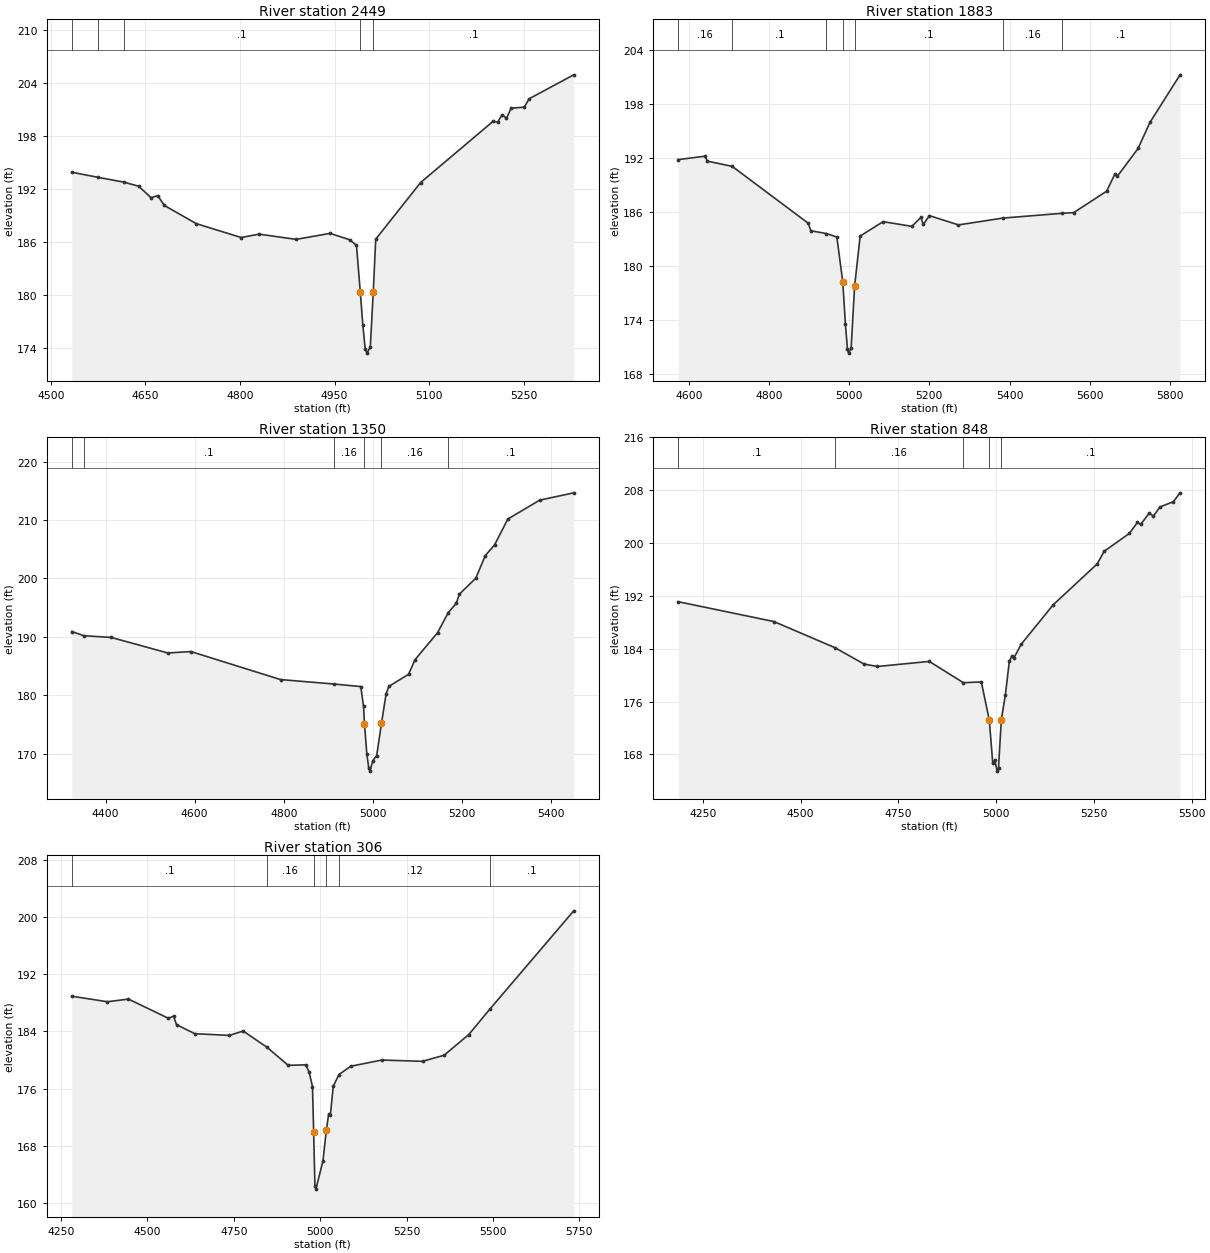
Type RM Length L Ch R = 1 ,2449    ,566,566,566
BEGIN DESCRIPTION:
Mapping XS d825e1e3
END DESCRIPTION:
XS GIS Cut Line= 3
      2264815.73     13234431.14      2264709.34     13233838.42
      2264567.47     13233706.68
#Sta/Elev= 30
  4533.4  193.91  4574.8  193.34  4615.8  192.79  4639.4  192.33  4659.1  191.03
  4669.8  191.26    4680  190.16  4730.8  188.09  4801.9  186.52  4830.4   186.9
  4889.2  186.31  4942.9  186.99  4974.6  186.25  4984.8  185.62 4990.91   180.3
  4994.9  176.56  4998.6  173.93  5001.4  173.43  5006.7  174.12 5011.36   180.3
  5015.3  186.33  5086.4  192.74  5201.6  199.69  5208.4  199.57  5215.8  200.43
  5222.6  200.02    5230  201.16    5251  201.28  5258.3  202.22  5329.2  204.94
#Mann= 5 ,-1 , 0
  4533.4      .1       0  4574.8     .16       0  4615.8      .1       0
 4990.91     .05       0 5011.36      .1       0
Bank Sta=4990.91,5011.36
XS Rating Curve= 0 ,0
Exp/Cntr=0.3,0.1

Type RM Length L Ch R = 1 ,1883    ,533,533,533
BEGIN DESCRIPTION:
UNT 028 IN RACR 4.0
END DESCRIPTION:
XS GIS Cut Line= 3
      2265023.45     13234415.97      2265332.49     13233985.34
      2264724.54     13233595.24
#Sta/Elev= 30
  4573.1  191.81  4640.1  192.19  4646.2  191.64  4708.1  191.06    4898  184.73
  4904.3   183.9    4943  183.59  4969.2   183.2  4983.9  178.24  4990.5  173.55
  4995.6  170.79  4998.4  170.29  5004.8  170.81  5013.4   177.7  5027.4  183.31
  5084.6  184.91  5156.3  184.39  5178.9  185.38  5184.9   184.6  5200.1  185.58
  5272.7  184.55  5383.5  185.31  5531.6  185.84  5560.3  185.92  5642.1  188.29
  5663.2  190.23  5669.2  189.97  5720.7  193.05  5750.4  195.95  5825.5  201.24
#Mann= 7 ,-1 , 0
  4573.1     .16       0  4708.1      .1       0    4943     .16       0
  4983.9     .05       0  5013.4      .1       0  5383.5     .16       0
  5531.6      .1       0
Bank Sta=4983.9,5013.4
XS Rating Curve= 0 ,0
Exp/Cntr=0.3,0.1

Type RM Length L Ch R = 1 ,1350    ,502,502,502
BEGIN DESCRIPTION:
UNT 028 IN RACR 3.0
END DESCRIPTION:
XS GIS Cut Line= 3
      2265124.78     13234491.97      2265550.34     13234279.19
      2265925.26     13233747.21
#Sta/Elev= 30
  4324.2   190.9  4351.7  190.17  4412.6  189.89  4539.9  187.22  4591.5  187.47
  4792.7  182.67  4912.1  181.91  4972.9  181.47    4979  178.11 4981.14  175.09
  4986.4  169.99  4990.8  167.49  4993.5  166.99  4999.9  168.78  5008.6  169.66
 5019.32  175.16  5029.5  180.12  5035.6  181.49    5080  183.57  5094.8  186.09
  5145.3  190.71  5169.1  194.12  5187.1  195.72  5194.3  197.31    5231  200.03
  5252.4  203.91  5273.3  205.75  5302.9  210.16  5374.3  213.39  5450.8  214.65
#Mann= 6 ,-1 , 0
  4324.2     .16       0  4351.7      .1       0  4912.1     .16       0
 4981.14     .05       0 5019.32     .16       0  5169.1      .1       0
Bank Sta=4981.14,5019.32
XS Rating Curve= 0 ,0
Exp/Cntr=0.3,0.1

Type RM Length L Ch R = 1 ,848     ,542,542,542
BEGIN DESCRIPTION:
Mapping XS 322276ac
END DESCRIPTION:
XS GIS Cut Line= 3
      2265114.62     13234618.63      2265347.69     13234623.69
      2266374.42     13234401.15
#Sta/Elev= 30
  4186.7  191.13  4431.9  188.12  4587.7  184.17  4662.4  181.69  4696.1  181.32
  4829.1  182.09  4916.1  178.87  4962.2  178.98  4982.6  173.18  4991.4  166.68
  4996.5  167.15  5002.8  165.48  5006.1  165.98  5013.3  173.26  5023.6  176.99
  5033.8  182.11  5040.6  182.93  5045.7  182.64  5064.5  184.72  5146.3  190.68
  5258.9  196.87  5276.2  198.75  5340.8  201.47  5361.2  203.12  5369.5  202.83
  5391.9  204.55  5402.2  204.07  5418.7  205.45  5453.3  206.28  5470.4  207.61
#Mann= 5 ,-1 , 0
  4186.7      .1       0  4587.7     .16       0  4916.1      .1       0
  4982.6     .07       0  5013.3      .1       0
Bank Sta=4982.6,5013.3
XS Rating Curve= 0 ,0
Exp/Cntr=0.3,0.1

Type RM Length L Ch R = 1 ,306     ,0,0,0
BEGIN DESCRIPTION:
UNT 028 IN RACR 1.0
END DESCRIPTION:
XS GIS Cut Line= 4
      2265276.72     13234871.92      2265682.07     13235044.19
      2266371.08     13234993.53      2266542.43     13234721.38
#Sta/Elev= 30
  4280.8  188.92    4384  188.15  4444.9  188.52  4560.4  185.84  4575.3  186.13
  4584.1  184.95  4636.8  183.69  4736.9  183.45    4777  184.06  4846.2  181.78
  4907.4  179.27  4957.5  179.34  4967.5   178.4  4977.6  176.31 4980.91  170.01
  4984.6  162.49  4987.4  161.99  5007.7  165.89  5017.7  170.21  5024.3  172.45
  5029.3  172.32  5037.7  176.35  5054.2  177.98  5087.9  179.14  5178.1  180.01
    5296  179.83  5358.6  180.68  5429.9  183.57  5492.4   187.2  5733.7  200.84
#Mann= 6 ,-1 , 0
  4280.8      .1       0  4846.2     .16       0 4980.91     .05       0
  5017.7     .16       0  5054.2     .12       0  5492.4      .1       0
Bank Sta=4980.91,5017.7
XS Rating Curve= 0 ,0
Exp/Cntr=0.3,0.1
Stream Node=UNT 028 IN RACR ,Reach-1         , 0 , 0 ,Upstream end
Stream Node=UNT 028 IN RACR ,Reach-1         , 0 , 1 ,Downstream end

Chan Stop Cuts=-1
Use User Specified Reach Order=0
Composite Channel Slope=5