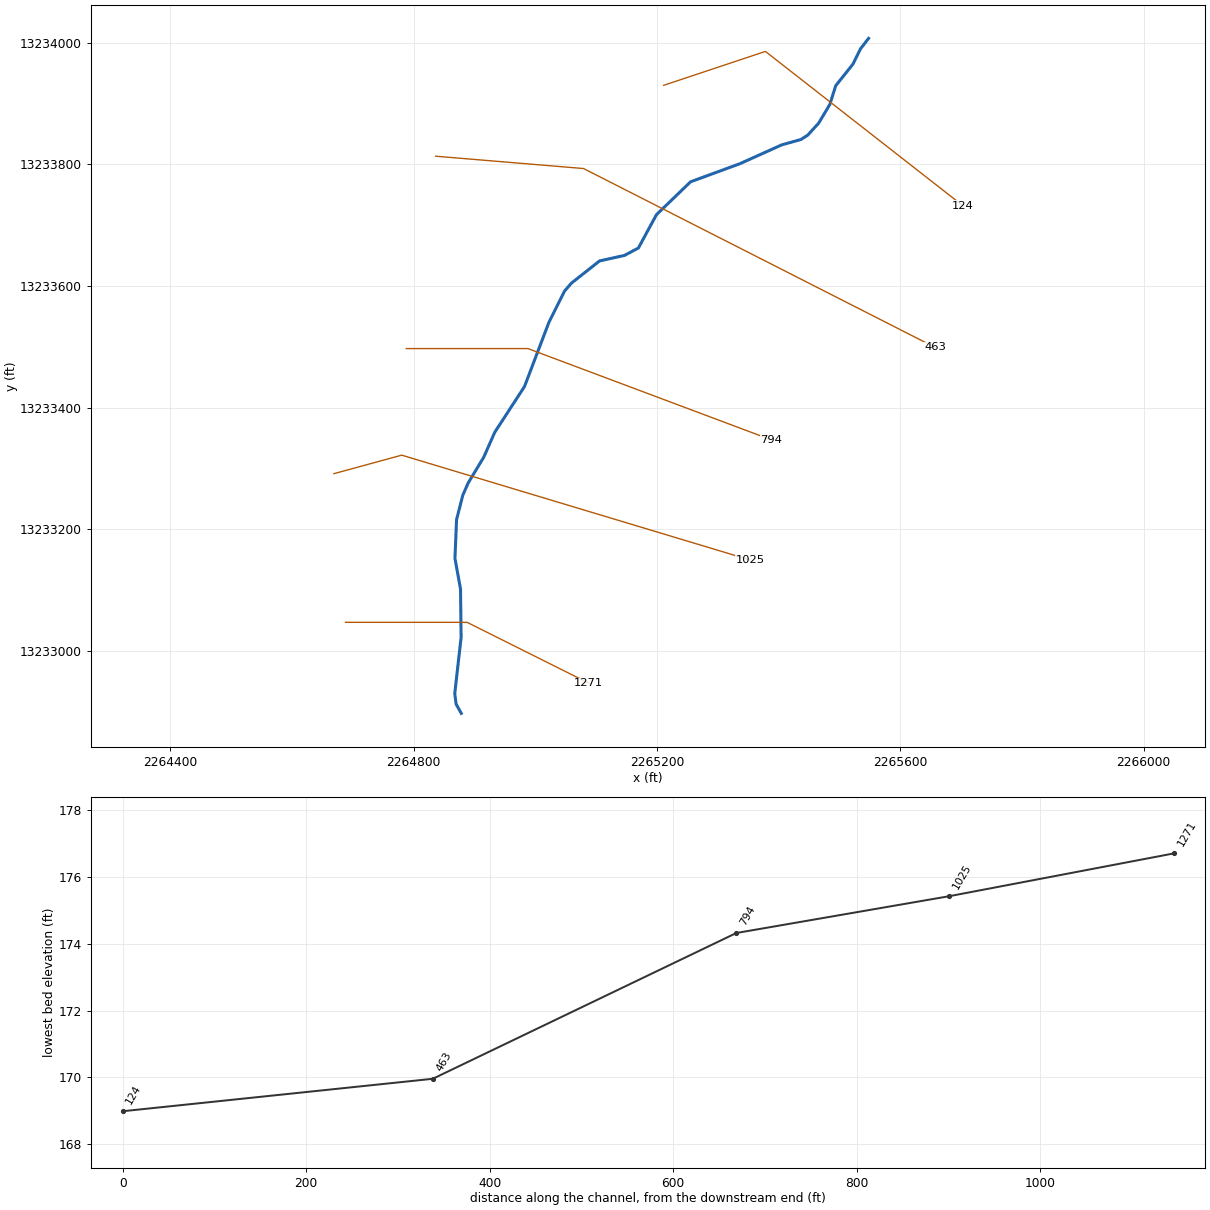
--- UNT 029 IN RACR.prj (project) ---

Proj Title=UNT 029 IN RACR Base Level Engineering
Current Plan=p01
Default Exp/Contr=0.3,0.1
English Units
Geom File=g01
Flow File=f01
Plan File=p01
Y Axis Title=Elevation
X Axis Title(PF)=Main Channel Distance
X Axis Title(XS)=Station
BEGIN DESCRIPTION:
UNT 029 IN RACR
END DESCRIPTION:
DSS Export Rating Curves= 0
DSS Export Rating Curve Sorted= 0
DSS Export Volume Flow Curves= 0
DXF OffsetX= 0
DXF OffsetY= 0
DXF ScaleX= 1
DXF ScaleY= 10

--- UNT 029 IN RACR.p01 (plan) ---

Plan Title=Multiple Run
Short Identifier=Multiple
Geom File=g01
Flow File=f01
Subcritical Flow
K Sum by GR= 0
Std Step Tol= 0.01
Critical Tol= 0.01
Num of Std Step Trials= 20
Max Error Tol= 0.3
Flow Tol Ratio= 0.001
Split Flow NTrial= 30
Split Flow Tol= 0.02
Split Flow Ratio= 0.02
Log Output Level= 0
Friction Slope Method= 1
Unsteady Friction Slope Method= 2
Unsteady Bridges Friction Slope Method= 1
Parabolic Critical Depth
Global Vel Dist=  1 , 1 , 1
Global Log Level= 0
CheckData=True
Encroach Param= -1, 0, 0, 0
BEGIN DESCRIPTION:
Multiple Run
END DESCRIPTION:

--- UNT 029 IN RACR.f01 (steady flow) ---

Flow Title=Multiple
Program Version=4.10
Number of Profiles= 7
Profile Names=10-year,25-year,50-year,1pct_min,100-year,1pct_plu,500-year
River Rch & RM=UNT 029 IN RACR,Reach-1         ,1271
     239     331     408     370     500     677     765
Boundary for River Rch & Prof#=UNT 029 IN RACR,Reach-1         , 1
Up Type= 0
Dn Type= 3
Dn Slope=0.005
Boundary for River Rch & Prof#=UNT 029 IN RACR,Reach-1         , 2
Up Type= 0
Dn Type= 3
Dn Slope=0.005
Boundary for River Rch & Prof#=UNT 029 IN RACR,Reach-1         , 3
Up Type= 0
Dn Type= 3
Dn Slope=0.005
Boundary for River Rch & Prof#=UNT 029 IN RACR,Reach-1         , 4
Up Type= 0
Dn Type= 3
Dn Slope=0.005
Boundary for River Rch & Prof#=UNT 029 IN RACR,Reach-1         , 5
Up Type= 0
Dn Type= 3
Dn Slope=0.005
Boundary for River Rch & Prof#=UNT 029 IN RACR,Reach-1         , 6
Up Type= 0
Dn Type= 3
Dn Slope=0.005
Boundary for River Rch & Prof#=UNT 029 IN RACR,Reach-1         , 7
Up Type= 0
Dn Type= 3
Dn Slope=0.005
DSS Import GetInterval= 0
DSS Import GetPeak= 0
DSS Import FillOption= 0

--- UNT 029 IN RACR.g01 (geometry) ---

Geom Title=Existing Conditions
Program Version=4.10

River Reach=UNT 029 IN RACR ,Reach-1
Reach XY= 30
      2264878.19     13232897.19      2264869.72     13232912.33
      2264867.41     13232929.79      2264877.86     13233021.81
      2264876.92     13233101.53      2264867.77       13233152.
      2264870.41      13233215.7      2264880.62     13233255.65
      2264889.56     13233276.09      2264914.94     13233318.01
      2264933.21     13233359.29      2264982.09     13233434.47
      2265022.13     13233539.79      2265048.01     13233591.48
      2265059.16     13233604.39      2265105.45     13233640.92
      2265146.56     13233650.04      2265169.33      13233662.2
      2265199.02       13233717.      2265255.12     13233771.05
      2265336.12     13233800.72      2265405.17     13233831.81
      2265436.38     13233840.49       2265447.5     13233847.57
      2265465.64     13233867.43      2265484.05     13233898.26
      2265493.72     13233929.05      2265522.02      13233964.5
      2265534.31     13233989.46      2265547.72     13234006.85

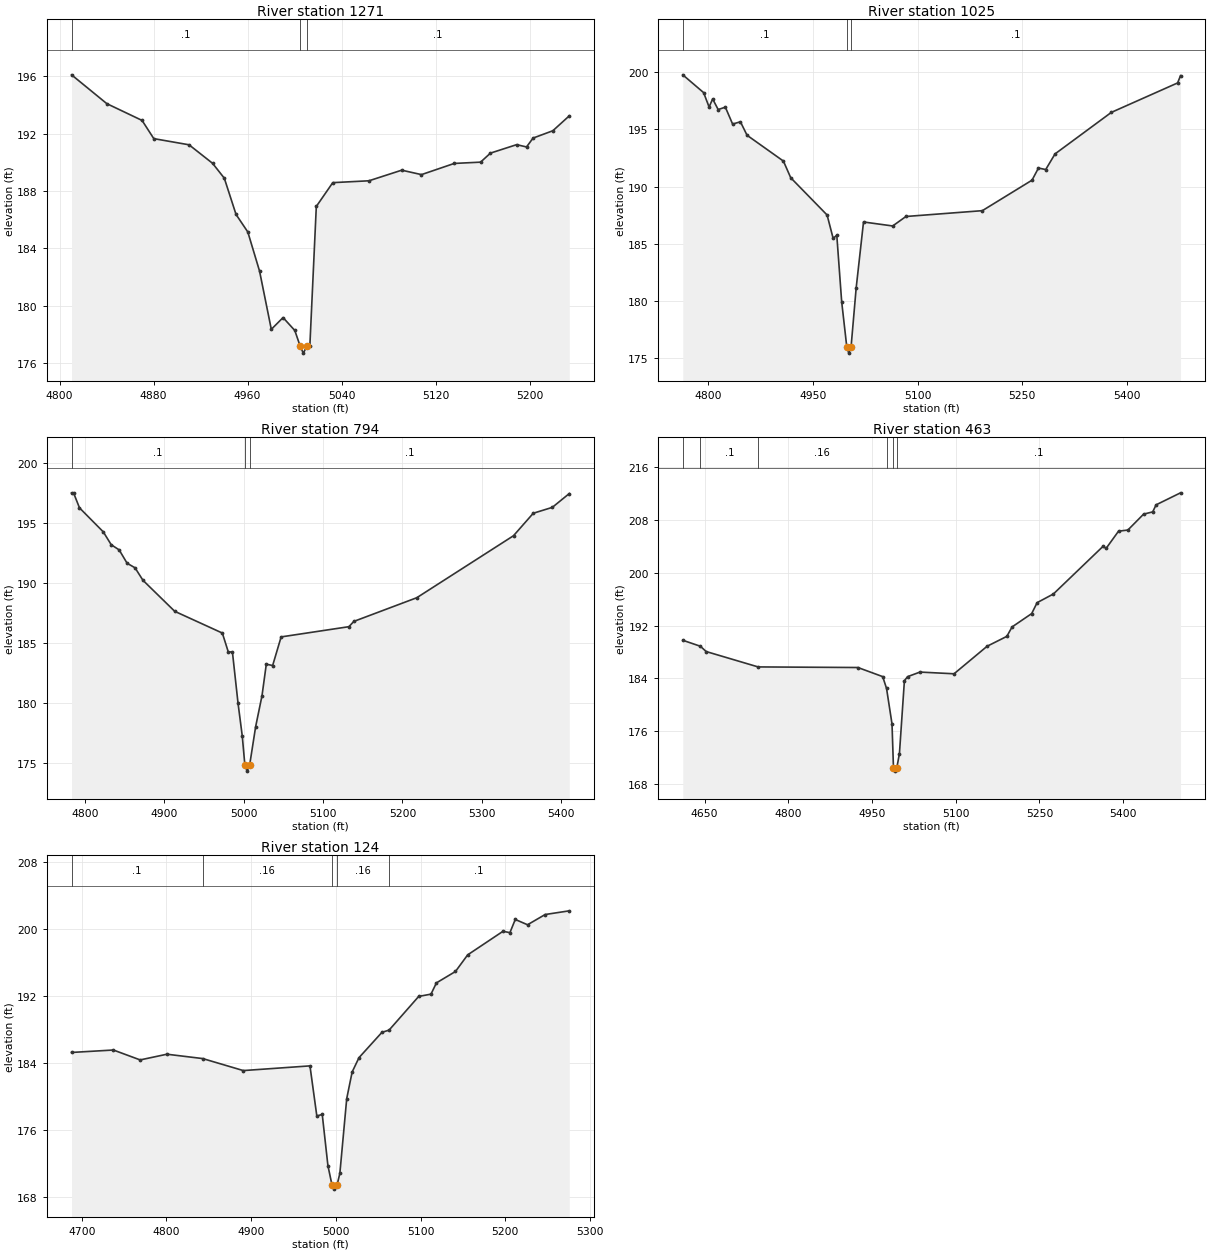
Type RM Length L Ch R = 1 ,1271    ,245,245,245
BEGIN DESCRIPTION:
UNT 029 IN RACR 3.0
END DESCRIPTION:
XS GIS Cut Line= 3
      2264687.76     13233046.85      2264887.72     13233046.85
      2265087.75     13232946.84
#Sta/Elev= 30
  4810.2  196.11  4840.2   194.1  4870.2  192.93  4880.2  191.66  4910.2  191.23
  4930.2  189.94  4940.2   188.9  4950.2  186.37  4960.2  185.15  4970.2  182.42
  4980.2  178.36  4990.2  179.18  5000.2  178.28  5004.7   177.2  5007.4   176.7
  5010.7   177.2    5013   177.2  5018.5  186.93  5032.5  188.59  5063.3  188.72
  5091.2  189.46    5108  189.15  5135.9  189.93  5158.3  190.02  5166.7  190.65
    5189  191.24  5197.4  191.08    5203   191.7  5219.8  192.21  5233.8  193.25
#Mann= 3 ,-1 , 0
  4810.2      .1       0  5004.7     .07       0  5010.7      .1       0
Bank Sta=5004.7,5010.7
XS Rating Curve= 0 ,0
Exp/Cntr=0.3,0.1

Type RM Length L Ch R = 1 ,1025    ,232,232,232
BEGIN DESCRIPTION:
Mapping XS 19814859
END DESCRIPTION:
XS GIS Cut Line= 3
      2264668.85     13233291.27      2264780.27     13233321.66
      2265352.73     13233149.42
#Sta/Elev= 30
  4763.6  199.78  4793.5  198.22  4801.3  196.96  4806.4  197.67  4814.3  196.74
  4824.6  196.95    4835  195.47  4846.2  195.67  4855.7  194.49  4907.8  192.23
  4918.3  190.77  4970.4  187.51  4979.1  185.46  4984.3  185.74  4991.3  179.92
  4998.7  175.92  5001.5  175.42  5004.7  175.92  5012.1  181.14  5022.6   186.9
  5064.4  186.55  5083.4  187.38  5192.9  187.89  5264.1  190.56  5273.3  191.62
  5283.7  191.49  5297.1  192.86  5377.7  196.49  5472.7  199.07  5476.9  199.71
#Mann= 3 ,-1 , 0
  4763.6      .1       0  4998.7     .07       0  5004.7      .1       0
Bank Sta=4998.7,5004.7
XS Rating Curve= 0 ,0
Exp/Cntr=0.3,0.1

Type RM Length L Ch R = 1 ,794     ,331,331,331
BEGIN DESCRIPTION:
UNT 029 IN RACR 2.0
END DESCRIPTION:
XS GIS Cut Line= 3
      2264787.73     13233496.85      2264987.72     13233496.85
      2265387.73     13233346.85
#Sta/Elev= 30
  4783.1  197.48  4785.6  197.48  4793.1  196.23  4823.1  194.23  4833.1  193.16
  4843.1  192.73  4853.1  191.62  4863.1  191.24  4873.1   190.2  4913.1  187.62
  4973.1  185.81  4980.6  184.24  4985.8  184.24  4992.9  179.96  4998.2  177.25
  5001.5  174.82  5004.2  174.32  5007.5  174.82  5015.1  178.03  5023.1   180.6
  5028.5  183.22  5036.5  183.11  5047.2  185.49  5132.6  186.34  5138.8  186.78
  5218.1  188.75    5340  193.91  5364.9  195.78  5388.9  196.27  5410.3  197.42
#Mann= 3 ,-1 , 0
  4783.1      .1       0  5001.5     .07       0  5007.5      .1       0
Bank Sta=5001.5,5007.5
XS Rating Curve= 0 ,0
Exp/Cntr=0.3,0.1

Type RM Length L Ch R = 1 ,463     ,338,338,338
BEGIN DESCRIPTION:
Mapping XS 9b0ed5f2
END DESCRIPTION:
XS GIS Cut Line= 3
      2264835.96     13233813.09      2265079.18     13233792.82
      2265656.76     13233498.97
#Sta/Elev= 30
  4610.8  189.79  4642.4  188.88  4652.7  188.08  4745.8  185.75  4924.7  185.66
  4969.1  184.28    4976  182.49  4985.8  177.11  4988.4  170.46  4991.1  169.96
  4994.4  170.46  4999.1  172.62    5008  183.65  5013.6  184.27  5035.9  184.97
    5097  184.71  5156.2  188.88  5191.6  190.38    5201  191.81  5236.1  193.83
  5245.9  195.49    5275   196.8    5364  204.02  5369.6  203.72  5391.8  206.32
  5408.5  206.49  5436.7   208.9    5453  209.24  5459.1  210.31  5502.9  212.13
#Mann= 6 ,-1 , 0
  4610.8     .16       0  4642.4      .1       0  4745.8     .16       0
    4976      .1       0  4988.4     .07       0  4994.4      .1       0
Bank Sta=4988.4,4994.4
XS Rating Curve= 0 ,0
Exp/Cntr=0.3,0.1

Type RM Length L Ch R = 1 ,124     ,0,0,0
BEGIN DESCRIPTION:
UNT 029 IN RACR 1.0
END DESCRIPTION:
XS GIS Cut Line= 3
      2265210.87      13233929.6      2265378.09     13233985.34
      2265702.31     13233732.04
#Sta/Elev= 30
  4687.9  185.28  4737.3  185.57  4768.9  184.39  4800.5  185.07  4842.8  184.55
  4890.7  183.12  4969.4  183.68  4977.5  177.71  4983.9  177.89  4990.6  171.79
  4995.4  169.49  4998.1  168.99  5001.4  169.49  5004.7  170.87  5012.8  179.78
  5019.2  182.95  5027.3  184.66  5054.4  187.68  5062.8  187.94  5097.8  191.96
  5112.3  192.23  5118.7  193.57  5141.2  194.93  5155.6  196.91  5197.3  199.72
  5205.5  199.56  5211.8  201.13  5226.3   200.5  5247.1  201.72  5275.6  202.16
#Mann= 5 ,-1 , 0
  4687.9      .1       0  4842.8     .16       0  4995.4     .07       0
  5001.4     .16       0  5062.8      .1       0
Bank Sta=4995.4,5001.4
XS Rating Curve= 0 ,0
Exp/Cntr=0.3,0.1
Stream Node=UNT 029 IN RACR ,Reach-1         , 0 , 0 ,Upstream end
Stream Node=UNT 029 IN RACR ,Reach-1         , 0 , 1 ,Downstream end

Chan Stop Cuts=-1
Use User Specified Reach Order=0
Composite Channel Slope=5