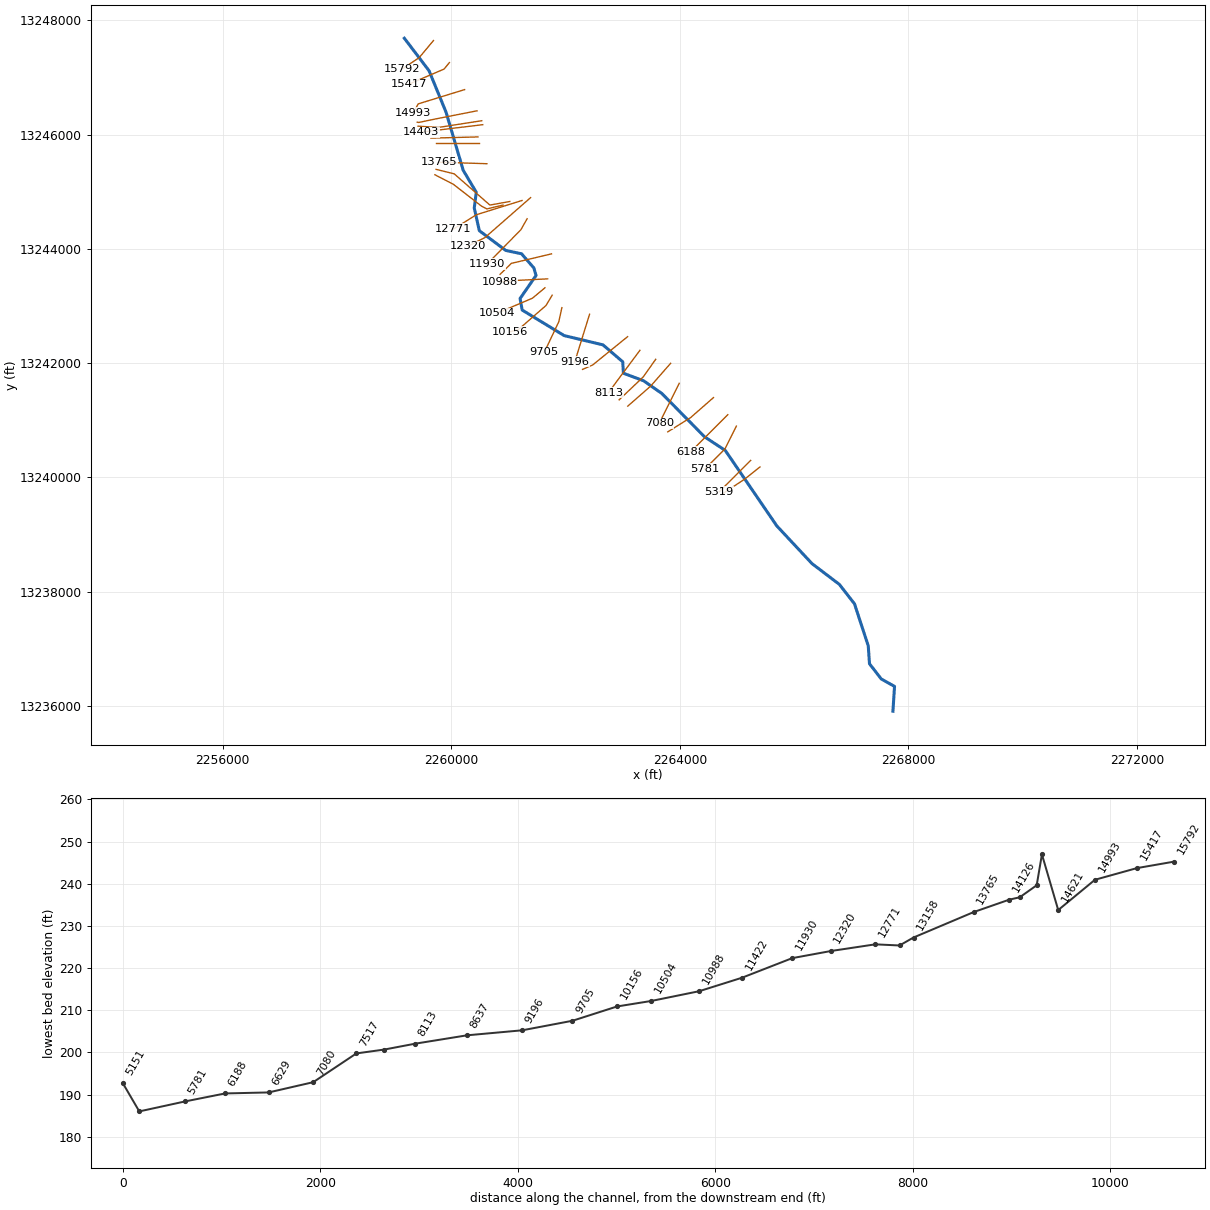
--- UNT 030 IN RACR.prj (project) ---

Proj Title=UNT 030 IN RACR Base Level Engineering
Current Plan=p01
Default Exp/Contr=0.3,0.1
English Units
Geom File=g01
Flow File=f01
Plan File=p01
Y Axis Title=Elevation
X Axis Title(PF)=Main Channel Distance
X Axis Title(XS)=Station
BEGIN DESCRIPTION:
UNT 030 IN RACR
END DESCRIPTION:
DSS Export Rating Curves= 0
DSS Export Rating Curve Sorted= 0
DSS Export Volume Flow Curves= 0
DXF OffsetX= 0
DXF OffsetY= 0
DXF ScaleX= 1
DXF ScaleY= 10

--- UNT 030 IN RACR.p01 (plan) ---

Plan Title=Multiple Run
Short Identifier=Multiple
Geom File=g01
Flow File=f01
Subcritical Flow
K Sum by GR= 0
Std Step Tol= 0.01
Critical Tol= 0.01
Num of Std Step Trials= 20
Max Error Tol= 0.3
Flow Tol Ratio= 0.001
Split Flow NTrial= 30
Split Flow Tol= 0.02
Split Flow Ratio= 0.02
Log Output Level= 0
Friction Slope Method= 1
Unsteady Friction Slope Method= 2
Unsteady Bridges Friction Slope Method= 1
Parabolic Critical Depth
Global Vel Dist=  1 , 1 , 1
Global Log Level= 0
CheckData=True
Encroach Param= -1, 0, 0, 0
BEGIN DESCRIPTION:
Multiple Run
END DESCRIPTION:

--- UNT 030 IN RACR.f01 (steady flow) ---

Flow Title=Multiple
Program Version=4.10
Number of Profiles= 7
Profile Names=10-year,25-year,50-year,1pct_min,100-year,1pct_plu,500-year
River Rch & RM=UNT 030 IN RACR,Reach-1         ,15792
     214     296     365     331     448     606     686
River Rch & RM=UNT 030 IN RACR,Reach-1         ,14993
     350     499     625     576     780    1054    1231
River Rch & RM=UNT 030 IN RACR,Reach-1         ,11930
     464     667     841     779    1054    1425    1680
River Rch & RM=UNT 030 IN RACR,Reach-1         ,5781
     535     772     977     907    1227    1660    1967
Boundary for River Rch & Prof#=UNT 030 IN RACR,Reach-1         , 1
Up Type= 0
Dn Type= 3
Dn Slope=0.005
Boundary for River Rch & Prof#=UNT 030 IN RACR,Reach-1         , 2
Up Type= 0
Dn Type= 3
Dn Slope=0.005
Boundary for River Rch & Prof#=UNT 030 IN RACR,Reach-1         , 3
Up Type= 0
Dn Type= 3
Dn Slope=0.005
Boundary for River Rch & Prof#=UNT 030 IN RACR,Reach-1         , 4
Up Type= 0
Dn Type= 3
Dn Slope=0.005
Boundary for River Rch & Prof#=UNT 030 IN RACR,Reach-1         , 5
Up Type= 0
Dn Type= 3
Dn Slope=0.005
Boundary for River Rch & Prof#=UNT 030 IN RACR,Reach-1         , 6
Up Type= 0
Dn Type= 3
Dn Slope=0.005
Boundary for River Rch & Prof#=UNT 030 IN RACR,Reach-1         , 7
Up Type= 0
Dn Type= 3
Dn Slope=0.005
DSS Import GetInterval= 0
DSS Import GetPeak= 0
DSS Import FillOption= 0

--- UNT 030 IN RACR.g01 (geometry) ---

Geom Title=Existing Conditions
Program Version=4.10

River Reach=UNT 030 IN RACR ,Reach-1
Reach XY= 30
      2259177.72     13247686.85       2259610.3     13247117.31
      2259907.52     13246392.14      2260207.81     13245375.43
      2260436.51     13244990.41      2260401.24     13244715.93
      2260489.89     13244317.72      2260951.69     13243972.27
      2261228.66     13243913.69      2261444.38     13243665.46
      2261482.31     13243534.26      2261203.02     13243130.04
      2261240.16     13242928.42      2261974.95     13242481.56
      2262654.09      13242319.1      2262999.72     13242022.86
      2263010.69     13241822.89       2263363.3     13241691.46
      2263684.11     13241468.54      2264431.66      13240709.5
      2264793.46       13240472.      2265695.65     13239150.18
      2266312.86     13238488.83      2266789.67     13238127.62
      2267055.19     13237785.81      2267295.72     13237051.49
      2267317.72     13236736.86       2267524.2     13236470.19
      2267755.72     13236341.05      2267727.72     13235906.85

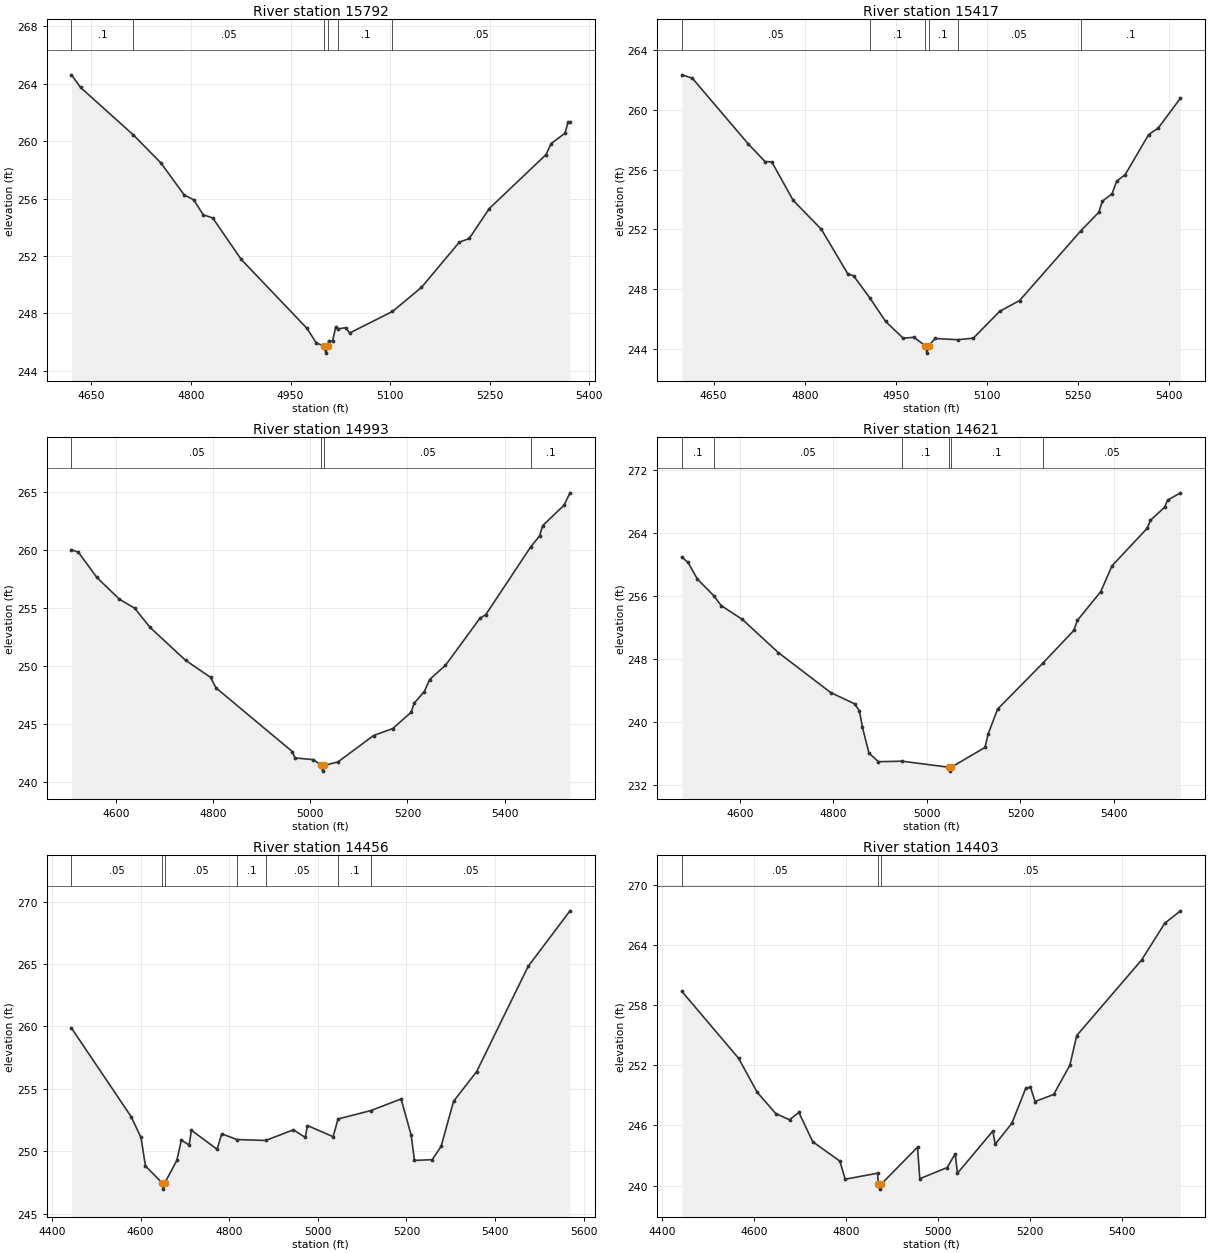
Type RM Length L Ch R = 1 ,15792   ,375,375,375
BEGIN DESCRIPTION:
UNT 030 IN RACR 36.0
END DESCRIPTION:
XS GIS Cut Line= 3
      2259687.73     13247646.86      2259437.72     13247346.85
       2259137.7     13247146.84
#Sta/Elev= 30
    4620  264.61  4633.7  263.73  4713.4  260.42  4754.7  258.48  4789.9  256.25
  4804.2  255.91  4818.5  254.87  4832.8  254.65  4875.8  251.76  4974.7  246.97
    4989  245.94  5000.4  245.74  5003.1  245.24  5006.4  245.74  5007.3  246.09
  5013.5  246.09    5018  247.05  5021.7  246.93  5033.1  247.01  5039.1  246.64
  5103.6  248.14  5147.2  249.81  5204.3  252.96  5219.3  253.22  5249.4   255.3
    5335  259.06  5342.5  259.82  5363.6  260.55  5368.1  261.31  5371.1  261.31
#Mann= 6 ,-1 , 0
    4620      .1       0  4713.4     .05       0  5000.4    .035       0
  5006.4     .05       0  5021.7      .1       0  5103.6     .05       0
Bank Sta=5000.4,5006.4
XS Rating Curve= 0 ,0
Exp/Cntr=0.3,0.1

Type RM Length L Ch R = 1 ,15417   ,424,424,424
BEGIN DESCRIPTION:
UNT 030 IN RACR 35.0
END DESCRIPTION:
XS GIS Cut Line= 3
       2259966.6     13247261.27      2259872.88     13247146.73
      2259253.93     13246881.46
#Sta/Elev= 30
  4597.7  262.35  4614.7  262.13  4706.8  257.73  4734.6  256.54  4745.7  256.52
    4781  253.94  4827.5     252    4871  249.02  4880.7  248.88  4907.6  247.39
  4933.3  245.83  4962.3  244.71  4979.8  244.77  4998.5  244.21  5001.3  243.71
  5004.5  244.21  5014.9  244.69  5051.9  244.61  5077.7  244.71  5121.2  246.51
  5153.9  247.23  5254.8   251.9  5284.4  253.14  5290.5  253.89  5306.2  254.38
  5314.1  255.24  5327.9  255.66  5366.7  258.35  5382.3  258.78  5419.1  260.79
#Mann= 6 ,-1 , 0
  4597.7     .05       0  4907.6      .1       0  4998.5     .07       0
  5004.5      .1       0  5051.9     .05       0  5254.8      .1       0
Bank Sta=4998.5,5004.5
XS Rating Curve= 0 ,0
Exp/Cntr=0.3,0.1

Type RM Length L Ch R = 1 ,14993   ,372,372,372
BEGIN DESCRIPTION:
UNT 030 IN RACR 34.0
END DESCRIPTION:
XS GIS Cut Line= 3
      2260232.28     13246787.36      2259419.75     13246537.35
      2259336.61     13246381.45
#Sta/Elev= 30
    4508  260.05  4522.4  259.82  4560.3  257.65  4606.9  255.77  4638.3     255
  4669.7  253.35  4742.9  250.51  4794.4  249.04  4805.7  248.13  4962.7  242.64
  4968.3  242.09  5006.3  241.94  5022.4  241.45  5025.2  240.95  5028.4  241.45
  5056.8  241.74  5130.1  244.02  5169.7  244.62  5207.7  246.03  5213.8  246.81
  5234.7  247.81  5245.6  248.85  5278.3  250.08  5349.8  254.16  5361.2  254.44
  5453.9  260.29    5472  261.23  5478.5  262.12  5522.4  263.88  5534.8  264.95
#Mann= 4 ,-1 , 0
    4508     .05       0  5022.4    .035       0  5028.4     .05       0
  5453.9      .1       0
Bank Sta=5022.4,5028.4
XS Rating Curve= 0 ,0
Exp/Cntr=0.3,0.1

Type RM Length L Ch R = 1 ,14621   ,165,165,165
BEGIN DESCRIPTION:
Mapping XS b3958466
END DESCRIPTION:
XS GIS Cut Line= 4
      2260450.29     13246416.57      2259721.12     13246273.34
      2259430.32     13246212.58      2259404.26     13246216.92
#Sta/Elev= 30
  4475.9  260.94  4488.7   260.3  4509.1  258.15  4543.8  256.07    4560  254.79
    4605  253.05  4682.3  248.82  4794.4  243.74  4845.4  242.32  4855.6  241.42
  4862.1  239.33    4876  236.06  4896.3  234.97  4947.2  235.03  5046.2  234.27
    5049  233.77  5052.2  234.27  5124.3  236.78  5130.7  238.43  5151.1  241.64
  5247.9  247.48  5314.4  251.65  5321.8  252.91  5371.8  256.56  5396.1  259.86
  5471.7  264.64  5477.9  265.62  5508.5  267.29  5514.9  268.19  5542.5  269.12
#Mann= 6 ,-1 , 0
  4475.9      .1       0  4543.8     .05       0  4947.2      .1       0
  5046.2     .07       0  5052.2      .1       0  5247.9     .05       0
Bank Sta=5046.2,5052.2
XS Rating Curve= 0 ,0
Exp/Cntr=0.3,0.1

Type RM Length L Ch R = 1 ,14456   ,53,53,53
BEGIN DESCRIPTION:
Mapping XS d098a396
END DESCRIPTION:
XS GIS Cut Line= 3
      2260532.79     13246242.96      2259777.54     13246125.77
      2259417.28     13246147.47
#Sta/Elev= 30
  4444.1  259.87  4578.7  252.78    4601  251.11  4611.1  248.82  4648.8  247.47
  4651.6  246.97  4654.8  247.47    4682  249.28  4692.1   250.9  4709.7   250.5
  4714.8  251.69  4772.7  250.16  4783.2   251.4  4817.8  250.94  4882.5  250.87
  4945.1  251.72  4971.7  251.11  4976.8  252.06  5034.7  251.17  5045.7  252.59
  5119.6  253.26    5188  254.19  5210.8   251.3  5218.2  249.27  5258.3  249.33
  5278.3  250.39  5306.5  254.01  5358.5  256.38  5474.8  264.81  5569.3  269.26
#Mann= 7 ,-1 , 0
  4444.1     .05       0  4648.8     .03       0  4654.8     .05       0
  4817.8      .1       0  4882.5     .05       0  5045.7      .1       0
  5119.6     .05       0
Bank Sta=4648.8,4654.8
XS Rating Curve= 0 ,0
Exp/Cntr=0.3,0.1

Type RM Length L Ch R = 1 ,14403   ,172,172,172
BEGIN DESCRIPTION:
UNT 030 IN RACR 33.0
END DESCRIPTION:
XS GIS Cut Line= 2
      2260550.12     13246173.51      2259473.77     13246043.31
#Sta/Elev= 30
  4443.1  259.38  4566.4   252.7  4606.7  249.32    4647  247.19  4677.2  246.56
  4697.3  247.31  4727.6  244.37  4786.5  242.44  4798.1  240.63  4868.4  241.23
  4870.4  240.14  4873.2  239.64  4876.4  240.14  4955.4  243.83  4960.4  240.68
  5019.7  241.79  5037.3  243.16  5042.3  241.23  5119.2  245.44  5124.3  244.13
  5160.7  246.22  5190.9  249.73    5201  249.82  5211.2  248.39  5251.4  249.09
  5286.6     252  5301.7  254.98  5442.7  262.52  5493.1  266.19  5527.3  267.43
#Mann= 3 ,-1 , 0
  4443.1     .05       0  4870.4     .03       0  4876.4     .05       0
Bank Sta=4870.4,4876.4
XS Rating Curve= 0 ,0
Exp/Cntr=0.3,0.1

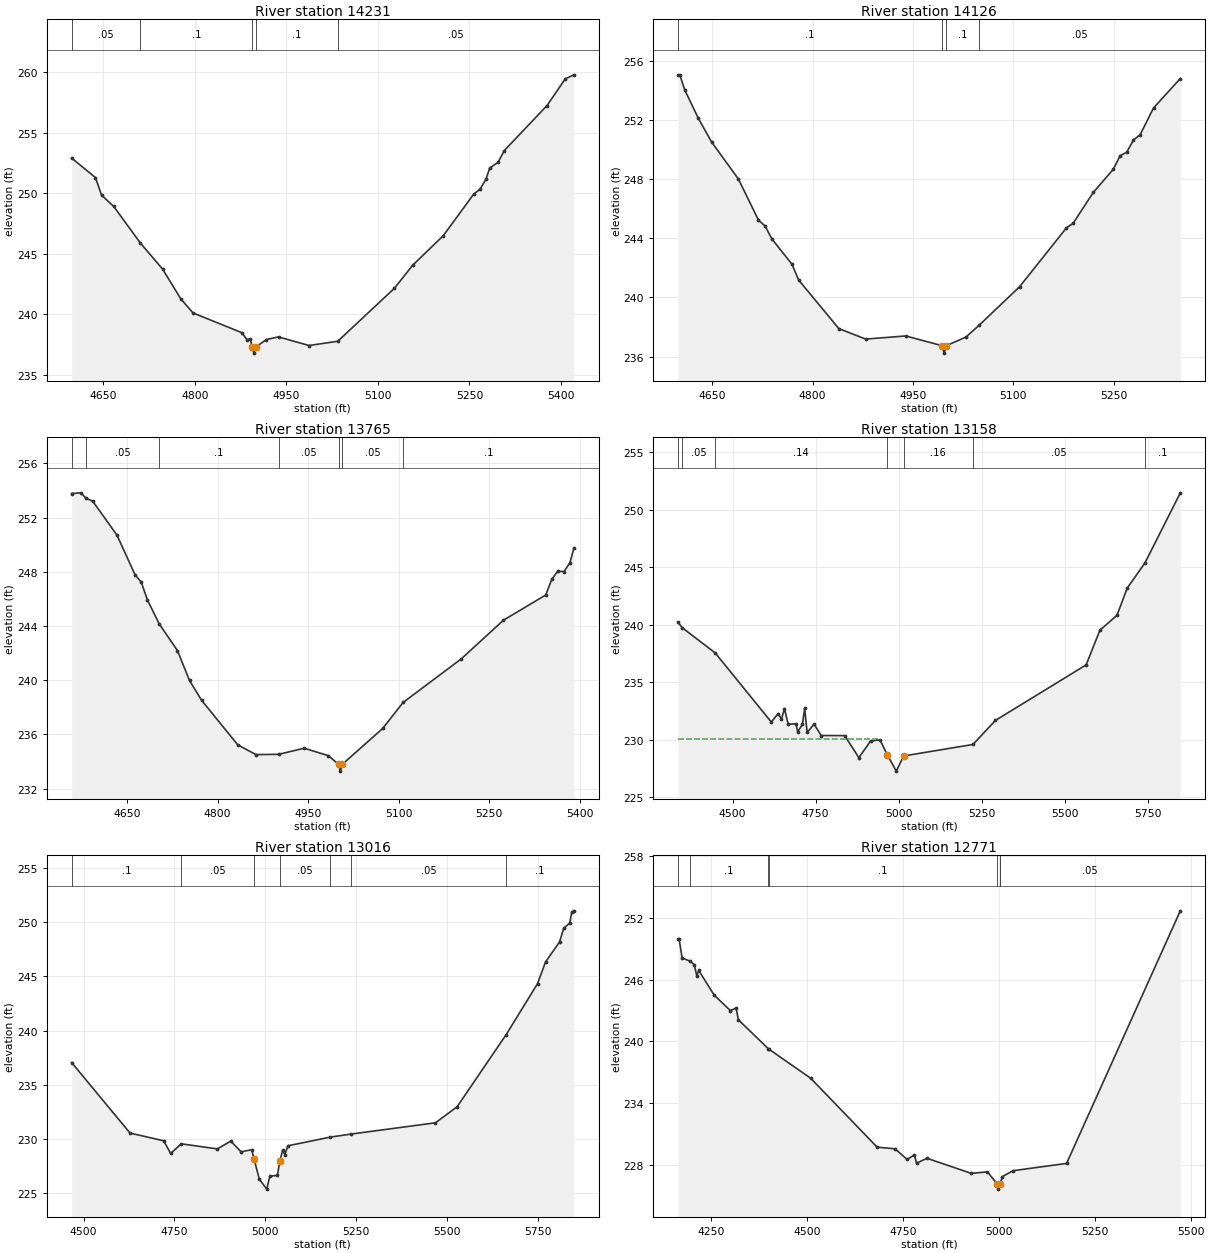
Type RM Length L Ch R = 1 ,14231   ,105,105,105
BEGIN DESCRIPTION:
Mapping XS 21094631
END DESCRIPTION:
XS GIS Cut Line= 2
      2260466.67     13245959.23      2259643.73     13245938.39
#Sta/Elev= 30
    4598  252.91    4637   251.3    4647  249.85    4667  248.91  4710.8  245.88
    4747  243.74    4777  241.27    4797  240.11    4877  238.48  4885.7  237.88
  4890.7  237.98    4894  237.29  4896.8  236.79    4900  237.29    4917  237.91
  4937.1  238.13  4987.1  237.42  5034.2  237.77  5127.1  242.15  5157.1  244.06
  5207.1  246.49  5257.2  249.94  5267.2  250.33  5277.2  251.16  5283.3  252.09
  5297.2  252.57  5307.2  253.53  5377.2  257.25  5407.2  259.46  5421.2  259.79
#Mann= 5 ,-1 , 0
    4598     .05       0  4710.8      .1       0    4894     .07       0
    4900      .1       0  5034.2     .05       0
Bank Sta=4894,4900
XS Rating Curve= 0 ,0
Exp/Cntr=0.3,0.1

Type RM Length L Ch R = 1 ,14126   ,361,361,361
BEGIN DESCRIPTION:
UNT 030 IN RACR 32.0
END DESCRIPTION:
XS GIS Cut Line= 3
      2260487.68     13245846.85      2260087.72     13245846.85
      2259737.68     13245846.85
#Sta/Elev= 30
  4599.3  255.05  4601.8  255.05  4609.3  254.02  4629.3  252.13  4649.3  250.51
  4689.3  248.01  4719.3  245.23  4729.3  244.83  4739.3  243.96  4769.3  242.25
  4779.3  241.18  4839.3   237.9  4879.3  237.19  4939.3   237.4  4993.8  236.74
  4996.5  236.24  4999.8  236.74  5029.3  237.33    5049  238.13  5109.3  240.73
  5179.3  244.71  5189.3  245.02  5219.3   247.1  5249.3  248.67  5259.3  249.58
  5269.3  249.82  5279.3  250.64  5289.3     251  5309.3  252.81  5349.3   254.8
#Mann= 4 ,-1 , 0
  4599.3      .1       0  4993.8     .07       0  4999.8      .1       0
    5049     .05       0
Bank Sta=4993.8,4999.8
XS Rating Curve= 0 ,0
Exp/Cntr=0.3,0.1

Type RM Length L Ch R = 1 ,13765   ,609,609,609
BEGIN DESCRIPTION:
UNT 030 IN RACR 31.0
END DESCRIPTION:
XS GIS Cut Line= 2
      2260622.92     13245490.47      2259791.13     13245516.47
#Sta/Elev= 30
  4558.1  253.78  4573.3  253.83  4581.7  253.44  4593.3   253.2  4633.3   250.7
  4663.4  247.76  4673.4  247.25  4683.4  245.95  4703.2  244.16  4733.4  242.19
  4753.4  239.98  4773.4  238.52  4833.4  235.23  4863.5  234.51    4901  234.53
  4943.5  234.98  4983.5  234.43  5000.5  233.79  5003.3  233.29  5006.5  233.79
  5073.6  236.44  5107.4  238.36  5203.6  241.57  5273.7  244.43  5343.7  246.29
  5353.7  247.44  5363.7  248.05  5373.7  248.01  5383.7  248.66  5390.3  249.73
#Mann= 7 ,-1 , 0
  4558.1      .1       0  4581.7     .05       0  4703.2      .1       0
    4901     .05       0  5000.5     .04       0  5006.5     .05       0
  5107.4      .1       0
Bank Sta=5000.5,5006.5
XS Rating Curve= 0 ,0
Exp/Cntr=0.3,0.1

Type RM Length L Ch R = 1 ,13158   ,142,142,142
BEGIN DESCRIPTION:
UNT 030 IN RACR 30.0
END DESCRIPTION:
XS GIS Cut Line= 4
      2261023.92     13244829.02      2260674.96     13244766.52
      2260049.96     13245313.39      2259732.51     13245391.46
#Sta/Elev= 30
  4335.9   240.2  4348.3  239.74  4447.5  237.55  4616.5  231.53  4636.8  232.27
    4647  231.79  4656.1   232.7  4667.3  231.34  4690.4  231.38    4696  230.69
  4710.2  231.33  4716.8  232.72  4724.4  230.63  4745.3  231.35  4766.5  230.36
  4837.4  230.35  4880.1  228.43  4915.2  229.88  4943.7  229.98  4965.5  228.69
  4992.8  227.26  5014.9  228.58  5223.6  229.58    5291  231.67  5564.4  236.51
  5605.6  239.52  5657.1  240.82    5688  243.19  5741.6  245.39  5847.8  251.48
#Mann= 7 ,-1 , 0
  4335.9      .1       0  4348.3     .05       0  4447.5     .14       0
  4965.5     .07       0  5014.9     .16       0  5223.6     .05       0
  5741.6      .1       0
#XS Ineff= 2 , 0
         4944.59  230.03
Permanent Ineff=
       F       F
Bank Sta=4965.5,5014.9
XS Rating Curve= 0 ,0
Exp/Cntr=0.3,0.1

Type RM Length L Ch R = 1 ,13016   ,245,245,245
BEGIN DESCRIPTION:
Mapping XS 378a52af
END DESCRIPTION:
XS GIS Cut Line= 5
      2260904.18     13244766.53      2260622.88     13244698.81
      2260523.92     13244750.89      2260034.34      13245131.1
      2259712.69     13245297.11
#Sta/Elev= 30
    4467  237.05  4627.9  230.54  4720.5  229.83  4739.6  228.66    4769  229.55
  4868.2  229.08    4905   229.8    4934  228.81  4962.9  229.01  4969.3  228.17
  4983.7   226.3  5004.3  225.37  5012.7  226.56  5033.5  226.64  5040.6  227.99
    5048  228.96  5054.3  228.55  5062.5  229.37  5179.3  230.17  5236.6  230.45
  5468.9  231.49  5528.5  232.97  5663.7  239.63    5750  244.33  5772.2  246.34
  5810.6  248.18  5822.1  249.43  5838.6  249.93  5844.3  250.91    5850  251.05
#Mann= 7 ,-1 , 0
    4467      .1       0    4769     .05       0  4969.3     .03       0
  5040.6     .05       0  5179.3      .1       0  5236.6     .05       0
  5663.7      .1       0
Bank Sta=4969.3,5040.6
XS Rating Curve= 0 ,0
Exp/Cntr=0.3,0.1

Type RM Length L Ch R = 1 ,12771   ,451,451,451
BEGIN DESCRIPTION:
UNT 030 IN RACR 29.0
END DESCRIPTION:
XS GIS Cut Line= 3
       2261237.7     13244846.85      2260437.72     13244596.85
      2260037.74     13244346.87
#Sta/Elev= 30
  4163.6  249.96  4166.2  249.96  4174.1   248.1    4195   247.8  4205.5  247.46
  4212.3  246.39  4217.5  246.89  4257.9  244.48  4299.8     243    4315  243.24
  4320.7   242.1  4398.8  239.29  4400.2  239.25  4509.3  236.42  4682.7  229.72
  4729.3  229.56  4760.8  228.53  4780.1  228.96  4785.4  228.16  4812.6  228.64
  4928.4  227.17  4970.3  227.32  4996.1  226.14  4998.9  225.64  5002.1  226.14
  5002.9  226.14  5009.4  226.86  5037.1  227.43  5176.8  228.14  5473.4  252.69
#Mann= 7 ,-1 , 0
  4163.6     .05       0    4195      .1       0  4398.8     .05       0
  4400.2      .1       0  4996.1     .07       0  5002.1      .1       0
  5002.9     .05       0
Bank Sta=4996.1,5002.1
XS Rating Curve= 0 ,0
Exp/Cntr=0.3,0.1

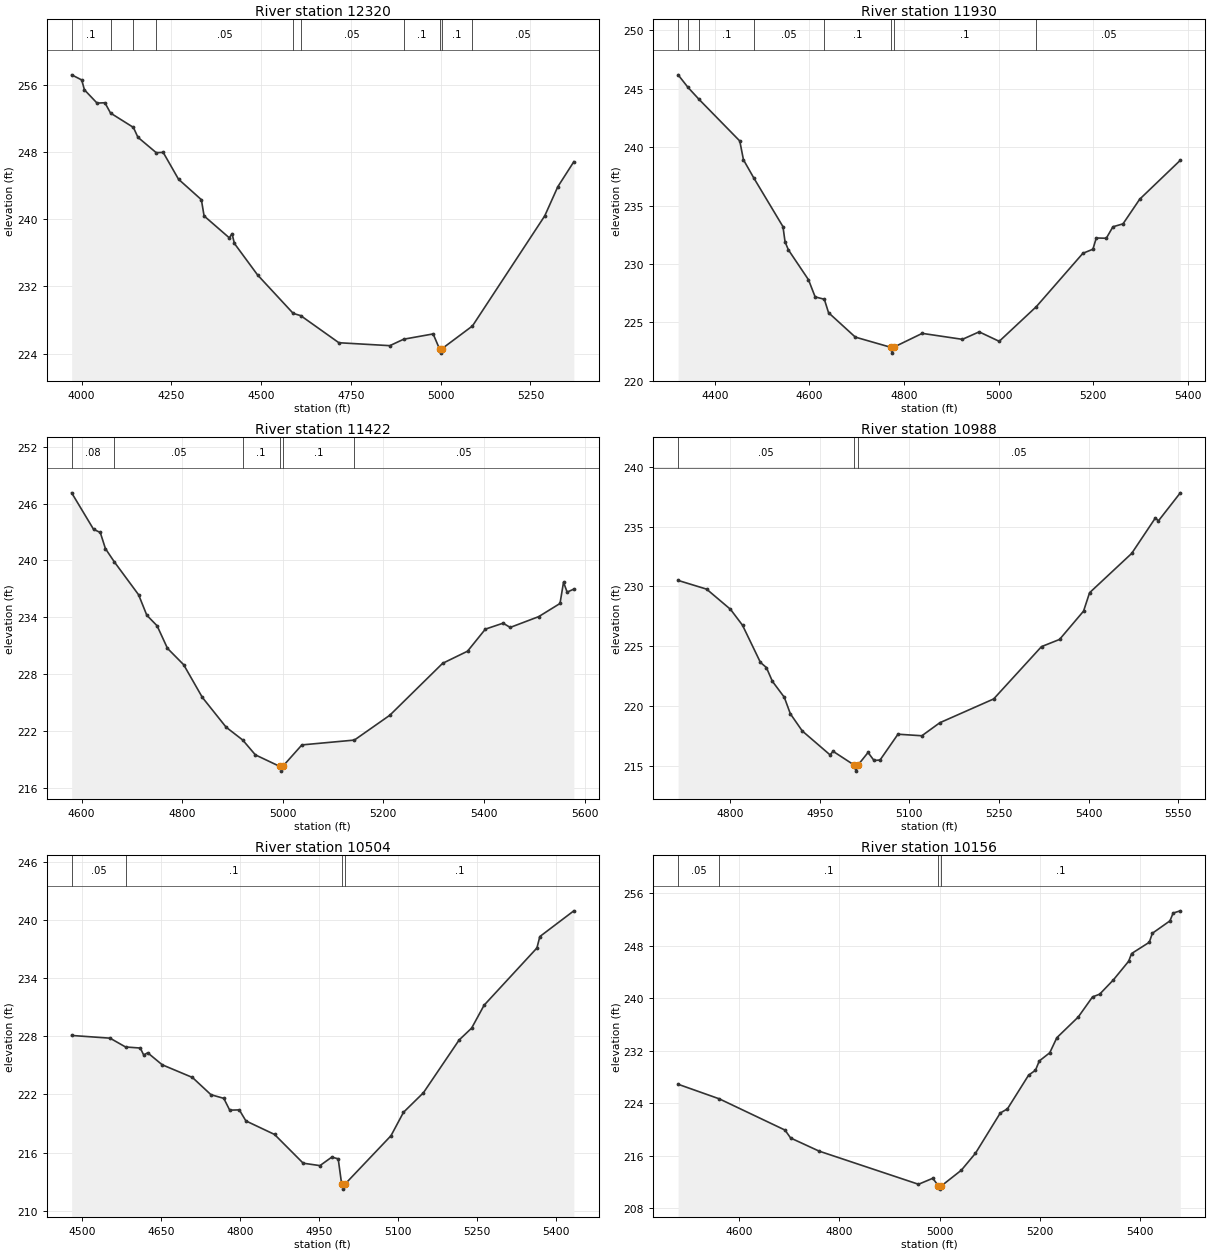
Type RM Length L Ch R = 1 ,12320   ,390,390,390
BEGIN DESCRIPTION:
UNT 030 IN RACR 28.0
END DESCRIPTION:
XS GIS Cut Line= 3
      2261387.74     13244896.87      2260587.72     13244196.85
      2260287.76     13244046.87
#Sta/Elev= 30
  3972.4  257.24  4000.4  256.63    4008  255.45  4043.1  253.87    4065  253.91
  4080.7  252.68  4144.3  250.97    4157  249.79  4207.8  247.96  4227.3  247.99
    4270  244.79  4333.6  242.35  4341.2  240.41  4411.4   237.8    4419   238.3
  4425.6  237.13  4490.2  233.37  4589.3  228.79  4610.3  228.52  4716.5  225.29
  4858.4  224.94    4897  225.71    4979  226.34  4996.8  224.55  4999.6  224.05
  5002.8  224.55  5088.5  227.29  5289.8  240.42  5326.1  243.89  5370.8  246.88
#Mann= 10 ,-1 , 0
  3972.4      .1       0  4080.7     .05       0  4144.3      .1       0
  4207.8     .05       0  4589.3      .1       0  4610.3     .05       0
    4897      .1       0  4996.8     .07       0  5002.8      .1       0
  5088.5     .05       0
Bank Sta=4996.8,5002.8
XS Rating Curve= 0 ,0
Exp/Cntr=0.3,0.1

Type RM Length L Ch R = 1 ,11930   ,508,508,508
BEGIN DESCRIPTION:
UNT 030 IN RACR 27.0
END DESCRIPTION:
XS GIS Cut Line= 3
        2261326.     13244526.93      2261216.63     13244334.23
      2260628.09     13243735.27
#Sta/Elev= 30
  4322.7  246.18  4343.7   245.1  4366.7  244.09    4453  240.52  4460.8  238.91
  4482.3  237.38  4544.3  233.19  4548.7  231.89  4555.7  231.21  4598.2  228.65
  4612.3  227.18  4631.7  226.98  4640.6  225.83  4697.2  223.74    4772  222.87
  4774.8  222.37    4778  222.87  4838.6  224.06  4923.5  223.55  4958.9  224.19
  5001.3  223.38  5079.8  226.35  5178.1  230.91  5199.3  231.26  5206.4  232.22
  5227.6   232.2  5241.6  233.18  5262.9  233.43  5298.2  235.54    5384  238.87
#Mann= 8 ,-1 , 0
  4322.7      .1       0  4343.7     .05       0  4366.7      .1       0
  4482.3     .05       0  4631.7      .1       0    4772     .07       0
    4778      .1       0  5079.8     .05       0
Bank Sta=4772,4778
XS Rating Curve= 0 ,0
Exp/Cntr=0.3,0.1

Type RM Length L Ch R = 1 ,11422   ,434,434,434
BEGIN DESCRIPTION:
UNT 030 IN RACR 26.0
END DESCRIPTION:
XS GIS Cut Line= 3
      2261753.05     13243912.34      2261049.96     13243745.68
      2260852.41     13243553.33
#Sta/Elev= 30
  4580.4  247.13  4623.9  243.28  4637.3  242.94  4647.5  241.24  4664.9  239.86
  4713.5  236.36  4729.8   234.2  4750.3  233.08  4770.9   230.7  4803.1  228.97
  4840.2  225.52  4887.5  222.37  4920.4  221.02  4945.6  219.45    4994  218.23
  4996.7  217.73    5000  218.23  5038.1   220.5  5142.4  221.01  5212.8  223.63
  5317.9  229.12  5367.4   230.4  5402.8  232.73  5438.1  233.36  5452.2  232.91
  5508.8  234.05  5551.2  235.44  5558.2  237.69  5565.4  236.64  5578.7  236.96
#Mann= 6 ,-1 , 0
  4580.4     .08       0  4664.9     .05       0  4920.4      .1       0
    4994     .07       0    5000      .1       0  5142.4     .05       0
Bank Sta=4994,5000
XS Rating Curve= 0 ,0
Exp/Cntr=0.3,0.1

Type RM Length L Ch R = 1 ,10988   ,484,484,484
BEGIN DESCRIPTION:
UNT 030 IN RACR 25.0
END DESCRIPTION:
XS GIS Cut Line= 3
      2261685.34     13243474.85       2261070.8      13243443.6
      2260846.84     13243417.56
#Sta/Elev= 30
  4712.8  230.49  4760.5  229.76  4800.5  228.07  4820.6  226.74  4850.6  223.63
  4860.6   223.2  4870.6  222.05  4890.6  220.71  4900.7  219.33  4920.7  217.89
  4967.2  215.89  4972.2  216.19  5007.8  215.03  5010.6  214.53  5013.8  215.03
  5030.8  216.09  5040.8  215.42  5050.9  215.46  5080.9  217.62  5120.9  217.49
    5151  218.58  5241.1  220.57  5321.2  224.95  5351.4  225.55  5391.6  227.92
  5401.7  229.46  5472.2  232.75  5511.9  235.72  5516.9  235.47  5553.6  237.82
#Mann= 3 ,-1 , 0
  4712.8     .05       0  5007.8     .03       0  5013.8     .05       0
Bank Sta=5007.8,5013.8
XS Rating Curve= 0 ,0
Exp/Cntr=0.3,0.1

Type RM Length L Ch R = 1 ,10504   ,348,348,348
BEGIN DESCRIPTION:
UNT 030 IN RACR 24.0
END DESCRIPTION:
XS GIS Cut Line= 3
      2261638.48     13243318.58      2261419.75     13243136.31
      2260805.17     13242875.89
#Sta/Elev= 30
  4480.9   228.1  4553.7  227.82  4583.1  226.91    4611   226.8  4617.5  226.08
  4625.1  226.31  4652.6  225.07  4709.9  223.76    4745  221.98  4769.4   221.6
  4780.6  220.38  4798.8  220.41  4811.3  219.27  4865.6  217.87  4919.9   214.9
  4951.7  214.65  4974.2  215.53  4986.3  215.35  4992.9  212.72  4995.6  212.22
  4998.9  212.72  5086.4  217.74  5110.1  220.16  5147.9  222.18  5215.7  227.64
  5239.3  228.86    5263  231.23  5363.1  237.14  5368.6  238.32  5433.1  240.98
#Mann= 4 ,-1 , 0
  4480.9     .05       0  4583.1      .1       0  4992.9     .07       0
  4998.9      .1       0
Bank Sta=4992.9,4998.9
XS Rating Curve= 0 ,0
Exp/Cntr=0.3,0.1

Type RM Length L Ch R = 1 ,10156   ,451,451,451
BEGIN DESCRIPTION:
UNT 030 IN RACR 23.0
END DESCRIPTION:
XS GIS Cut Line= 4
      2261765.06     13243188.81      2261656.05      13243007.9
      2261169.06     13242583.52      2261027.64     13242548.74
#Sta/Elev= 30
    4478  226.89  4560.5  224.66  4691.4  219.91  4702.7   218.7  4759.6   216.7
    4958  211.65  4986.5  212.56  4997.8  211.41  5000.5  210.91  5003.8  211.41
  5043.5  213.79  5071.7  216.37  5121.3  222.51  5135.6  223.14  5177.8  228.27
  5191.6  229.03  5199.2  230.44  5220.1  231.69  5234.3  233.99    5277  237.14
  5305.5   240.2  5319.8  240.62  5347.1  242.79  5377.7  245.64  5383.5  246.81
  5418.9  248.53    5425   249.9  5460.1  251.79  5466.5  252.98  5480.8  253.32
#Mann= 4 ,-1 , 0
    4478     .05       0  4560.5      .1       0  4997.8     .07       0
  5003.8      .1       0
Bank Sta=4997.8,5003.8
XS Rating Curve= 0 ,0
Exp/Cntr=0.3,0.1

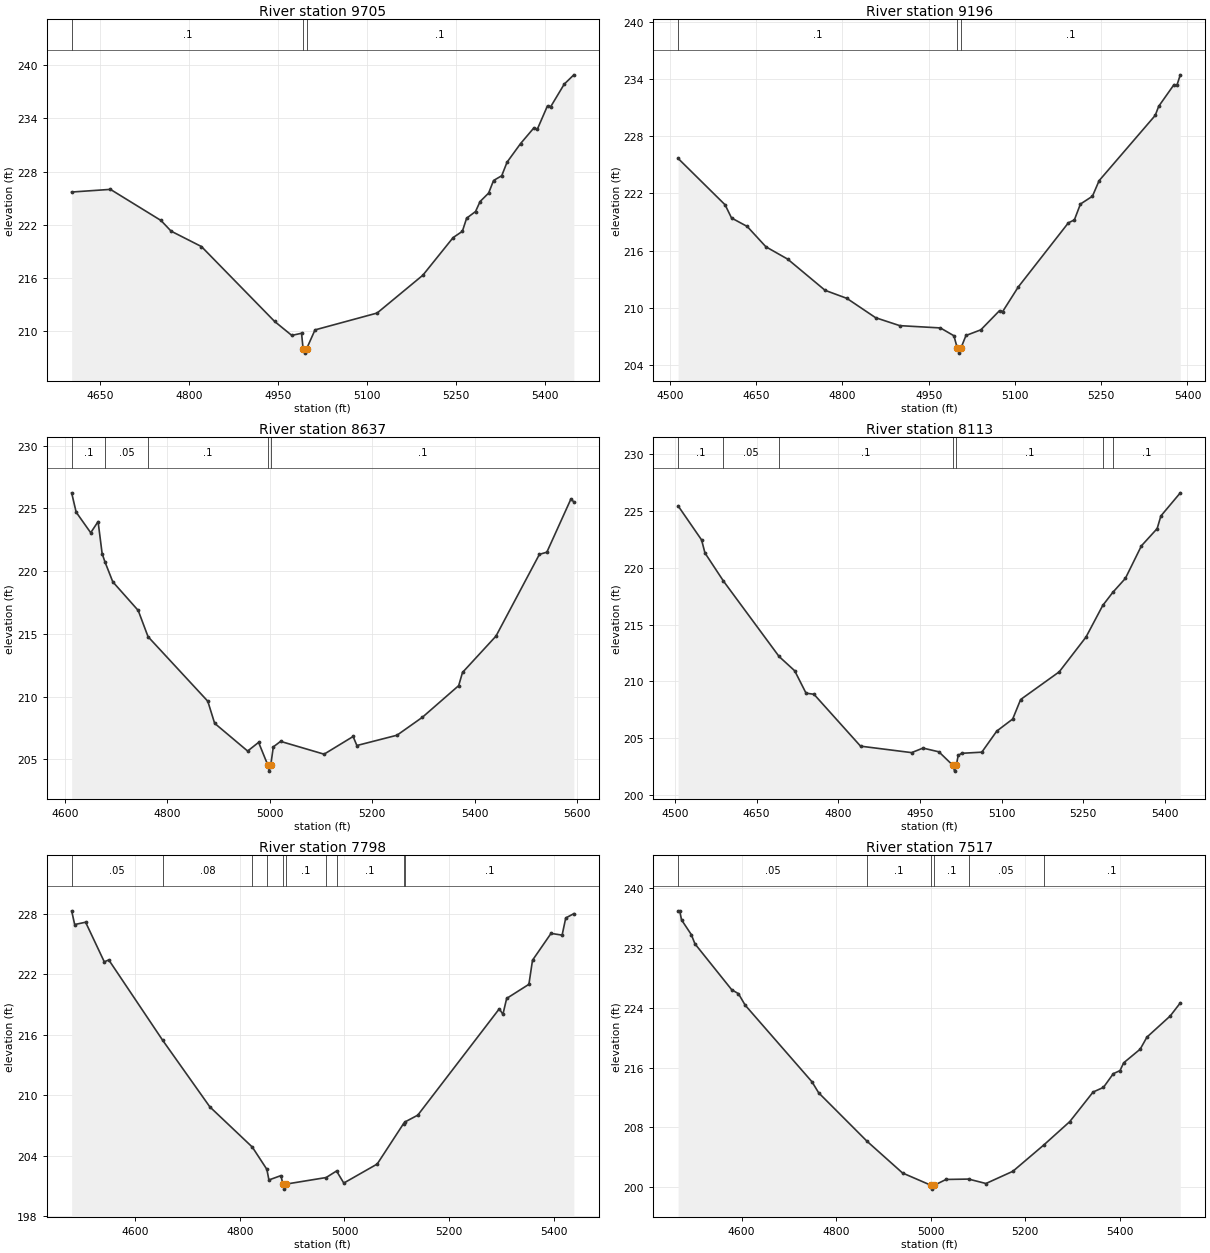
Type RM Length L Ch R = 1 ,9705    ,509,509,509
BEGIN DESCRIPTION:
UNT 030 IN RACR 22.0
END DESCRIPTION:
XS GIS Cut Line= 3
      2261934.33     13242970.78      2261880.99     13242724.98
      2261625.92     13242187.01
#Sta/Elev= 30
  4602.3  225.69  4667.7  225.99    4753  222.48    4770  221.28  4821.2  219.54
  4944.5   211.1  4973.5  209.52    4990  209.76  4992.6  208.02  4995.4  207.52
  4998.6  208.02  5012.7  210.14  5117.4  212.04  5194.6  216.31  5245.6  220.55
  5261.2  221.26  5268.4  222.74  5283.4  223.49  5291.1  224.62  5305.5  225.57
  5313.8  226.99  5327.6  227.53  5336.6  229.06  5359.3  231.15    5382  232.94
  5387.6  232.77  5404.8  235.42  5410.3  235.33    5433  237.86  5449.2  238.91
#Mann= 3 ,-1 , 0
  4602.3      .1       0  4992.6     .07       0  4998.6      .1       0
Bank Sta=4992.6,4998.6
XS Rating Curve= 0 ,0
Exp/Cntr=0.3,0.1

Type RM Length L Ch R = 1 ,9196    ,559,559,559
BEGIN DESCRIPTION:
UNT 030 IN RACR 21.0
END DESCRIPTION:
XS GIS Cut Line= 2
      2262418.99     13242854.82      2262159.57     13242020.94
#Sta/Elev= 30
  4514.2  225.66  4595.9   220.8  4607.1  219.42  4634.4  218.53  4666.9   216.4
  4704.7  215.11  4769.8  211.84  4807.6     211  4857.7  208.97  4899.6  208.14
  4970.3   207.9  4993.8  207.08  4999.8  205.76  5002.6  205.26  5005.8  205.76
  5014.8  207.11  5040.6   207.7  5073.1  209.71  5078.4   209.6  5105.7  212.19
  5192.8  218.91  5203.3  219.22  5213.8  220.88  5234.7   221.7  5246.3  223.33
  5343.9  230.17  5349.9  231.12  5376.5  233.39  5381.7  233.35  5387.5  234.42
#Mann= 3 ,-1 , 0
  4514.2      .1       0  4999.8     .07       0  5005.8      .1       0
Bank Sta=4999.8,5005.8
XS Rating Curve= 0 ,0
Exp/Cntr=0.3,0.1

Type RM Length L Ch R = 1 ,8637    ,524,524,524
BEGIN DESCRIPTION:
UNT 030 IN RACR 20.0
END DESCRIPTION:
XS GIS Cut Line= 3
      2263084.53     13242462.92      2262472.34     13241966.67
       2262296.1     13241890.14
#Sta/Elev= 30
  4613.4  226.24  4622.2   224.7  4650.6  223.06    4665  223.95  4672.9   221.4
  4678.2  220.76  4693.7  219.15  4743.3  216.87  4762.5  214.78  4879.1  209.64
  4892.5  207.88  4956.9  205.67  4978.3  206.36  4996.1  204.57  4998.8  204.07
  5002.1  204.57    5007     206  5021.2  206.44  5106.1  205.42  5162.8  206.83
  5170.1  206.11  5248.4  206.93    5298  208.36  5368.8  210.88  5376.3  211.93
  5441.7  214.83  5526.4  221.34  5540.9  221.51  5587.8  225.74  5593.6  225.52
#Mann= 5 ,-1 , 0
  4613.4      .1       0  4678.2     .05       0  4762.5      .1       0
  4996.1     .07       0  5002.1      .1       0
Bank Sta=4996.1,5002.1
XS Rating Curve= 0 ,0
Exp/Cntr=0.3,0.1

Type RM Length L Ch R = 1 ,8113    ,315,315,315
BEGIN DESCRIPTION:
UNT 030 IN RACR 19.0
END DESCRIPTION:
XS GIS Cut Line= 3
      2263300.21     13242224.06      2262852.65     13241623.46
      2262752.42     13241482.22
#Sta/Elev= 30
  4505.9  225.46    4549  222.46  4555.2  221.31  4589.1  218.84  4691.3  212.19
    4720  210.93  4740.8  208.96  4755.4  208.86  4840.9  204.29  4934.7  203.72
  4955.6  204.12  4984.8  203.79  5010.7  202.59  5013.5  202.09  5016.7  202.59
  5020.2  203.47  5026.5  203.66  5063.6  203.76  5091.1  205.62  5120.3  206.68
  5134.9   208.4  5205.8  210.84  5254.9   213.9  5285.7  216.69  5304.3  217.85
  5327.2  219.07  5356.7  221.94  5385.6  223.46  5392.4  224.57  5428.1  226.61
#Mann= 7 ,-1 , 0
  4505.9      .1       0  4589.1     .05       0  4691.3      .1       0
  5010.7     .07       0  5016.7      .1       0  5285.7     .05       0
  5304.3      .1       0
Bank Sta=5010.7,5016.7
XS Rating Curve= 0 ,0
Exp/Cntr=0.3,0.1

Type RM Length L Ch R = 1 ,7798    ,281,281,281
BEGIN DESCRIPTION:
UNT 030 IN RACR 18.0
END DESCRIPTION:
XS GIS Cut Line= 3
       2263576.2     13242066.42      2263355.87     13241755.64
      2262936.13     13241356.76
#Sta/Elev= 30
  4478.5   228.3  4484.3  226.94  4505.2  227.17  4540.9  223.24  4549.5  223.43
  4652.2  215.48  4742.7  208.85  4823.9  204.86  4851.7  202.65  4855.6   201.6
  4878.5  202.03  4882.4  201.19  4885.2  200.69  4888.4  201.19    4965  201.84
  4984.9  202.49  4998.7  201.29  5062.6  203.18  5113.1   207.2  5116.6  207.38
  5140.2  208.03    5296  218.58  5302.9  218.03  5310.1  219.61  5352.6  221.01
  5359.5   223.4  5394.9  226.06  5416.1  225.89    5423  227.59  5438.5  228.02
#Mann= 10 ,-1 , 0
  4478.5     .05       0  4652.2     .08       0  4823.9     .05       0
  4851.7      .1       0  4882.4     .07       0  4888.4      .1       0
    4965     .05       0  4984.9      .1       0  5113.1     .05       0
  5116.6      .1       0
Bank Sta=4882.4,4888.4
XS Rating Curve= 0 ,0
Exp/Cntr=0.3,0.1

Type RM Length L Ch R = 1 ,7517    ,437,437,437
BEGIN DESCRIPTION:
UNT 030 IN RACR 17.0
END DESCRIPTION:
XS GIS Cut Line= 3
      2263837.74     13241996.88      2263487.72     13241596.85
      2263087.76     13241246.89
#Sta/Elev= 30
  4465.7   236.9  4469.1   236.9  4472.9   235.7  4493.7  233.72  4501.3   232.5
  4579.2  226.37  4593.4  225.85  4607.6  224.32    4749   214.1  4763.3  212.62
    4866  206.14  4940.8  201.93  5001.4  200.28  5004.1  199.78  5007.4  200.28
  5032.8  201.07  5080.6  201.12  5117.3  200.53  5174.3  202.16  5239.6  205.66
  5294.8  208.79  5344.1  212.73    5366  213.35  5386.9  215.18  5401.1  215.59
  5408.7  216.62  5443.8  218.45    5458  220.05  5507.4  222.88  5528.7  224.62
#Mann= 6 ,-1 , 0
  4465.7     .05       0    4866      .1       0  5001.4     .07       0
  5007.4      .1       0  5080.6     .05       0  5239.6      .1       0
Bank Sta=5001.4,5007.4
XS Rating Curve= 0 ,0
Exp/Cntr=0.3,0.1

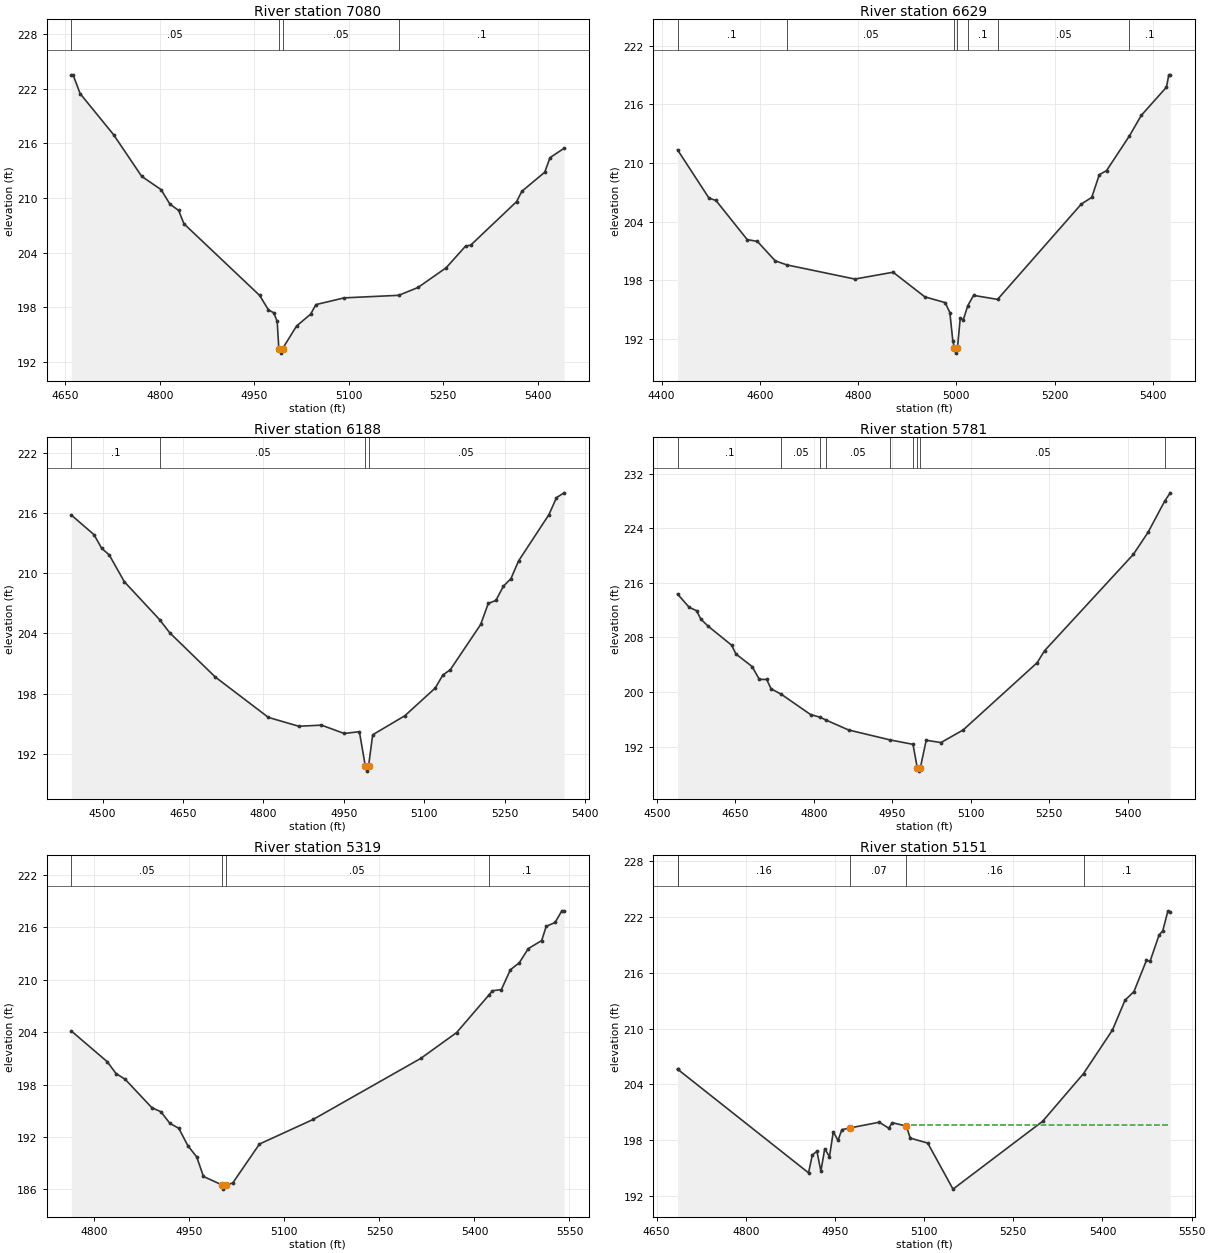
Type RM Length L Ch R = 1 ,7080    ,451,451,451
BEGIN DESCRIPTION:
UNT 030 IN RACR 16.0
END DESCRIPTION:
XS GIS Cut Line= 3
      2263987.73     13241646.87      2263837.72     13241346.85
      2263637.74     13240946.89
#Sta/Elev= 30
  4659.5  223.53  4662.3  223.53  4673.5  221.47  4726.6  216.96  4771.3  212.38
  4802.1  210.92    4816  209.34    4830  208.63  4838.4  207.17  4958.6   199.3
  4972.6  197.71    4981  197.39  4986.5  196.45  4989.1  193.46  4991.9  192.96
  4995.1  193.46  5017.3  195.94  5039.6  197.24    5048  198.29  5092.8  199.03
  5179.5  199.31  5210.1  200.17  5254.9  202.34  5285.6  204.71    5294  204.83
  5366.7   209.6  5375.1  210.74  5411.4  212.83  5419.8  214.43  5442.1  215.46
#Mann= 4 ,-1 , 0
  4659.5     .05       0  4989.1     .03       0  4995.1     .05       0
  5179.5      .1       0
Bank Sta=4989.1,4995.1
XS Rating Curve= 0 ,0
Exp/Cntr=0.3,0.1

Type RM Length L Ch R = 1 ,6629    ,441,441,441
BEGIN DESCRIPTION:
UNT 030 IN RACR 15.0
END DESCRIPTION:
XS GIS Cut Line= 3
       2264587.7     13241396.83      2264187.72     13241046.85
       2263787.7     13240796.84
#Sta/Elev= 30
  4432.4  211.34  4496.4   206.4  4510.7  206.15  4574.3  202.15  4595.1  201.96
  4631.2  199.98  4654.9  199.56  4793.5  198.11  4871.3  198.81  4935.9  196.29
  4977.4   195.7  4986.9  194.68  4992.8  191.82  4996.3  191.03    4999  190.53
  5002.3  191.03  5008.1  194.14    5014  193.91  5023.5   195.4  5035.2  196.44
    5084  196.03  5254.6  205.79  5275.8  206.47  5291.1  208.79  5305.9  209.21
  5352.6  212.77  5376.6  214.86  5427.9  217.75  5432.6  219.01  5435.6  219.01
#Mann= 7 ,-1 , 0
  4432.4      .1       0  4654.9     .05       0  4996.3     .03       0
  5002.3     .05       0  5023.5      .1       0    5084     .05       0
  5352.6      .1       0
Bank Sta=4996.3,5002.3
XS Rating Curve= 0 ,0
Exp/Cntr=0.3,0.1

Type RM Length L Ch R = 1 ,6188    ,407,407,407
BEGIN DESCRIPTION:
UNT 030 IN RACR 14.0
END DESCRIPTION:
XS GIS Cut Line= 3
      2264837.72     13241096.86      2264437.72     13240696.85
      2264187.75     13240446.88
#Sta/Elev= 30
  4441.6   215.8    4484  213.84  4498.2  212.49  4512.3  211.83  4540.6  209.15
  4606.3  205.38  4625.4  204.06  4710.3  199.66  4809.3  195.64  4865.9  194.76
  4908.3  194.87  4950.7  194.04    4979  194.22  4990.1  190.79  4992.9  190.29
  4996.1  190.79  5003.8  193.91  5063.9  195.81  5120.4  198.56  5134.6  199.85
  5148.7   200.4  5205.3   204.9  5219.4  206.99  5233.6  207.29  5247.7  208.71
  5261.8  209.47    5276  211.23  5332.6  215.84  5346.7  217.53  5360.8  218.01
#Mann= 4 ,-1 , 0
  4441.6      .1       0  4606.3     .05       0  4990.1     .03       0
  4996.1     .05       0
Bank Sta=4990.1,4996.1
XS Rating Curve= 0 ,0
Exp/Cntr=0.3,0.1

Type RM Length L Ch R = 1 ,5781    ,462,462,462
BEGIN DESCRIPTION:
UNT 030 IN RACR 13.0
END DESCRIPTION:
XS GIS Cut Line= 3
      2264987.73     13240896.87      2264787.72     13240496.85
      2264437.72     13240146.86
#Sta/Elev= 30
  4539.4  214.37  4561.8  212.42  4575.8  211.93  4584.1  210.68  4598.1  209.65
  4642.8  206.87  4651.2  205.57    4682  203.74  4695.9  201.85  4709.9  201.84
  4718.3  200.47  4738.2  199.65  4793.8  196.69  4812.3  196.29  4822.6  195.91
  4866.4  194.43  4945.9  192.97  4989.7  192.32  4997.8  188.89  5000.5  188.39
  5003.8  188.89  5014.9  192.92  5043.2  192.58  5085.6  194.43    5227  204.29
  5241.2  206.05  5410.9  220.18  5439.2  223.43  5471.2  228.04  5481.6  229.22
#Mann= 9 ,-1 , 0
  4539.4      .1       0  4738.2     .05       0  4812.3      .1       0
  4822.6     .05       0  4945.9      .1       0  4989.7     .05       0
  4997.8     .03       0  5003.8     .05       0  5471.2      .1       0
Bank Sta=4997.8,5003.8
XS Rating Curve= 0 ,0
Exp/Cntr=0.3,0.1

Type RM Length L Ch R = 1 ,5319    ,168,168,168
BEGIN DESCRIPTION:
UNT 030 IN RACR 12.0
END DESCRIPTION:
XS GIS Cut Line= 3
      2265237.74     13240296.88      2265087.72     13240146.85
      2264687.75     13239746.89
#Sta/Elev= 30
  4763.6  204.13  4820.2  200.62  4834.3  199.25  4848.5  198.61  4890.9  195.34
    4905  194.89  4919.2  193.56  4933.3  192.99  4947.5  191.01  4961.6  189.71
  4972.2  187.48    5001  186.53  5003.8  186.03    5007  186.53  5018.2  186.71
  5060.6  191.19  5145.5  194.01  5315.2  200.99  5371.7  203.94    5423  208.26
  5428.3  208.73  5442.5  208.87  5456.6  211.13  5470.7  211.93  5484.9  213.55
  5506.1  214.48  5513.2   216.1  5527.3  216.55  5537.9  217.88  5541.4  217.88
#Mann= 4 ,-1 , 0
  4763.6     .05       0    5001     .03       0    5007     .05       0
    5423      .1       0
Bank Sta=5001,5007
XS Rating Curve= 0 ,0
Exp/Cntr=0.3,0.1

Type RM Length L Ch R = 1 ,5151    ,72,72,72
BEGIN DESCRIPTION:
Mapping XS e2c45200
END DESCRIPTION:
XS GIS Cut Line= 3
       2265401.1     13240182.32      2265134.21     13239969.68
      2264727.22     13239701.23
#Sta/Elev= 30
  4685.2  205.64  4685.4  205.64  4905.6  194.52    4912  196.45  4919.7  196.83
  4926.4  194.69  4932.8  197.11  4940.8  196.25  4947.2  198.93  4955.2     198
  4961.6  199.15    4976  199.35  5024.7  199.95  5040.4  199.31  5046.4   199.9
  5070.2  199.54  5076.6  198.25  5106.1  197.71  5148.6  192.77  5299.3  200.05
  5368.1  205.17  5416.8  209.85  5437.9  213.05  5452.9  213.97    5474  217.33
    5480  217.22  5495.1  220.03  5501.4   220.5  5510.1  222.64    5514  222.48
#Mann= 5 ,-1 , 0
  4685.2      .1       0  4685.4     .16       0    4976     .07       0
  5070.2     .16       0  5368.1      .1       0
#XS Ineff= 2 , 0
       0 4978.38  199.13 5071.74       0  199.63
Permanent Ineff=
       T       T
Bank Sta=4976,5070.2
XS Rating Curve= 0 ,0
Exp/Cntr=0.3,0.1