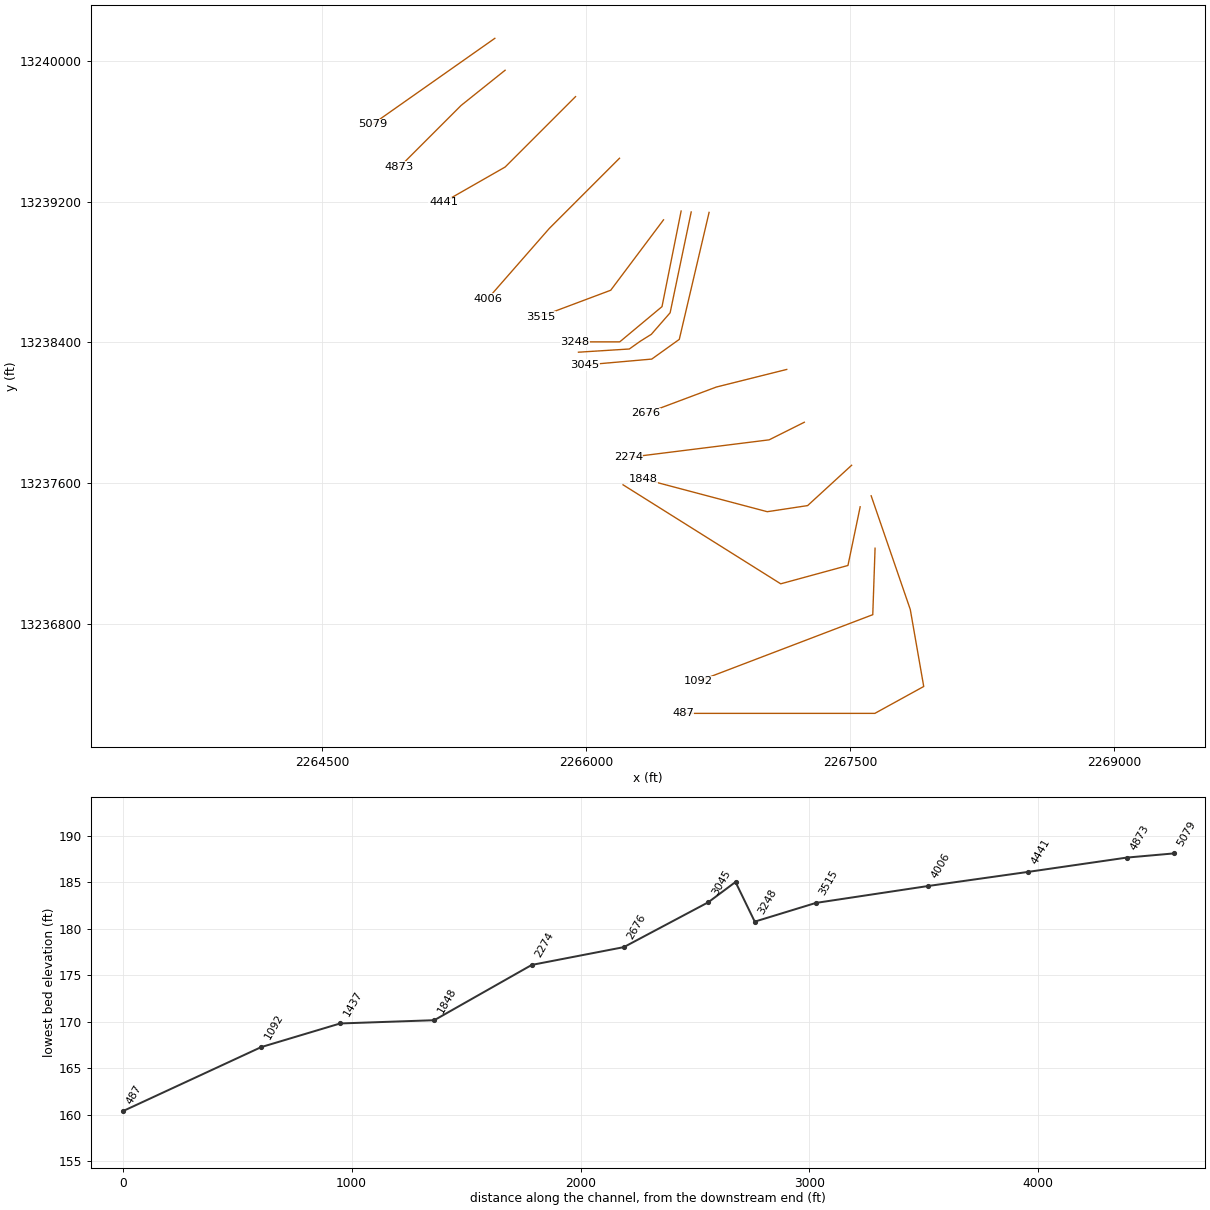
HEC-RAS study UNT 030 IN RACR.prj: UNT 030 IN RACR Base Level Engineering

--- UNT 030 IN RACR.g01 (geometry) --- (continued)

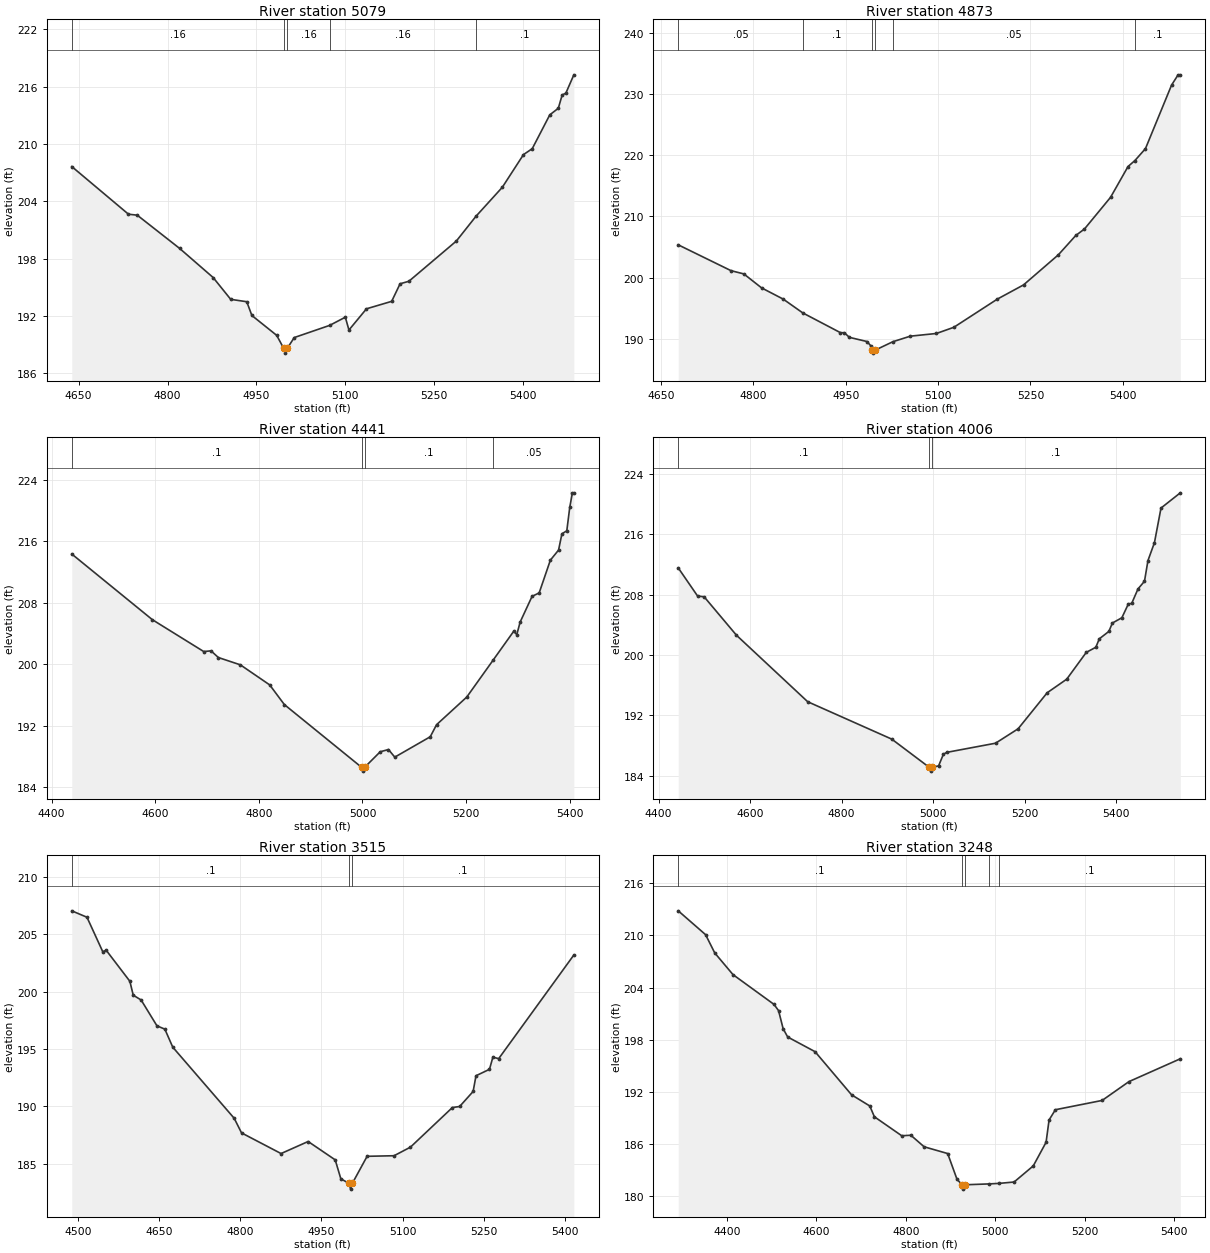
Type RM Length L Ch R = 1 ,5079    ,206,206,206
BEGIN DESCRIPTION:
Mapping XS d3322e6e
END DESCRIPTION:
XS GIS Cut Line= 2
      2265479.28     13240128.11      2264786.25     13239640.82
#Sta/Elev= 30
  4638.4  207.63  4734.1  202.64  4748.9  202.54  4820.4  199.06    4877  196.01
  4906.6  193.73  4933.7  193.48  4942.3  192.04  4984.2  189.96    4996   188.6
  4998.7   188.1    5002   188.6  5013.8  189.73  5073.4     191    5100  191.86
  5106.1  190.52  5135.7  192.74  5178.2  193.52  5192.4  195.36  5207.2  195.62
  5287.3  199.83  5320.4  202.42  5364.9  205.46  5400.6  208.88  5415.4   209.5
    5445  213.04  5459.4  213.73  5465.9  215.12  5472.1  215.31  5485.6  217.23
#Mann= 5 ,-1 , 0
  4638.4     .16       0    4996     .07       0    5002     .16       0
  5073.4     .16       0  5320.4      .1       0
Bank Sta=4996,5002
XS Rating Curve= 0 ,0
Exp/Cntr=0.3,0.1

Type RM Length L Ch R = 1 ,4873    ,432,432,432
BEGIN DESCRIPTION:
UNT 030 IN RACR 11.0
END DESCRIPTION:
XS GIS Cut Line= 3
      2265537.74     13239946.87      2265287.72     13239746.85
      2264937.69     13239396.82
#Sta/Elev= 30
  4678.1  205.34  4763.8  201.12  4784.6  200.59  4813.4  198.31  4848.6  196.47
  4880.3  194.22  4941.5  190.99  4947.9  190.98  4955.9  190.23  4984.7  189.54
  4991.1   188.8  4992.1  188.15  4994.8  187.65  4998.1  188.15  5026.5  189.51
  5054.9  190.42  5097.3  190.86  5125.6  191.87  5196.3  196.48  5238.7  198.79
  5295.3  203.71  5323.6  206.87  5337.7  207.93  5380.1  213.11  5408.4  218.13
  5419.6  219.11  5436.7  221.05  5479.1  231.43  5489.7  233.11  5493.3  233.11
#Mann= 6 ,-1 , 0
  4678.1     .05       0  4880.3      .1       0  4992.1     .07       0
  4998.1      .1       0  5026.5     .05       0  5419.6      .1       0
Bank Sta=4992.1,4998.1
XS Rating Curve= 0 ,0
Exp/Cntr=0.3,0.1

Type RM Length L Ch R = 1 ,4441    ,435,435,435
BEGIN DESCRIPTION:
UNT 030 IN RACR 10.0
END DESCRIPTION:
XS GIS Cut Line= 3
      2265937.75     13239796.88      2265537.72     13239396.85
      2265187.75     13239196.87
#Sta/Elev= 30
  4439.1  214.36  4594.7  205.81  4693.7  201.67  4707.8  201.76    4722  200.89
  4764.4  199.94    4821  197.33  4849.3  194.77  4998.3  186.61    5001  186.11
  5004.3  186.61  5034.3  188.63  5050.2  188.92  5062.4  187.93  5130.8  190.58
    5143  192.15  5201.3  195.75  5251.8  200.52    5292  204.32  5297.8  203.87
  5304.3  205.51  5327.3  208.85    5341   209.3  5362.6  213.56  5378.4  214.87
  5384.9  216.99  5394.3  217.38    5400  220.43  5405.1  222.32  5407.9  222.32
#Mann= 4 ,-1 , 0
  4439.1      .1       0  4998.3     .07       0  5004.3      .1       0
  5251.8     .05       0
Bank Sta=4998.3,5004.3
XS Rating Curve= 0 ,0
Exp/Cntr=0.3,0.1

Type RM Length L Ch R = 1 ,4006    ,491,491,491
BEGIN DESCRIPTION:
UNT 030 IN RACR 9.0
END DESCRIPTION:
XS GIS Cut Line= 3
      2266187.73     13239446.86      2265787.72     13239046.85
      2265437.72     13238646.86
#Sta/Elev= 30
    4443  211.54  4485.4   207.8  4499.6  207.71  4570.3  202.61  4725.9   193.8
  4909.7  188.84  4991.6   185.1  4994.3   184.6  4997.6   185.1    5012   185.3
  5022.5  186.84    5030  187.09  5136.4   188.3  5185.7  190.21  5249.3  194.99
    5292  196.79  5334.7  200.34  5355.6  201.02  5363.2  202.14  5384.1  203.12
  5391.7  204.23  5412.5  204.93  5426.8  206.78  5433.9  206.82  5447.7  208.75
  5461.9  209.77  5469.5  212.51  5483.7  214.89    5498  219.47  5540.2  221.49
#Mann= 3 ,-1 , 0
    4443      .1       0  4991.6     .07       0  4997.6      .1       0
Bank Sta=4991.6,4997.6
XS Rating Curve= 0 ,0
Exp/Cntr=0.3,0.1

Type RM Length L Ch R = 1 ,3515    ,267,267,267
BEGIN DESCRIPTION:
UNT 030 IN RACR 8.0
END DESCRIPTION:
XS GIS Cut Line= 3
      2266437.72     13239096.85      2266137.72     13238696.85
      2265737.72     13238546.85
#Sta/Elev= 30
  4488.9  207.03    4517  206.47  4546.2  203.46  4552.4   203.6  4596.2  200.89
  4602.4  199.68    4617  199.26  4646.2  197.01  4660.8  196.72  4675.4  195.15
  4788.9  188.95  4802.4  187.68  4875.4  185.88  4925.4  186.93  4975.4  185.33
  4985.8  183.68    5001  183.28  5003.8  182.78    5007  183.28  5034.3  185.64
  5084.1  185.69  5114.4  186.44  5191.8  189.89  5205.2  189.98  5230.1  191.29
  5235.4  192.66  5260.3  193.22  5266.6  194.28  5277.3  194.15  5416.1  203.18
#Mann= 3 ,-1 , 0
  4488.9      .1       0    5001     .07       0    5007      .1       0
Bank Sta=5001,5007
XS Rating Curve= 0 ,0
Exp/Cntr=0.3,0.1

Type RM Length L Ch R = 1 ,3248    ,84,84,84
BEGIN DESCRIPTION:
UNT 030 IN RACR 7.0
END DESCRIPTION:
XS GIS Cut Line= 4
      2266537.72     13239146.83      2266429.11     13238603.79
        2266189.     13238403.55      2265932.95     13238403.55
#Sta/Elev= 30
  4291.3  212.84  4352.5  210.09  4372.9  207.99  4413.7  205.49  4505.4  202.06
  4515.6  201.34  4525.8  199.26    4536   198.3  4597.2  196.61  4678.8  191.64
  4719.6  190.35  4729.8  189.11    4791  186.92  4811.4  186.98    4841  185.65
  4893.7  184.87  4914.5  181.91  4925.9  181.27  4928.6  180.77  4931.9  181.27
  4985.6  181.37  5008.3  181.43  5042.2  181.59  5085.1  183.45  5113.7  186.17
  5120.4  188.74  5134.5  189.92    5239  190.99    5299  193.16  5413.8  195.79
#Mann= 5 ,-1 , 0
  4291.3      .1       0  4925.9     .07       0  4931.9      .1       0
  4985.6     .08       0  5008.3      .1       0
Bank Sta=4925.9,4931.9
XS Rating Curve= 0 ,0
Exp/Cntr=0.3,0.1

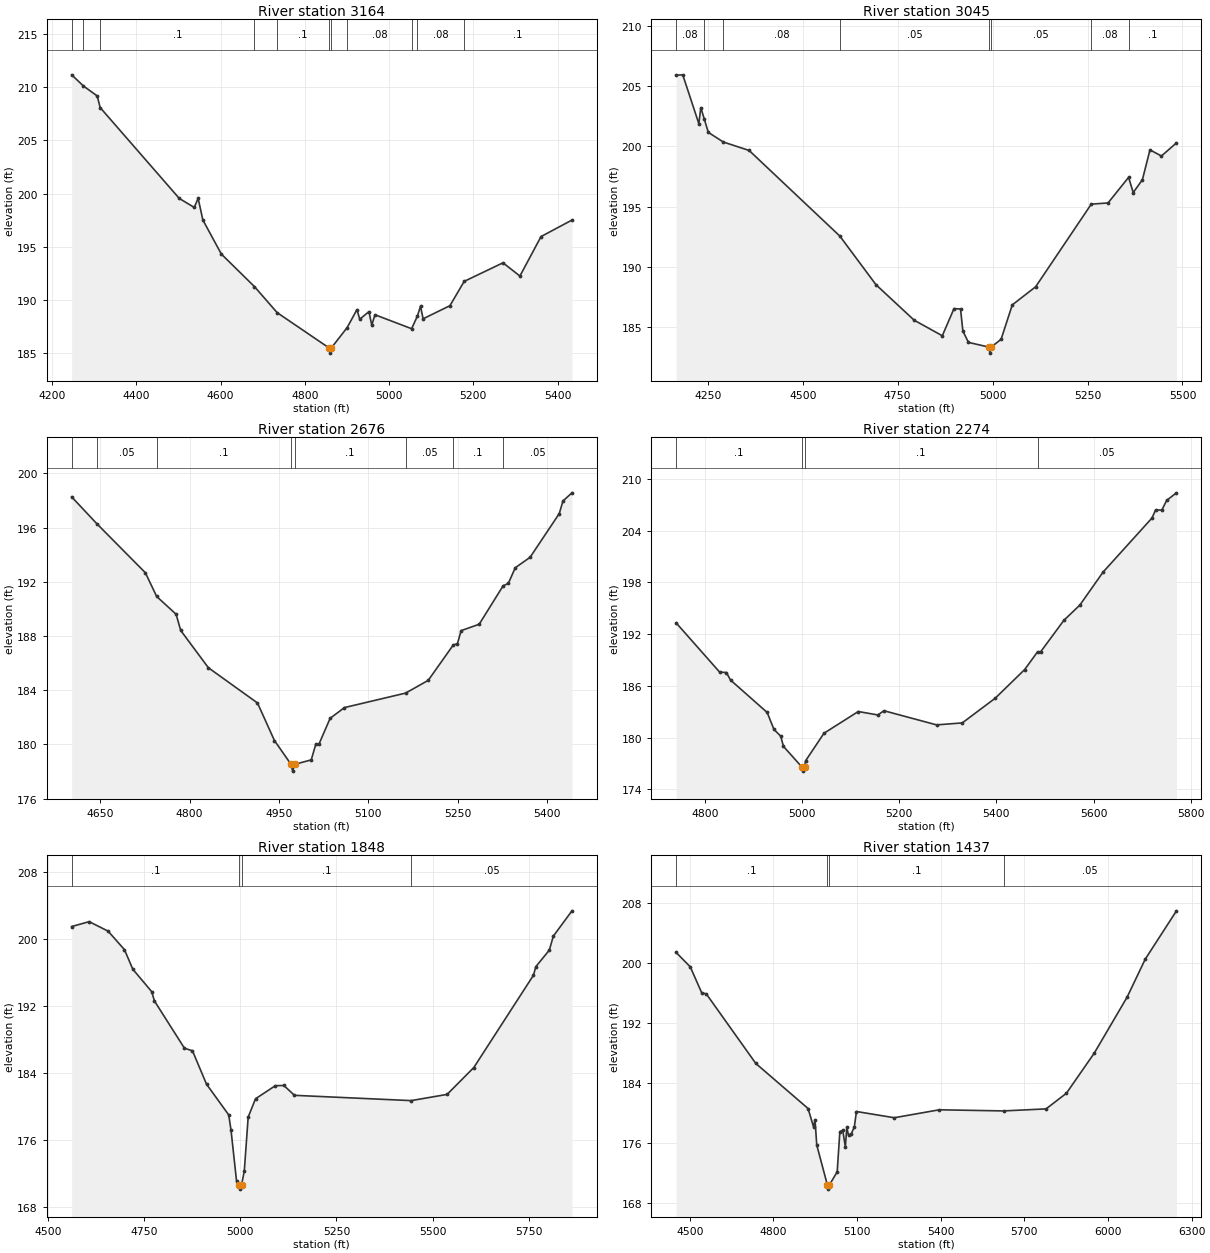
Type RM Length L Ch R = 1 ,3164    ,119,119,119
BEGIN DESCRIPTION:
Mapping XS 85a59cf9
END DESCRIPTION:
XS GIS Cut Line= 6
        2266595.      13239141.7      2266475.21     13238568.78
      2266368.44     13238446.38      2266305.94     13238407.32
      2266243.44     13238363.05      2265954.34     13238344.82
#Sta/Elev= 30
  4246.6  211.13  4274.3  210.09  4307.2  209.15  4314.2  208.06    4502  199.54
  4537.6  198.69  4546.8  199.55    4558  197.52  4601.9  194.32  4680.5  191.27
  4734.3  188.83  4857.2  185.53    4860  185.03  4863.2  185.53  4900.5  187.42
  4923.8  189.11  4930.5  188.21  4952.3  188.92    4959  187.65  4966.6  188.63
  5053.6  187.32  5067.4  188.51  5074.7  189.43  5080.9  188.25  5144.6  189.48
  5178.4  191.76  5270.6   193.5  5310.7  192.26  5360.8  195.96  5434.3  197.51
#Mann= 11 ,-1 , 0
  4246.6      .1       0  4274.3     .05       0  4314.2      .1       0
  4680.5     .05       0  4734.3      .1       0  4857.2     .07       0
  4863.2      .1       0  4900.5     .08       0  5053.6     .05       0
  5067.4     .08       0  5178.4      .1       0
Bank Sta=4857.2,4863.2
XS Rating Curve= 0 ,0
Exp/Cntr=0.3,0.1

Type RM Length L Ch R = 1 ,3045    ,369,369,369
BEGIN DESCRIPTION:
Mapping XS 3b96cbf4
END DESCRIPTION:
XS GIS Cut Line= 4
      2266696.57     13239139.09       2266527.3     13238417.74
      2266371.05     13238305.76      2265988.22      13238271.9
#Sta/Elev= 30
  4166.8  205.89  4184.1  205.92  4226.5  201.87  4231.6   203.2  4241.1  202.23
  4251.3  201.15    4291  200.35  4358.9  199.65  4597.6  192.56    4693  188.52
  4793.5  185.58  4867.6  184.29  4898.4  186.54  4915.6  186.51  4921.8  184.68
  4936.5  183.74  4990.3  183.35  4993.1  182.85  4996.3  183.35  5022.5     184
  5051.9  186.85  5113.4  188.35  5259.9   195.2  5304.1   195.3  5358.2  197.42
  5370.4  196.16  5394.5  197.22  5414.5   199.7  5444.6  199.19  5484.3  200.28
#Mann= 8 ,-1 , 0
  4166.8     .08       0  4241.1     .05       0    4291     .08       0
  4597.6     .05       0  4990.3     .03       0  4996.3     .05       0
  5259.9     .08       0  5358.2      .1       0
Bank Sta=4990.3,4996.3
XS Rating Curve= 0 ,0
Exp/Cntr=0.3,0.1

Type RM Length L Ch R = 1 ,2676    ,402,402,402
BEGIN DESCRIPTION:
UNT 030 IN RACR 6.0
END DESCRIPTION:
XS GIS Cut Line= 3
      2267137.72     13238246.86      2266737.72     13238146.85
      2266337.73     13237996.86
#Sta/Elev= 30
  4602.1  198.27  4644.3  196.29  4725.8  192.67  4744.7  190.92  4777.3  189.61
  4785.1  188.41  4831.5  185.66  4913.9  183.06  4942.3  180.29  4970.2  178.53
  4972.9  178.03  4976.2  178.53  5004.1  178.86  5011.8  180.03  5017.1  180.03
  5035.8  181.93  5059.8  182.72  5162.5  183.79  5200.4  184.73  5242.4  187.34
  5249.4  187.44  5255.6   188.4  5285.9  188.87  5326.1  191.71  5334.8  191.88
  5346.4  193.04  5371.3  193.81  5420.3  197.04  5426.5  197.97  5441.6  198.57
#Mann= 8 ,-1 , 0
  4602.1      .1       0  4644.3     .05       0  4744.7      .1       0
  4970.2     .07       0  4976.2      .1       0  5162.5     .05       0
  5242.4      .1       0  5326.1     .05       0
Bank Sta=4970.2,4976.2
XS Rating Curve= 0 ,0
Exp/Cntr=0.3,0.1

Type RM Length L Ch R = 1 ,2274    ,426,426,426
BEGIN DESCRIPTION:
UNT 030 IN RACR 5.0
END DESCRIPTION:
XS GIS Cut Line= 3
      2267237.71     13237946.85      2267037.72     13237846.85
      2266237.74     13237746.86
#Sta/Elev= 30
  4740.8   193.3  4830.2   187.6  4844.2  187.55  4852.6  186.68  4928.1  182.92
    4942  180.96    4956  180.17  4961.6  178.99  4999.2  176.62  5001.9  176.12
  5005.2  176.62  5007.2  177.32    5045  180.51  5115.6  183.03  5155.9  182.63
  5168.5  183.12  5276.8  181.48  5329.7  181.71  5397.7  184.58  5458.2   187.9
  5484.8  189.96    5491  189.95  5538.8   193.6  5571.6  195.36  5619.5  199.19
  5720.2  205.46  5727.8  206.41  5740.4  206.37  5750.5  207.51  5770.6  208.38
#Mann= 4 ,-1 , 0
  4740.8      .1       0  4999.2     .07       0  5005.2      .1       0
  5484.8     .05       0
Bank Sta=4999.2,5005.2
XS Rating Curve= 0 ,0
Exp/Cntr=0.3,0.1

Type RM Length L Ch R = 1 ,1848    ,411,411,411
BEGIN DESCRIPTION:
UNT 030 IN RACR 4.0
END DESCRIPTION:
XS GIS Cut Line= 4
      2267506.42     13237702.45      2267256.42     13237473.28
      2267027.25     13237438.56      2266320.81     13237625.56
#Sta/Elev= 30
    4561  201.45  4606.5  202.03  4655.8   200.9  4698.4  198.69    4720  196.37
  4769.3  193.69  4776.3  192.59  4854.4  186.96  4875.3  186.65  4911.8  182.68
  4969.6  179.02  4975.6   177.2  4989.9  171.17    4997  170.68  4999.7  170.18
    5003  170.68  5010.1  172.33  5020.2  178.75  5039.3  180.94    5091   182.5
  5113.1  182.52  5140.7  181.35  5444.1  180.72  5537.8  181.46  5607.3  184.66
  5762.5  195.65  5768.8  196.68  5803.8  198.64  5814.2  200.31  5862.7  203.32
#Mann= 4 ,-1 , 0
    4561      .1       0    4997     .07       0    5003      .1       0
  5444.1     .05       0
Bank Sta=4997,5003
XS Rating Curve= 0 ,0
Exp/Cntr=0.3,0.1

Type RM Length L Ch R = 1 ,1437    ,345,345,345
BEGIN DESCRIPTION:
UNT 030 IN RACR 3.0
END DESCRIPTION:
XS GIS Cut Line= 4
      2267555.03     13237466.33      2267485.59       13237133.
      2267103.64     13237028.84      2266207.78     13237591.36
#Sta/Elev= 30
  4451.4  201.42  4501.9   199.5  4542.8  196.05  4559.4  195.89  4736.9  186.61
  4924.4  180.59  4944.1  178.13  4949.3   179.1  4955.5  175.72    4994  170.33
  4996.7  169.83    5000  170.33  5028.8  172.14  5038.4  177.51  5048.8  177.68
  5058.1  175.45  5063.3   178.1  5069.5  176.99  5079.9  177.25  5090.3  178.15
  5097.9  180.19  5233.6  179.36    5395  180.42  5625.4  180.27  5777.8  180.54
  5850.9  182.63    5951     188  6068.6  195.46  6133.6  200.53  6245.6  206.98
#Mann= 4 ,-1 , 0
  4451.4      .1       0    4994     .07       0    5000      .1       0
  5625.4     .05       0
Bank Sta=4994,5000
XS Rating Curve= 0 ,0
Exp/Cntr=0.3,0.1

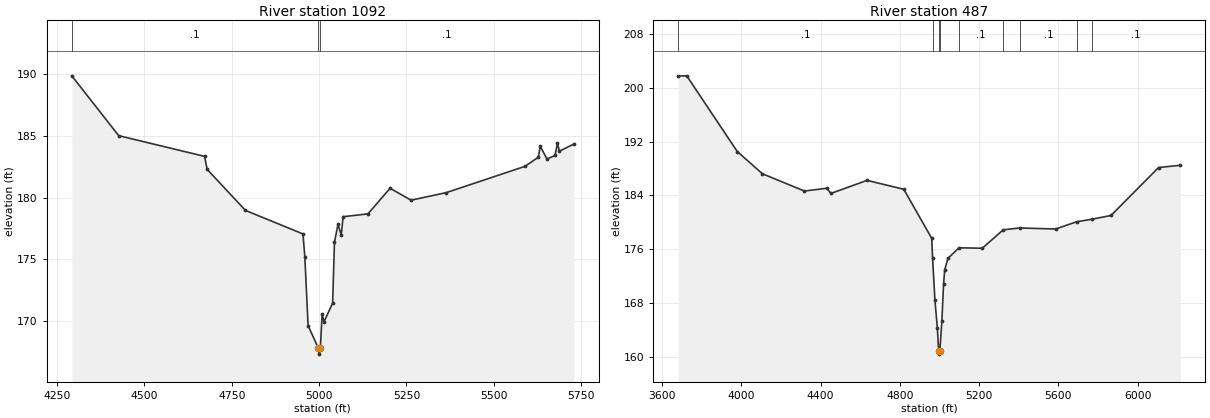
Type RM Length L Ch R = 1 ,1092    ,605,605,605
BEGIN DESCRIPTION:
Mapping XS b9b66d96
END DESCRIPTION:
XS GIS Cut Line= 3
      2267639.67     13237231.14      2267626.64     13236853.51
       2266637.1     13236475.92
#Sta/Elev= 30
  4292.2  189.89  4426.6  185.03  4672.2  183.35  4679.8  182.29  4789.4  178.96
  4953.9  177.05  4959.2  175.21  4968.6   169.6  4997.7  167.79  5000.5  167.29
  5003.7  167.79  5008.7  170.54    5014  169.91  5038.8  171.43  5044.1   176.4
  5054.2  177.83  5063.5  176.96  5068.8  178.45  5139.9  178.68  5203.2  180.76
  5263.3  179.79  5364.6  180.41  5589.4  182.54  5627.6  183.28    5633  184.17
  5652.4  183.13    5675  183.42  5682.4   184.4  5687.8  183.77  5729.2  184.35
#Mann= 3 ,-1 , 0
  4292.2      .1       0  4997.7     .07       0  5003.7      .1       0
Bank Sta=4997.7,5003.7
XS Rating Curve= 0 ,0
Exp/Cntr=0.3,0.1

Type RM Length L Ch R = 1 ,487     ,0,0,0
BEGIN DESCRIPTION:
UNT 030 IN RACR 1.0
END DESCRIPTION:
XS GIS Cut Line= 5
      2267617.52     13237528.87      2267839.75       13236883.
      2267916.14      13236445.5      2267638.37     13236292.73
      2266548.04     13236292.73
#Sta/Elev= 30
  3681.3  201.78  3724.2   201.8  3979.5  190.53  4106.5  187.23    4318  184.66
  4431.5  185.08  4451.8   184.3  4634.5  186.25  4819.9  184.92    4961  177.62
  4965.2  174.73  4977.1  168.43  4989.3  164.32  4995.9   160.9  4998.6   160.4
  5001.9   160.9  5012.1  165.26  5020.7  170.81  5026.4  172.94  5042.4  174.63
  5098.6  176.22  5216.1  176.15  5321.8  178.89  5405.3  179.17  5586.1  179.01
  5693.4   180.1  5768.4  180.46  5866.1  181.03  6106.1  188.16  6215.8  188.49
#Mann= 9 ,-1 , 0
  3681.3      .1       0  4965.2     .12       0  4995.9     .07       0
  5001.9     .12       0  5098.6      .1       0  5321.8     .12       0
  5405.3      .1       0  5693.4     .16       0  5768.4      .1       0
Bank Sta=4995.9,5001.9
XS Rating Curve= 0 ,0
Exp/Cntr=0.3,0.1
Stream Node=UNT 030 IN RACR ,Reach-1         , 0 , 0 ,Upstream end
Stream Node=UNT 030 IN RACR ,Reach-1         , 0 , 1 ,Downstream end

Chan Stop Cuts=-1
Use User Specified Reach Order=0
Composite Channel Slope=5