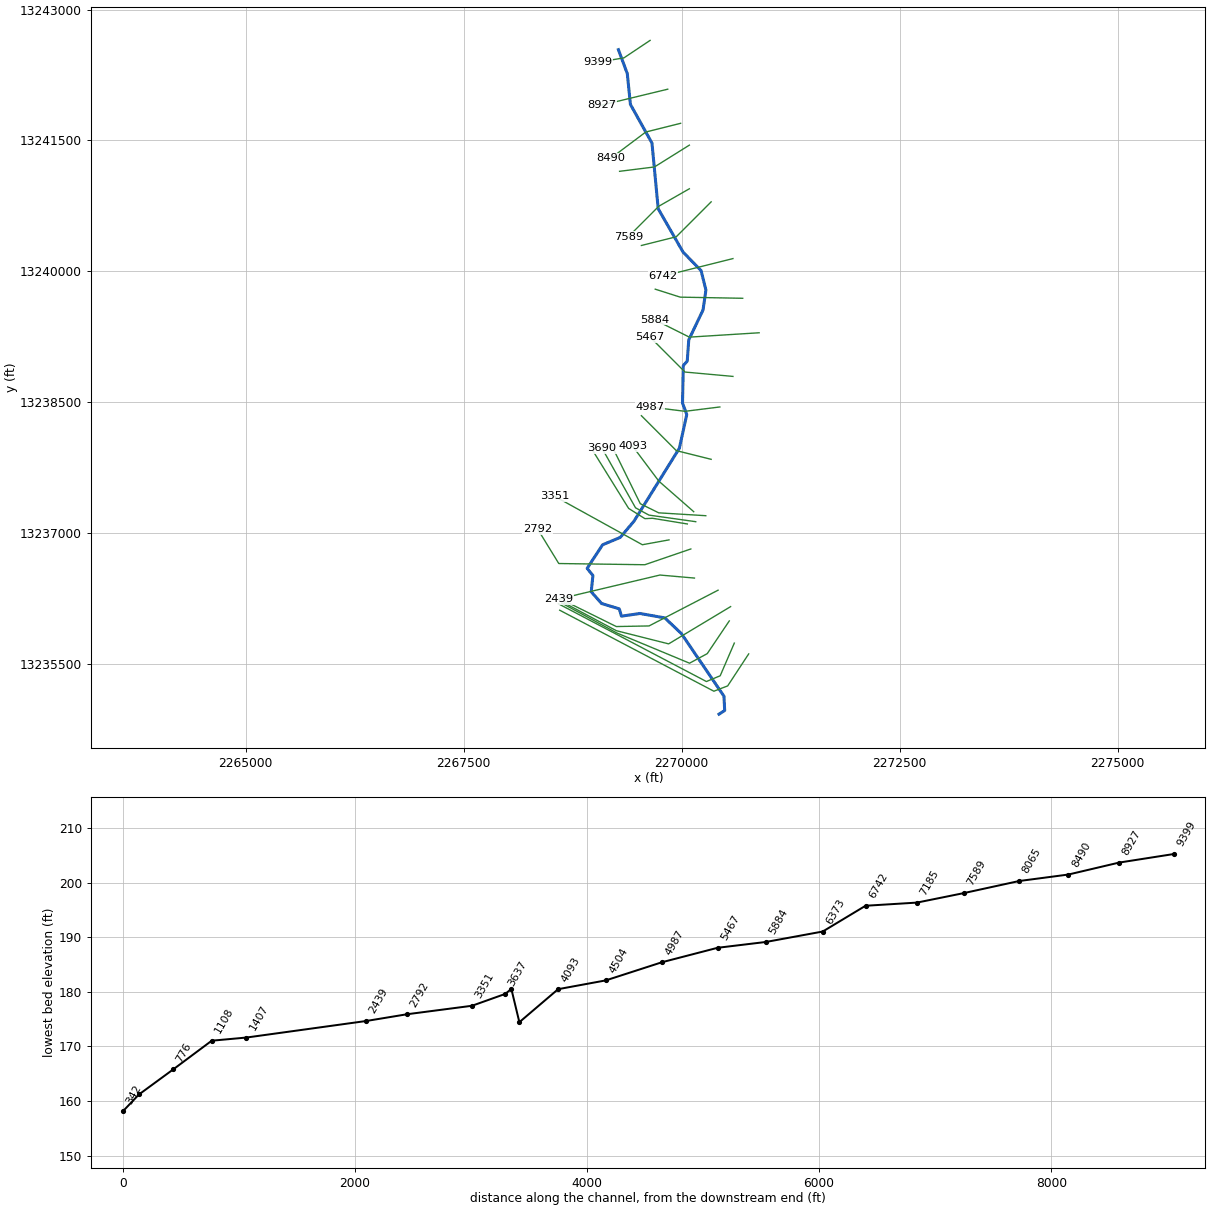
--- UNT 031 IN RACR.prj (project) ---

Proj Title=UNT 031 IN RACR Base Level Engineering
Current Plan=p01
Default Exp/Contr=0.3,0.1
English Units
Geom File=g01
Flow File=f01
Plan File=p01
Y Axis Title=Elevation
X Axis Title(PF)=Main Channel Distance
X Axis Title(XS)=Station
BEGIN DESCRIPTION:
UNT 031 IN RACR
END DESCRIPTION:
DSS Export Rating Curves= 0
DSS Export Rating Curve Sorted= 0
DSS Export Volume Flow Curves= 0
DXF OffsetX= 0
DXF OffsetY= 0
DXF ScaleX= 1
DXF ScaleY= 10

--- UNT 031 IN RACR.p01 (plan) ---

Plan Title=Multiple Run
Short Identifier=Multiple
Geom File=g01
Flow File=f01
Subcritical Flow
K Sum by GR= 0
Std Step Tol= 0.01
Critical Tol= 0.01
Num of Std Step Trials= 20
Max Error Tol= 0.3
Flow Tol Ratio= 0.001
Split Flow NTrial= 30
Split Flow Tol= 0.02
Split Flow Ratio= 0.02
Log Output Level= 0
Friction Slope Method= 1
Unsteady Friction Slope Method= 2
Unsteady Bridges Friction Slope Method= 1
Parabolic Critical Depth
Global Vel Dist=  1 , 1 , 1
Global Log Level= 0
CheckData=True
Encroach Param= -1, 0, 0, 0
BEGIN DESCRIPTION:
Multiple Run
END DESCRIPTION:

--- UNT 031 IN RACR.f01 (steady flow) ---

Flow Title=Multiple
Number of Profiles=7
Profile Names=10-year,25-year,50-year,1pct_min,100-year,1pct_plu,500-year
River Rch & RM= UNT 031 IN RACR,Reach-1,9399
     227     314     387     352     476     643     728
River Rch & RM= UNT 031 IN RACR,Reach-1,8927
     308     431     535     488     660     893    1021
Boundary for River Rch & Prof#=UNT 031 IN RACR,Reach-1,1
Up Type=0
Dn Type=3
Dn Slope=0.005
Boundary for River Rch & Prof#=UNT 031 IN RACR,Reach-1,2
Up Type=0
Dn Type=3
Dn Slope=0.005
Boundary for River Rch & Prof#=UNT 031 IN RACR,Reach-1,3
Up Type=0
Dn Type=3
Dn Slope=0.005
Boundary for River Rch & Prof#=UNT 031 IN RACR,Reach-1,4
Up Type=0
Dn Type=3
Dn Slope=0.005
Boundary for River Rch & Prof#=UNT 031 IN RACR,Reach-1,5
Up Type=0
Dn Type=3
Dn Slope=0.005
Boundary for River Rch & Prof#=UNT 031 IN RACR,Reach-1,6
Up Type=0
Dn Type=3
Dn Slope=0.005
Boundary for River Rch & Prof#=UNT 031 IN RACR,Reach-1,7
Up Type=0
Dn Type=3
Dn Slope=0.005

--- UNT 031 IN RACR.g01 (geometry) ---

Geom Title=Existing Conditions
Program Version=4.10

River Reach=UNT 031 IN RACR ,Reach-1
Reach XY= 30
      2269274.18     13242540.65      2269376.26     13242266.25
      2269411.87     13241913.88      2269659.17     13241470.18
      2269730.54     13240718.09      2270016.01     13240220.42
      2270222.22     13240009.36       2270277.5     13239787.02
      2270244.64     13239558.13        2270081.     13239215.49
       2270063.4     13238971.92      2270018.24     13238921.55
      2270009.42      13238491.3      2270058.06     13238360.11
      2269973.21     13237974.02      2269453.08     13237137.98
      2269295.38     13236951.83      2269092.99     13236867.46
      2268915.85     13236597.53      2268982.07     13236515.33
       2268962.8     13236328.85      2269081.48     13236194.71
      2269284.85     13236133.14      2269308.95     13236049.68
      2269521.73     13236080.19      2269806.52     13236029.78
      2269996.82      13235849.5      2270484.73     13235132.12
      2270492.77     13234968.43      2270427.72     13234926.86

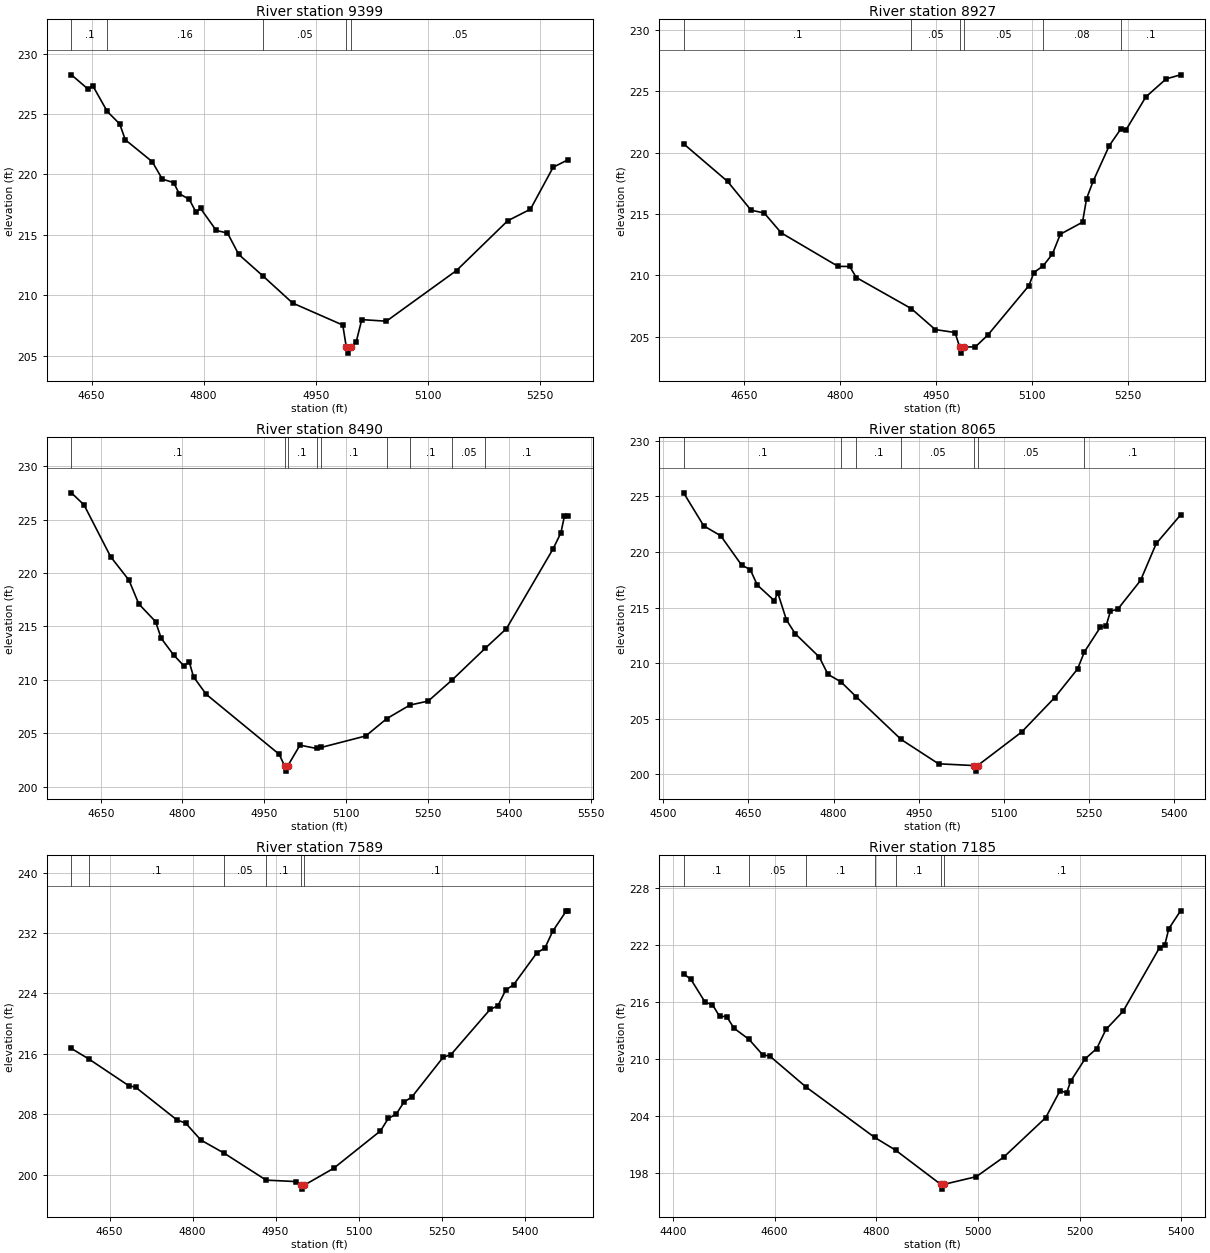
Type RM Length L Ch R = 1 ,9399    ,472,472,472
BEGIN DESCRIPTION:
UNT 031 IN RACR 16.0
END DESCRIPTION:
XS GIS Cut Line= 3
      2269637.69     13242646.83      2269337.72     13242446.85
      2269037.67     13242396.85
#Sta/Elev= 30
  4623.1  228.24  4645.6  227.05  4651.6  227.35  4671.1  225.21  4687.7  224.18
  4695.2  222.87  4731.2  221.06  4744.7  219.62  4759.8  219.33  4767.3  218.42
  4780.8  217.94  4789.8  216.88  4795.8   217.2  4816.9  215.37  4831.9  215.16
  4846.9  213.39  4879.3  211.61    4919  209.37  4986.1  207.55  4990.8  205.73
  4993.5  205.23  4996.8  205.73  5003.9  206.13  5011.5     208  5044.4  207.87
  5138.2  212.06  5206.6  216.17  5237.1  217.13  5267.5   220.6  5287.8  221.23
#Mann= 5 ,-1 , 0
  4623.1      .1       0  4671.1     .16       0  4879.3     .05       0
  4990.8    .035       0  4996.8     .05       0
Bank Sta=4990.8,4996.8
XS Rating Curve= 0 ,0
Exp/Cntr=0.3,0.1

Type RM Length L Ch R = 1 ,8927    ,437,437,437
BEGIN DESCRIPTION:
UNT 031 IN RACR 15.0
END DESCRIPTION:
XS GIS Cut Line= 2
      2269840.16     13242087.87      2269084.95     13241905.58
#Sta/Elev= 30
  4554.9  220.72  4623.7  217.65  4660.3  215.31  4680.9  215.08  4707.5  213.46
  4796.4  210.73  4814.6  210.72  4824.9  209.82  4910.8  207.29  4948.3  205.58
  4979.2  205.34  4986.5  204.16  4989.2  203.66  4992.5  204.16    5011  204.17
  5030.6  205.14  5094.7  209.16  5102.6  210.23  5117.1  210.78  5131.5  211.74
  5143.8  213.35  5178.5  214.33  5184.9  216.26  5195.2  217.68  5220.4  220.57
  5238.4  221.93  5246.6  221.86  5277.5  224.54  5309.3  226.01  5331.8  226.34
#Mann= 6 ,-1 , 0
  4554.9      .1       0  4910.8     .05       0  4986.5    .035       0
  4992.5     .05       0  5117.1     .08       0  5238.4      .1       0
Bank Sta=4986.5,4992.5
XS Rating Curve= 0 ,0
Exp/Cntr=0.3,0.1

Type RM Length L Ch R = 1 ,8490    ,425,425,425
BEGIN DESCRIPTION:
UNT 031 IN RACR 14.0
END DESCRIPTION:
XS GIS Cut Line= 3
       2269987.7     13241696.85      2269587.72     13241596.85
      2269187.71     13241296.85
#Sta/Elev= 30
  4596.2   227.5  4619.4  226.37  4668.3  221.52  4701.8  219.34  4719.9  217.11
  4750.8  215.45  4761.1  213.89  4784.3  212.31  4802.3  211.34  4812.6  211.68
  4820.4  210.29  4843.6  208.66  4977.6  203.05  4987.5  201.97  4990.2  201.47
  4993.5  201.97  5015.8   203.9  5046.2  203.59  5055.1  203.69  5136.6  204.76
  5175.2  206.38  5217.7  207.65  5251.2  208.02  5295.2     210  5355.5  212.94
  5394.9   214.8  5480.4  222.25  5494.9  223.77  5501.2   225.3  5508.5  225.32
#Mann= 9 ,-1 , 0
  4596.2      .1       0  4987.5     .07       0  4993.5      .1       0
  5046.2     .08       0  5055.1      .1       0  5175.2     .05       0
  5217.7      .1       0  5295.2     .05       0  5355.5      .1       0
Bank Sta=4987.5,4993.5
XS Rating Curve= 0 ,0
Exp/Cntr=0.3,0.1

Type RM Length L Ch R = 1 ,8065    ,476,476,476
BEGIN DESCRIPTION:
UNT 031 IN RACR 13.0
END DESCRIPTION:
XS GIS Cut Line= 3
      2270087.72     13241446.85      2269687.72     13241196.85
      2269287.73     13241146.86
#Sta/Elev= 30
    4536  225.33  4571.4  222.36  4601.4  221.46    4638  218.83  4653.3  218.42
  4665.7  217.03  4695.8  215.62  4701.7  216.34    4717  213.89  4732.3  212.66
  4774.8  210.55  4790.1  208.99  4812.9  208.32  4839.5  206.99  4918.9  203.13
  4984.7  200.94  5047.5  200.78  5050.3  200.28  5053.5  200.78  5131.1   203.8
  5189.1  206.89  5229.4  209.47  5241.6  211.02  5269.7  213.24  5279.8  213.36
  5287.4  214.69    5300  214.84  5340.3  217.44    5368  220.77  5410.8  223.34
#Mann= 7 ,-1 , 0
    4536      .1       0  4812.9     .08       0  4839.5      .1       0
  4918.9     .05       0  5047.5    .035       0  5053.5     .05       0
  5241.6      .1       0
Bank Sta=5047.5,5053.5
XS Rating Curve= 0 ,0
Exp/Cntr=0.3,0.1

Type RM Length L Ch R = 1 ,7589    ,404,404,404
BEGIN DESCRIPTION:
UNT 031 IN RACR 12.0
END DESCRIPTION:
XS GIS Cut Line= 3
      2270087.69     13240946.84      2269737.72     13240746.85
      2269387.69     13240396.82
#Sta/Elev= 30
  4581.1  216.71  4612.9   215.3  4684.7  211.78    4697  211.58  4771.8  207.24
  4787.7  206.81    4815  204.58    4857  202.84  4933.1  199.26  4987.7  199.07
  4995.3  198.57  4998.1  198.07  5001.3  198.57  5054.9  200.82  5139.7  205.79
  5153.9  207.45    5168  207.99  5182.2  209.62  5196.3  210.27  5252.9  215.54
    5267  215.89  5337.7  221.88  5351.9  222.36    5366  224.45  5380.2  225.15
  5422.6  229.41  5436.7     230  5450.9  232.24  5475.6  234.95  5479.2  234.95
#Mann= 6 ,-1 , 0
  4581.1     .05       0  4612.9      .1       0    4857     .05       0
  4933.1      .1       0  4995.3     .07       0  5001.3      .1       0
Bank Sta=4995.3,5001.3
XS Rating Curve= 0 ,0
Exp/Cntr=0.3,0.1

Type RM Length L Ch R = 1 ,7185    ,443,443,443
BEGIN DESCRIPTION:
UNT 031 IN RACR 11.0
END DESCRIPTION:
XS GIS Cut Line= 3
      2270337.74     13240796.88      2269937.72     13240396.85
      2269537.75     13240296.86
#Sta/Elev= 30
  4420.9  218.95  4435.1  218.39  4463.4  215.96  4477.5  215.73  4491.6   214.5
  4505.8  214.46  4519.9  213.25  4549.8  212.06  4576.5  210.44  4590.6  210.31
  4661.9  207.06  4796.8  201.77  4837.9  200.43    4927  196.83  4929.8  196.33
    4933  196.83  4996.9  197.64    5051   199.7  5133.5  203.84  5161.8  206.69
  5174.7  206.44  5182.5  207.67  5210.8  210.01    5234  211.11    5252  213.11
  5285.5     215  5357.7  221.72    5368  222.02  5375.7   223.7  5398.9  225.58
#Mann= 7 ,-1 , 0
  4420.9      .1       0  4549.8     .05       0  4661.9      .1       0
  4796.8     .05       0  4837.9      .1       0    4927     .07       0
    4933      .1       0
Bank Sta=4927,4933
XS Rating Curve= 0 ,0
Exp/Cntr=0.3,0.1

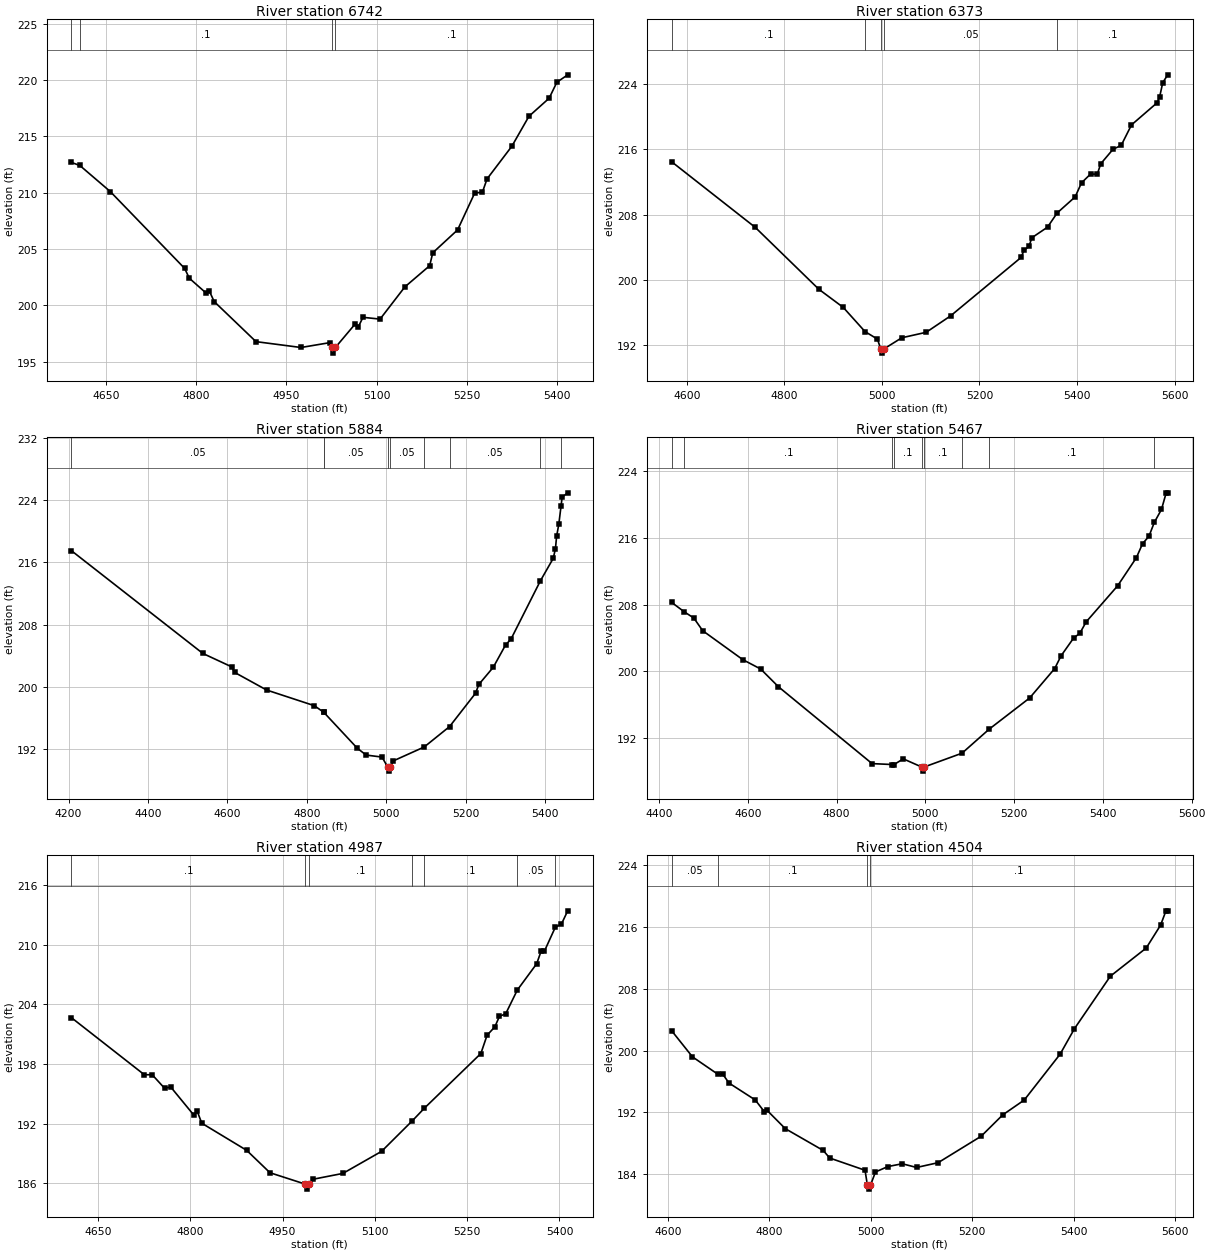
Type RM Length L Ch R = 1 ,6742    ,369,369,369
BEGIN DESCRIPTION:
UNT 031 IN RACR 10.0
END DESCRIPTION:
XS GIS Cut Line= 3
      2270587.69     13240146.85      2270187.72     13240046.85
      2269787.72     13239946.85
#Sta/Elev= 30
  4592.8  212.68  4606.7  212.41  4657.2   210.1  4780.9  203.27  4788.6   202.4
    4817  201.06  4822.1  201.24  4829.9  200.33  4899.4  196.77  4974.2  196.25
  5023.1  196.69  5025.3  196.25    5028  195.75  5031.3  196.25  5064.4  198.35
  5069.5  198.09  5077.2  198.93  5105.6  198.77  5146.8  201.63    5188  203.51
  5193.2  204.66  5234.4  206.69  5262.8  209.96  5275.7  210.05  5283.4  211.22
  5324.6  214.12    5353  216.78  5386.5  218.38  5399.4   219.8  5417.4  220.46
#Mann= 4 ,-1 , 0
  4592.8     .08       0  4606.7      .1       0  5025.3     .07       0
  5031.3      .1       0
Bank Sta=5025.3,5031.3
XS Rating Curve= 0 ,0
Exp/Cntr=0.3,0.1

Type RM Length L Ch R = 1 ,6373    ,489,489,489
BEGIN DESCRIPTION:
UNT 031 IN RACR 9.0
END DESCRIPTION:
XS GIS Cut Line= 3
      2270699.55     13239692.05      2269983.42     13239705.07
      2269696.92     13239796.23
#Sta/Elev= 30
  4568.9  214.47  4740.8  206.41  4870.8  198.85  4920.8  196.63  4965.4  193.67
  4990.8  192.75  4997.8  191.53  5000.6  191.03  5003.8  191.53  5040.8  192.91
  5090.8  193.58  5140.8  195.59  5285.2  202.74  5291.1   203.6  5301.6  204.11
  5307.2  205.15  5339.4  206.45  5359.2  208.19  5396.1  210.16  5409.1  211.88
  5427.6  212.95  5441.4  212.93  5448.5  214.21  5473.6  215.98  5490.5  216.47
  5511.5  218.97    5564  221.68  5569.2   222.4  5575.6  224.15  5585.8   225.1
#Mann= 5 ,-1 , 0
  4568.9      .1       0  4965.4     .05       0  4997.8     .03       0
  5003.8     .05       0  5359.2      .1       0
Bank Sta=4997.8,5003.8
XS Rating Curve= 0 ,0
Exp/Cntr=0.3,0.1

Type RM Length L Ch R = 1 ,5884    ,417,417,417
BEGIN DESCRIPTION:
UNT 031 IN RACR 8.0
END DESCRIPTION:
XS GIS Cut Line= 3
      2270887.72     13239296.85      2270087.72     13239246.85
       2269687.7     13239446.87
#Sta/Elev= 30
  4207.4  217.51    4538  204.28  4610.7  202.55  4618.2  201.83  4698.4  199.57
  4818.6  197.55  4842.2   196.7  4842.3   196.7  4926.3  192.09  4948.8  191.19
  4988.9  190.93  5003.5  189.62  5006.2  189.12  5009.5  189.62  5017.3  190.44
  5095.1  192.23  5158.9  194.86  5224.2  199.15  5232.6  200.29  5268.9   202.5
  5299.7  205.36  5313.6  206.14  5387.4  213.63  5419.8  216.53  5425.4  217.79
  5428.2  219.35  5433.8  220.92  5439.5   223.3  5442.2  224.42  5456.2  224.97
#Mann= 9 ,-1 , 0
  4207.4     .05       0  4842.2      .1       0  4842.3     .05       0
  5003.5     .03       0  5009.5     .05       0  5095.1      .1       0
  5158.9     .05       0  5387.4      .1       0  5439.5     .05       0
Bank Sta=5003.5,5009.5
XS Rating Curve= 0 ,0
Exp/Cntr=0.3,0.1

Type RM Length L Ch R = 1 ,5467    ,480,480,480
BEGIN DESCRIPTION:
UNT 031 IN RACR 7.0
END DESCRIPTION:
XS GIS Cut Line= 3
      2270587.77     13238796.85      2270037.72     13238846.85
      2269637.72     13239246.85
#Sta/Elev= 30
  4428.1  208.29  4456.7  207.15  4478.4   206.4  4498.4  204.88  4588.8  201.41
    4629  200.29  4669.1  198.16    4880  188.95  4925.9  188.84  4929.4  188.84
  4950.3  189.52  4991.6  188.55  4994.3  188.05  4997.6  188.55  5082.6   190.2
    5144  193.09    5235  196.82  5291.5  200.35  5305.7  201.87    5334     204
  5348.1  204.58  5362.3  205.94    5433  210.25  5475.4  213.63  5489.5  215.33
  5503.7  216.19  5515.8  217.86    5532  219.42  5542.6  221.41  5546.1  221.41
#Mann= 9 ,-1 , 0
  4428.1     .05       0  4456.7      .1       0  4925.9     .05       0
  4929.4      .1       0  4991.6     .07       0  4997.6      .1       0
  5082.6     .05       0    5144      .1       0  5515.8     .05       0
Bank Sta=4991.6,4997.6
XS Rating Curve= 0 ,0
Exp/Cntr=0.3,0.1

Type RM Length L Ch R = 1 ,4987    ,483,483,483
BEGIN DESCRIPTION:
UNT 031 IN RACR 6.0
END DESCRIPTION:
XS GIS Cut Line= 3
      2270437.77     13238446.86      2270037.72     13238396.85
       2269637.7     13238446.86
#Sta/Elev= 30
  4607.1  202.64  4725.6   196.9  4738.2  196.91  4758.3  195.55  4768.4  195.67
  4806.2  192.82  4811.2  193.27  4818.8  192.03  4891.8   189.3  4929.6  187.05
  4987.1   185.9  4989.9   185.4  4993.1   185.9  5000.2   186.4  5048.1  186.98
    5111   189.2  5161.2  192.29  5180.5  193.54  5272.3  199.04  5282.4  200.88
    5295  201.72  5302.5  202.78  5312.6  203.03  5331.5  205.42    5363  208.07
  5370.5  209.39  5375.6  209.34  5393.2  211.73  5403.3  212.07  5413.4  213.39
#Mann= 7 ,-1 , 0
  4607.1      .1       0  4987.1     .07       0  4993.1      .1       0
  5161.2     .05       0  5180.5      .1       0  5331.5     .05       0
  5393.2      .1       0
Bank Sta=4987.1,4993.1
XS Rating Curve= 0 ,0
Exp/Cntr=0.3,0.1

Type RM Length L Ch R = 1 ,4504    ,411,411,411
BEGIN DESCRIPTION:
UNT 031 IN RACR 5.0
END DESCRIPTION:
XS GIS Cut Line= 3
      2270337.75     13237846.85      2269937.72     13237946.85
      2269537.74     13238346.84
#Sta/Elev= 30
  4607.3  202.58  4648.6  199.18  4698.9  196.92  4707.8  196.99  4720.7  195.79
  4772.3  193.61  4790.3  192.09  4795.4  192.28  4831.5   189.9  4906.3  187.08
  4919.1   186.1  4988.7  184.52  4993.4  182.58  4996.2  182.08  4999.4  182.58
  5009.3   184.3  5033.8     185  5062.1  185.36  5090.3  184.88  5132.8   185.5
  5217.6  188.92  5260.1  191.68  5302.5   193.6  5373.2  199.53  5401.5  202.83
  5472.2  209.61  5542.9  213.25  5571.2  216.21  5581.8  218.06  5585.3  218.06
#Mann= 4 ,-1 , 0
  4607.3     .05       0  4698.9      .1       0  4993.4     .07       0
  4999.4      .1       0
Bank Sta=4993.4,4999.4
XS Rating Curve= 0 ,0
Exp/Cntr=0.3,0.1

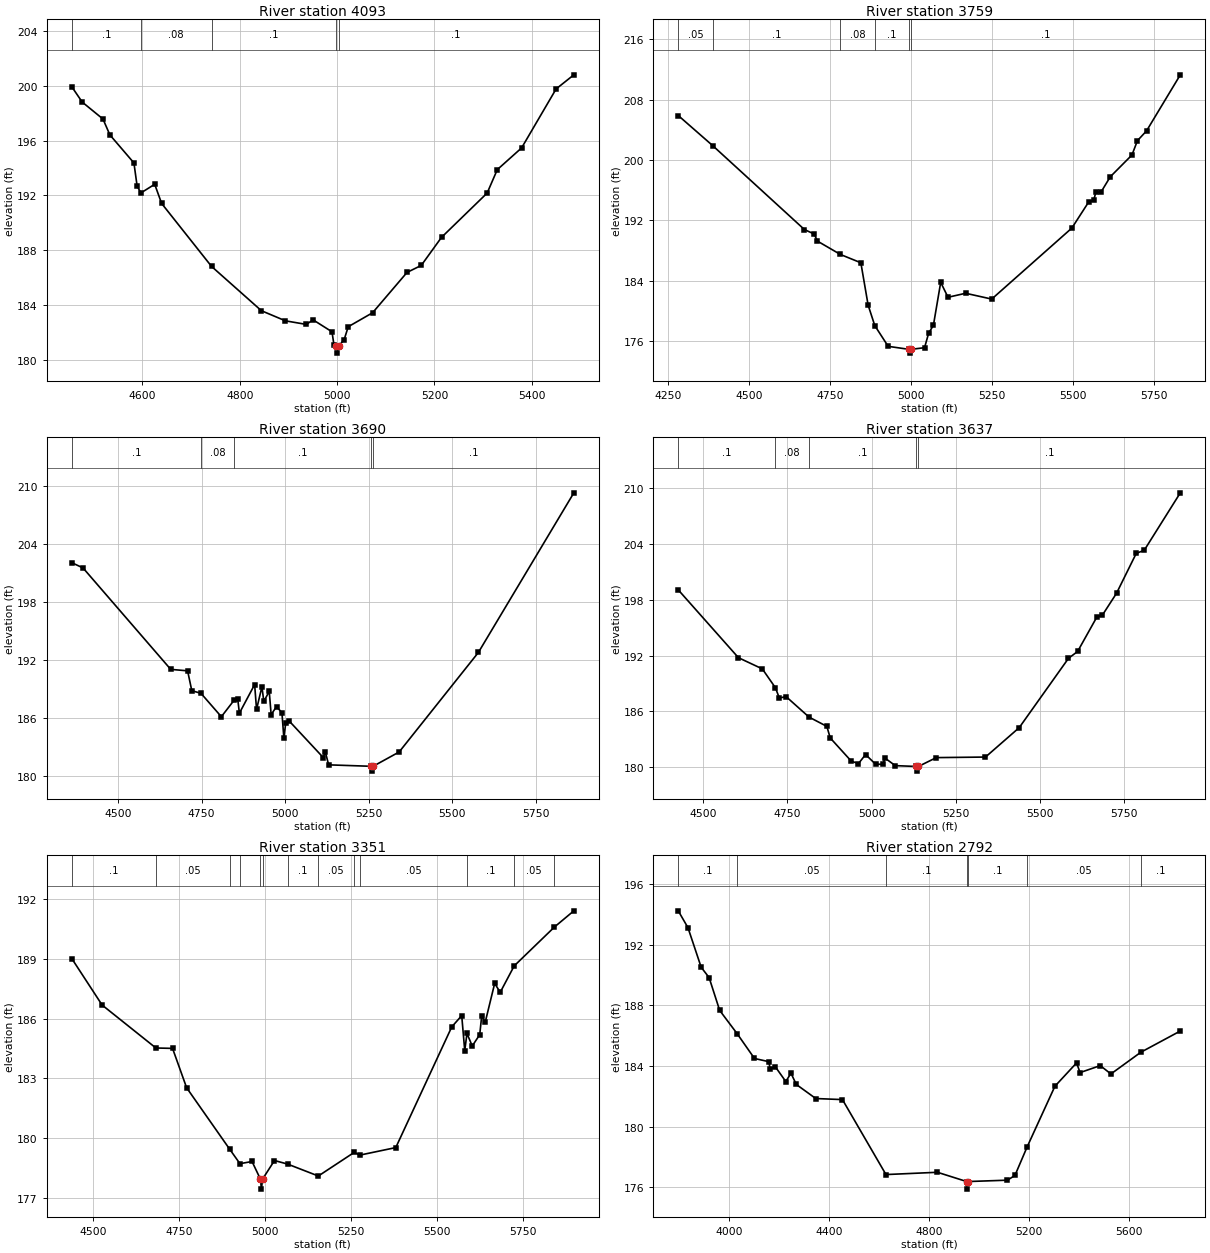
Type RM Length L Ch R = 1 ,4093    ,334,334,334
BEGIN DESCRIPTION:
UNT 031 IN RACR 4.0
END DESCRIPTION:
XS GIS Cut Line= 3
      2270137.73     13237246.85      2269737.72     13237596.85
      2269437.73     13237996.84
#Sta/Elev= 30
  4454.9  199.94  4476.3  198.82    4519  197.58  4533.2  196.42  4582.6  194.37
  4589.2  192.67    4597  192.18  4625.3  192.81  4639.5  191.41    4742  186.81
  4844.5  183.57  4893.9  182.83  4936.6  182.57  4950.8   182.9  4989.5  182.03
  4993.7  181.04    4997  180.97  4999.7  180.47    5003  180.97  5014.5  181.46
  5022.9   182.4  5072.9  183.42  5143.7  186.37  5172.9  186.88  5214.5  188.93
  5308.3  192.17  5329.1  193.88  5379.1  195.47    5450  199.78  5486.4  200.81
#Mann= 5 ,-1 , 0
  4454.9      .1       0    4597     .08       0    4742      .1       0
    4997     .07       0    5003      .1       0
Bank Sta=4997,5003
XS Rating Curve= 0 ,0
Exp/Cntr=0.3,0.1

Type RM Length L Ch R = 1 ,3759    ,69,69,69
BEGIN DESCRIPTION:
UNT 031 IN RACR 3.0
END DESCRIPTION:
XS GIS Cut Line= 4
       2270276.1     13237200.71      2269736.46      13237233.7
      2269525.52     13237337.86      2269184.36     13238030.61
#Sta/Elev= 30
    4282   205.9    4388  201.92  4671.1  190.79  4701.2   190.2  4711.2  189.26
  4782.1  187.49  4845.1  186.39  4867.5  180.78    4888  178.07  4929.3  175.32
  4993.6  174.92  4996.4  174.42  4999.6  174.92  5041.5  175.14  5053.9  177.03
  5068.9  178.13  5091.3   183.8  5113.8  181.82  5168.2  182.35  5248.6  181.58
  5495.7  190.99  5547.2  194.42  5563.1  194.67  5569.5  195.72  5585.5  195.75
  5614.1  197.78    5681  200.67  5697.9  202.57  5725.9  203.86  5830.1  211.29
#Mann= 6 ,-1 , 0
    4282     .05       0    4388      .1       0  4782.1     .08       0
    4888      .1       0  4993.6     .07       0  4999.6      .1       0
Bank Sta=4993.6,4999.6
XS Rating Curve= 0 ,0
Exp/Cntr=0.3,0.1

Type RM Length L Ch R = 1 ,3690    ,53,53,53
BEGIN DESCRIPTION:
Mapping XS dc0910d0
END DESCRIPTION:
XS GIS Cut Line= 4
      2270160.95     13237132.13      2269624.48     13237207.66
      2269470.83     13237290.99      2269085.44     13237975.84
#Sta/Elev= 30
  4361.6  202.08  4395.2  201.54  4657.7  191.04  4708.2  190.89  4720.8  188.83
    4748  188.57  4809.2  186.14  4847.6  187.86  4858.2  187.97  4863.2  186.51
  4908.8  189.47  4914.5   186.9  4930.6  189.24  4936.3  187.72  4952.5  188.77
  4958.2  186.36  4974.4  187.19  4990.5  186.55  4996.2  183.96  5002.1  185.54
  5012.4  185.69  5114.3  181.91  5120.1  182.52  5130.3  181.16  5257.3  181.01
    5260  180.51  5263.3  181.01  5341.2  182.49  5578.3  192.79    5864  209.31
#Mann= 5 ,-1 , 0
  4361.6      .1       0    4748     .08       0  4847.6      .1       0
  5257.3     .07       0  5263.3      .1       0
Bank Sta=5257.3,5263.3
XS Rating Curve= 0 ,0
Exp/Cntr=0.3,0.1

Type RM Length L Ch R = 1 ,3637    ,286,286,286
BEGIN DESCRIPTION:
Mapping XS 3c461cc2
END DESCRIPTION:
XS GIS Cut Line= 5
      2270064.53      13237106.1      2269665.28      13237171.2
      2269578.47     13237166.86      2269391.84     13237284.05
       2268979.5     13237948.13
#Sta/Elev= 30
  4425.1  199.05  4604.2  191.77  4675.2  190.57  4714.1  188.55  4725.8  187.45
  4746.1  187.59  4814.1   185.4  4867.2   184.4  4877.2  183.16  4939.9  180.67
  4961.2  180.41  4982.4  181.38  5011.9  180.35  5034.2  180.33  5040.1     181
  5070.7  180.19  5133.4   180.1  5136.1   179.6  5139.4   180.1  5192.7  181.05
  5339.1  181.11  5439.5  184.27  5585.9   191.7  5613.1  192.44  5670.9  196.17
  5686.3  196.31  5728.8  198.68  5787.6  202.97  5811.2  203.29  5918.6  209.46
#Mann= 5 ,-1 , 0
  4425.1      .1       0  4714.1     .08       0  4814.1      .1       0
  5133.4     .07       0  5139.4      .1       0
Bank Sta=5133.4,5139.4
XS Rating Curve= 0 ,0
Exp/Cntr=0.3,0.1

Type RM Length L Ch R = 1 ,3351    ,559,559,559
BEGIN DESCRIPTION:
Mapping XS 70548c89
END DESCRIPTION:
XS GIS Cut Line= 3
       2269854.6     13236923.68        2269549.     13236868.12
       2268542.1     13237423.66
#Sta/Elev= 30
  4436.8  189.03  4525.1  186.69  4681.5  184.53    4730  184.51  4770.9  182.53
  4896.1  179.44  4926.1  178.71  4961.2  178.82  4985.7  177.93  4988.5  177.43
  4991.7  177.93  5026.5  178.87  5064.6  178.69  5154.1  178.09  5258.6  179.28
  5274.5  179.14  5379.4  179.52  5542.2  185.59  5571.2  186.16    5580   184.4
  5586.5  185.26  5601.8  184.63  5623.6   185.2  5629.3  186.14  5639.6  185.83
  5667.1  187.78  5683.2  187.33  5723.9  188.66  5840.6  190.61  5897.4  191.43
#Mann= 13 ,-1 , 0
  4436.8      .1       0  4681.5     .05       0  4896.1      .1       0
  4926.1     .05       0  4985.7     .04       0  4991.7     .05       0
  5064.6      .1       0  5154.1     .05       0  5258.6      .1       0
  5274.5     .05       0  5586.5      .1       0  5723.9     .05       0
  5840.6      .1       0
Bank Sta=4985.7,4991.7
XS Rating Curve= 0 ,0
Exp/Cntr=0.3,0.1

Type RM Length L Ch R = 1 ,2792    ,353,353,353
BEGIN DESCRIPTION:
UNT 031 IN RACR 2.0
END DESCRIPTION:
XS GIS Cut Line= 4
      2270104.54      13236819.5      2269576.78     13236638.95
      2268590.67     13236652.84      2268347.61     13237048.68
#Sta/Elev= 30
  3797.7  194.22  3836.6  193.11  3889.5   190.5  3921.2  189.82  3963.4  187.66
  4033.5  186.12  4102.7  184.49  4160.1  184.28  4165.4  183.78  4185.4  183.96
    4228  182.97  4248.7  183.52  4269.9  182.78  4347.9  181.85  4454.6  181.78
  4628.7  176.84  4834.6  176.99  4951.6  176.38  4954.4  175.88  4957.6  176.38
  5114.6  176.47  5144.6  176.78  5193.1  178.65  5304.6  182.66  5391.3   184.2
  5405.1  183.56    5486  184.02  5528.6  183.47  5648.2   184.9  5806.2   186.3
#Mann= 7 ,-1 , 0
  3797.7      .1       0  4033.5     .05       0  4628.7      .1       0
  4951.6     .07       0  4957.6      .1       0  5193.1     .05       0
  5648.2      .1       0
Bank Sta=4951.6,4957.6
XS Rating Curve= 0 ,0
Exp/Cntr=0.3,0.1

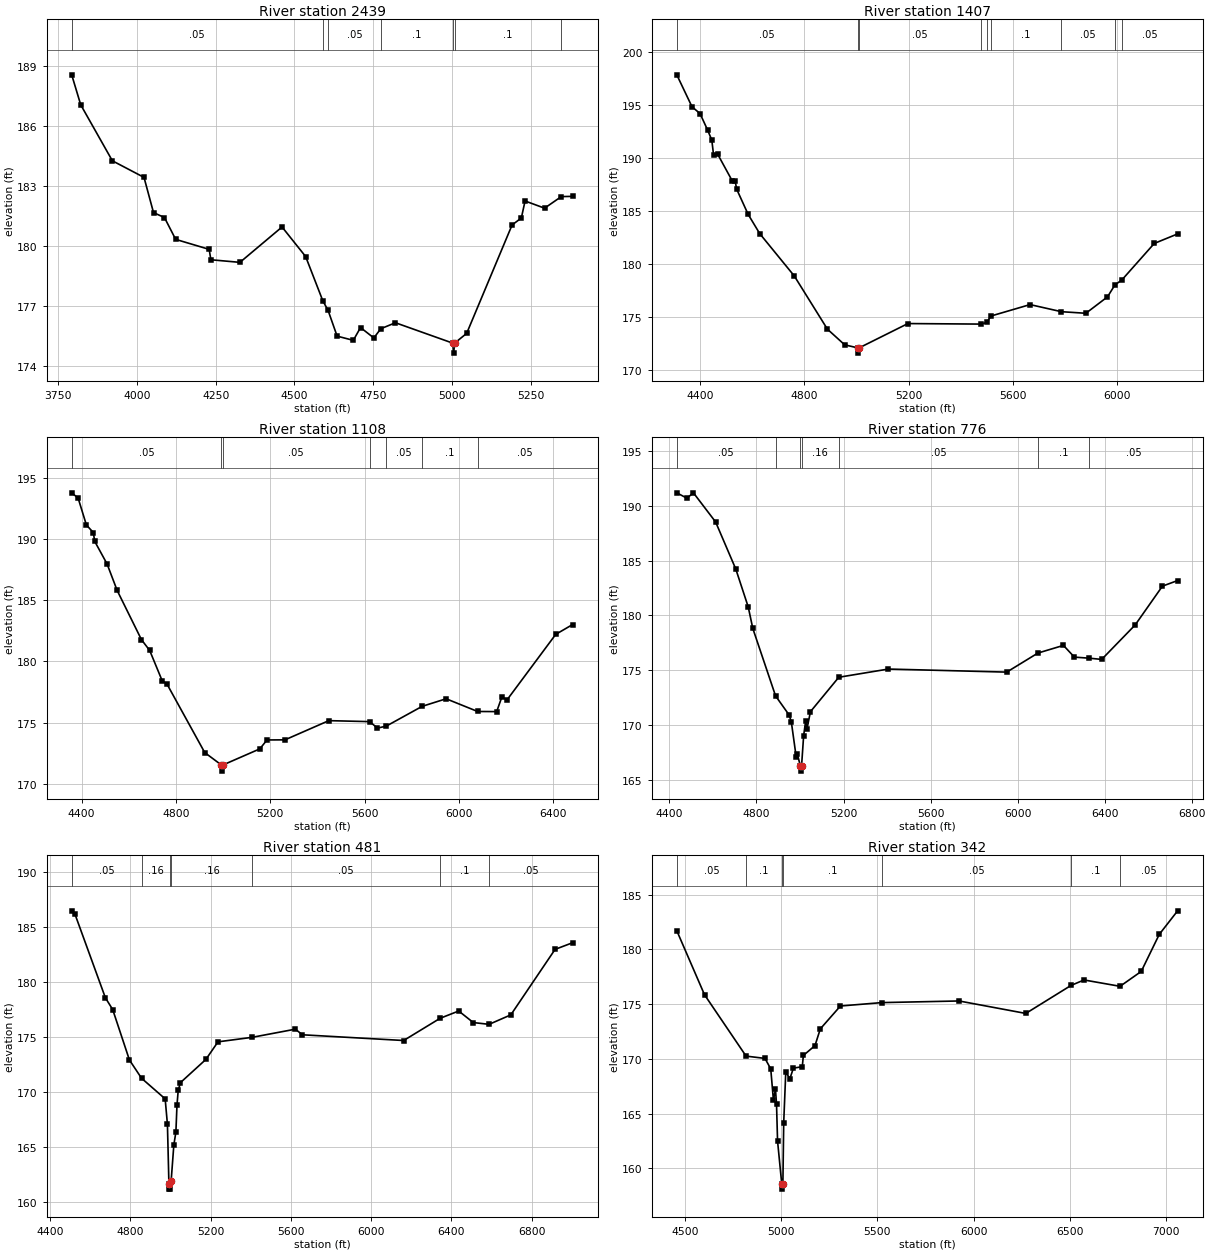
Type RM Length L Ch R = 1 ,2439    ,1032,1032,1032
BEGIN DESCRIPTION:
Mapping XS 1309b3d7
END DESCRIPTION:
XS GIS Cut Line= 4
      2270146.25     13236486.17      2269750.39      13236520.9
      2268812.89     13236298.68      2268591.66     13236243.37
#Sta/Elev= 30
  3793.2  188.56  3821.8  187.06  3922.2  184.26  4022.6  183.43  4052.7  181.67
  4087.5  181.42    4123  180.33  4229.3  179.83  4234.7  179.31  4326.9  179.18
  4460.5  180.95  4535.4  179.47  4589.8  177.26  4606.5  176.78  4635.2  175.49
  4686.6  175.28  4709.5  175.92  4751.7   175.4  4773.8  175.86  4820.2  176.16
  5002.1  175.14  5004.9  174.64  5008.1  175.14  5046.3  175.63  5190.3  181.05
  5219.7   181.4  5231.5  182.25  5293.4  181.89  5346.6  182.47  5382.1  182.48
#Mann= 7 ,-1 , 0
  3793.2     .05       0  4589.8      .1       0  4606.5     .05       0
  4773.8      .1       0  5002.1     .07       0  5008.1      .1       0
  5346.6     .05       0
Bank Sta=5002.1,5008.1
XS Rating Curve= 0 ,0
Exp/Cntr=0.3,0.1

Type RM Length L Ch R = 1 ,1407    ,299,299,299
BEGIN DESCRIPTION:
Mapping XS 9188bcee
END DESCRIPTION:
XS GIS Cut Line= 4
      2270417.06     13236347.29      2269625.39     13235937.57
      2269250.39     13235930.62      2268661.89     13236221.41
#Sta/Elev= 30
  4309.8  197.87  4368.1  194.86  4399.1  194.21  4428.8  192.62  4444.2  191.71
    4451   190.3  4466.7  190.38    4523  187.85  4533.9  187.85  4539.5  187.09
  4583.8   184.7  4628.1  182.89  4760.9  178.89  4888.1  173.87  4954.5  172.39
  5004.2  172.11  5006.9  171.61  5010.2  172.11  5197.1   174.4  5476.7  174.35
  5500.2   174.5  5515.8  175.11  5666.1  176.19  5786.4  175.52  5880.4  175.37
  5963.4  176.92  5991.8  178.04  6018.8  178.52    6143  181.96  6232.7  182.86
#Mann= 9 ,-1 , 0
  4309.8     .05       0  5004.2     .03       0  5010.2     .05       0
  5476.7      .1       0  5500.2     .05       0  5515.8      .1       0
  5786.4     .05       0  5991.8      .1       0  6018.8     .05       0
Bank Sta=5004.2,5010.2
XS Rating Curve= 0 ,0
Exp/Cntr=0.3,0.1

Type RM Length L Ch R = 1 ,1108    ,332,332,332
BEGIN DESCRIPTION:
Mapping XS 17b4157b
END DESCRIPTION:
XS GIS Cut Line= 4
      2270561.06     13236159.16      2269850.16      13235732.1
       2269251.2     13235883.14      2268654.87     13236200.84
#Sta/Elev= 30
  4358.4   193.8  4385.6  193.37  4420.6  191.17    4450  190.55  4455.9  189.83
  4508.3  187.98  4551.1  185.81  4653.9  181.79    4689   180.9  4741.5  178.44
  4762.9  178.13  4922.2  172.55    4993  171.53  4995.8  171.03    4999  171.53
  5155.6  172.85  5186.2  173.58  5262.4  173.59  5448.1  175.16  5621.4  175.08
  5654.3  174.55  5691.4  174.71  5843.6  176.33  5945.3  176.95  6078.8  175.91
  6159.6   175.9  6181.6   177.1  6203.5  176.86  6409.9  182.22  6481.1  183.02
#Mann= 7 ,-1 , 0
  4358.4     .05       0    4993     .03       0    4999     .05       0
  5621.4      .1       0  5691.4     .05       0  5843.6      .1       0
  6078.8     .05       0
Bank Sta=4993,4999
XS Rating Curve= 0 ,0
Exp/Cntr=0.3,0.1

Type RM Length L Ch R = 1 ,776     ,295,295,295
BEGIN DESCRIPTION:
Mapping XS efa8dbfd
END DESCRIPTION:
XS GIS Cut Line= 5
      2270545.49     13235995.15      2270292.87     13235620.12
      2270089.74     13235510.75      2269256.41      13235857.1
      2268626.24     13236198.23
#Sta/Elev= 30
  4433.7  191.18  4480.2  190.69  4510.1  191.18  4612.1  188.52    4705  184.21
    4762  180.76    4783   178.8  4887.6  172.64  4949.8   170.9  4959.9  170.29
  4982.3  167.09    4988  167.31  5001.2  166.27    5004  165.77  5007.2  166.27
  5016.7  169.01  5026.1  170.37  5031.8  169.61    5048   171.2  5178.2  174.34
  5405.9  175.09  5950.2  174.81  6093.3  176.55  6210.8  177.25    6261  176.18
  6330.5  176.08  6386.6  175.97  6540.6  179.12  6665.7  182.66  6735.6  183.17
#Mann= 7 ,-1 , 0
  4433.7     .05       0  4887.6     .16       0  5001.2     .07       0
  5007.2     .16       0  5178.2     .05       0  6093.3      .1       0
  6330.5     .05       0
Bank Sta=5001.2,5007.2
XS Rating Curve= 0 ,0
Exp/Cntr=0.3,0.1

Type RM Length L Ch R = 1 ,481     ,139,139,139
BEGIN DESCRIPTION:
Mapping XS d30718f6
END DESCRIPTION:
XS GIS Cut Line= 4
      2270603.13     13235740.99      2270441.31     13235366.65
      2270283.32     13235300.68      2268585.33     13236192.11
#Sta/Elev= 30
  4507.1  186.46  4522.5   186.2    4675  178.56  4711.5  177.49  4794.9  172.91
  4855.4  171.25    4973  169.38  4984.3  167.06  4991.7  161.68  4994.4  161.18
  4994.9  161.18  5002.7  161.89  5016.3   165.2  5026.5  166.36  5031.9   168.8
    5038  170.14  5048.9  170.85  5175.9  172.96  5236.4  174.56  5406.9  174.97
  5622.1  175.71  5657.2   175.2    6162  174.68    6344   176.7  6436.5  177.36
  6509.2  176.31  6587.9  176.15  6696.3  177.01  6916.9  182.96  7003.9  183.56
#Mann= 7 ,-1 , 0
  4507.1     .05       0  4855.4     .16       0  4994.9     .07       0
  5002.7     .16       0  5406.9     .05       0    6344      .1       0
  6587.9     .05       0
Bank Sta=4991.7,5002.7
XS Rating Curve= 0 ,0
Exp/Cntr=0.3,0.1

Type RM Length L Ch R = 1 ,342     ,0,0,0
BEGIN DESCRIPTION:
UNT 031 IN RACR 1.0
END DESCRIPTION:
XS GIS Cut Line= 4
      2270768.05     13235617.26      2270527.16      13235250.5
      2270368.74     13235189.74      2268601.39     13236117.87
#Sta/Elev= 30
  4456.9  181.71    4601  175.86  4817.1  170.25  4915.5  170.04  4945.5  169.08
  4959.4  166.22  4970.1  167.23  4975.6  165.83  4980.9  162.49  5002.6  158.59
  5005.3  158.09  5008.6  158.59  5012.9  164.16  5023.6   168.8    5045  168.18
  5063.2  169.15  5109.5  169.28  5115.1  170.31  5175.6  171.21  5203.3  172.74
  5307.9  174.83  5522.2  175.14  5924.8  175.29  6271.9  174.15  6507.1  176.71
  6574.9  177.21  6762.2  176.63  6872.3  177.99  6966.2  181.38  7061.6  183.53
#Mann= 7 ,-1 , 0
  4456.9     .05       0  4817.1      .1       0  5002.6     .07       0
  5008.6      .1       0  5522.2     .05       0  6507.1      .1       0
  6762.2     .05       0
Bank Sta=5002.6,5008.6
XS Rating Curve= 0 ,0
Exp/Cntr=0.3,0.1

Chan Stop Cuts=-1
Use User Specified Reach Order=0
Composite Channel Slope=5