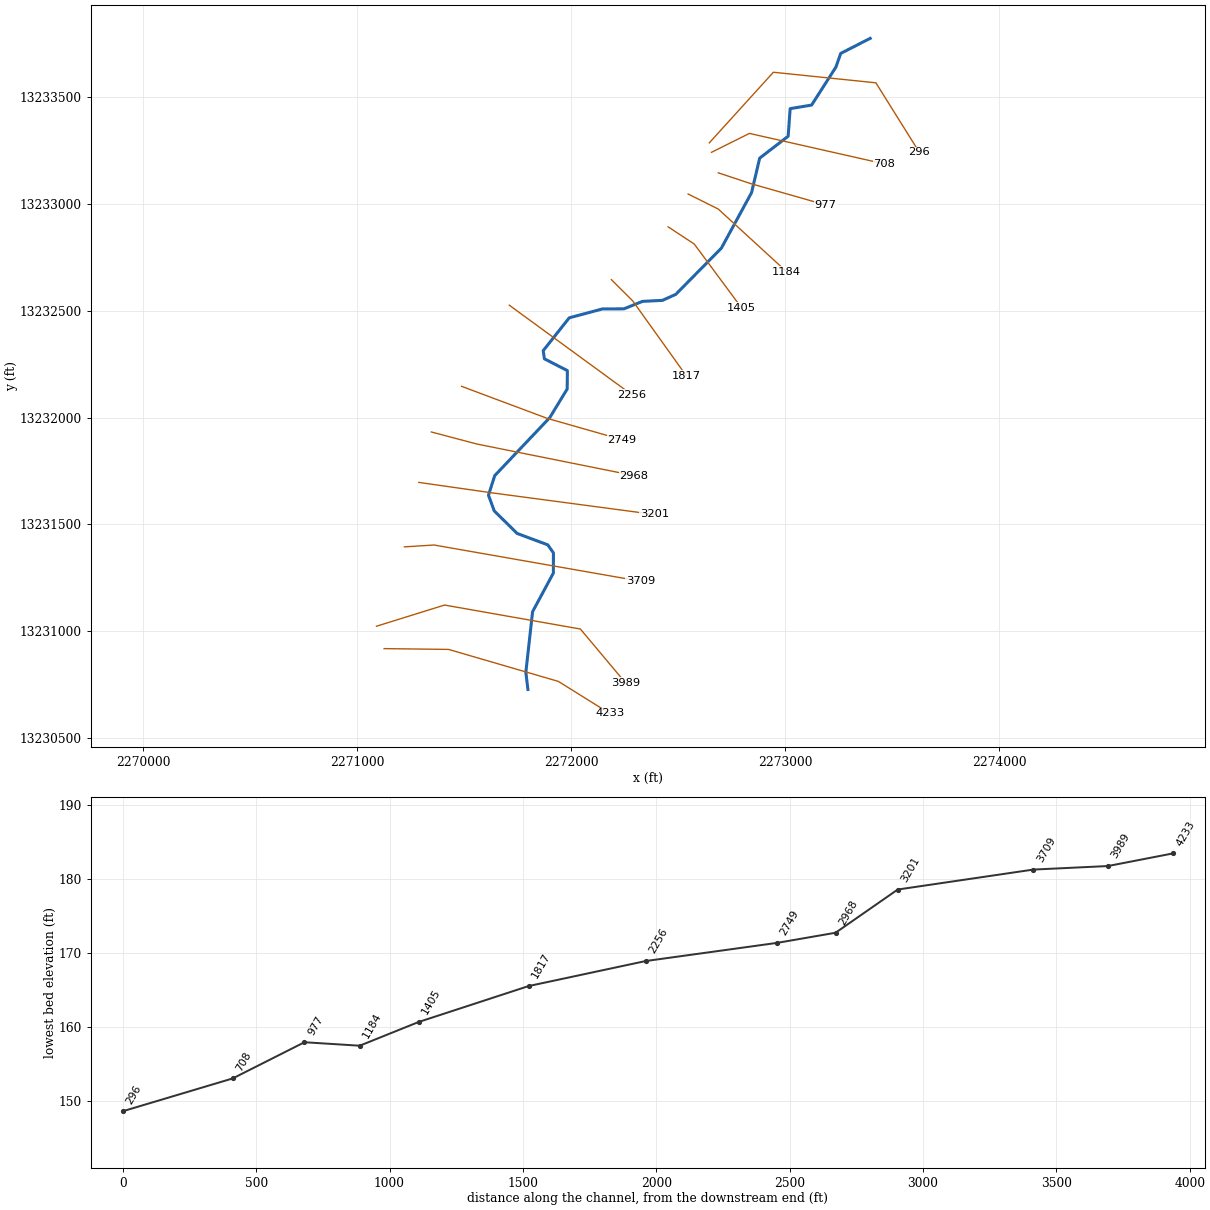
--- UNT 032 IN RACR.prj (project) ---

Proj Title=UNT 032 IN RACR Base Level Engineering
Current Plan=p01
Default Exp/Contr=0.3,0.1
English Units
Geom File=g01
Flow File=f01
Plan File=p01
Y Axis Title=Elevation
X Axis Title(PF)=Main Channel Distance
X Axis Title(XS)=Station
BEGIN DESCRIPTION:
UNT 032 IN RACR
END DESCRIPTION:
DSS Export Rating Curves= 0
DSS Export Rating Curve Sorted= 0
DSS Export Volume Flow Curves= 0
DXF OffsetX= 0
DXF OffsetY= 0
DXF ScaleX= 1
DXF ScaleY= 10

--- UNT 032 IN RACR.p01 (plan) ---

Plan Title=Multiple Run
Short Identifier=Multiple
Geom File=g01
Flow File=f01
Subcritical Flow
K Sum by GR= 0
Std Step Tol= 0.01
Critical Tol= 0.01
Num of Std Step Trials= 20
Max Error Tol= 0.3
Flow Tol Ratio= 0.001
Split Flow NTrial= 30
Split Flow Tol= 0.02
Split Flow Ratio= 0.02
Log Output Level= 0
Friction Slope Method= 1
Unsteady Friction Slope Method= 2
Unsteady Bridges Friction Slope Method= 1
Parabolic Critical Depth
Global Vel Dist=  1 , 1 , 1
Global Log Level= 0
CheckData=True
Encroach Param= -1, 0, 0, 0
BEGIN DESCRIPTION:
Multiple Run
END DESCRIPTION:

--- UNT 032 IN RACR.f01 (steady flow) ---

Flow Title=Multiple
Program Version=4.10
Number of Profiles= 7
Profile Names=10-year,25-year,50-year,1pct_min,100-year,1pct_plu,500-year
River Rch & RM=UNT 032 IN RACR,Reach-1         ,4233
     210     289     353     319     431     583     650
River Rch & RM=UNT 032 IN RACR,Reach-1         ,3989
     254     352     434     393     532     720     813
Boundary for River Rch & Prof#=UNT 032 IN RACR,Reach-1         , 1
Up Type= 0
Dn Type= 3
Dn Slope=0.011
Boundary for River Rch & Prof#=UNT 032 IN RACR,Reach-1         , 2
Up Type= 0
Dn Type= 3
Dn Slope=0.011
Boundary for River Rch & Prof#=UNT 032 IN RACR,Reach-1         , 3
Up Type= 0
Dn Type= 3
Dn Slope=0.011
Boundary for River Rch & Prof#=UNT 032 IN RACR,Reach-1         , 4
Up Type= 0
Dn Type= 3
Dn Slope=0.011
Boundary for River Rch & Prof#=UNT 032 IN RACR,Reach-1         , 5
Up Type= 0
Dn Type= 3
Dn Slope=0.011
Boundary for River Rch & Prof#=UNT 032 IN RACR,Reach-1         , 6
Up Type= 0
Dn Type= 3
Dn Slope=0.011
Boundary for River Rch & Prof#=UNT 032 IN RACR,Reach-1         , 7
Up Type= 0
Dn Type= 3
Dn Slope=0.011
DSS Import GetInterval= 0
DSS Import GetPeak= 0
DSS Import FillOption= 0

--- UNT 032 IN RACR.g01 (geometry) ---

Geom Title=Existing Conditions

River Reach=UNT 032 IN RACR,Reach-1
Reach XY= 30
      2271797.72     13230726.85      2271788.08     13230807.82
      2271819.52     13231091.29      2271916.83     13231272.37
      2271916.96     13231366.73      2271890.66     13231404.34
      2271747.37     13231457.76      2271640.28     13231563.54
      2271613.29     13231636.85      2271642.59     13231728.57
      2271899.78     13232000.21      2271981.34     13232134.43
      2271982.20     13232220.37      2271874.57     13232275.92
      2271869.36     13232314.12      2271990.88     13232467.76
      2272146.27     13232509.43      2272246.42     13232509.81
      2272333.54     13232544.88      2272426.63     13232549.49
      2272489.03     13232577.73      2272702.04     13232794.27
      2272843.09     13233054.06      2272881.07     13233215.71
      2273014.21     13233318.31      2273023.47     13233447.48
      2273123.81     13233464.28      2273237.47     13233642.15
      2273259.71     13233706.11      2273397.72     13233776.86

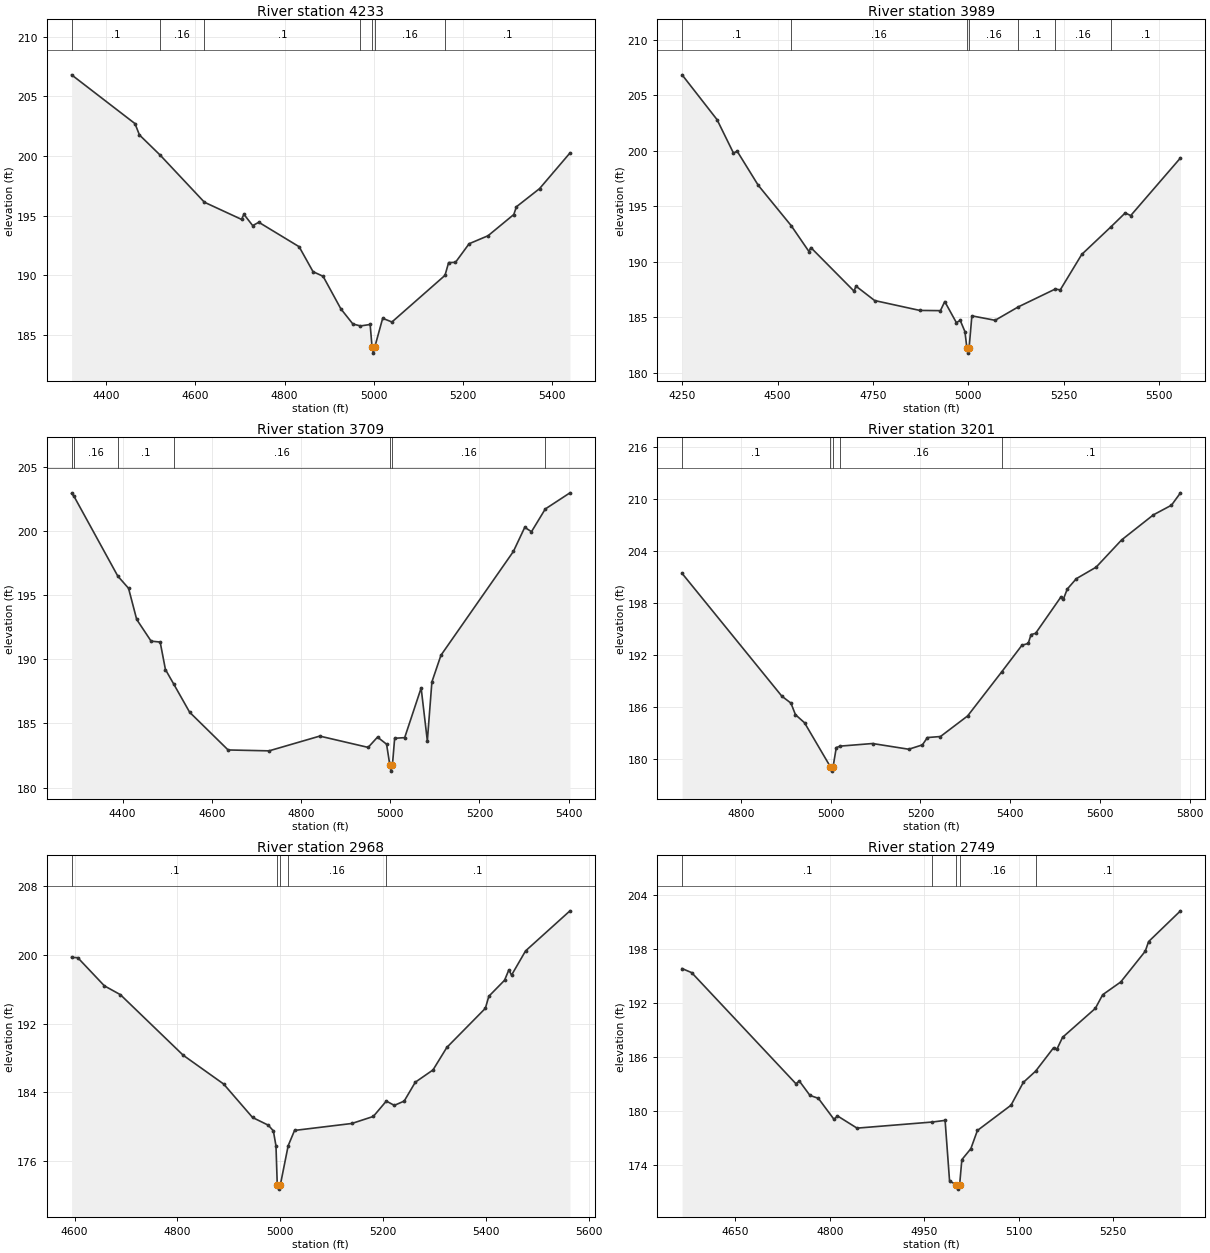
Type RM Length L Ch R = 1,4233,244,244,244
BEGIN DESCRIPTION:
UNT 032 IN RACR 9.0
END DESCRIPTION:
XS GIS Cut Line= 4
      2271125.45     13230918.32      2271426.92     13230914.57
      2271939.99     13230764.77      2272179.65     13230614.99
#Sta/Elev= 30
  4322.0  206.80  4464.3  202.71  4474.3  201.76  4520.8  200.07  4620.1  196.12
  4703.5  194.68  4708.7  195.11  4728.5  194.16  4742.2  194.44  4832.7  192.39
  4863.9  190.30  4886.5  189.91  4926.4  187.18  4953.4  185.91  4970.4  185.75
  4992.1  185.87  4996.4  183.97  4999.1  183.47  5002.4  183.97  5020.2  186.39
  5041.0  186.08  5160.1  189.99  5168.2  191.06  5183.6  191.08  5214.2  192.64
  5256.7  193.31  5314.5  195.09  5320.4  195.74  5372.3  197.26  5440.6  200.25
#Mann=7,-1,0
  4322.0     0.1       0  4520.8    0.16       0  4620.1     0.1       0
  4970.4    0.16       0  4996.4    0.07       0  5002.4    0.16       0
  5160.1     0.1       0
Bank Sta=4996.4,5002.4
Exp/Cntr=0.3,0.1

Type RM Length L Ch R = 1,3989,280,280,280
BEGIN DESCRIPTION:
Mapping XS 0550f667
END DESCRIPTION:
XS GIS Cut Line= 4
      2271089.85     13231023.18      2271408.19     13231122.42
      2272042.98     13231010.07      2272253.63     13230758.41
#Sta/Elev= 30
  4249.8  206.85  4341.4  202.81  4384.4  199.80  4394.2  199.96  4449.4  196.89
  4536.0  193.24  4582.3  190.92  4587.2  191.28  4700.4  187.35  4705.5  187.80
  4754.5  186.50  4872.8  185.61  4926.9  185.59  4938.2  186.41  4968.7  184.51
  4978.8  184.71  4991.1  183.70  4996.1  182.26  4998.9  181.76  5002.1  182.26
  5009.3  185.12  5070.2  184.72  5131.0  185.93  5228.0  187.54  5240.9  187.46
  5297.3  190.66  5373.3  193.13  5411.3  194.40  5425.6  194.16  5556.1  199.36
#Mann=7,-1,0
  4249.8     0.1       0  4536.0    0.16       0  4996.1    0.07       0
  5002.1    0.16       0  5131.0     0.1       0  5228.0    0.16       0
  5373.3     0.1       0
Bank Sta=4996.1,5002.1
Exp/Cntr=0.3,0.1

Type RM Length L Ch R = 1,3709,508,508,508
BEGIN DESCRIPTION:
UNT 032 IN RACR 8.0
END DESCRIPTION:
XS GIS Cut Line= 3
      2271220.31     13231394.92      2271359.15     13231403.60
      2272322.68     13231234.33
#Sta/Elev= 30
  4285.7  202.92  4291.1  202.70  4389.3  196.48  4413.4  195.53  4431.7  193.10
  4464.0  191.41  4484.3  191.34  4496.1  189.20  4514.3  188.09  4550.4  185.87
  4636.6  182.93  4728.4  182.86  4842.1  184.01  4950.6  183.13  4971.6  183.93
  4991.9  183.38  4999.1  181.78  5001.8  181.28  5005.1  181.78  5010.0  183.84
  5032.5  183.89  5069.4  187.76  5083.3  183.64  5093.5  188.23  5113.8  190.31
  5276.2  198.40  5301.7  200.28  5316.8  199.94  5347.7  201.71  5403.1  202.97
#Mann=7,-1,0
  4285.7     0.1       0  4291.1    0.16       0  4389.3     0.1       0
  4514.3    0.16       0  4999.1    0.07       0  5005.1    0.16       0
  5347.7     0.1       0
Bank Sta=4999.1,5005.1
Exp/Cntr=0.3,0.1

Type RM Length L Ch R = 1,3201,233,233,233
BEGIN DESCRIPTION:
UNT 032 IN RACR 7.0
END DESCRIPTION:
XS GIS Cut Line= 3
      2271287.77     13231696.85      2271637.72     13231646.85
      2272387.68     13231546.86
#Sta/Elev= 30
  4669.2  201.43  4891.4  187.24  4911.6  186.44  4921.7  185.10  4941.9  184.17
  4999.5  179.08  5002.3  178.58  5005.5  179.08  5012.6  181.30  5021.4  181.47
  5093.3  181.77  5174.0  181.11  5204.3  181.61  5215.6  182.46  5244.7  182.58
  5305.2  184.96  5381.5  190.08  5426.2  193.13  5440.1  193.33  5446.4  194.36
  5456.5  194.50  5513.3  198.73  5518.3  198.43  5527.1  199.62  5547.3  200.82
  5591.4  202.15  5648.2  205.30  5718.8  208.19  5759.2  209.31  5779.3  210.74
#Mann=5,-1,0
  4669.2     0.1       0  4999.5    0.07       0  5005.5     0.1       0
  5021.4    0.16       0  5381.5     0.1       0
Bank Sta=4999.5,5005.5
Exp/Cntr=0.3,0.1

Type RM Length L Ch R = 1,2968,219,219,219
BEGIN DESCRIPTION:
Mapping XS 43c2247b
END DESCRIPTION:
XS GIS Cut Line= 3
      2271346.10     13231933.12      2271558.80     13231876.69
      2272292.35     13231729.11
#Sta/Elev= 30
  4594.3  199.73  4606.3  199.70  4658.0  196.42  4689.1  195.39  4811.2  188.33
  4889.7  184.98  4945.9  181.08  4976.5  180.18  4986.3  179.52  4991.4  177.77
  4993.9  173.23  4996.6  172.73  4999.9  173.23  5015.1  177.79  5027.5  179.57
  5138.8  180.38  5180.5  181.20  5205.8  182.99  5221.3  182.49  5240.5  182.99
  5262.1  185.19  5296.5  186.62  5323.3  189.24  5398.2  193.80  5404.9  195.20
  5435.5  197.07  5443.9  198.29  5449.0  197.66  5476.3  200.49  5562.6  205.16
#Mann=5,-1,0
  4594.3     0.1       0  4993.9    0.07       0  4999.9     0.1       0
  5015.1    0.16       0  5205.8     0.1       0
Bank Sta=4993.9,4999.9
Exp/Cntr=0.3,0.1

Type RM Length L Ch R = 1,2749,493,493,493
BEGIN DESCRIPTION:
UNT 032 IN RACR 6.0
END DESCRIPTION:
XS GIS Cut Line= 3
      2271487.68     13232146.87      2271887.72     13231996.85
      2272237.67     13231896.87
#Sta/Elev= 30
  4565.7  195.84  4580.9  195.39  4746.4  183.06  4751.8  183.36  4768.7  181.76
  4782.0  181.44  4806.9  179.10  4812.3  179.49  4843.4  178.13  4963.2  178.81
  4983.2  178.99  4990.3  172.27  5000.3  171.86  5003.1  171.36  5006.3  171.86
  5009.8  174.63  5024.1  175.85  5034.5  177.87  5087.8  180.67  5107.3  183.20
  5127.0  184.46  5155.4  187.05  5160.6  186.88  5169.7  188.21  5221.7  191.42
  5233.4  192.94  5262.0  194.35  5301.0  197.77  5306.2  198.83  5356.9  202.25
#Mann=5,-1,0
  4565.7     0.1       0  4963.2    0.16       0  5000.3    0.07       0
  5006.3    0.16       0  5127.0     0.1       0
Bank Sta=5000.3,5006.3
Exp/Cntr=0.3,0.1

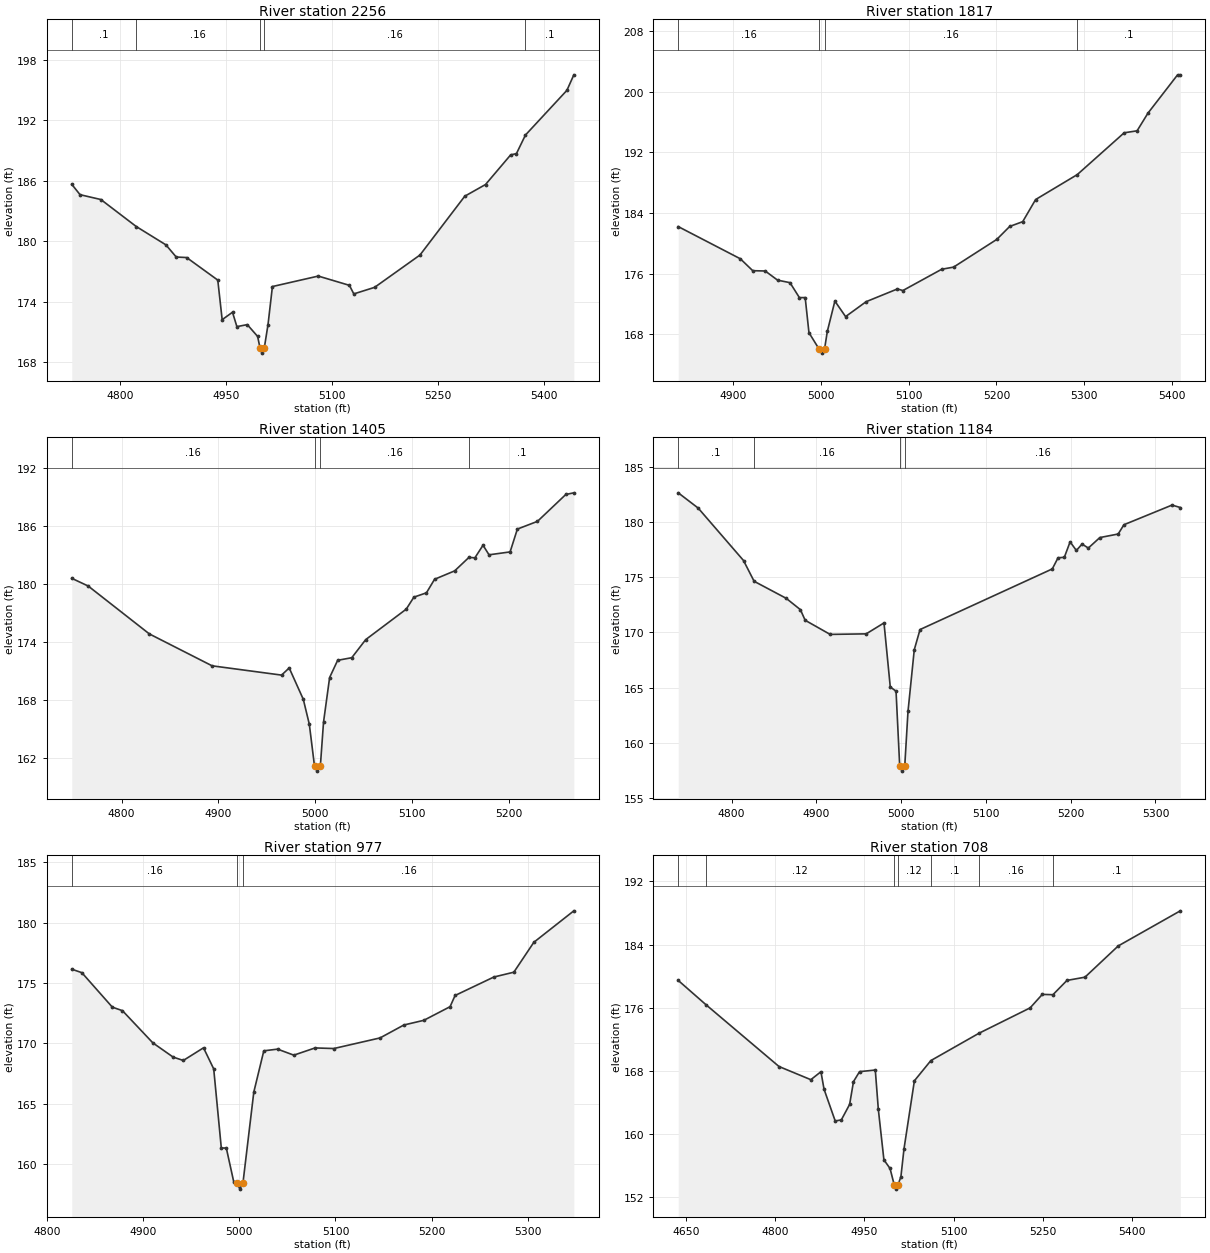
Type RM Length L Ch R = 1,2256,439,439,439
BEGIN DESCRIPTION:
UNT 032 IN RACR 5.0
END DESCRIPTION:
XS GIS Cut Line= 2
      2271710.67     13232526.89      2272283.15     13232107.94
#Sta/Elev= 30
  4732.2  185.66  4743.9  184.63  4773.3  184.15  4823.3  181.47  4865.2  179.65
  4879.8  178.44  4894.5  178.39  4938.5  176.15  4944.7  172.22  4959.3  172.96
  4965.5  171.53  4980.2  171.73  4994.8  170.56  4998.2  169.40  5000.9  168.90
  5004.2  169.40  5009.5  171.74  5015.7  175.51  5080.5  176.55  5124.5  175.63
  5130.7  174.78  5160.1  175.43  5224.2  178.64  5287.5  184.48  5316.8  185.64
  5352.3  188.58  5360.5  188.71  5373.2  190.55  5431.8  194.99  5441.6  196.53
#Mann=5,-1,0
  4732.2     0.1       0  4823.3    0.16       0  4998.2    0.07       0
  5004.2    0.16       0  5373.2     0.1       0
Bank Sta=4998.2,5004.2
Exp/Cntr=0.3,0.1

Type RM Length L Ch R = 1,1817,412,412,412
BEGIN DESCRIPTION:
UNT 032 IN RACR 4.0
END DESCRIPTION:
XS GIS Cut Line= 3
      2272187.74     13232646.83      2272287.72     13232546.85
      2272537.72     13232196.86
#Sta/Elev= 30
  4837.8  182.21  4908.5  177.96  4922.6  176.39  4936.8  176.35  4950.9  175.14
  4965.0  174.81  4975.7  172.84  4982.3  172.84  4986.6  168.21  4998.3  166.01
  5001.1  165.51  5004.3  166.01  5007.5  168.38  5016.1  172.38  5028.3  170.33
  5051.7  172.30  5087.3  173.98  5093.5  173.77  5137.7  176.58  5151.2  176.86
  5200.4  180.52  5215.1  182.23  5229.9  182.86  5244.6  185.78  5292.0  189.07
  5345.4  194.59  5360.1  194.85  5372.4  197.17  5406.2  202.24  5409.3  202.24
#Mann=4,-1,0
  4837.8    0.16       0  4998.3    0.07       0  5004.3    0.16       0
  5292.0     0.1       0
Bank Sta=4998.3,5004.3
Exp/Cntr=0.3,0.1

Type RM Length L Ch R = 1,1405,221,221,221
BEGIN DESCRIPTION:
UNT 032 IN RACR 3.0
END DESCRIPTION:
XS GIS Cut Line= 3
      2272452.86     13232894.08      2272575.30     13232813.32
      2272796.67     13232513.82
#Sta/Elev= 30
  4748.4  180.59  4765.4  179.79  4828.6  174.84  4893.5  171.54  4965.3  170.58
  4973.2  171.32  4987.8  168.07  4994.0  165.50  4999.4  161.15  5002.2  160.65
  5005.4  161.15  5008.7  165.72  5015.0  170.33  5023.3  172.11  5037.9  172.38
  5052.3  174.25  5094.2  177.40  5102.1  178.64  5115.1  179.09  5123.5  180.49
  5144.3  181.36  5159.0  182.75  5165.2  182.71  5173.6  184.01  5179.8  183.02
  5201.6  183.32  5209.1  185.68  5229.9  186.48  5259.2  189.26  5267.5  189.43
#Mann=4,-1,0
  4748.4    0.16       0  4999.4    0.07       0  5005.4    0.16       0
  5159.0     0.1       0
Bank Sta=4999.4,5005.4
Exp/Cntr=0.3,0.1

Type RM Length L Ch R = 1,1184,207,207,207
BEGIN DESCRIPTION:
Mapping XS dc2441b9
END DESCRIPTION:
XS GIS Cut Line= 3
      2272546.68     13233047.68      2272687.27     13232977.39
      2273007.62     13232683.09
#Sta/Elev= 30
  4737.1  182.64  4760.6  181.26  4814.1  176.51  4826.6  174.63  4864.4  173.09
  4881.2  172.06  4886.8  171.10  4916.3  169.82  4958.8  169.87  4979.8  170.86
  4987.2  165.06  4994.0  164.68  4998.3  157.94  5001.1  157.44  5004.3  157.94
  5008.1  162.84  5015.5  168.43  5022.3  170.26  5178.3  175.75  5185.1  176.76
  5192.5  176.80  5199.3  178.20  5206.7  177.42  5213.4  178.00  5220.8  177.64
  5234.4  178.59  5256.0  178.91  5262.8  179.75  5319.5  181.53  5329.3  181.31
#Mann=4,-1,0
  4737.1     0.1       0  4826.6    0.16       0  4998.3    0.07       0
  5004.3    0.16       0
Bank Sta=4998.3,5004.3
Exp/Cntr=0.3,0.1

Type RM Length L Ch R = 1,977,269,269,269
BEGIN DESCRIPTION:
UNT 032 IN RACR 2.0
END DESCRIPTION:
XS GIS Cut Line= 3
      2272687.72     13233146.86      2272837.72     13233096.85
      2273187.70     13232996.86
#Sta/Elev= 30
  4825.8  176.15  4836.3  175.86  4868.0  173.00  4878.5  172.71  4910.1  170.04
  4931.2  168.86  4941.8  168.58  4962.8  169.63  4973.4  167.88  4981.3  161.32
  4986.5  161.32  4994.3  158.49  4997.8  158.41  5000.6  157.91  5003.8  158.41
  5015.1  165.96  5025.5  169.38  5039.8  169.52  5056.7  169.02  5078.8  169.62
  5098.3  169.57  5146.4  170.45  5171.1  171.52  5191.9  171.91  5219.2  173.04
  5224.4  173.97  5264.7  175.50  5285.5  175.90  5306.3  178.38  5347.9  180.99
#Mann=3,-1,0
  4825.8    0.16       0  4997.8    0.07       0  5003.8    0.16       0
Bank Sta=4997.8,5003.8
Exp/Cntr=0.3,0.1

Type RM Length L Ch R = 1,708,412,412,412
BEGIN DESCRIPTION:
Mapping XS 428116de
END DESCRIPTION:
XS GIS Cut Line= 3
      2272656.04     13233243.02      2272833.11     13233331.55
      2273464.28     13233188.69
#Sta/Elev= 30
  4636.6  179.46  4683.0  176.40  4806.2  168.55  4859.8  166.88  4876.8  167.89
  4882.0  165.68  4900.8  161.65  4911.1  161.78  4925.1  163.75  4931.6  166.64
  4941.8  167.90  4968.3  168.10  4973.4  163.12  4982.8  156.72  4993.1  155.63
  5000.3  153.51  5003.1  153.01  5006.3  153.51  5011.4  154.58  5016.6  158.11
  5034.1  166.74  5061.8  169.30  5142.7  172.76  5228.9  175.98  5249.4  177.69
  5267.3  177.65  5290.9  179.46  5321.2  179.87  5377.2  183.83  5481.7  188.28
#Mann=7,-1,0
  4636.6    0.16       0  4683.0    0.12       0  5000.3    0.07       0
  5006.3    0.12       0  5061.8     0.1       0  5142.7    0.16       0
  5267.3     0.1       0
Bank Sta=5000.3,5006.3
Exp/Cntr=0.3,0.1

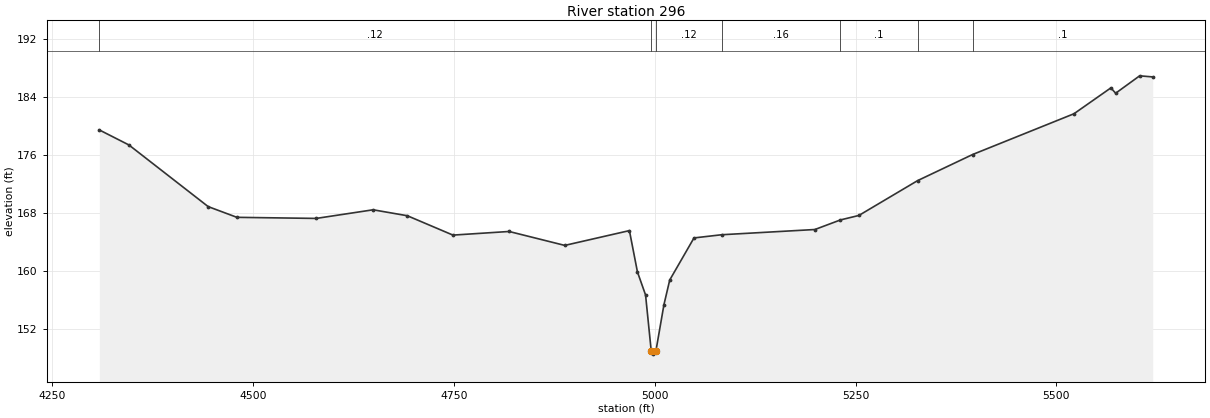
Type RM Length L Ch R = 1,296,0,0,0
BEGIN DESCRIPTION:
UNT 032 IN RACR 1.0
END DESCRIPTION:
XS GIS Cut Line= 4
      2272645.58     13233287.25      2272945.09     13233618.01
      2273424.25     13233568.53      2273627.37     13233243.03
#Sta/Elev= 30
  4308.4  179.48  4345.2  177.41  4443.9  168.91  4479.7  167.43  4578.4  167.28
  4649.3  168.47  4691.9  167.65  4748.7  164.98  4818.6  165.48  4887.9  163.56
  4968.4  165.60  4978.4  159.90  4988.5  156.73  4995.5  149.07  4998.3  148.57
  5001.5  149.07  5011.4  155.39  5018.6  158.79  5048.8  164.59  5083.3  165.03
  5199.3  165.75  5231.1  167.07  5254.1  167.69  5327.2  172.49  5395.7  176.09
  5521.9  181.71  5567.9  185.28  5573.8  184.54  5603.7  186.94  5620.0  186.79
#Mann=7,-1,0
  4308.4    0.12       0  4995.5    0.07       0  5001.5    0.12       0
  5083.3    0.16       0  5231.1     0.1       0  5327.2    0.16       0
  5395.7     0.1       0
Bank Sta=4995.5,5001.5
Exp/Cntr=0.3,0.1

Chan Stop Cuts=-1