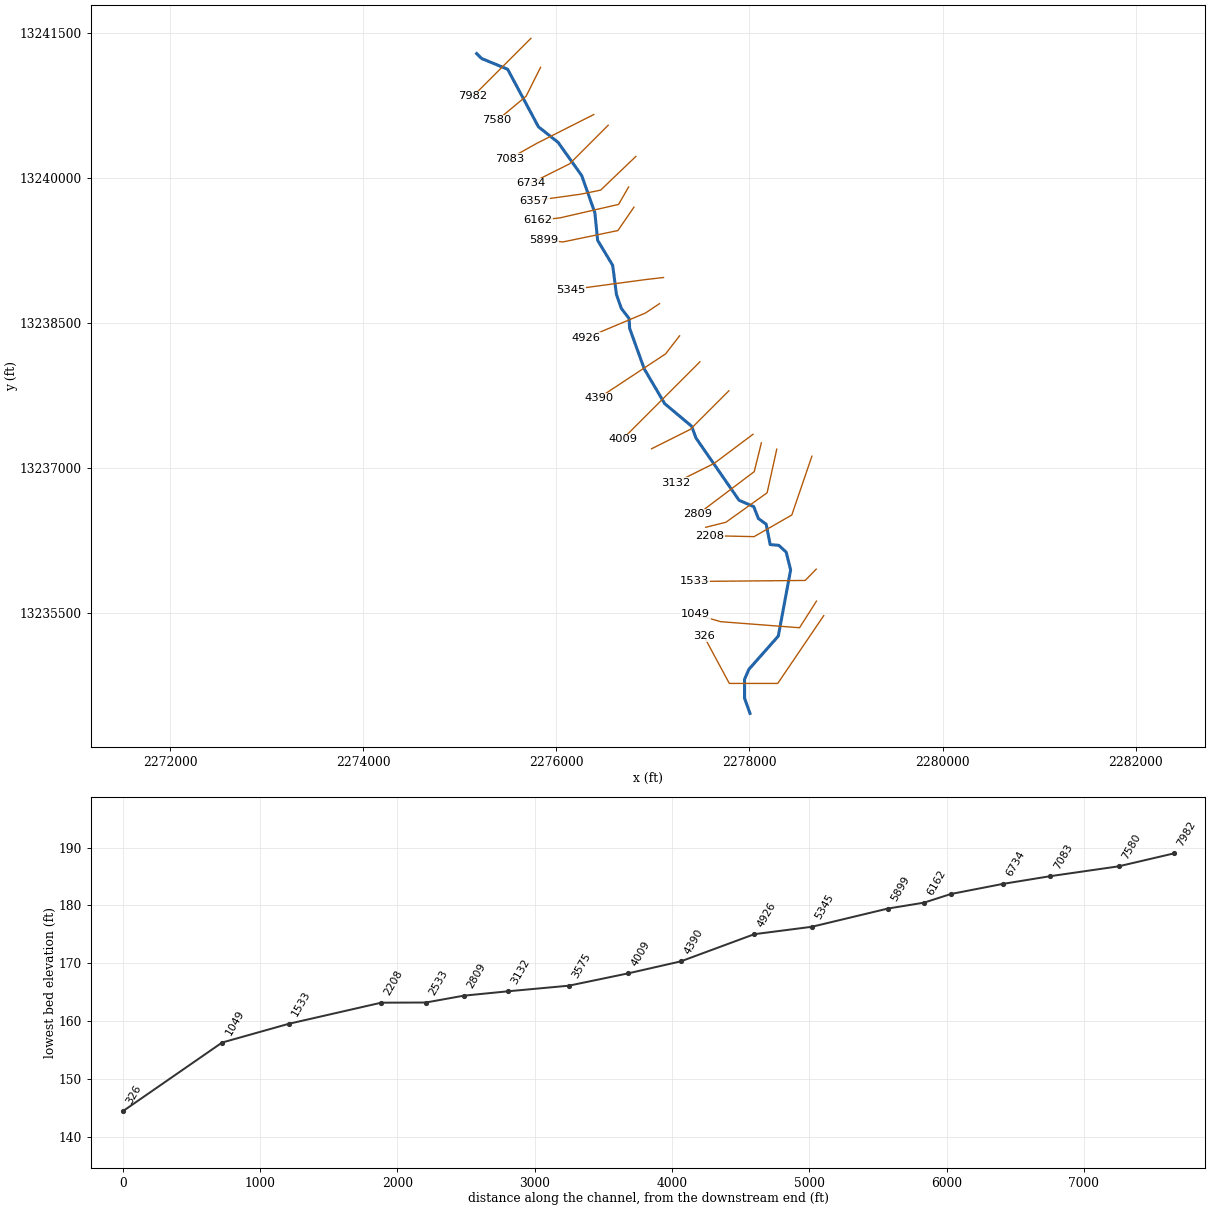
--- UNT 033 IN RACR.prj (project) ---

Proj Title=UNT 033 IN RACR Base Level Engineering
Current Plan=p01
Default Exp/Contr=0.3,0.1
English Units
Geom File=g01
Flow File=f01
Plan File=p01
BEGIN DESCRIPTION:
UNT 033 IN RACR
END DESCRIPTION:

--- UNT 033 IN RACR.p01 (plan) ---

Plan Title=Multiple Run
Short Identifier=Multiple
Geom File=g01
Flow File=f01
Subcritical Flow
K Sum by GR= 0
Std Step Tol= 0.01
Critical Tol= 0.01
Num of Std Step Trials= 20
Max Error Tol= 0.3
Flow Tol Ratio= 0.001
Split Flow NTrial= 30
Split Flow Tol= 0.02
Split Flow Ratio= 0.02
Log Output Level= 0
Friction Slope Method= 1
Unsteady Friction Slope Method= 2
Unsteady Bridges Friction Slope Method= 1
Parabolic Critical Depth
Global Vel Dist=  1 , 1 , 1
Global Log Level= 0
CheckData=True
Encroach Param= -1, 0, 0, 0
BEGIN DESCRIPTION:
Multiple Run
END DESCRIPTION:

--- UNT 033 IN RACR.f01 (steady flow) ---

Flow Title=Multiple
Number of Profiles=7
Profile Names=10-year,25-year,50-year,1pct_min,100-year,1pct_plu,500-year
River Rch & RM= UNT 033 IN RACR,Reach-1,7982
     263     367     455     415     562     760     868
River Rch & RM= UNT 033 IN RACR,Reach-1,7083
     348     491     613     562     761    1028    1188
Boundary for River Rch & Prof#=UNT 033 IN RACR,Reach-1,1
Up Type=0
Dn Type=3
Dn Slope=0.005
Boundary for River Rch & Prof#=UNT 033 IN RACR,Reach-1,2
Up Type=0
Dn Type=3
Dn Slope=0.005
Boundary for River Rch & Prof#=UNT 033 IN RACR,Reach-1,3
Up Type=0
Dn Type=3
Dn Slope=0.005
Boundary for River Rch & Prof#=UNT 033 IN RACR,Reach-1,4
Up Type=0
Dn Type=3
Dn Slope=0.005
Boundary for River Rch & Prof#=UNT 033 IN RACR,Reach-1,5
Up Type=0
Dn Type=3
Dn Slope=0.005
Boundary for River Rch & Prof#=UNT 033 IN RACR,Reach-1,6
Up Type=0
Dn Type=3
Dn Slope=0.005
Boundary for River Rch & Prof#=UNT 033 IN RACR,Reach-1,7
Up Type=0
Dn Type=3
Dn Slope=0.005

--- UNT 033 IN RACR.g01 (geometry) ---

Geom Title=Existing Conditions

River Reach=UNT 033 IN RACR,Reach-1
Reach XY= 30
      2275175.84     13241289.63      2275227.73     13241237.78
      2275496.87     13241126.65      2275815.78     13240530.65
      2276020.02     13240368.63      2276264.08     13240024.73
      2276400.03     13239640.18      2276428.65     13239355.10
      2276584.64     13239095.60      2276623.37     13238793.74
      2276674.01     13238650.07      2276754.15     13238545.47
      2276760.29     13238442.70      2276911.46     13238023.69
      2277122.69     13237664.31      2277402.73     13237429.38
      2277447.69     13237306.77      2277892.60     13236663.89
      2278044.91     13236597.78      2278093.25     13236474.50
      2278174.10     13236415.25      2278215.25     13236204.41
      2278304.09     13236196.93      2278381.26     13236126.02
      2278427.16     13235942.38      2278299.52     13235257.12
      2277995.29     13234913.25      2277950.13     13234810.84
      2277950.38     13234612.30      2278006.42     13234456.60

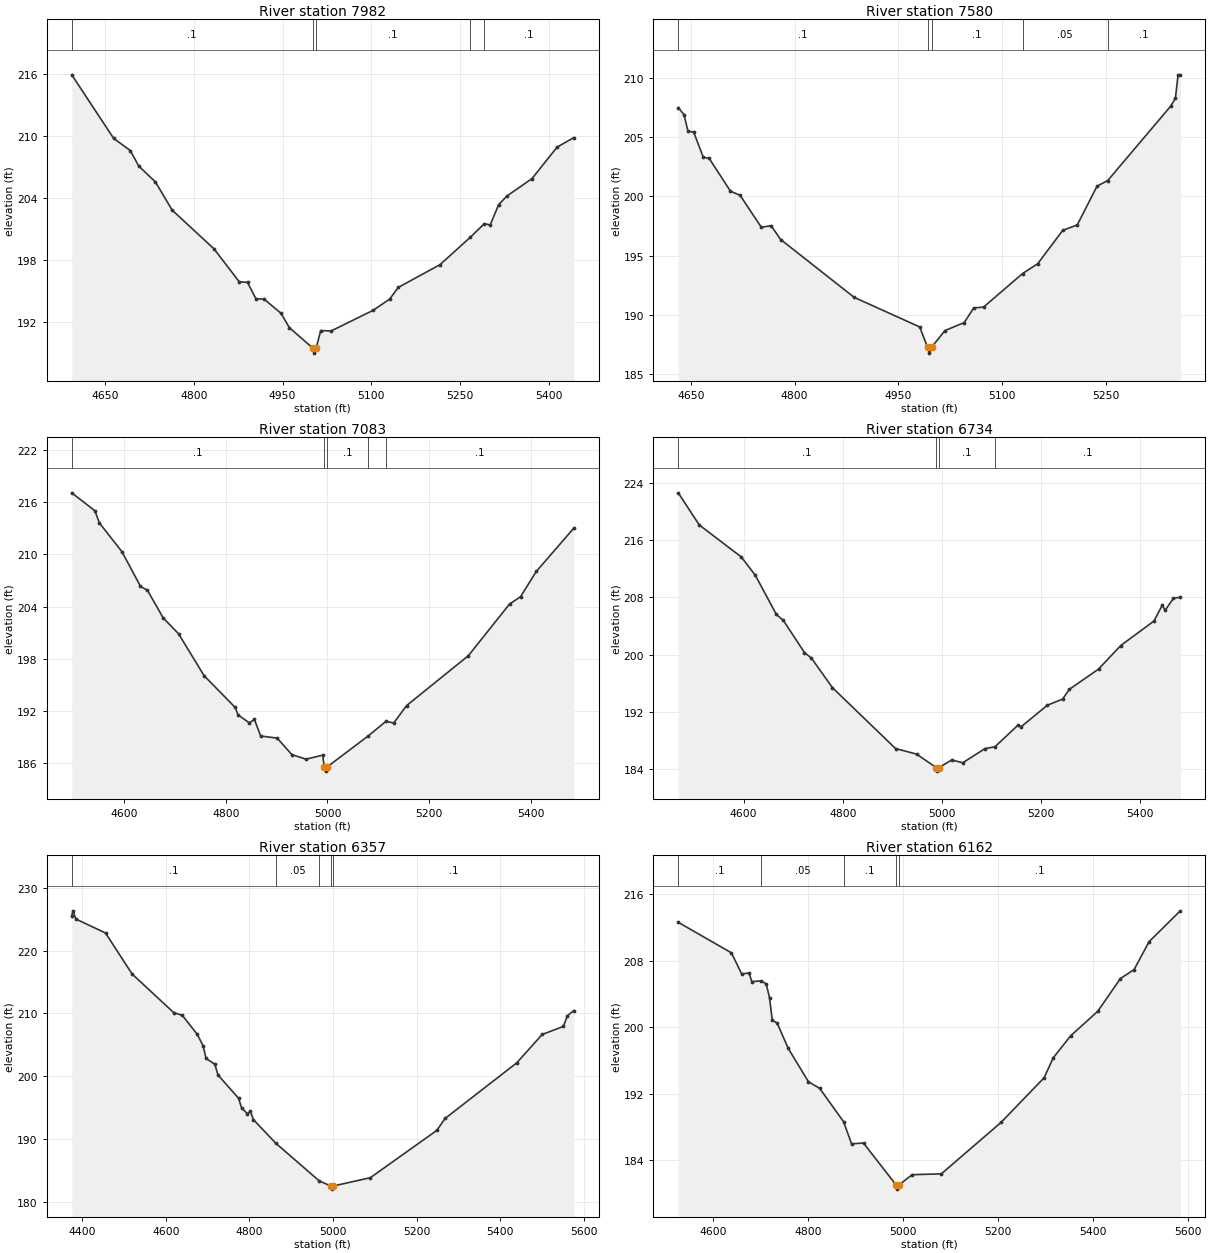
Type RM Length L Ch R = 1,7982,402,402,402
BEGIN DESCRIPTION:
UNT 033 IN RACR 17.0
END DESCRIPTION:
XS GIS Cut Line= 3
      2275737.73     13241446.86      2275437.72     13241146.85
      2275137.75     13240846.88
#Sta/Elev= 30
  4593.7  215.96  4664.4  209.81  4692.7  208.62  4706.8  207.13  4735.1  205.58
  4763.4  202.85  4834.1  199.10  4876.6  195.92  4890.7  195.85  4904.8  194.28
  4919.0  194.22  4947.3  192.86  4961.4  191.47  5000.8  189.50  5003.6  189.00
  5006.8  189.50  5014.4  191.18  5032.1  191.15  5102.8  193.14  5131.1  194.24
  5145.3  195.36  5216.0  197.57  5267.0  200.21  5291.1  201.55  5300.8  201.41
  5315.0  203.37  5329.1  204.22  5371.5  205.91  5414.0  208.96  5442.2  209.88
#Mann=5,-1,0
  4593.7     0.1       0  5000.8    0.07       0  5006.8     0.1       0
  5267.0    0.05       0  5291.1     0.1       0
Bank Sta=5000.8,5006.8
Exp/Cntr=0.3,0.1

Type RM Length L Ch R = 1,7580,497,497,497
BEGIN DESCRIPTION:
UNT 033 IN RACR 16.0
END DESCRIPTION:
XS GIS Cut Line= 3
      2275837.72     13241146.84      2275687.72     13240846.85
      2275387.73     13240596.86
#Sta/Elev= 30
  4631.8  207.49  4640.2  206.90  4645.8  205.52  4654.1  205.42  4668.1  203.30
  4676.5  203.21  4707.3  200.44  4721.2  200.09  4752.0  197.39  4766.0  197.53
  4779.9  196.36  4886.1  191.48  4980.9  188.98  4992.2  187.27  4994.9  186.77
  4998.2  187.27  5017.3  188.67  5045.3  189.35  5059.0  190.58  5073.3  190.66
  5129.7  193.49  5151.4  194.31  5187.8  197.14  5208.7  197.59  5237.3  200.86
  5252.8  201.34  5344.0  207.63  5350.6  208.29  5354.5  210.26  5357.7  210.26
#Mann=5,-1,0
  4631.8     0.1       0  4992.2    0.07       0  4998.2     0.1       0
  5129.7    0.05       0  5252.8     0.1       0
Bank Sta=4992.2,4998.2
Exp/Cntr=0.3,0.1

Type RM Length L Ch R = 1,7083,349,349,349
BEGIN DESCRIPTION:
UNT 033 IN RACR 15.0
END DESCRIPTION:
XS GIS Cut Line= 3
      2276388.38     13240657.72      2275798.10     13240359.11
      2275513.36     13240199.37
#Sta/Elev= 30
  4496.8  217.09  4542.4  215.02  4551.0  213.64  4595.6  210.31  4632.0  206.33
  4645.8  205.87  4676.8  202.69  4707.0  200.87  4757.2  196.05  4818.4  192.40
  4824.0  191.54  4846.3  190.62  4856.2  191.02  4868.6  189.11  4901.0  188.87
  4929.8  186.98  4957.7  186.44  4990.6  186.91  4993.7  185.57  4996.4  185.07
  4999.7  185.57  5080.4  189.13  5115.1  190.80  5130.4  190.61  5155.7  192.61
  5277.2  198.35  5358.2  204.29  5379.9  205.14  5411.0  208.05  5484.8  213.03
#Mann=5,-1,0
  4496.8     0.1       0  4993.7    0.07       0  4999.7     0.1       0
  5080.4    0.05       0  5115.1     0.1       0
Bank Sta=4993.7,4999.7
Exp/Cntr=0.3,0.1

Type RM Length L Ch R = 1,6734,377,377,377
BEGIN DESCRIPTION:
UNT 033 IN RACR 14.0
END DESCRIPTION:
XS GIS Cut Line= 3
      2276537.73     13240546.86      2276137.72     13240146.85
      2275737.73     13239946.86
#Sta/Elev= 30
  4468.0  222.63  4510.4  218.14  4595.3  213.66  4623.6  211.09  4666.0  205.62
  4680.1  204.79  4722.6  200.30  4736.7  199.52  4779.1  195.39  4906.4  186.88
  4948.8  186.10  4988.3  184.22  4991.0  183.72  4994.3  184.22  5019.6  185.28
  5042.1  184.89  5086.8  186.87  5106.9  187.12  5153.9  190.18  5159.5  189.91
  5212.6  192.93  5243.3  193.79  5257.3  195.17  5316.0  197.99  5360.7  201.28
  5427.8  204.71  5444.6  206.93  5450.2  206.20  5466.9  207.87  5480.9  208.05
#Mann=4,-1,0
  4468.0     0.1       0  4988.3    0.04       0  4994.3     0.1       0
  5106.9     0.1       0
Bank Sta=4988.3,4994.3
Exp/Cntr=0.3,0.1

Type RM Length L Ch R = 1,6357,195,195,195
BEGIN DESCRIPTION:
Mapping XS f311e99d
END DESCRIPTION:
XS GIS Cut Line= 4
      2276824.60     13240224.18      2276459.98     13239875.19
      2276256.85     13239833.52      2275772.63     13239765.84
#Sta/Elev= 30
  4375.2  225.59  4378.2  226.34  4385.1  225.03  4455.9  222.81  4519.7  216.26
  4618.8  210.13  4639.8  209.67  4675.4  206.65  4689.3  204.83  4696.5  202.81
  4717.5  201.88  4724.8  200.19  4774.1  196.47  4781.4  194.94  4795.5  193.98
  4802.4  194.42  4809.7  193.06  4863.8  189.26  4967.4  183.28  4994.8  182.48
  4997.6  181.98  5000.8  182.48  5089.4  183.80  5248.4  191.34  5268.1  193.24
  5439.8  202.12  5500.4  206.63  5550.9  207.91  5561.0  209.63  5576.2  210.44
#Mann=5,-1,0
  4375.2     0.1       0  4863.8    0.05       0  4967.4     0.1       0
  4994.8    0.07       0  5000.8     0.1       0
Bank Sta=4994.8,5000.8
Exp/Cntr=0.3,0.1

Type RM Length L Ch R = 1,6162,263,263,263
BEGIN DESCRIPTION:
UNT 033 IN RACR 13.0
END DESCRIPTION:
XS GIS Cut Line= 4
      2276749.48     13239907.70      2276645.32     13239727.16
      2276041.16     13239588.27      2275812.38     13239560.54
#Sta/Elev= 30
  4525.9  212.64  4638.0  208.96  4659.6  206.43  4675.3  206.52  4681.1  205.49
  4700.6  205.58  4711.6  205.21  4718.4  203.54  4724.2  200.85  4734.3  200.51
  4757.8  197.45  4800.6  193.42  4824.2  192.63  4874.6  188.61  4891.4  185.95
  4916.6  186.04  4985.4  180.99  4988.1  180.49  4991.4  180.99  5019.2  182.23
  5080.7  182.33  5206.7  188.53  5297.5  193.91  5316.7  196.31  5353.4  198.96
  5410.4  201.90  5458.4  205.86  5487.2  206.94  5518.9  210.31  5584.7  214.02
#Mann=5,-1,0
  4525.9     0.1       0  4700.6    0.05       0  4874.6     0.1       0
  4985.4    0.07       0  4991.4     0.1       0
Bank Sta=4985.4,4991.4
Exp/Cntr=0.3,0.1

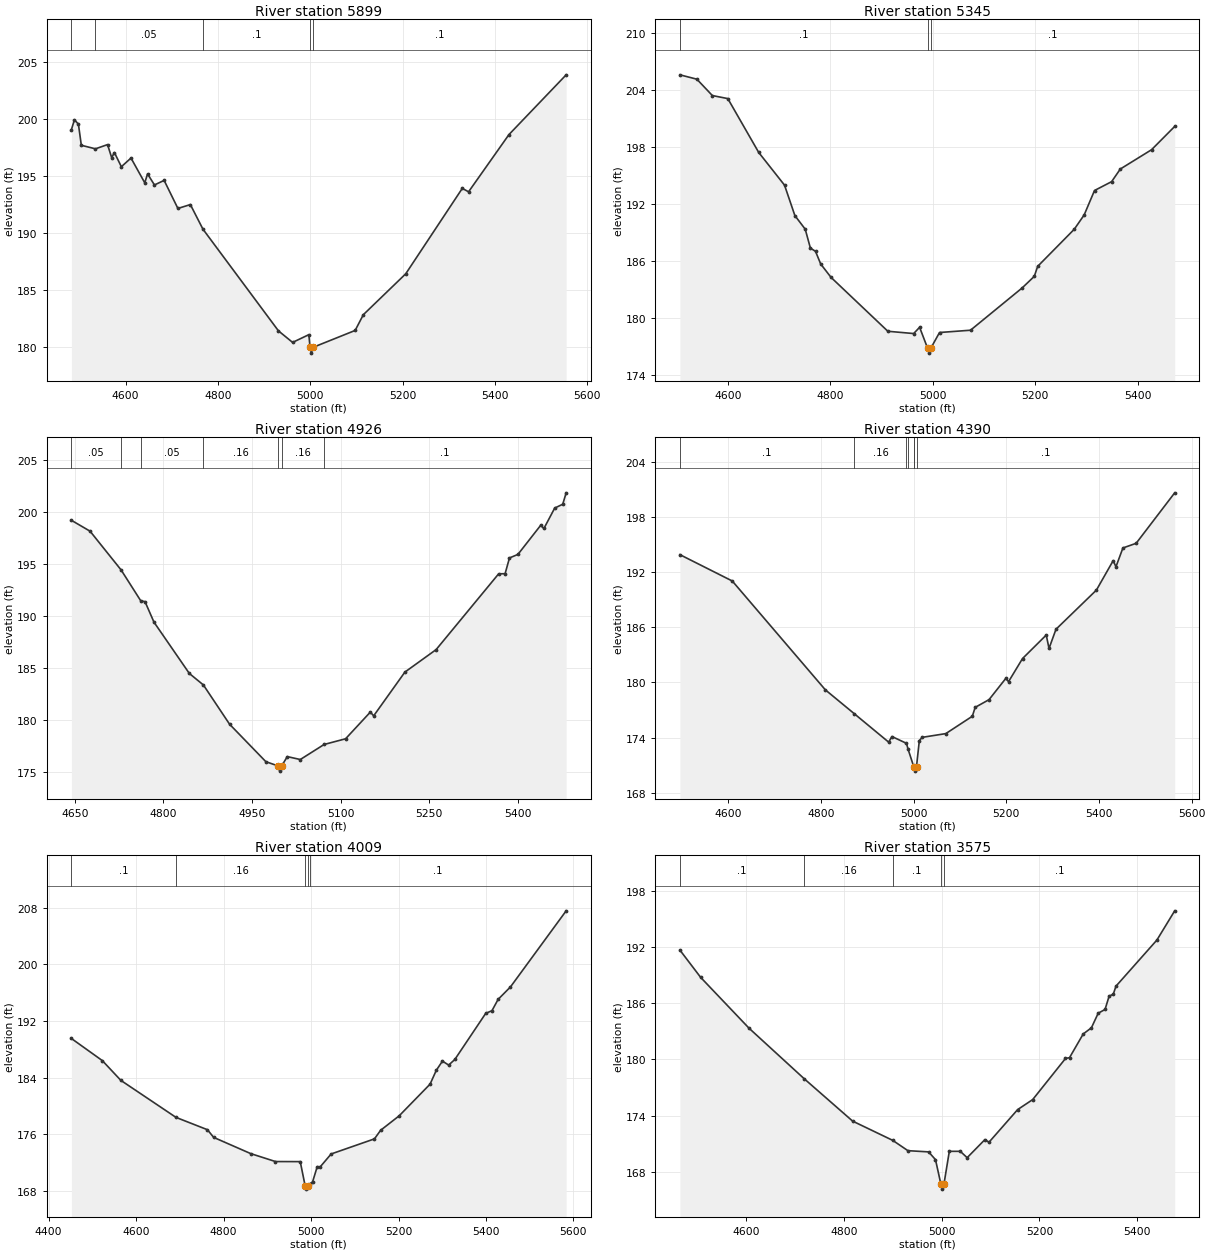
Type RM Length L Ch R = 1,5899,554,554,554
BEGIN DESCRIPTION:
Mapping XS e9e52e14
END DESCRIPTION:
XS GIS Cut Line= 4
      2276805.04     13239699.37      2276638.38     13239456.33
      2276068.93     13239338.27      2275874.49     13239359.11
#Sta/Elev= 30
  4482.5  199.07  4489.1  199.94  4497.7  199.55  4504.0  197.70  4534.6  197.39
  4560.8  197.76  4569.7  196.62  4575.7  197.06  4590.7  195.82  4611.6  196.58
  4641.4  194.41  4647.5  195.19  4662.4  194.22  4683.4  194.62  4713.2  192.16
  4740.2  192.50  4767.5  190.34  4931.1  181.42  4961.7  180.41  4996.9  181.09
  4999.5  179.97  5002.3  179.47  5005.5  179.97  5097.2  181.46  5114.9  182.84
  5206.8  186.43  5329.3  193.92  5342.9  193.62  5430.4  198.64  5554.3  203.88
#Mann=5,-1,0
  4482.5     0.1       0  4534.6    0.05       0  4767.5     0.1       0
  4999.5    0.07       0  5005.5     0.1       0
Bank Sta=4999.5,5005.5
Exp/Cntr=0.3,0.1

Type RM Length L Ch R = 1,5345,419,419,419
BEGIN DESCRIPTION:
UNT 033 IN RACR 11.0
END DESCRIPTION:
XS GIS Cut Line= 3
      2277110.63     13238970.22      2276930.05     13238949.39
      2276152.47     13238845.25
#Sta/Elev= 30
  4506.0  205.60  4539.1  205.14  4569.3  203.42  4599.5  203.10  4659.9  197.43
  4710.3  193.99  4730.5  190.79  4750.7  189.36  4760.8  187.37  4770.8  187.03
  4780.9  185.70  4801.1  184.29  4912.1  178.62  4962.5  178.38  4974.1  179.04
  4989.8  176.82  4992.6  176.32  4995.8  176.82  5013.0  178.49  5073.5  178.73
  5174.4  183.18  5198.1  184.40  5204.7  185.45  5276.1  189.35  5295.5  190.86
  5315.7  193.43  5349.1  194.36  5366.1  195.69  5427.1  197.72  5472.3  200.17
#Mann=3,-1,0
  4506.0     0.1       0  4989.8    0.07       0  4995.8     0.1       0
Bank Sta=4989.8,4995.8
Exp/Cntr=0.3,0.1

Type RM Length L Ch R = 1,4926,536,536,536
BEGIN DESCRIPTION:
UNT 033 IN RACR 10.0
END DESCRIPTION:
XS GIS Cut Line= 3
      2277068.97     13238699.41      2276923.10     13238602.16
      2276312.40     13238345.39
#Sta/Elev= 30
  4644.1  199.23  4675.7  198.18  4728.3  194.44  4761.5  191.47  4768.8  191.38
  4783.9  189.41  4843.8  184.46  4867.6  183.35  4912.0  179.56  4973.4  175.95
  4994.1  175.54  4996.9  175.04  5000.1  175.54  5009.7  176.44  5031.7  176.16
  5072.0  177.61  5108.4  178.16  5150.4  180.74  5155.9  180.37  5208.8  184.59
  5261.7  186.76  5367.6  194.07  5378.5  194.08  5385.9  195.60  5400.2  195.94
  5438.8  198.75  5444.2  198.44  5462.5  200.41  5476.1  200.78  5481.9  201.88
#Mann=7,-1,0
  4644.1    0.05       0  4728.3     0.1       0  4761.5    0.05       0
  4867.6    0.16       0  4994.1    0.07       0  5000.1    0.16       0
  5072.0     0.1       0
Bank Sta=4994.1,5000.1
Exp/Cntr=0.3,0.1

Type RM Length L Ch R = 1,4390,381,381,381
BEGIN DESCRIPTION:
UNT 033 IN RACR 9.0
END DESCRIPTION:
XS GIS Cut Line= 3
      2277277.28     13238366.07      2277131.43     13238178.55
      2276438.26     13237721.06
#Sta/Elev= 30
  4495.3  193.93  4608.3  191.06  4809.2  179.20  4872.1  176.58  4945.9  173.50
  4953.0  174.11  4984.3  173.37  4987.9  172.72  4999.9  170.85  5000.0  170.84
  5002.8  170.34  5006.0  170.84  5012.1  173.66  5018.1  174.02  5069.3  174.43
  5126.5  176.32  5132.7  177.29  5162.6  178.13  5198.7  180.44  5204.7  180.09
  5234.9  182.61  5286.1  185.17  5292.1  183.71  5307.1  185.80  5394.4  190.07
  5430.6  193.28  5436.6  192.61  5451.6  194.66  5480.2  195.17  5563.4  200.67
#Mann=7,-1,0
  4495.3     0.1       0  4872.1    0.16       0  4984.3     0.1       0
  4987.9    0.16       0  4999.9     0.1       0  5000.0    0.07       0
  5006.0     0.1       0
Bank Sta=5000,5006
Exp/Cntr=0.3,0.1

Type RM Length L Ch R = 1,4009,434,434,434
BEGIN DESCRIPTION:
UNT 033 IN RACR 8.0
END DESCRIPTION:
XS GIS Cut Line= 3
      2277487.72     13238096.85      2277087.72     13237696.85
      2276687.70     13237296.83
#Sta/Elev= 30
  4452.0  189.53  4522.7  186.41  4565.1  183.62  4691.2  178.40  4763.1  176.66
  4777.3  175.58  4862.1  173.29  4918.7  172.17  4975.3  172.16  4986.4  168.78
  4989.1  168.28  4992.4  168.78  4998.0  169.04  5003.5  169.30  5014.1  171.44
  5021.2  171.44  5046.0  173.24  5145.0  175.37  5159.1  176.58  5201.5  178.62
  5272.2  183.09  5286.4  185.04  5300.5  186.34  5314.7  185.78  5328.8  186.57
  5399.5  193.08  5413.7  193.45  5427.8  195.05  5456.1  196.81  5583.4  207.54
#Mann=5,-1,0
  4452.0     0.1       0  4691.2    0.16       0  4986.4    0.07       0
  4992.4    0.16       0  4998.0     0.1       0
Bank Sta=4986.4,4992.4
Exp/Cntr=0.3,0.1

Type RM Length L Ch R = 1,3575,443,443,443
BEGIN DESCRIPTION:
UNT 033 IN RACR 7.0
END DESCRIPTION:
XS GIS Cut Line= 3
      2277787.70     13237796.83      2277387.72     13237396.85
      2276987.69     13237196.84
#Sta/Elev= 30
  4463.9  191.68  4506.3  188.77  4605.3  183.34  4718.0  177.95  4817.4  173.41
  4899.6  171.35  4930.6  170.25  4973.0  170.12  4987.1  169.29  4998.3  166.64
  5001.0  166.14  5004.3  166.64  5015.4  170.18  5037.9  170.18  5051.9  169.50
  5088.2  171.43  5096.6  171.15  5155.3  174.64  5186.1  175.71  5253.2  180.10
  5261.5  180.19  5289.5  182.72  5306.3  183.38  5320.2  184.94  5334.2  185.34
  5342.6  186.77  5351.0  186.96  5356.6  187.83  5440.4  192.76  5476.8  195.88
#Mann=5,-1,0
  4463.9     0.1       0  4718.0    0.16       0  4899.6     0.1       0
  4998.3    0.07       0  5004.3     0.1       0
Bank Sta=4998.3,5004.3
Exp/Cntr=0.3,0.1

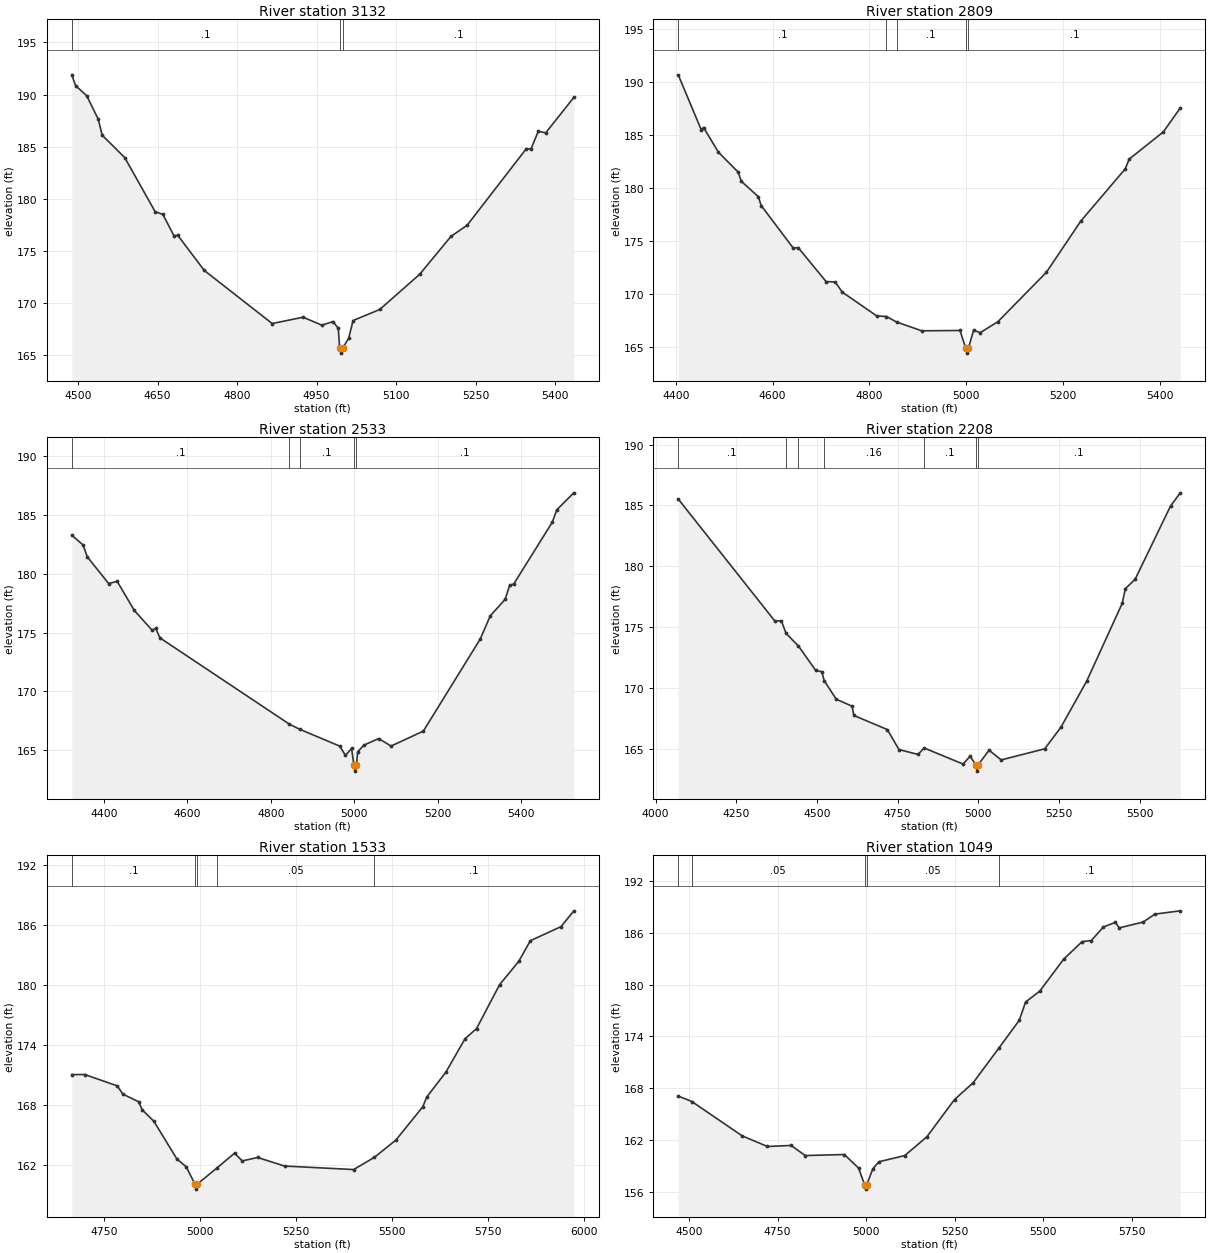
Type RM Length L Ch R = 1,3132,323,323,323
BEGIN DESCRIPTION:
UNT 033 IN RACR 6.0
END DESCRIPTION:
XS GIS Cut Line= 3
      2278037.76     13237346.88      2277637.72     13237046.85
      2277237.69     13236846.84
#Sta/Elev= 30
  4488.1  191.89  4495.4  190.85  4516.3  189.88  4538.1  187.63  4545.4  186.10
  4588.1  183.94  4645.4  178.75  4660.0  178.49  4680.9  176.44  4688.1  176.48
  4738.1  173.11  4866.3  168.01  4924.6  168.62  4960.0  167.85  4980.9  168.20
  4990.9  167.56  4993.5  165.67  4996.3  165.17  4999.5  165.67  5010.5  166.60
  5018.9  168.30  5069.2  169.36  5144.7  172.75  5203.4  176.37  5234.1  177.45
  5345.9  184.81  5354.3  184.74  5368.3  186.47  5382.3  186.32  5435.4  189.72
#Mann=3,-1,0
  4488.1     0.1       0  4993.5    0.07       0  4999.5     0.1       0
Bank Sta=4993.5,4999.5
Exp/Cntr=0.3,0.1

Type RM Length L Ch R = 1,2809,276,276,276
BEGIN DESCRIPTION:
UNT 033 IN RACR 5.0
END DESCRIPTION:
XS GIS Cut Line= 3
      2278124.14     13237257.57      2278050.30     13236959.84
      2277466.81     13236519.25
#Sta/Elev= 30
  4405.0  190.71  4452.3  185.54  4457.4  185.73  4488.2  183.39  4529.4  181.49
  4535.0  180.67  4570.6  179.19  4576.4  178.36  4642.7  174.34  4653.0  174.38
  4710.7  171.17  4729.4  171.14  4744.0  170.18  4815.2  167.93  4835.5  167.87
  4856.3  167.35  4908.4  166.52  4987.5  166.55  4999.0  164.91  5001.8  164.41
  5005.0  164.91  5015.7  166.58  5029.1  166.34  5065.8  167.38  5166.1  172.05
  5237.2  176.89  5329.0  181.82  5337.1  182.74  5407.9  185.32  5442.9  187.58
#Mann=5,-1,0
  4405.0     0.1       0  4835.5    0.16       0  4856.3     0.1       0
  4999.0    0.07       0  5005.0     0.1       0
Bank Sta=4999,5005
Exp/Cntr=0.3,0.1

Type RM Length L Ch R = 1,2533,325,325,325
BEGIN DESCRIPTION:
UNT 033 IN RACR 4.0
END DESCRIPTION:
XS GIS Cut Line= 4
      2278283.70     13237193.21      2278183.67     13236740.73
      2277757.36     13236435.87      2277547.81     13236383.49
#Sta/Elev= 30
  4322.7  183.29  4349.7  182.46  4359.9  181.45  4411.1  179.18  4431.6  179.36
  4472.6  176.89  4515.6  175.20  4523.8  175.38  4534.0  174.56  4844.5  167.22
  4868.9  166.79  4965.5  165.35  4978.6  164.56  4993.4  165.16  4999.0  163.73
  5001.7  163.23  5005.0  163.73  5008.1  164.88  5022.9  165.44  5058.5  166.00
  5088.0  165.36  5165.4  166.63  5301.8  174.46  5326.0  176.44  5361.4  177.83
  5372.4  179.04  5382.0  179.13  5474.8  184.41  5485.1  185.44  5526.2  186.89
#Mann=5,-1,0
  4322.7     0.1       0  4844.5    0.16       0  4868.9     0.1       0
  4999.0    0.07       0  5005.0     0.1       0
Bank Sta=4999,5005
Exp/Cntr=0.3,0.1

Type RM Length L Ch R = 1,2208,675,675,675
BEGIN DESCRIPTION:
UNT 033 IN RACR 3.0
END DESCRIPTION:
XS GIS Cut Line= 4
      2278647.48     13237119.97      2278439.15     13236510.61
      2278048.52     13236286.65      2277587.70     13236296.86
#Sta/Elev= 30
  4070.3  185.53  4369.5  175.52  4389.7  175.54  4404.2  174.51  4442.6  173.47
  4496.3  171.46  4515.0  171.36  4522.4  170.63  4559.7  169.10  4608.9  168.53
  4614.2  167.77  4718.0  166.61  4754.1  164.97  4813.1  164.57  4832.0  165.10
  4952.6  163.78  4974.2  164.42  4992.8  163.70  4995.6  163.20  4998.8  163.70
  5033.2  164.92  5070.6  164.12  5205.4  165.03  5255.4  166.79  5335.4  170.58
  5445.4  176.96  5455.4  178.18  5485.4  178.94  5595.5  184.97  5625.5  186.04
#Mann=7,-1,0
  4070.3     0.1       0  4404.2    0.16       0  4442.6     0.1       0
  4522.4    0.16       0  4832.0     0.1       0  4992.8    0.07       0
  4998.8     0.1       0
Bank Sta=4992.8,4998.8
Exp/Cntr=0.3,0.1

Type RM Length L Ch R = 1,1533,484,484,484
BEGIN DESCRIPTION:
UNT 033 IN RACR 2.0
END DESCRIPTION:
XS GIS Cut Line= 3
      2278692.23     13235950.29      2278577.62     13235833.07
      2277434.41     13235822.65
#Sta/Elev= 30
  4666.1  171.00  4699.9  171.01  4784.8  169.87  4799.0  169.05  4839.9  168.29
  4849.9  167.46  4879.9  166.33  4939.9  162.55  4964.0  161.78  4986.9  160.04
  4989.7  159.54  4992.9  160.04  5044.5  161.67  5090.0  163.14  5110.0  162.36
  5150.0  162.71  5220.0  161.85  5400.0  161.50  5454.0  162.72  5510.0  164.45
  5580.0  167.78  5590.0  168.74  5640.0  171.24  5690.0  174.59  5720.0  175.61
  5780.0  180.00  5830.0  182.34  5860.0  184.40  5940.0  185.81  5973.3  187.39
#Mann=5,-1,0
  4666.1     0.1       0  4986.9    0.07       0  4992.9     0.1       0
  5044.5    0.05       0  5454.0     0.1       0
Bank Sta=4986.9,4992.9
Exp/Cntr=0.3,0.1

Type RM Length L Ch R = 1,1049,723,723,723
BEGIN DESCRIPTION:
Mapping XS d8e407a3
END DESCRIPTION:
XS GIS Cut Line= 4
      2278694.75     13235619.06      2278519.28     13235343.32
      2277704.63     13235405.98      2277442.03     13235481.01
#Sta/Elev= 30
  4469.8  167.09  4508.2  166.46  4650.2  162.48  4721.5  161.25  4788.4  161.37
  4828.3  160.20  4938.6  160.32  4978.7  158.75  4995.8  156.81  4998.5  156.31
  5001.8  156.81  5018.9  158.66  5036.1  159.48  5109.1  160.20  5171.5  162.37
  5249.5  166.69  5301.9  168.62  5375.3  172.68  5432.3  175.87  5450.1  177.98
  5490.2  179.25  5557.6  182.95  5609.6  184.98  5635.8  185.11  5669.6  186.68
  5703.4  187.21  5714.5  186.58  5781.4  187.24  5815.2  188.17  5886.8  188.55
#Mann=5,-1,0
  4469.8     0.1       0  4508.2    0.05       0  4995.8    0.03       0
  5001.8    0.05       0  5375.3     0.1       0
Bank Sta=4995.8,5001.8
Exp/Cntr=0.3,0.1

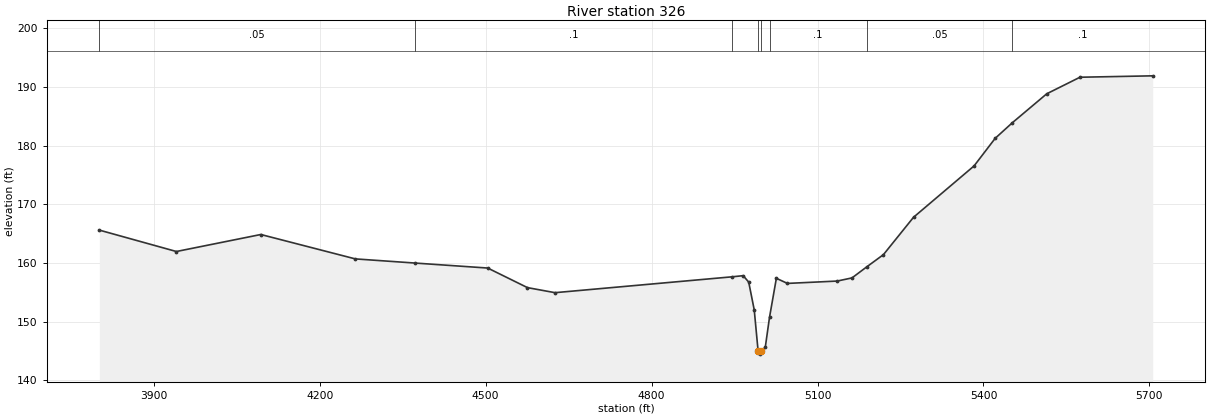
Type RM Length L Ch R = 1,326,0,0,0
BEGIN DESCRIPTION:
UNT 033 IN RACR 1.0
END DESCRIPTION:
XS GIS Cut Line= 4
      2278769.94     13235468.65      2278293.69     13234766.80
      2277792.36     13234766.80      2277529.19     13235255.55
#Sta/Elev= 30
  3801.5  165.59  3940.8  161.94  4093.5  164.84  4264.3  160.68  4372.4  159.97
  4503.7  159.12  4575.6  155.78  4625.4  154.92  4946.2  157.63  4965.6  157.82
  4975.6  156.72  4985.6  151.98  4992.6  144.94  4995.4  144.44  4998.6  144.94
  5005.6  145.64  5013.2  150.72  5025.6  157.37  5045.6  156.50  5135.6  156.90
  5162.4  157.44  5189.4  159.35  5219.2  161.41  5273.6  167.78  5383.1  176.54
  5421.2  181.24  5452.5  183.92  5514.5  188.84  5574.5  191.66  5706.1  191.90
#Mann=8,-1,0
  3801.5    0.05       0  4372.4     0.1       0  4946.2    0.12       0
  4992.6    0.07       0  4998.6    0.12       0  5013.2     0.1       0
  5189.4    0.05       0  5452.5     0.1       0
Bank Sta=4992.6,4998.6
Exp/Cntr=0.3,0.1

Chan Stop Cuts=-1