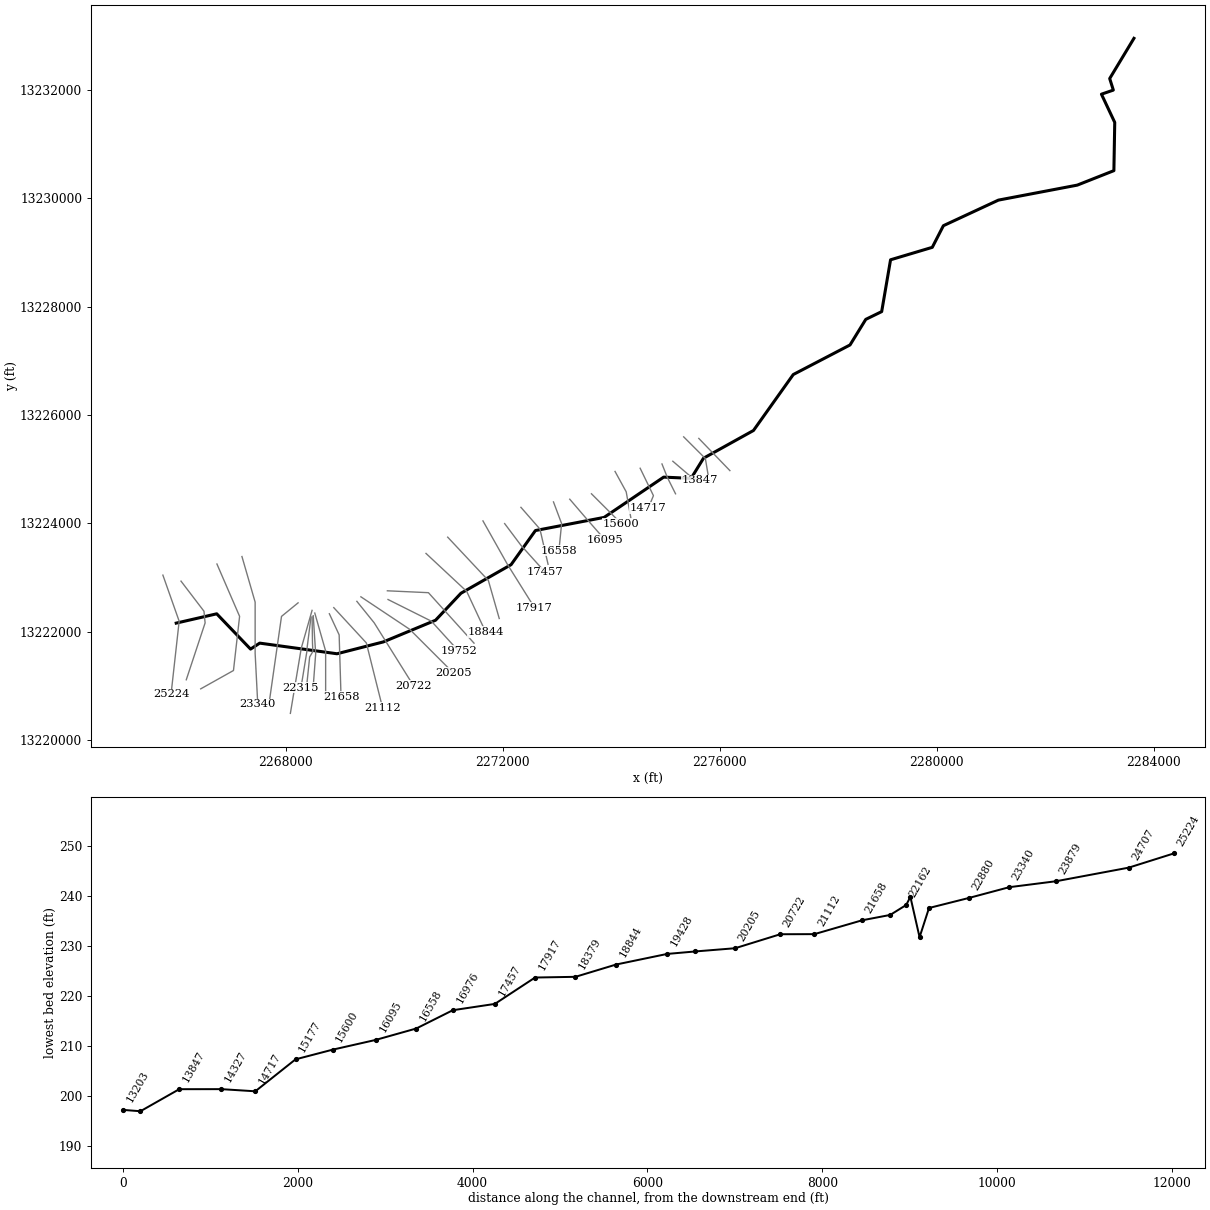
--- UNT 034 IN RACR.prj (project) ---

Proj Title=UNT 034 IN RACR Base Level Engineering
Current Plan=p01
Default Exp/Contr=0.3,0.1
English Units
Geom File=g01
Flow File=f01
Plan File=p01
BEGIN DESCRIPTION:
UNT 034 IN RACR
END DESCRIPTION:

--- UNT 034 IN RACR.p01 (plan) ---

Plan Title=Multiple Run
Short Identifier=Multiple
Geom File=g01
Flow File=f01
Subcritical Flow
K Sum by GR= 0
Std Step Tol= 0.01
Critical Tol= 0.01
Num of Std Step Trials= 20
Max Error Tol= 0.3
Flow Tol Ratio= 0.001
Split Flow NTrial= 30
Split Flow Tol= 0.02
Split Flow Ratio= 0.02
Log Output Level= 0
Friction Slope Method= 1
Unsteady Friction Slope Method= 2
Unsteady Bridges Friction Slope Method= 1
Parabolic Critical Depth
Global Vel Dist=  1 , 1 , 1
Global Log Level= 0
CheckData=True
Encroach Param= -1, 0, 0, 0
BEGIN DESCRIPTION:
Multiple Run
END DESCRIPTION:

--- UNT 034 IN RACR.f01 (steady flow) ---

Flow Title=Multiple
Number of Profiles=7
Profile Names=10-year,25-year,50-year,1pct_min,100-year,1pct_plu,500-year
River Rch & RM= UNT 034 IN RACR,Reach-1,25224
     134     175     207     181     245     331     345
River Rch & RM= UNT 034 IN RACR,Reach-1,23340
     264     359     436     390     527     712     780
River Rch & RM= UNT 034 IN RACR,Reach-1,17917
     358     497     612     553     748    1012    1135
River Rch & RM= UNT 034 IN RACR,Reach-1,13029
     463     652     810     739    1000    1352    1544
River Rch & RM= UNT 034 IN RACR,Reach-1,6332
     537     762     952     872    1180    1595    1840
Boundary for River Rch & Prof#=UNT 034 IN RACR,Reach-1,1
Up Type=0
Dn Type=3
Dn Slope=0.005
Boundary for River Rch & Prof#=UNT 034 IN RACR,Reach-1,2
Up Type=0
Dn Type=3
Dn Slope=0.005
Boundary for River Rch & Prof#=UNT 034 IN RACR,Reach-1,3
Up Type=0
Dn Type=3
Dn Slope=0.005
Boundary for River Rch & Prof#=UNT 034 IN RACR,Reach-1,4
Up Type=0
Dn Type=3
Dn Slope=0.005
Boundary for River Rch & Prof#=UNT 034 IN RACR,Reach-1,5
Up Type=0
Dn Type=3
Dn Slope=0.005
Boundary for River Rch & Prof#=UNT 034 IN RACR,Reach-1,6
Up Type=0
Dn Type=3
Dn Slope=0.005
Boundary for River Rch & Prof#=UNT 034 IN RACR,Reach-1,7
Up Type=0
Dn Type=3
Dn Slope=0.005

--- UNT 034 IN RACR.g01 (geometry) ---

Geom Title=Existing Conditions

River Reach=UNT 034 IN RACR,Reach-1
Reach XY= 30
      2265983.16     13222161.56      2266730.03     13222333.25
      2267353.53     13221682.35      2267522.55     13221792.49
      2268947.29     13221596.41      2269801.21     13221814.89
      2270763.98     13222214.81      2271231.84     13222712.18
      2272156.39     13223239.76      2272604.93     13223868.90
      2273870.64     13224111.12      2274968.93     13224854.18
      2275474.65     13224831.30      2275702.82     13225202.48
      2276624.13     13225714.10      2277357.83     13226746.26
      2278403.89     13227291.56      2278694.35     13227763.66
      2278987.72     13227906.86      2279151.23     13228862.45
      2279920.36     13229092.17      2280125.14     13229491.28
      2281139.29     13229963.07      2282592.51     13230239.44
      2283268.06     13230506.62      2283283.78     13231396.29
      2283038.51     13231916.74      2283257.79     13231992.04
      2283190.83     13232205.38      2283637.72     13232946.85

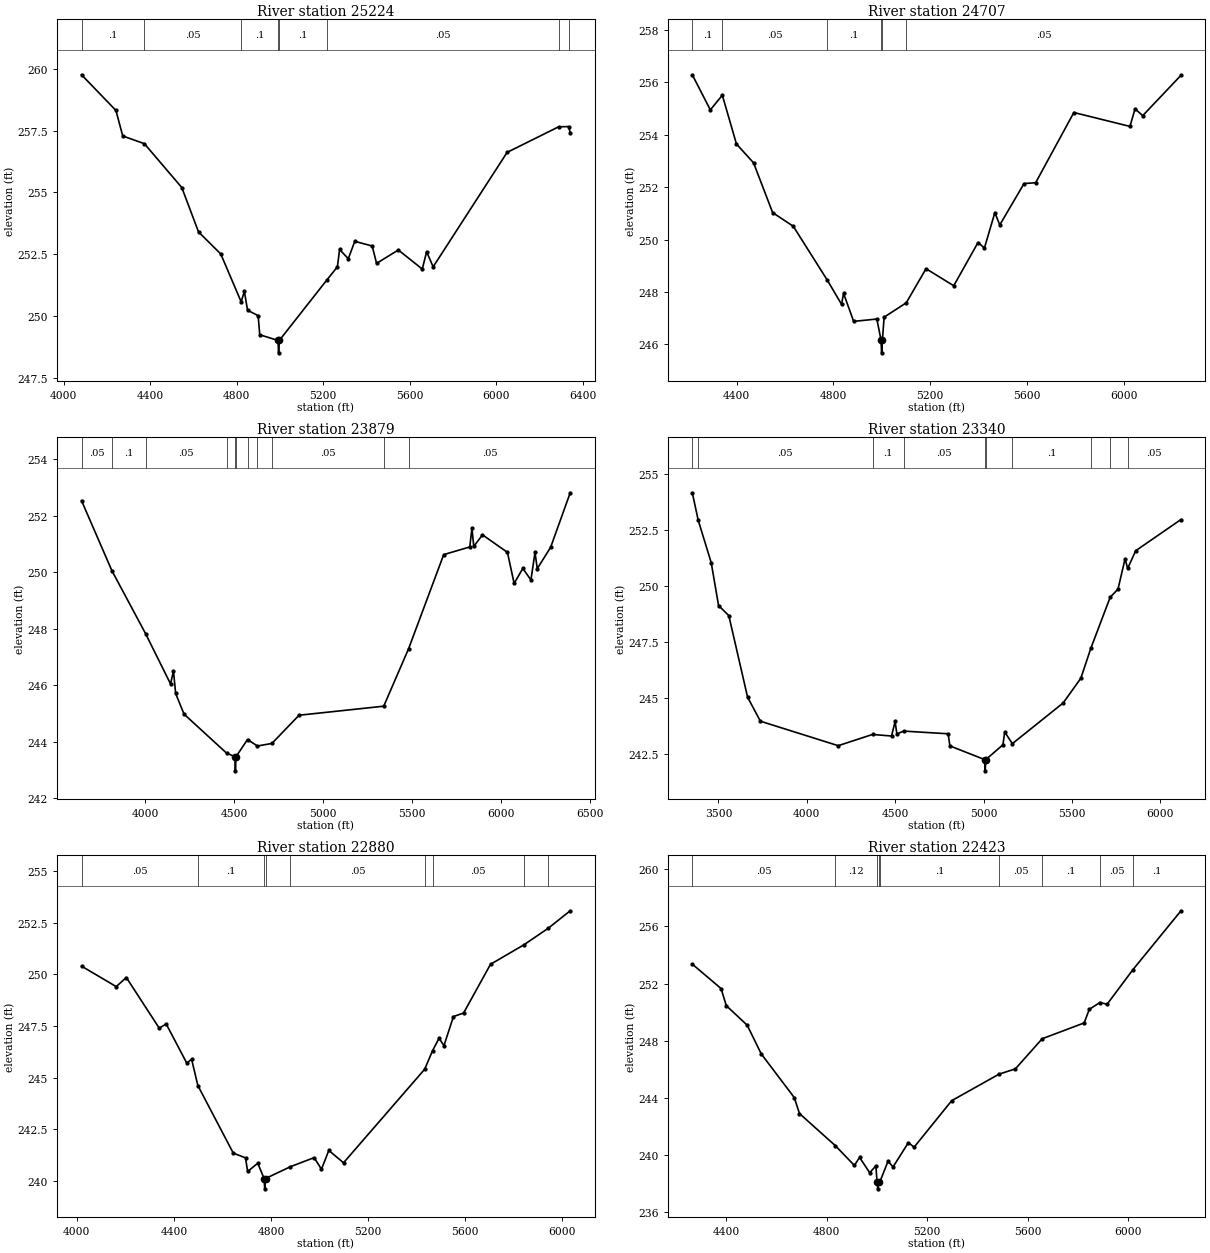
Type RM Length L Ch R = 1,25224,517,517,517
BEGIN DESCRIPTION:
UNT 034 IN RACR 54.0
END DESCRIPTION:
XS GIS Cut Line= 3
      2265737.70     13223046.90      2266037.72     13222196.85
      2265887.73     13220846.90
#Sta/Elev= 30
  4082.7  259.75  4241.8  258.31  4273.2  257.28  4373.2  256.97  4546.3  255.20
  4623.6  253.41  4726.5  252.52  4820.7  250.59  4835.7  251.01  4850.3  250.25
  4899.3  250.03  4906.8  249.26  4991.2  249.03  4993.9  248.53  4997.2  249.03
  5217.1  251.47  5265.9  252.00  5275.9  252.70  5316.2  252.33  5346.3  253.03
  5426.8  252.84  5447.0  252.14  5547.6  252.68  5658.3  251.91  5678.4  252.61
  5708.6  252.00  6050.7  256.62  6288.8  257.65  6335.2  257.66  6342.4  257.41
#Mann=8,-1,0
  4082.7     0.1       0  4373.2    0.05       0  4820.7     0.1       0
  4991.2    0.07       0  4997.2     0.1       0  5217.1    0.05       0
  6288.8     0.1       0  6335.2    0.05       0
Bank Sta=4991.2,4997.2
Exp/Cntr=0.3,0.1

Type RM Length L Ch R = 1,24707,828,828,828
BEGIN DESCRIPTION:
UNT 034 IN RACR 53.0
END DESCRIPTION:
XS GIS Cut Line= 4
      2266071.55     13222936.07      2266495.14     13222380.54
      2266515.97     13222165.27      2266168.74     13221116.64
#Sta/Elev= 30
  4217.2  256.29  4291.7  254.95  4341.3  255.51  4399.6  253.65  4470.3  252.93
  4549.2  251.03  4634.5  250.51  4774.6  248.46  4834.0  247.53  4842.3  247.95
  4883.9  246.88  4979.8  246.97  4996.9  246.18  4999.6  245.68  5002.9  246.18
  5009.9  247.04  5101.4  247.59  5183.1  248.89  5297.6  248.24  5398.0  249.89
  5424.4  249.68  5467.5  251.03  5487.8  250.56  5588.2  252.14  5636.0  252.17
  5794.0  254.85  6025.8  254.32  6046.9  254.99  6078.5  254.73  6236.7  256.27
#Mann=6,-1,0
  4217.2     0.1       0  4341.3    0.05       0  4774.6     0.1       0
  4996.9    0.07       0  5002.9     0.1       0  5101.4    0.05       0
Bank Sta=4996.9,5002.9
Exp/Cntr=0.3,0.1

Type RM Length L Ch R = 1,23879,539,539,539
BEGIN DESCRIPTION:
UNT 034 IN RACR 52.0
END DESCRIPTION:
XS GIS Cut Line= 4
      2266734.01     13223251.54      2267151.64     13222286.49
      2267038.77     13221287.57      2266434.93     13220948.97
#Sta/Elev= 30
  3641.7  252.54  3812.5  250.06  4002.0  247.83  4142.3  246.05  4158.9  246.50
  4171.2  245.71  4218.2  244.98  4457.3  243.60  4504.6  243.47  4507.3  242.97
  4510.6  243.47  4575.5  244.08  4631.1  243.85  4712.6  243.94  4865.3  244.94
  5341.7  245.26  5481.9  247.30  5679.1  250.63  5825.8  250.90  5837.9  251.56
  5848.2  250.92  5897.3  251.33  6037.6  250.71  6075.3  249.61  6124.4  250.14
  6169.8  249.73  6192.7  250.71  6205.4  250.13  6280.7  250.89  6390.8  252.82
#Mann=11,-1,0
  3641.7    0.05       0  3812.5     0.1       0  4002.0    0.05       0
  4457.3    0.12       0  4504.6    0.03       0  4510.6    0.12       0
  4575.5    0.05       0  4631.1     0.1       0  4712.6    0.05       0
  5341.7     0.1       0  5481.9    0.05       0
Bank Sta=4504.6,4510.6
Exp/Cntr=0.3,0.1

Type RM Length L Ch R = 1,23340,460,460,460
BEGIN DESCRIPTION:
Mapping XS 9d8eff5b
END DESCRIPTION:
XS GIS Cut Line= 4
      2267195.08     13223389.55      2267438.15     13222549.23
      2267438.15     13221604.79      2267486.73     13220661.05
#Sta/Elev= 30
  3352.5  254.15  3385.8  252.93  3459.4  251.04  3501.0  249.13  3559.1  248.68
  3665.1  245.05  3737.6  243.98  4177.7  242.89  4371.9  243.39  4479.6  243.32
  4499.6  243.97  4509.6  243.41  4547.7  243.54  4799.6  243.42  4809.6  242.88
  5006.6  242.27  5009.4  241.77  5012.6  242.27  5109.6  242.93  5119.6  243.50
  5162.8  242.98  5450.0  244.79  5550.1  245.89  5606.5  247.22  5716.3  249.50
  5760.4  249.86  5800.5  251.21  5815.1  250.78  5860.6  251.57  6116.7  252.96
#Mann=10,-1,0
  3352.5     0.1       0  3385.8    0.05       0  4371.9     0.1       0
  4547.7    0.05       0  5006.6    0.03       0  5012.6    0.05       0
  5162.8     0.1       0  5606.5    0.05       0  5716.3     0.1       0
  5815.1    0.05       0
Bank Sta=5006.6,5012.6
Exp/Cntr=0.3,0.1

Type RM Length L Ch R = 1,22880,457,457,457
BEGIN DESCRIPTION:
UNT 034 IN RACR 51.0
END DESCRIPTION:
XS GIS Cut Line= 3
      2268229.84     13222535.36      2267924.26     13222285.34
      2267695.15     13220681.55
#Sta/Elev= 30
  4019.3  250.40  4162.3  249.41  4204.0  249.85  4339.6  247.40  4368.4  247.60
  4453.0  245.71  4473.2  245.89  4498.9  244.62  4644.9  241.35  4695.4  241.12
  4704.2  240.46  4746.0  240.86  4771.9  240.12  4774.6  239.62  4777.9  240.12
  4880.3  240.69  4978.3  241.13  5008.6  240.57  5038.9  241.48  5099.5  240.88
  5434.1  245.41  5466.7  246.31  5493.5  246.91  5513.7  246.55  5552.7  247.96
  5594.5  248.13  5705.6  250.49  5842.9  251.43  5943.1  252.23  6034.2  253.08
#Mann=9,-1,0
  4019.3    0.05       0  4498.9     0.1       0  4771.9    0.03       0
  4777.9     0.1       0  4880.3    0.05       0  5434.1     0.1       0
  5466.7    0.05       0  5842.9     0.1       0  5943.1    0.05       0
Bank Sta=4771.9,4777.9
Exp/Cntr=0.3,0.1

Type RM Length L Ch R = 1,22423,108,108,108
BEGIN DESCRIPTION:
UNT 034 IN RACR 50.0
END DESCRIPTION:
XS GIS Cut Line= 3
      2268487.71     13222396.82      2268287.72     13221696.85
      2268087.72     13220496.88
#Sta/Elev= 30
  4265.7  253.36  4380.1  251.65  4400.9  250.45  4484.1  249.08  4540.0  247.07
  4671.3  244.01  4692.1  242.89  4835.2  240.63  4910.5  239.25  4931.3  239.81
  4971.6  238.74  4996.2  239.22  5000.8  238.11  5003.6  237.61  5006.8  238.11
  5012.6  238.13  5044.4  239.54  5064.6  239.15  5125.5  240.85  5148.3  240.53
  5297.8  243.79  5486.4  245.65  5551.3  246.02  5657.9  248.13  5825.0  249.24
  5845.3  250.19  5887.6  250.67  5916.2  250.55  6019.3  252.98  6210.2  257.10
#Mann=9,-1,0
  4265.7    0.05       0  4835.2    0.12       0  5000.8    0.07       0
  5006.8    0.12       0  5012.6     0.1       0  5486.4    0.05       0
  5657.9     0.1       0  5887.6    0.05       0  6019.3     0.1       0
Bank Sta=5000.8,5006.8
Exp/Cntr=0.3,0.1

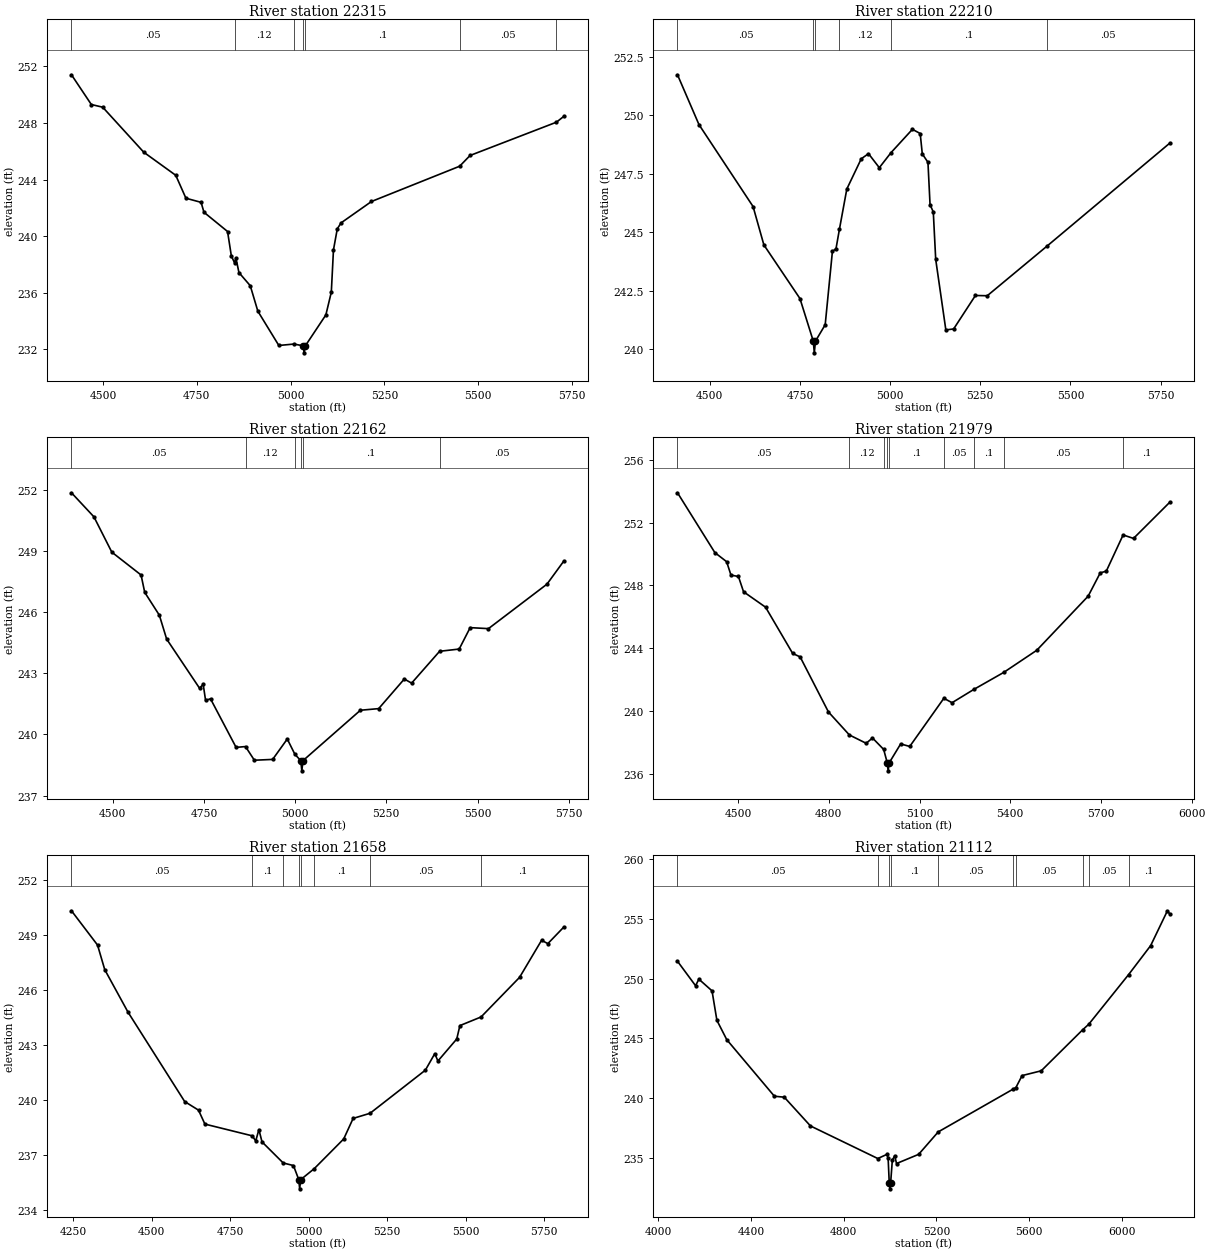
Type RM Length L Ch R = 1,22315,105,105,105
BEGIN DESCRIPTION:
Mapping XS f6afd694
END DESCRIPTION:
XS GIS Cut Line= 4
      2268467.35     13222269.39      2268397.91     13221720.82
      2268390.97     13221634.02      2268283.41     13220971.31
#Sta/Elev= 30
  4416.3  251.40  4469.2  249.30  4499.5  249.11  4608.9  245.93  4694.1  244.30
  4721.2  242.68  4761.6  242.39  4769.2  241.69  4832.1  240.33  4842.2  238.60
  4850.9  238.11  4854.3  238.47  4862.4  237.43  4892.6  236.50  4912.8  234.70
  4968.7  232.28  5008.7  232.38  5033.4  232.26  5036.1  231.76  5039.4  232.26
  5094.0  234.44  5108.5  236.05  5114.2  239.03  5124.4  240.52  5134.5  240.94
  5215.5  242.45  5450.3  244.94  5478.1  245.70  5708.1  248.05  5727.7  248.46
#Mann=7,-1,0
  4416.3    0.05       0  4850.9    0.12       0  5008.7     0.1       0
  5033.4    0.07       0  5039.4     0.1       0  5450.3    0.05       0
  5708.1     0.1       0
Bank Sta=5033.4,5039.4
Exp/Cntr=0.3,0.1

Type RM Length L Ch R = 1,22210,48,48,48
BEGIN DESCRIPTION:
Mapping XS c0d344ba
END DESCRIPTION:
XS GIS Cut Line= 5
      2268488.19     13222276.41      2268495.14     13221797.21
      2268502.08     13221637.49      2268443.05     13221536.79
      2268380.70     13220930.54
#Sta/Elev= 30
  4410.4  251.72  4470.0  249.59  4620.0  246.09  4650.0  244.45  4750.0  242.16
  4787.0  240.34  4789.8  239.84  4793.0  240.34  4820.0  241.04  4840.0  244.17
  4850.0  244.29  4859.6  245.13  4880.0  246.84  4920.0  248.13  4940.1  248.35
  4970.1  247.75  5002.4  248.39  5061.9  249.39  5083.5  249.21  5089.3  248.34
  5105.0  247.98  5110.8  246.17  5119.8  245.86  5126.5  243.83  5154.6  240.82
  5176.2  240.86  5236.6  242.29  5269.5  242.28  5434.4  244.39  5775.7  248.80
#Mann=6,-1,0
  4410.4    0.05       0  4787.0    0.07       0  4793.0    0.05       0
  4859.6    0.12       0  5002.4     0.1       0  5434.4    0.05       0
Bank Sta=4787,4793
Exp/Cntr=0.3,0.1

Type RM Length L Ch R = 1,22162,183,183,183
BEGIN DESCRIPTION:
Mapping XS f110acfe
END DESCRIPTION:
XS GIS Cut Line= 3
      2268509.02     13222297.25      2268554.16     13221595.82
      2268505.62     13220950.93
#Sta/Elev= 30
  4386.9  251.84  4448.5  250.66  4497.5  248.93  4577.7  247.81  4587.7  246.96
  4627.8  245.84  4647.8  244.67  4738.0  242.26  4748.0  242.45  4754.5  241.67
  4768.1  241.74  4838.2  239.36  4864.0  239.40  4888.3  238.73  4938.4  238.77
  4978.5  239.77  4999.4  239.02  5015.6  238.71  5018.4  238.21  5021.6  238.71
  5179.0  241.18  5229.1  241.26  5299.3  242.71  5319.4  242.51  5396.1  244.07
  5449.8  244.18  5479.9  245.23  5530.0  245.18  5690.4  247.36  5736.5  248.49
#Mann=6,-1,0
  4386.9    0.05       0  4864.0    0.12       0  4999.4     0.1       0
  5015.6    0.07       0  5021.6     0.1       0  5396.1    0.05       0
Bank Sta=5015.6,5021.6
Exp/Cntr=0.3,0.1

Type RM Length L Ch R = 1,21979,321,321,321
BEGIN DESCRIPTION:
UNT 034 IN RACR 49.0
END DESCRIPTION:
XS GIS Cut Line= 3
      2268537.72     13222346.86      2268737.72     13221646.85
      2268737.72     13220746.87
#Sta/Elev= 30
  4299.7  253.89  4423.2  250.09  4462.2  249.51  4476.5  248.66  4501.2  248.57
  4518.1  247.60  4590.9  246.62  4680.6  243.68  4705.3  243.46  4798.9  239.96
  4868.1  238.50  4923.7  237.97  4944.5  238.31  4981.5  237.58  4993.5  236.72
  4996.3  236.22  4999.5  236.72  5037.7  237.93  5067.7  237.77  5180.5  240.83
  5207.7  240.55  5279.3  241.39  5378.1  242.47  5487.7  243.88  5657.7  247.32
  5697.7  248.80  5717.7  248.91  5773.3  251.21  5807.7  250.99  5927.7  253.29
#Mann=9,-1,0
  4299.7    0.05       0  4868.1    0.12       0  4981.5     0.1       0
  4993.5    0.07       0  4999.5     0.1       0  5180.5    0.05       0
  5279.3     0.1       0  5378.1    0.05       0  5773.3     0.1       0
Bank Sta=4993.5,4999.5
Exp/Cntr=0.3,0.1

Type RM Length L Ch R = 1,21658,546,546,546
BEGIN DESCRIPTION:
UNT 034 IN RACR 48.0
END DESCRIPTION:
XS GIS Cut Line= 3
      2268806.21     13222333.95      2268986.76     13221945.06
      2269021.49     13220806.15
#Sta/Elev= 30
  4244.1  250.31  4327.2  248.44  4350.1  247.10  4424.3  244.78  4604.7  239.91
  4648.8  239.44  4669.1  238.68  4819.9  238.04  4831.1  237.76  4841.1  238.38
  4851.1  237.71  4918.6  236.56  4951.2  236.42  4968.2  235.65  4971.0  235.15
  4974.2  235.65  5017.4  236.25  5111.3  237.87  5141.3  238.99  5195.3  239.27
  5371.4  241.62  5401.4  242.52  5411.4  242.12  5471.4  243.32  5481.4  244.05
  5548.8  244.52  5671.5  246.68  5741.6  248.70  5761.6  248.52  5812.3  249.42
#Mann=8,-1,0
  4244.1    0.05       0  4819.9     0.1       0  4918.6    0.05       0
  4968.2    0.03       0  4974.2    0.05       0  5017.4     0.1       0
  5195.3    0.05       0  5548.8     0.1       0
Bank Sta=4968.2,4974.2
Exp/Cntr=0.3,0.1

Type RM Length L Ch R = 1,21112,390,390,390
BEGIN DESCRIPTION:
UNT 034 IN RACR 47.0
END DESCRIPTION:
XS GIS Cut Line= 3
      2268887.75     13222446.83      2269487.72     13221796.85
      2269787.72     13220596.84
#Sta/Elev= 30
  4084.0  251.45  4161.9  249.40  4176.1  249.95  4232.8  248.97  4253.8  246.50
  4296.3  244.88  4501.6  240.14  4544.1  240.06  4657.0  237.65  4947.2  234.92
  4986.6  235.27  4991.7  234.94  4996.5  232.88  4999.2  232.38  5002.5  232.88
  5009.8  234.78  5020.1  235.16  5027.8  234.50  5123.2  235.27  5207.5  237.15
  5529.9  240.73  5542.1  240.86  5569.0  241.87  5651.4  242.27  5829.6  245.70
  5856.2  246.17  6028.3  250.34  6123.0  252.76  6195.2  255.68  6205.5  255.40
#Mann=10,-1,0
  4084.0    0.05       0  4947.2     0.1       0  4996.5    0.07       0
  5002.5     0.1       0  5207.5    0.05       0  5529.9     0.1       0
  5542.1    0.05       0  5829.6     0.1       0  5856.2    0.05       0
  6028.3     0.1       0
Bank Sta=4996.5,5002.5
Exp/Cntr=0.3,0.1

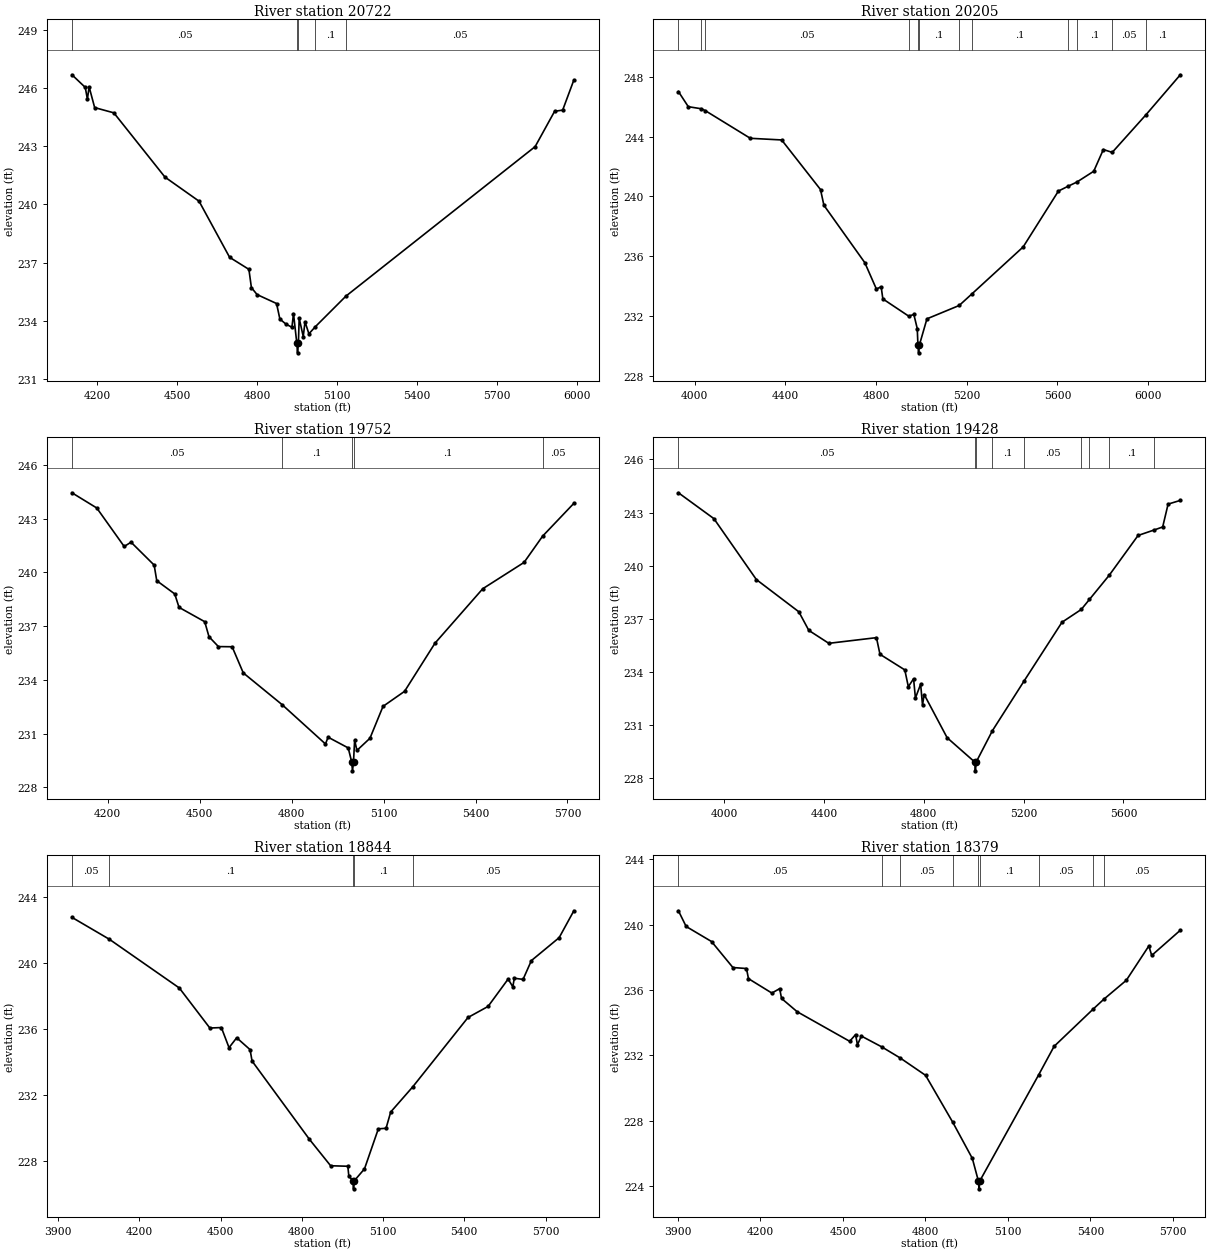
Type RM Length L Ch R = 1,20722,517,517,517
BEGIN DESCRIPTION:
UNT 034 IN RACR 46.0
END DESCRIPTION:
XS GIS Cut Line= 3
      2269313.15     13222563.11      2269632.60     13222167.29
      2270361.37     13221001.24
#Sta/Elev= 30
  4104.8  246.68  4154.8  246.03  4162.8  245.42  4169.2  246.06  4190.0  244.99
  4262.0  244.72  4453.9  241.41  4581.8  240.17  4696.5  237.28  4768.9  236.66
  4778.3  235.72  4799.6  235.36  4872.7  234.90  4885.2  234.10  4908.8  233.83
  4930.4  233.68  4936.3  234.38  4948.7  232.86  4951.4  232.36  4954.7  232.86
  4957.6  234.14  4972.9  233.20  4979.5  233.96  4994.1  233.34  5018.6  233.71
  5133.0  235.28  5843.2  242.98  5916.3  244.80  5946.5  244.86  5988.5  246.41
#Mann=5,-1,0
  4104.8    0.05       0  4948.7    0.03       0  4954.7    0.05       0
  5018.6     0.1       0  5133.0    0.05       0
Bank Sta=4948.7,4954.7
Exp/Cntr=0.3,0.1

Type RM Length L Ch R = 1,20205,453,453,453
BEGIN DESCRIPTION:
UNT 034 IN RACR 45.0
END DESCRIPTION:
XS GIS Cut Line= 3
      2269387.71     13222646.86      2270287.72     13222046.85
      2271087.69     13221246.89
#Sta/Elev= 30
  3928.9  247.00  3972.5  245.99  4030.5  245.85  4048.0  245.72  4245.9  243.88
  4384.1  243.77  4555.4  240.46  4570.4  239.41  4750.7  235.58  4801.8  233.82
  4822.8  233.97  4830.3  233.16  4944.2  232.01  4967.0  232.12  4982.0  231.18
  4985.0  230.06  4987.8  229.56  4991.0  230.06  5024.7  231.83  5166.8  232.72
  5223.4  233.50  5449.0  236.63  5604.5  240.36  5647.2  240.68  5685.9  240.96
  5760.1  241.68  5802.5  243.13  5841.7  242.94  5990.4  245.45  6141.9  248.12
#Mann=12,-1,0
  3928.9    0.05       0  4030.5     0.1       0  4048.0    0.05       0
  4944.2     0.1       0  4985.0    0.07       0  4991.0     0.1       0
  5166.8    0.05       0  5223.4     0.1       0  5647.2    0.05       0
  5685.9     0.1       0  5841.7    0.05       0  5990.4     0.1       0
Bank Sta=4985,4991
Exp/Cntr=0.3,0.1

Type RM Length L Ch R = 1,19752,324,324,324
BEGIN DESCRIPTION:
UNT 034 IN RACR 44.0
END DESCRIPTION:
XS GIS Cut Line= 3
      2269887.75     13222596.84      2270687.72     13222196.85
      2271187.72     13221646.86
#Sta/Elev= 30
  4083.2  244.45  4164.2  243.60  4253.7  241.45  4276.0  241.69  4351.5  240.41
  4359.9  239.54  4418.6  238.80  4432.6  238.05  4516.4  237.25  4530.4  236.41
  4561.1  235.86  4605.9  235.85  4642.2  234.39  4768.7  232.62  4910.5  230.42
  4918.9  230.80  4984.7  230.20  4995.9  229.42  4998.6  228.92  5001.9  229.42
  5005.6  230.63  5013.1  230.06  5055.6  230.74  5098.2  232.52  5168.5  233.36
  5267.8  236.05  5423.6  239.09  5558.4  240.56  5619.1  242.03  5720.9  243.86
#Mann=5,-1,0
  4083.2    0.05       0  4768.7     0.1       0  4995.9    0.07       0
  5001.9     0.1       0  5619.1    0.05       0
Bank Sta=4995.9,5001.9
Exp/Cntr=0.3,0.1

Type RM Length L Ch R = 1,19428,584,584,584
BEGIN DESCRIPTION:
UNT 034 IN RACR 43.0
END DESCRIPTION:
XS GIS Cut Line= 3
      2269875.64     13222757.56      2270632.60     13222722.84
      2271472.78     13221792.39
#Sta/Elev= 30
  3816.8  244.12  3959.0  242.66  4129.2  239.22  4299.4  237.40  4339.4  236.35
  4419.5  235.62  4610.4  235.94  4624.6  235.00  4724.0  234.12  4738.2  233.17
  4759.2  233.62  4766.6  232.53  4787.5  233.31  4795.0  232.14  4801.7  232.73
  4893.7  230.29  5004.2  228.92  5007.0  228.42  5010.2  228.92  5075.3  230.69
  5201.5  233.48  5354.0  236.81  5431.1  237.53  5464.2  238.10  5543.1  239.46
  5658.9  241.71  5723.4  242.02  5757.5  242.19  5779.2  243.48  5828.2  243.69
#Mann=9,-1,0
  3816.8    0.05       0  5004.2   0.035       0  5010.2    0.05       0
  5075.3     0.1       0  5201.5    0.05       0  5431.1     0.1       0
  5464.2    0.05       0  5543.1     0.1       0  5723.4    0.05       0
Bank Sta=5004.2,5010.2
Exp/Cntr=0.3,0.1

Type RM Length L Ch R = 1,18844,465,465,465
BEGIN DESCRIPTION:
UNT 034 IN RACR 42.0
END DESCRIPTION:
XS GIS Cut Line= 3
      2270587.74     13223446.84      2271337.72     13222746.85
      2271687.70     13221996.89
#Sta/Elev= 30
  3951.2  242.76  4089.6  241.43  4347.6  238.48  4460.5  236.05  4503.0  236.08
  4531.3  234.86  4559.6  235.46  4609.0  234.74  4616.3  234.05  4828.3  229.30
  4906.5  227.70  4970.0  227.67  4973.7  227.07  4988.3  226.80  4991.0  226.30
  4994.3  226.80  5031.5  227.51  5082.7  229.94  5111.1  229.97  5128.4  230.96
  5209.5  232.48  5413.8  236.69  5487.9  237.36  5562.0  239.02  5579.3  238.55
  5584.8  239.07  5617.1  239.00  5647.9  240.14  5750.4  241.53  5804.7  243.16
#Mann=5,-1,0
  3951.2    0.05       0  4089.6     0.1       0  4988.3    0.07       0
  4994.3     0.1       0  5209.5    0.05       0
Bank Sta=4988.3,4994.3
Exp/Cntr=0.3,0.1

Type RM Length L Ch R = 1,18379,462,462,462
BEGIN DESCRIPTION:
UNT 034 IN RACR 41.0
END DESCRIPTION:
XS GIS Cut Line= 3
      2270987.71     13223746.87      2271737.72     13222946.85
      2271937.72     13222246.87
#Sta/Elev= 30
  3902.0  240.84  3930.1  239.88  4022.4  238.96  4100.1  237.37  4149.4  237.31
  4156.7  236.69  4241.7  235.81  4270.1  236.08  4276.9  235.48  4333.6  234.67
  4524.6  232.86  4546.0  233.27  4552.9  232.65  4567.1  233.18  4641.1  232.52
  4708.3  231.84  4800.5  230.78  4899.3  227.91  4970.5  225.70  4992.2  224.34
  4994.9  223.84  4998.2  224.34  5212.3  230.83  5267.7  232.55  5409.8  234.83
  5448.4  235.43  5530.3  236.59  5612.2  238.69  5622.6  238.11  5726.6  239.65
#Mann=9,-1,0
  3902.0    0.05       0  4641.1     0.1       0  4708.3    0.05       0
  4899.3     0.1       0  4992.2    0.07       0  4998.2     0.1       0
  5212.3    0.05       0  5409.8     0.1       0  5448.4    0.05       0
Bank Sta=4992.2,4998.2
Exp/Cntr=0.3,0.1

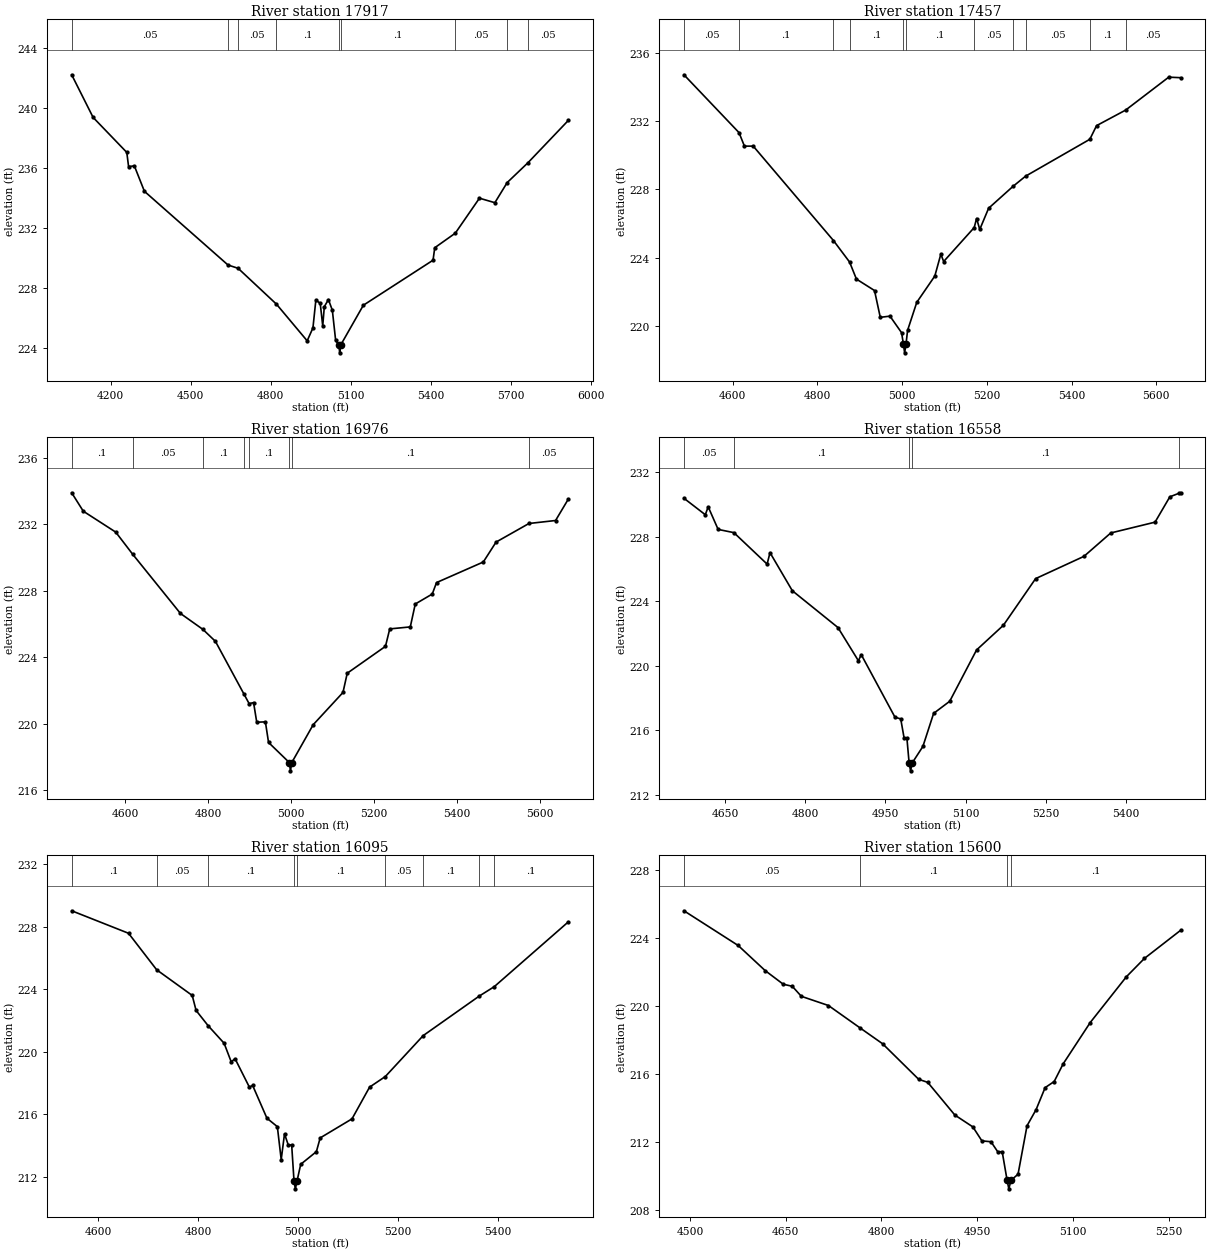
Type RM Length L Ch R = 1,17917,460,460,460
BEGIN DESCRIPTION:
UNT 034 IN RACR 40.0
END DESCRIPTION:
XS GIS Cut Line= 3
      2271637.74     13224046.82      2272087.72     13223246.85
      2272587.70     13222446.89
#Sta/Elev= 30
  4053.9  242.22  4134.2  239.38  4260.4  237.05  4267.1  236.11  4288.8  236.15
  4326.4  234.46  4639.7  229.55  4677.6  229.33  4821.4  226.94  4936.4  224.50
  4958.0  225.36  4968.9  227.21  4985.3  227.00  4994.7  225.49  5000.6  226.77
  5016.0  227.25  5030.7  226.54  5043.1  224.53  5055.4  224.20  5058.2  223.70
  5061.4  224.20  5146.9  226.87  5408.1  229.87  5414.5  230.70  5491.5  231.67
  5582.0  234.00  5639.8  233.70  5685.9  235.04  5764.3  236.37  5915.1  239.18
#Mann=9,-1,0
  4053.9    0.05       0  4639.7     0.1       0  4677.6    0.05       0
  4821.4     0.1       0  5055.4    0.07       0  5061.4     0.1       0
  5491.5    0.05       0  5685.9     0.1       0  5764.3    0.05       0
Bank Sta=5055.4,5061.4
Exp/Cntr=0.3,0.1

Type RM Length L Ch R = 1,17457,481,481,481
BEGIN DESCRIPTION:
UNT 034 IN RACR 39.0
END DESCRIPTION:
XS GIS Cut Line= 3
      2272037.69     13223996.89      2272337.72     13223596.85
      2272787.70     13223096.88
#Sta/Elev= 30
  4484.7  234.71  4614.8  231.32  4627.5  230.53  4648.3  230.53  4837.7  225.00
  4875.8  223.74  4892.0  222.74  4934.7  222.07  4948.3  220.50  4971.2  220.57
  4998.6  219.60  5003.0  218.92  5005.8  218.42  5009.0  218.92  5012.8  219.74
  5034.5  221.38  5077.1  222.92  5091.3  224.20  5098.0  223.77  5170.1  225.76
  5175.7  226.29  5183.2  225.65  5204.1  226.89  5261.6  228.17  5291.4  228.77
  5443.1  230.93  5459.0  231.73  5527.6  232.64  5629.4  234.57  5657.4  234.54
#Mann=11,-1,0
  4484.7    0.05       0  4614.8     0.1       0  4837.7    0.05       0
  4875.8     0.1       0  5003.0    0.07       0  5009.0     0.1       0
  5170.1    0.05       0  5261.6     0.1       0  5291.4    0.05       0
  5443.1     0.1       0  5527.6    0.05       0
Bank Sta=5003,5009
Exp/Cntr=0.3,0.1

Type RM Length L Ch R = 1,16976,418,418,418
BEGIN DESCRIPTION:
UNT 034 IN RACR 38.0
END DESCRIPTION:
XS GIS Cut Line= 3
      2272337.70     13224296.88      2272687.72     13223896.85
      2272837.72     13223246.88
#Sta/Elev= 30
  4470.2  233.91  4498.2  232.80  4576.5  231.54  4617.0  230.22  4732.7  226.64
  4786.9  225.68  4817.1  224.96  4885.4  221.81  4898.4  221.21  4909.2  221.27
  4916.8  220.09  4937.7  220.11  4945.3  218.87  4995.4  217.66  4998.2  217.16
  5001.4  217.66  5053.1  219.94  5124.9  221.88  5135.2  223.04  5227.5  224.66
  5237.8  225.71  5287.4  225.83  5299.4  227.21  5340.4  227.81  5350.7  228.50
  5463.6  229.74  5494.4  230.94  5573.8  232.06  5638.0  232.24  5668.8  233.53
#Mann=8,-1,0
  4470.2     0.1       0  4617.0    0.05       0  4786.9     0.1       0
  4885.4    0.05       0  4898.4     0.1       0  4995.4    0.07       0
  5001.4     0.1       0  5573.8    0.05       0
Bank Sta=4995.4,5001.4
Exp/Cntr=0.3,0.1

Type RM Length L Ch R = 1,16558,463,463,463
BEGIN DESCRIPTION:
UNT 034 IN RACR 37.0
END DESCRIPTION:
XS GIS Cut Line= 3
      2272937.73     13224396.83      2273087.72     13223996.85
      2273037.72     13223496.82
#Sta/Elev= 30
  4572.8  230.39  4612.8  229.37  4618.2  229.86  4636.8  228.46  4666.3  228.26
  4728.5  226.31  4733.9  227.02  4775.7  224.66  4861.1  222.38  4899.4  220.32
  4904.7  220.70  4967.9  216.82  4978.6  216.72  4984.8  215.56  4990.2  215.52
  4994.3  214.00  4997.0  213.50  5000.3  214.00  5020.1  215.01  5040.2  217.06
  5070.3  217.81  5120.6  220.99  5170.8  222.52  5231.1  225.41  5321.6  226.79
  5371.8  228.24  5454.7  228.91  5482.4  230.48  5499.5  230.70  5502.5  230.73
#Mann=5,-1,0
  4572.8    0.05       0  4666.3     0.1       0  4994.3    0.07       0
  5000.3     0.1       0  5499.5    0.05       0
Bank Sta=4994.3,5000.3
Exp/Cntr=0.3,0.1

Type RM Length L Ch R = 1,16095,495,495,495
BEGIN DESCRIPTION:
UNT 034 IN RACR 36.0
END DESCRIPTION:
XS GIS Cut Line= 3
      2273237.72     13224446.85      2273537.72     13224096.85
      2273887.73     13223696.84
#Sta/Elev= 30
  4547.6  229.02  4661.2  227.58  4717.5  225.24  4788.5  223.60  4796.2  222.64
  4820.1  221.67  4852.2  220.54  4866.4  219.35  4874.1  219.55  4902.7  217.73
  4909.2  217.84  4937.8  215.74  4958.6  215.20  4966.3  213.09  4972.9  214.74
  4980.6  214.01  4987.2  214.04  4991.9  211.72  4994.6  211.22  4997.9  211.72
  5005.3  212.79  5036.6  213.60  5044.2  214.48  5107.8  215.70  5142.9  217.73
  5174.4  218.41  5250.1  221.03  5362.1  223.56  5392.0  224.16  5540.1  228.31
#Mann=9,-1,0
  4547.6     0.1       0  4717.5    0.05       0  4820.1     0.1       0
  4991.9    0.07       0  4997.9     0.1       0  5174.4    0.05       0
  5250.1     0.1       0  5362.1    0.05       0  5392.0     0.1       0
Bank Sta=4991.9,4997.9
Exp/Cntr=0.3,0.1

Type RM Length L Ch R = 1,15600,423,423,423
BEGIN DESCRIPTION:
UNT 034 IN RACR 35.0
END DESCRIPTION:
XS GIS Cut Line= 3
      2273637.69     13224546.88      2273987.72     13224196.85
      2274187.75     13223996.82
#Sta/Elev= 30
  4490.7  225.61  4575.6  223.57  4618.0  222.09  4646.3  221.29  4660.4  221.17
  4674.6  220.58  4717.0  220.04  4765.9  218.74  4801.9  217.79  4858.4  215.70
  4872.6  215.52  4915.0  213.60  4943.3  212.90  4957.4  212.08  4971.6  212.03
  4982.2  211.44  4989.2  211.44  4996.9  209.76  4999.6  209.26  5002.9  209.76
  5014.0  210.12  5028.1  212.97  5042.3  213.92  5056.4  215.21  5070.6  215.57
  5084.7  216.61  5127.1  219.04  5183.7  221.73  5212.0  222.81  5268.6  224.46
#Mann=4,-1,0
  4490.7    0.05       0  4765.9     0.1       0  4996.9    0.07       0
  5002.9     0.1       0
Bank Sta=4996.9,5002.9
Exp/Cntr=0.3,0.1

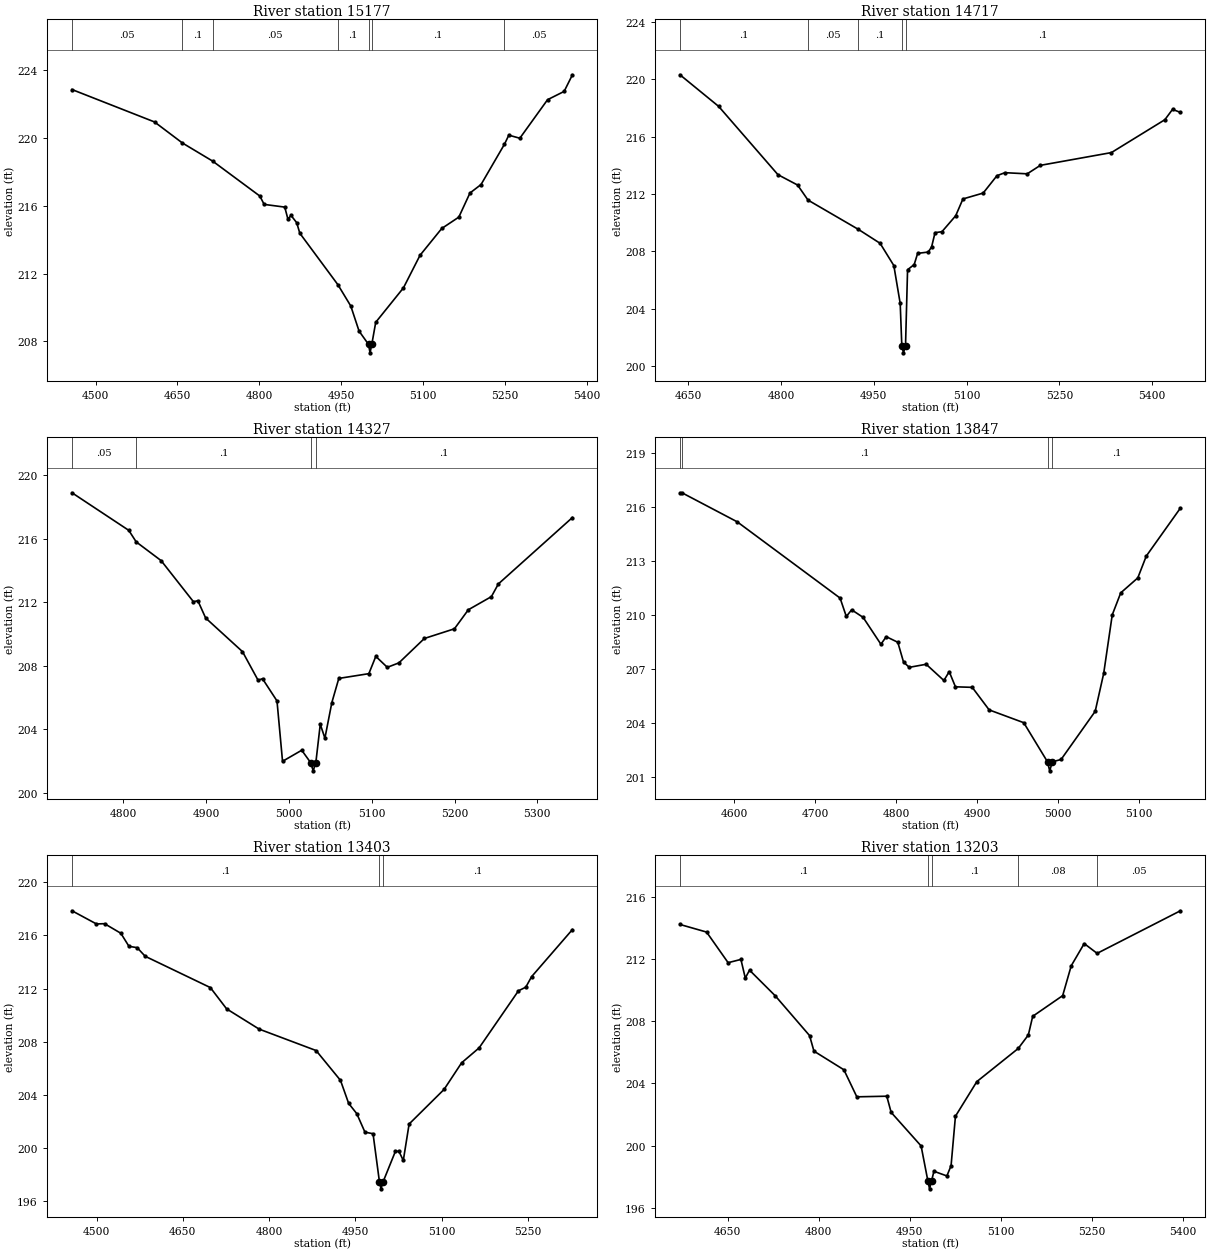
Type RM Length L Ch R = 1,15177,460,460,460
BEGIN DESCRIPTION:
UNT 034 IN RACR 34.0
END DESCRIPTION:
XS GIS Cut Line= 3
      2274072.38     13224958.69      2274278.12     13224583.67
      2274364.05     13224101.93
#Sta/Elev= 30
  4456.7  222.85  4607.9  220.94  4659.0  219.70  4714.5  218.63  4801.0  216.57
  4808.8  216.08  4846.6  215.92  4852.4  215.21  4858.1  215.43  4868.5  215.00
  4874.2  214.38  4943.9  211.35  4967.6  210.09  4982.8  208.61  5000.1  207.83
  5002.9  207.33  5006.1  207.83  5013.3  209.13  5064.1  211.16  5094.5  213.08
  5134.3  214.66  5165.6  215.33  5186.0  216.75  5206.3  217.25  5249.3  219.63
  5257.2  220.16  5277.4  219.98  5328.2  222.25  5358.6  222.74  5373.8  223.72
#Mann=7,-1,0
  4456.7    0.05       0  4659.0     0.1       0  4714.5    0.05       0
  4943.9     0.1       0  5000.1    0.07       0  5006.1     0.1       0
  5249.3    0.05       0
Bank Sta=5000.1,5006.1
Exp/Cntr=0.3,0.1

Type RM Length L Ch R = 1,14717,390,390,390
BEGIN DESCRIPTION:
UNT 034 IN RACR 33.0
END DESCRIPTION:
XS GIS Cut Line= 3
      2274535.39     13225017.94      2274780.17     13224512.77
      2274686.43     13224283.64
#Sta/Elev= 30
  4636.6  220.31  4699.1  218.11  4795.0  213.35  4826.7  212.63  4843.6  211.58
  4925.0  209.54  4960.1  208.57  4982.3  207.02  4992.6  204.38  4995.2  201.44
  4997.9  200.94  5001.2  201.44  5004.5  206.73  5015.2  207.09  5020.8  207.87
  5037.8  207.96  5043.3  208.31  5048.9  209.31  5060.1  209.38  5082.3  210.49
  5094.0  211.66  5126.7  212.07  5149.0  213.28  5161.8  213.49  5197.9  213.41
  5219.1  214.00  5334.0  214.89  5420.4  217.18  5432.8  217.90  5445.5  217.69
#Mann=5,-1,0
  4636.6     0.1       0  4843.6    0.05       0  4925.0     0.1       0
  4995.2    0.07       0  5001.2     0.1       0
Bank Sta=4995.2,5001.2
Exp/Cntr=0.3,0.1

Type RM Length L Ch R = 1,14327,480,480,480
BEGIN DESCRIPTION:
UNT 034 IN RACR 32.0
END DESCRIPTION:
XS GIS Cut Line= 3
      2274937.73     13225096.84      2275037.72     13224846.85
      2275187.74     13224546.81
#Sta/Elev= 30
  4737.8  218.91  4806.4  216.54  4815.4  215.81  4845.5  214.63  4884.5  212.04
  4889.9  212.10  4899.3  211.01  4943.8  208.89  4962.6  207.09  4968.0  207.18
  4985.5  205.78  4992.2  201.97  5015.4  202.67  5026.4  201.87  5029.2  201.37
  5032.4  201.87  5037.8  204.31  5043.4  203.43  5051.8  205.68  5060.2  207.20
  5096.5  207.50  5104.9  208.59  5118.8  207.90  5132.8  208.18  5163.6  209.72
  5199.9  210.33  5216.7  211.53  5244.6  212.36  5253.0  213.16  5342.5  217.35
#Mann=4,-1,0
  4737.8    0.05       0  4815.4     0.1       0  5026.4    0.07       0
  5032.4     0.1       0
Bank Sta=5026.4,5032.4
Exp/Cntr=0.3,0.1

Type RM Length L Ch R = 1,13847,444,444,444
BEGIN DESCRIPTION:
UNT 034 IN RACR 31.0
END DESCRIPTION:
XS GIS Cut Line= 3
      2275137.72     13225146.85      2275487.72     13224846.85
      2275637.73     13224796.85
#Sta/Elev= 30
  4532.6  216.78  4535.1  216.78  4603.4  215.17  4730.7  210.94  4738.4  209.92
  4745.0  210.29  4759.2  209.87  4781.2  208.38  4787.8  208.80  4802.1  208.49
  4809.2  207.39  4816.3  207.10  4837.2  207.27  4859.1  206.37  4865.7  206.86
  4873.4  206.02  4894.2  205.99  4915.1  204.74  4957.9  204.03  4987.3  201.86
  4990.0  201.36  4993.3  201.86  5004.1  201.99  5046.3  204.66  5056.8  206.76
  5067.4  210.01  5077.9  211.23  5099.0  212.06  5109.5  213.27  5151.7  215.93
#Mann=4,-1,0
  4532.6    0.05       0  4535.1     0.1       0  4987.3    0.07       0
  4993.3     0.1       0
Bank Sta=4987.3,4993.3
Exp/Cntr=0.3,0.1

Type RM Length L Ch R = 1,13403,200,200,200
BEGIN DESCRIPTION:
UNT 034 IN RACR 30.0
END DESCRIPTION:
XS GIS Cut Line= 3
      2275337.69     13225596.89      2275737.72     13225196.85
      2275787.72     13224896.83
#Sta/Elev= 30
  4457.3  217.84  4499.8  216.85  4513.9  216.87  4542.2  216.15  4556.3  215.17
  4570.5  215.07  4584.6  214.42  4697.8  212.07  4726.1  210.47  4782.6  208.95
  4881.6  207.34  4924.0  205.10  4938.2  203.37  4952.3  202.60  4966.5  201.21
  4980.6  201.09  4991.8  197.45  4994.5  196.95  4997.8  197.45  5019.5  199.77
  5025.6  199.77  5033.2  199.08  5043.3  201.82  5104.1  204.42  5134.6  206.42
  5165.0  207.54  5233.4  211.83  5246.1  212.10  5256.2  212.89  5327.2  216.43
#Mann=3,-1,0
  4457.3     0.1       0  4991.8    0.07       0  4997.8     0.1       0
Bank Sta=4991.8,4997.8
Exp/Cntr=0.3,0.1

Type RM Length L Ch R = 1,13203,174,174,174
BEGIN DESCRIPTION:
Mapping XS 19bb6c93
END DESCRIPTION:
XS GIS Cut Line= 2
      2275616.66     13225568.05      2276189.59     13224974.29
#Sta/Elev= 30
  4571.1  214.23  4615.0  213.74  4650.5  211.77  4671.6  211.98  4678.8  210.78
  4685.8  211.29  4728.2  209.64  4784.8  207.08  4792.0  206.08  4841.4  204.88
  4862.7  203.14  4912.1  203.18  4919.3  202.14  4968.7  199.98  4979.9  197.72
  4982.6  197.22  4985.9  197.72  4989.8  198.35  5011.2  198.05  5018.1  198.71
  5025.3  201.89  5060.6  204.12  5128.8  206.25  5145.5  207.12  5152.7  208.32
  5202.1  209.65  5216.2  211.57  5237.6  213.00  5258.9  212.37  5396.2  215.11
#Mann=5,-1,0
  4571.1     0.1       0  4979.9    0.07       0  4985.9     0.1       0
  5128.8    0.08       0  5258.9    0.05       0
Bank Sta=4979.9,4985.9
Exp/Cntr=0.3,0.1