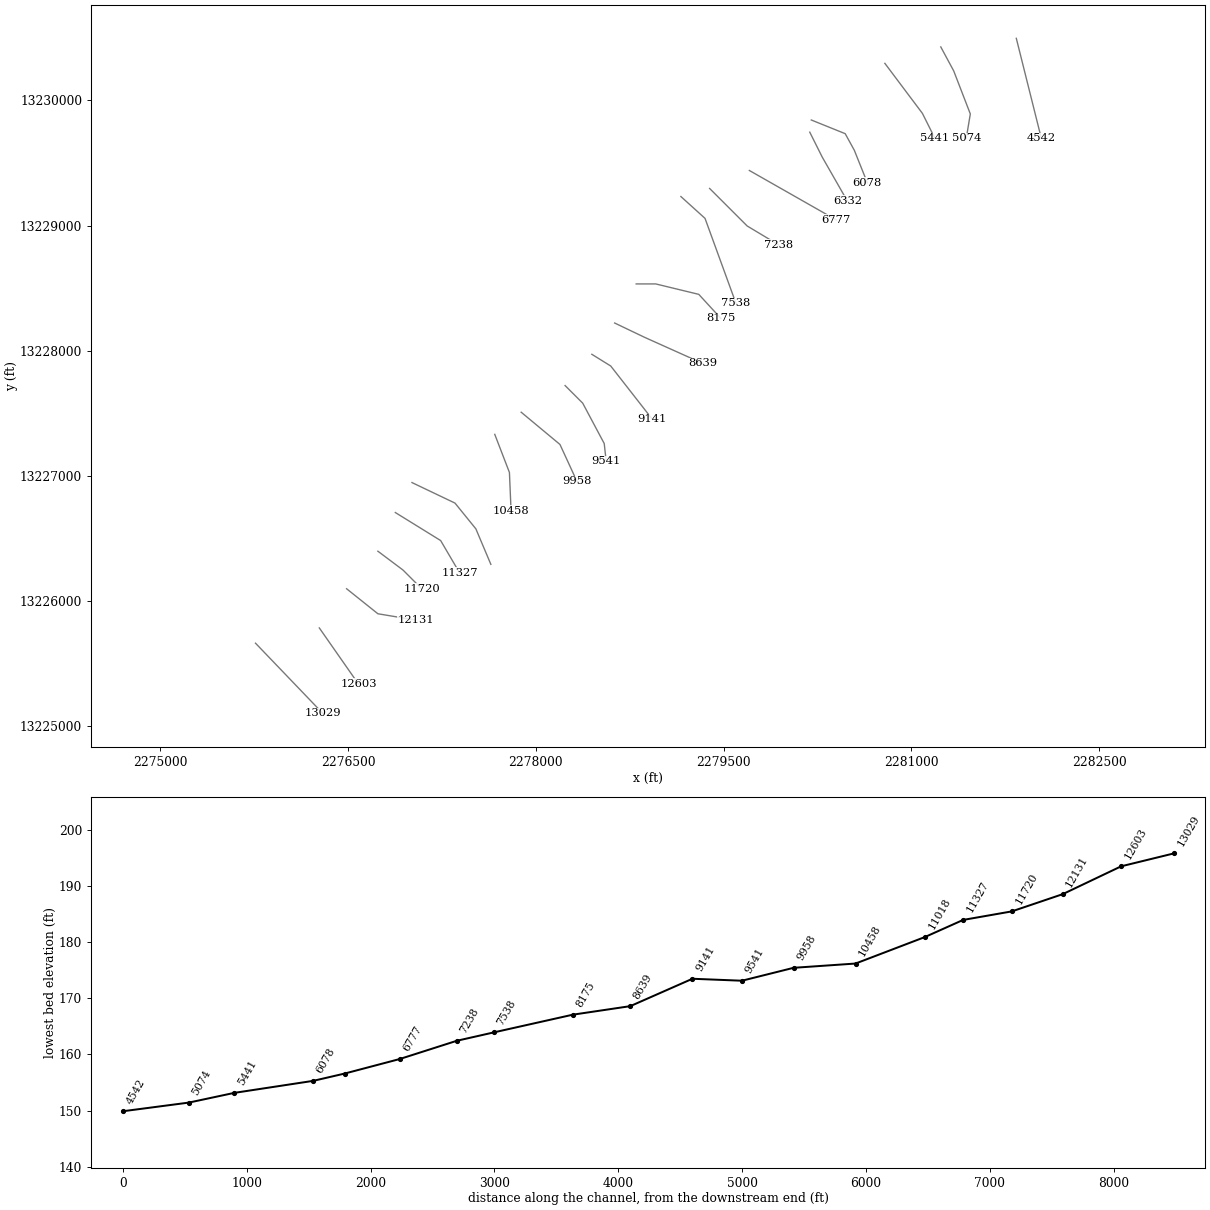
HEC-RAS study UNT 034 IN RACR.prj: UNT 034 IN RACR Base Level Engineering

--- UNT 034 IN RACR.g01 (geometry) --- (continued)

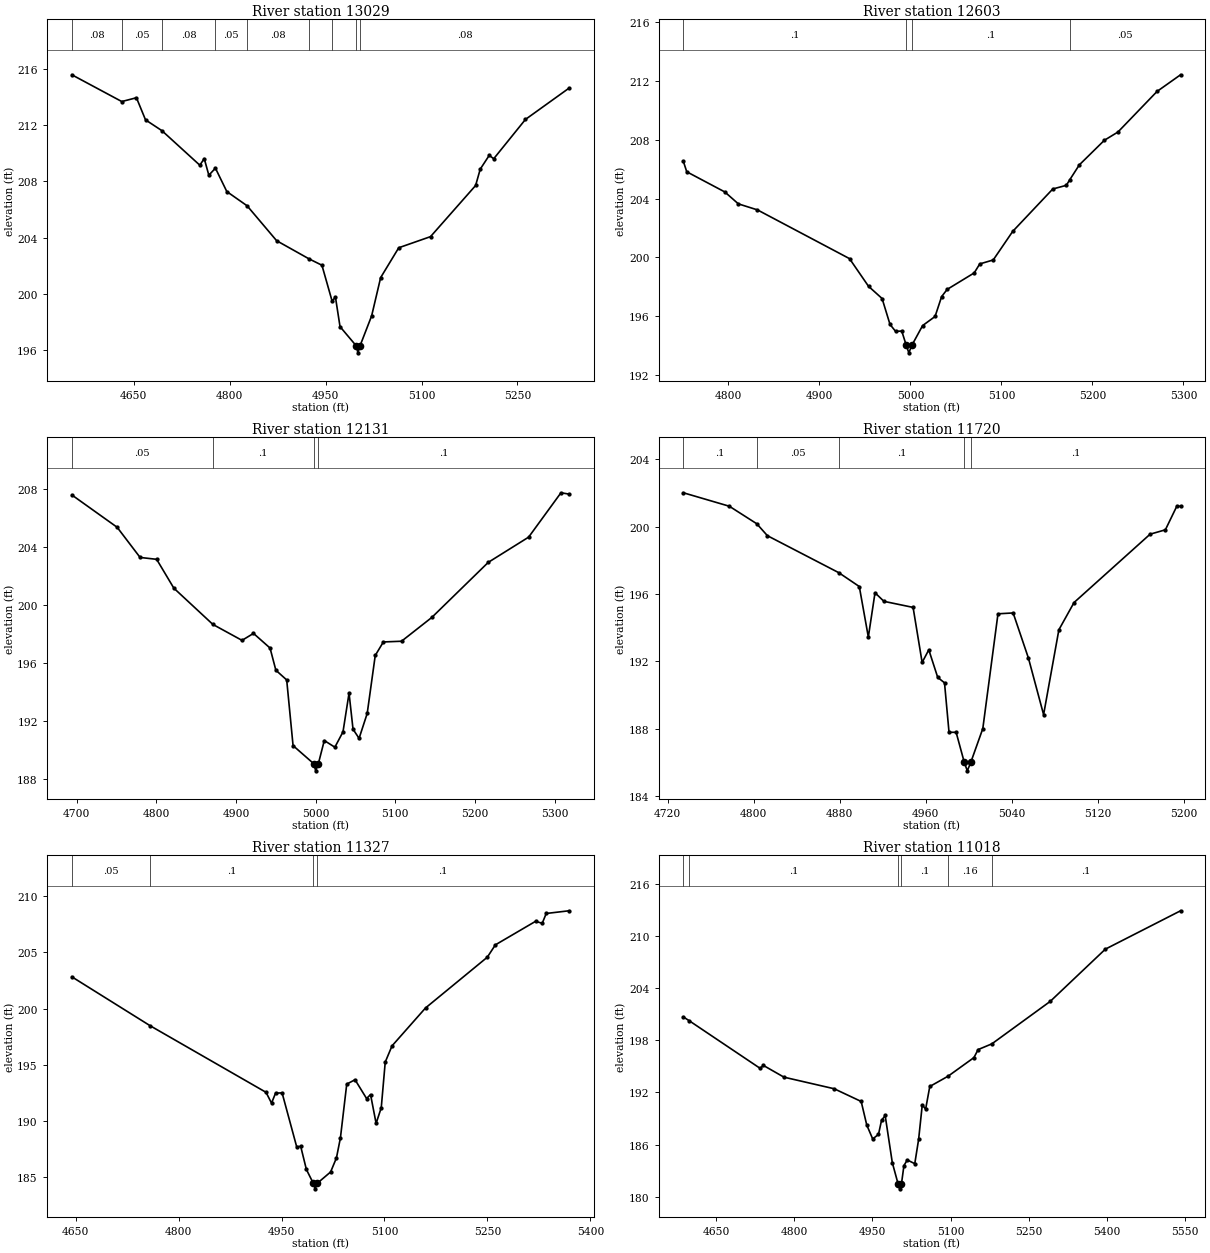
Type RM Length L Ch R = 1,13029,426,426,426
BEGIN DESCRIPTION:
UNT 034 IN RACR 29.0
END DESCRIPTION:
XS GIS Cut Line= 2
      2275759.92     13225661.77      2276297.74     13225100.56
#Sta/Elev= 30
  4553.3  215.56  4631.4  213.66  4654.3  213.93  4668.5  212.36  4694.2  211.59
  4753.4  209.14  4760.3  209.61  4767.5  208.43  4777.8  208.93  4795.6  207.27
  4827.3  206.26  4873.5  203.78  4924.2  202.49  4944.3  202.04  4960.3  199.48
  4965.4  199.79  4972.6  197.68  4997.9  196.32  5000.6  195.82  5003.9  196.32
  5022.0  198.44  5036.1  201.16  5064.4  203.28  5114.1  204.07  5184.6  207.70
  5191.8  208.86  5205.9  209.84  5212.9  209.60  5262.5  212.39  5330.6  214.61
#Mann=9,-1,0
  4553.3    0.08       0  4631.4    0.05       0  4694.2    0.08       0
  4777.8    0.05       0  4827.3    0.08       0  4924.2    0.05       0
  4960.3    0.08       0  4997.9    0.07       0  5003.9    0.08       0
Bank Sta=4997.9,5003.9
Exp/Cntr=0.3,0.1

Type RM Length L Ch R = 1,12603,472,472,472
BEGIN DESCRIPTION:
UNT 034 IN RACR 28.0
END DESCRIPTION:
XS GIS Cut Line= 2
      2276269.74     13225783.61      2276582.27     13225335.66
#Sta/Elev= 30
  4750.6  206.52  4754.3  205.82  4796.1  204.45  4811.0  203.64  4832.0  203.23
  4933.1  199.92  4954.0  198.04  4968.9  197.21  4977.6  195.45  4983.7  194.98
  4990.5  195.00  4995.5  194.02  4998.3  193.52  5001.5  194.02  5013.4  195.37
  5027.1  195.99  5034.3  197.34  5040.4  197.83  5070.1  198.95  5076.2  199.56
  5091.0  199.83  5112.4  201.77  5156.4  204.65  5171.3  204.90  5175.0  205.27
  5185.6  206.29  5213.1  207.96  5228.0  208.52  5271.0  211.28  5296.8  212.41
#Mann=4,-1,0
  4750.6     0.1       0  4995.5    0.07       0  5001.5     0.1       0
  5175.0    0.05       0
Bank Sta=4995.5,5001.5
Exp/Cntr=0.3,0.1

Type RM Length L Ch R = 1,12131,411,411,411
BEGIN DESCRIPTION:
UNT 034 IN RACR 27.0
END DESCRIPTION:
XS GIS Cut Line= 3
      2276487.70     13226096.87      2276737.72     13225896.85
      2277037.70     13225846.86
#Sta/Elev= 30
  4693.8  207.59  4750.7  205.36  4779.5  203.28  4800.3  203.15  4821.9  201.16
  4870.9  198.66  4907.5  197.56  4921.9  198.04  4942.7  197.03  4950.0  195.50
  4963.6  194.83  4971.6  190.30  4997.4  189.06  5000.1  188.56  5003.4  189.06
  5010.8  190.65  5024.1  190.19  5034.3  191.25  5041.9  193.92  5046.9  191.43
  5054.5  190.80  5064.7  192.52  5074.8  196.52  5085.0  197.45  5107.8  197.50
  5145.8  199.14  5216.7  202.94  5267.4  204.68  5308.0  207.74  5318.1  207.65
#Mann=4,-1,0
  4693.8    0.05       0  4870.9     0.1       0  4997.4    0.07       0
  5003.4     0.1       0
Bank Sta=4997.4,5003.4
Exp/Cntr=0.3,0.1

Type RM Length L Ch R = 1,11720,393,393,393
BEGIN DESCRIPTION:
UNT 034 IN RACR 26.0
END DESCRIPTION:
XS GIS Cut Line= 3
      2276737.74     13226396.84      2276937.72     13226246.85
      2277087.71     13226096.86
#Sta/Elev= 30
  4734.7  202.01  4777.4  201.21  4802.9  200.17  4812.8  199.46  4879.2  197.26
  4898.2  196.44  4906.6  193.44  4912.8  196.07  4921.1  195.56  4948.2  195.20
  4956.6  191.93  4962.8  192.68  4971.1  191.04  4977.4  190.72  4981.6  187.78
  4988.2  187.78  4995.8  185.99  4998.6  185.49  5001.8  185.99  5013.0  188.00
  5027.1  194.82  5041.2  194.87  5055.4  192.19  5069.5  188.83  5083.7  193.87
  5097.8  195.49  5168.5  199.55  5182.7  199.81  5193.3  201.21  5196.8  201.21
#Mann=5,-1,0
  4734.7     0.1       0  4802.9    0.05       0  4879.2     0.1       0
  4995.8    0.07       0  5001.8     0.1       0
Bank Sta=4995.8,5001.8
Exp/Cntr=0.3,0.1

Type RM Length L Ch R = 1,11327,309,309,309
BEGIN DESCRIPTION:
UNT 034 IN RACR 25.0
END DESCRIPTION:
XS GIS Cut Line= 3
      2276877.05     13226706.09      2277239.06     13226482.11
      2277390.10     13226224.29
#Sta/Elev= 30
  4644.4  202.82  4758.5  198.47  4927.4  192.55  4935.4  191.59  4941.3  192.48
  4950.8  192.50  4972.1  187.70  4977.9  187.75  4986.2  185.69  4996.2  184.47
  4999.0  183.97  5002.2  184.47  5021.5  185.47  5030.0  186.72  5035.8  188.50
  5045.0  193.28  5057.1  193.67  5073.9  192.00  5079.7  192.35  5087.8  189.79
  5095.3  191.18  5101.1  195.24  5111.0  196.68  5159.8  200.05  5249.8  204.56
  5261.6  205.66  5320.1  207.75  5329.9  207.58  5335.7  208.45  5368.9  208.69
#Mann=4,-1,0
  4644.4    0.05       0  4758.5     0.1       0  4996.2    0.07       0
  5002.2     0.1       0
Bank Sta=4996.2,5002.2
Exp/Cntr=0.3,0.1

Type RM Length L Ch R = 1,11018,560,560,560
BEGIN DESCRIPTION:
UNT 034 IN RACR 24.0
END DESCRIPTION:
XS GIS Cut Line= 4
      2277009.90     13226945.65      2277353.64     13226781.59
      2277520.31     13226575.86      2277640.12     13226291.96
#Sta/Elev= 30
  4587.5  200.67  4598.3  200.25  4735.1  194.75  4740.7  195.11  4780.5  193.75
  4876.8  192.42  4928.6  190.96  4939.3  188.25  4950.7  186.65  4961.8  187.18
  4967.6  188.78  4974.6  189.35  4988.3  183.93  4999.7  181.42  5002.4  180.92
  5005.7  181.42  5010.6  183.59  5017.0  184.24  5031.4  183.81  5038.8  186.61
  5045.8  190.58  5052.2  190.07  5060.2  192.68  5095.5  193.87  5144.9  196.00
  5152.9  196.92  5179.3  197.58  5291.3  202.46  5397.0  208.46  5541.3  212.87
#Mann=6,-1,0
  4587.5    0.05       0  4598.3     0.1       0  4999.7    0.07       0
  5005.7     0.1       0  5095.5    0.16       0  5179.3     0.1       0
Bank Sta=4999.7,5005.7
Exp/Cntr=0.3,0.1

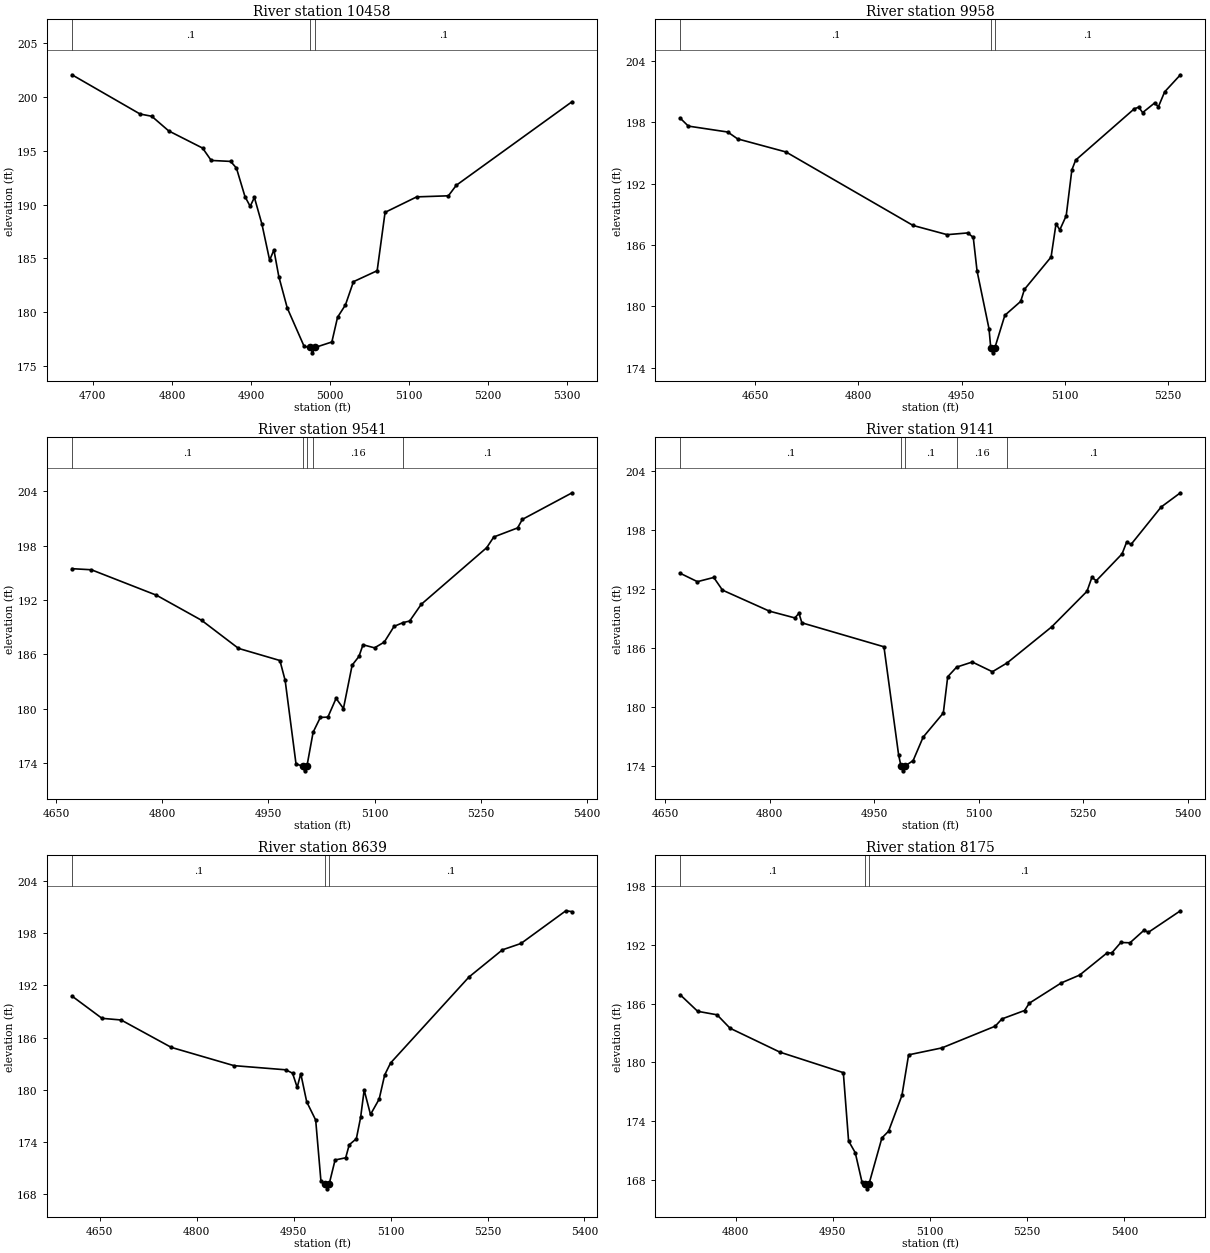
Type RM Length L Ch R = 1,10458,500,500,500
BEGIN DESCRIPTION:
UNT 034 IN RACR 23.0
END DESCRIPTION:
XS GIS Cut Line= 3
      2277671.37     13227331.02      2277788.54     13227026.38
      2277801.50     13226720.46
#Sta/Elev= 30
  4673.6  202.07  4759.7  198.42  4774.5  198.21  4795.9  196.85  4838.8  195.25
  4849.7  194.10  4874.3  194.01  4881.6  193.39  4892.4  190.74  4899.0  189.83
  4904.3  190.66  4913.8  188.19  4923.6  184.82  4929.0  185.77  4935.2  183.30
  4945.9  180.37  4967.3  176.79  4975.1  176.70  4977.8  176.20  4981.1  176.70
  5002.3  177.21  5009.5  179.51  5019.5  180.66  5029.6  182.82  5059.6  183.84
  5069.6  189.27  5109.6  190.71  5149.7  190.81  5159.7  191.79  5306.2  199.57
#Mann=3,-1,0
  4673.6     0.1       0  4975.1    0.07       0  4981.1     0.1       0
Bank Sta=4975.1,4981.1
Exp/Cntr=0.3,0.1

Type RM Length L Ch R = 1,9958,417,417,417
BEGIN DESCRIPTION:
UNT 034 IN RACR 22.0
END DESCRIPTION:
XS GIS Cut Line= 3
      2277882.32     13227508.12      2278192.18     13227250.34
      2278327.60     13226956.08
#Sta/Elev= 30
  4541.1  198.39  4552.8  197.62  4610.1  197.04  4624.4  196.37  4694.7  195.09
  4879.5  187.90  4929.0  187.00  4959.0  187.17  4967.0  186.73  4972.5  183.45
  4989.9  177.79  4992.4  175.94  4995.2  175.44  4998.4  175.94  5012.9  179.11
  5035.9  180.47  5041.4  181.65  5080.1  184.81  5087.3  188.06  5092.8  187.47
  5102.1  188.85  5110.3  193.33  5115.8  194.29  5201.2  199.32  5207.6  199.47
  5213.2  198.94  5230.6  199.88  5236.1  199.51  5245.2  200.97  5268.1  202.64
#Mann=3,-1,0
  4541.1     0.1       0  4992.4    0.07       0  4998.4     0.1       0
Bank Sta=4992.4,4998.4
Exp/Cntr=0.3,0.1

Type RM Length L Ch R = 1,9541,400,400,400
BEGIN DESCRIPTION:
UNT 034 IN RACR 21.0
END DESCRIPTION:
XS GIS Cut Line= 4
      2278233.26     13227721.13      2278373.92     13227580.48
      2278545.79     13227257.56      2278561.41     13227116.95
#Sta/Elev= 30
  4672.7  195.46  4700.1  195.34  4792.0  192.53  4855.7  189.76  4907.8  186.66
  4966.3  185.32  4973.7  183.12  4989.0  173.92  4998.4  173.64  5001.1  173.14
  5004.4  173.64  5013.2  177.41  5023.4  179.04  5034.0  179.07  5045.6  181.14
  5056.0  180.02  5068.3  184.81  5077.9  185.77  5083.6  187.06  5099.9  186.72
  5113.6  187.35  5127.5  189.09  5140.3  189.51  5149.5  189.68  5165.8  191.52
  5258.3  197.78  5268.3  198.96  5301.9  199.96  5308.6  200.90  5378.9  203.84
#Mann=5,-1,0
  4672.7     0.1       0  4998.4    0.07       0  5004.4     0.1       0
  5013.2    0.16       0  5140.3     0.1       0
Bank Sta=4998.4,5004.4
Exp/Cntr=0.3,0.1

Type RM Length L Ch R = 1,9141,502,502,502
BEGIN DESCRIPTION:
UNT 034 IN RACR 20.0
END DESCRIPTION:
XS GIS Cut Line= 3
      2278446.83     13227971.11      2278597.87     13227877.35
      2278930.57     13227451.09
#Sta/Elev= 30
  4671.3  193.60  4695.9  192.75  4719.4  193.18  4731.9  191.89  4799.3  189.75
  4835.9  189.06  4841.8  189.53  4846.0  188.56  4963.9  186.12  4984.9  175.15
  4988.3  173.99  4991.0  173.49  4994.3  173.99  5005.8  174.53  5020.2  176.92
  5049.2  179.38  5055.5  183.07  5068.3  184.05  5090.8  184.57  5119.7  183.58
  5140.9  184.48  5204.9  188.15  5255.6  191.77  5262.6  193.18  5269.0  192.85
  5306.0  195.58  5312.4  196.75  5319.1  196.56  5362.1  200.35  5389.8  201.80
#Mann=5,-1,0
  4671.3     0.1       0  4988.3    0.07       0  4994.3     0.1       0
  5068.3    0.16       0  5140.9     0.1       0
Bank Sta=4988.3,4994.3
Exp/Cntr=0.3,0.1

Type RM Length L Ch R = 1,8639,464,464,464
BEGIN DESCRIPTION:
UNT 034 IN RACR 19.0
END DESCRIPTION:
XS GIS Cut Line= 3
      2278629.16     13228221.09      2278868.71     13228106.52
      2279332.21     13227898.21
#Sta/Elev= 30
  4607.2  190.78  4653.6  188.22  4683.2  188.03  4760.8  184.88  4857.7  182.78
  4937.9  182.30  4948.4  181.91  4955.6  180.28  4961.1  181.86  4970.3  178.62
  4984.2  176.52  4992.3  169.52  4998.9  169.11  5001.7  168.61  5004.9  169.11
  5014.2  171.93  5030.6  172.18  5036.1  173.68  5047.1  174.37  5053.7  176.82
  5059.2  179.97  5069.0  177.16  5082.4  178.93  5090.9  181.70  5100.0  183.08
  5221.3  192.97  5273.1  196.10  5301.8  196.83  5371.2  200.59  5380.9  200.49
#Mann=3,-1,0
  4607.2     0.1       0  4998.9    0.07       0  5004.9     0.1       0
Bank Sta=4998.9,5004.9
Exp/Cntr=0.3,0.1

Type RM Length L Ch R = 1,8175,637,637,637
BEGIN DESCRIPTION:
UNT 034 IN RACR 18.0
END DESCRIPTION:
XS GIS Cut Line= 4
      2278800.96     13228533.60      2278957.25     13228533.60
      2279301.00     13228450.27      2279478.07     13228257.57
#Sta/Elev= 30
  4714.6  186.91  4741.4  185.23  4771.4  184.87  4791.4  183.50  4868.6  181.05
  4966.2  178.96  4974.3  171.98  4984.6  170.78  4994.9  167.81  4999.8  167.59
  5002.6  167.09  5005.8  167.59  5025.7  172.29  5036.0  172.98  5056.6  176.63
  5066.9  180.78  5118.3  181.49  5200.6  183.71  5210.9  184.45  5245.8  185.31
  5253.2  186.06  5302.5  188.13  5330.8  188.93  5373.4  191.21  5380.2  191.18
  5394.4  192.26  5408.5  192.23  5430.1  193.51  5436.9  193.30  5486.3  195.50
#Mann=3,-1,0
  4714.6     0.1       0  4999.8    0.07       0  5005.8     0.1       0
Bank Sta=4999.8,5005.8
Exp/Cntr=0.3,0.1

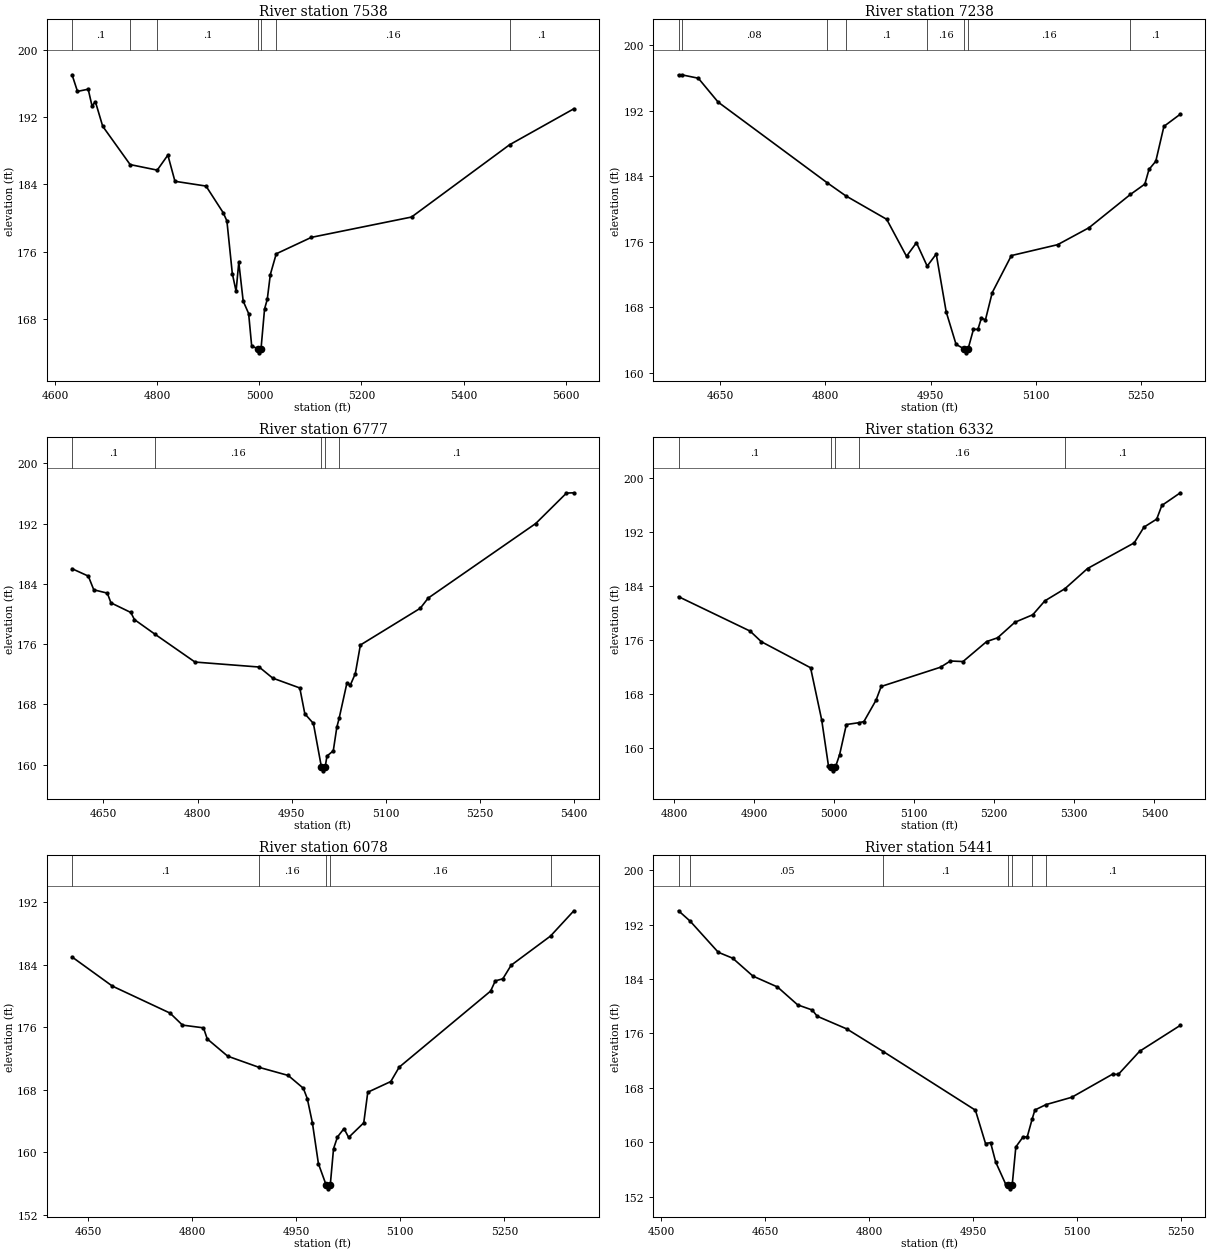
Type RM Length L Ch R = 1,7538,300,300,300
BEGIN DESCRIPTION:
UNT 034 IN RACR 17.0
END DESCRIPTION:
XS GIS Cut Line= 3
      2279158.29     13229232.14      2279351.04     13229057.63
      2279598.43     13228377.96
#Sta/Elev= 30
  4632.9  197.07  4643.5  195.09  4664.5  195.35  4671.9  193.38  4678.7  193.85
  4692.9  190.94  4746.7  186.37  4799.8  185.71  4820.6  187.50  4834.5  184.38
  4895.4  183.81  4929.0  180.64  4936.3  179.66  4946.9  173.39  4954.3  171.28
  4959.6  174.73  4968.2  170.11  4978.9  168.62  4984.9  164.73  4997.2  164.44
  4999.9  163.94  5003.2  164.44  5010.1  169.17  5015.4  170.31  5021.4  173.27
  5033.0  175.74  5101.9  177.70  5298.1  180.12  5490.2  188.73  5616.2  193.02
#Mann=7,-1,0
  4632.9     0.1       0  4746.7    0.05       0  4799.8     0.1       0
  4997.2    0.07       0  5003.2     0.1       0  5033.0    0.16       0
  5490.2     0.1       0
Bank Sta=4997.2,5003.2
Exp/Cntr=0.3,0.1

Type RM Length L Ch R = 1,7238,461,461,461
BEGIN DESCRIPTION:
UNT 034 IN RACR 16.0
END DESCRIPTION:
XS GIS Cut Line= 3
      2279387.75     13229296.82      2279687.72     13228996.85
      2279937.75     13228846.84
#Sta/Elev= 30
  4590.5  196.38  4594.8  196.40  4618.7  195.98  4647.0  193.06  4802.1  183.24
  4828.8  181.63  4887.4  178.75  4915.7  174.23  4929.9  175.89  4945.2  173.03
  4958.1  174.51  4972.3  167.45  4986.4  163.47  4997.6  162.94  5000.3  162.44
  5003.6  162.94  5011.2  165.31  5017.6  165.31  5022.5  166.69  5028.3  166.47
  5038.0  169.80  5065.3  174.32  5131.3  175.65  5176.0  177.72  5235.0  181.78
  5255.7  183.05  5261.6  184.84  5271.3  185.84  5282.9  190.10  5306.3  191.59
#Mann=8,-1,0
  4590.5     0.1       0  4594.8    0.08       0  4802.1    0.16       0
  4828.8     0.1       0  4945.2    0.16       0  4997.6    0.07       0
  5003.6    0.16       0  5235.0     0.1       0
Bank Sta=4997.6,5003.6
Exp/Cntr=0.3,0.1

Type RM Length L Ch R = 1,6777,445,445,445
BEGIN DESCRIPTION:
UNT 034 IN RACR 15.0
END DESCRIPTION:
XS GIS Cut Line= 2
      2279705.23     13229440.43      2280400.55     13229044.59
#Sta/Elev= 30
  4600.0  186.02  4625.9  185.04  4634.6  183.22  4656.2  182.78  4662.0  181.49
  4693.7  180.21  4699.4  179.27  4732.3  177.32  4796.0  173.63  4898.3  172.97
  4919.9  171.50  4963.1  170.19  4971.1  166.77  4984.8  165.48  4997.6  159.69
  5000.4  159.19  5003.6  159.69  5006.4  161.15  5016.5  161.85  5022.2  165.00
  5025.8  166.15  5038.1  170.79  5043.8  170.60  5051.6  172.08  5059.7  175.89
  5155.2  180.77  5167.8  182.12  5339.3  192.02  5388.3  196.06  5400.1  196.10
#Mann=5,-1,0
  4600.0     0.1       0  4732.3    0.16       0  4997.6    0.07       0
  5003.6    0.16       0  5025.8     0.1       0
Bank Sta=4997.6,5003.6
Exp/Cntr=0.3,0.1

Type RM Length L Ch R = 1,6332,254,254,254
BEGIN DESCRIPTION:
UNT 034 IN RACR 14.0
END DESCRIPTION:
XS GIS Cut Line= 3
      2280187.74     13229746.82      2280287.72     13229546.85
      2280487.73     13229196.83
#Sta/Elev= 30
  4805.7  182.40  4895.1  177.30  4909.1  175.73  4970.6  171.87  4984.5  164.14
  4992.9  157.38  4995.5  157.10  4998.3  156.60  5001.5  157.10  5006.9  159.01
  5015.3  163.46  5031.4  163.74  5037.2  163.90  5052.3  167.05  5058.8  169.10
  5132.9  171.95  5145.2  172.87  5161.0  172.79  5190.5  175.75  5204.2  176.31
  5225.8  178.61  5248.1  179.72  5263.2  181.78  5288.3  183.58  5316.5  186.57
  5374.8  190.37  5387.0  192.70  5402.9  193.89  5409.3  195.91  5432.4  197.79
#Mann=5,-1,0
  4805.7     0.1       0  4995.5    0.07       0  5001.5     0.1       0
  5031.4    0.16       0  5288.3     0.1       0
Bank Sta=4995.5,5001.5
Exp/Cntr=0.3,0.1

Type RM Length L Ch R = 1,6078,637,637,637
BEGIN DESCRIPTION:
UNT 034 IN RACR 13.0
END DESCRIPTION:
XS GIS Cut Line= 4
      2280199.98     13229844.09      2280470.83     13229734.71
      2280543.75     13229601.90      2280647.84     13229341.66
#Sta/Elev= 30
  4626.4  185.01  4684.5  181.28  4767.7  177.82  4785.7  176.28  4816.0  175.93
  4821.4  174.51  4850.9  172.30  4895.7  170.88  4938.2  169.83  4960.0  168.19
  4965.7  166.87  4973.1  163.76  4981.8  158.52  4992.9  155.80  4995.7  155.30
  4998.9  155.80  5003.6  160.44  5009.3  161.95  5018.7  163.02  5025.4  161.89
  5047.2  163.76  5053.0  167.68  5086.2  169.05  5098.3  170.89  5230.2  180.64
  5237.0  181.95  5247.8  182.21  5259.8  183.95  5316.6  187.69  5350.3  190.93
#Mann=5,-1,0
  4626.4     0.1       0  4895.7    0.16       0  4992.9    0.07       0
  4998.9    0.16       0  5316.6     0.1       0
Bank Sta=4992.9,4998.9
Exp/Cntr=0.3,0.1

Type RM Length L Ch R = 1,5441,367,367,367
BEGIN DESCRIPTION:
UNT 034 IN RACR 12.0
END DESCRIPTION:
XS GIS Cut Line= 3
      2280787.74     13230296.83      2281087.72     13229896.85
      2281187.73     13229696.84
#Sta/Elev= 30
  4525.1  194.03  4541.9  192.50  4582.4  187.93  4603.2  187.06  4632.4  184.43
  4667.8  182.83  4696.9  180.20  4717.8  179.45  4725.1  178.53  4767.8  176.66
  4820.3  173.34  4953.2  164.72  4967.8  159.82  4975.1  159.96  4982.4  157.11
  4996.9  153.84  5000.2  153.66  5002.9  153.16  5006.2  153.66  5011.5  159.32
  5021.9  160.79  5027.9  160.79  5035.1  163.44  5039.0  164.75  5055.0  165.54
  5092.2  166.62  5150.9  170.01  5159.2  169.97  5190.0  173.38  5248.7  177.19
#Mann=7,-1,0
  4525.1     0.1       0  4541.9    0.05       0  4820.3     0.1       0
  5000.2    0.07       0  5006.2     0.1       0  5035.1    0.16       0
  5055.0     0.1       0
Bank Sta=5000.2,5006.2
Exp/Cntr=0.3,0.1

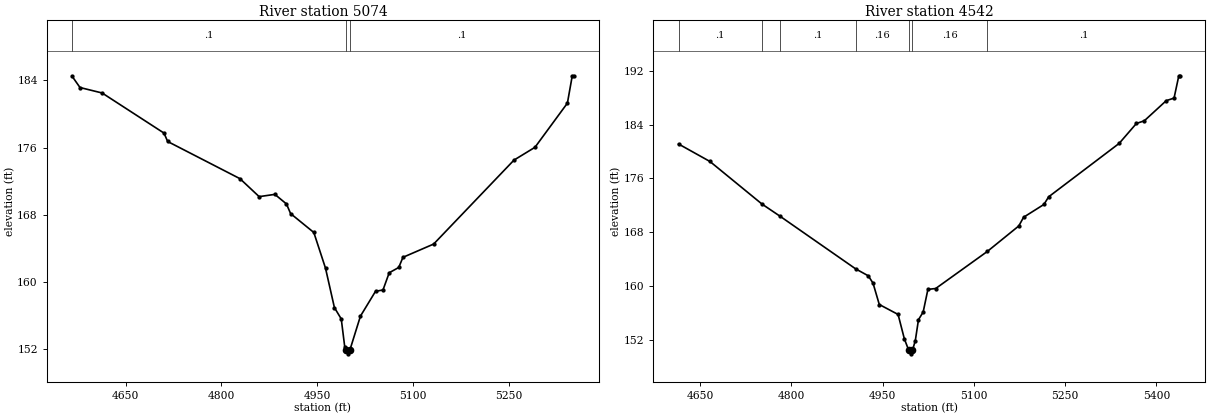
Type RM Length L Ch R = 1,5074,532,532,532
BEGIN DESCRIPTION:
UNT 034 IN RACR 11.0
END DESCRIPTION:
XS GIS Cut Line= 4
      2281234.41     13230428.21      2281337.63     13230236.51
      2281470.36     13229892.41      2281437.72     13229696.85
#Sta/Elev= 30
  4566.3  184.51  4578.7  183.16  4613.3  182.51  4710.1  177.73  4715.8  176.73
  4828.9  172.30  4858.9  170.16  4883.5  170.43  4901.6  169.29  4908.1  168.14
  4944.4  165.89  4962.7  161.63  4976.6  156.94  4987.3  155.59  4992.7  152.29
  4995.0  151.93  4997.8  151.43  5001.0  151.93  5017.3  155.92  5040.9  158.88
  5052.6  159.04  5062.3  161.09  5077.2  161.72  5083.8  162.93  5131.8  164.51
  5257.4  174.51  5290.3  176.04  5341.0  181.30  5348.6  184.56  5351.1  184.56
#Mann=3,-1,0
  4566.3     0.1       0  4995.0    0.07       0  5001.0     0.1       0
Bank Sta=4995,5001
Exp/Cntr=0.3,0.1

Type RM Length L Ch R = 1,4542,387,387,387
BEGIN DESCRIPTION:
UNT 034 IN RACR 10.0
END DESCRIPTION:
XS GIS Cut Line= 3
      2281837.71     13230496.88      2281937.72     13230096.85
      2282037.71     13229696.90
#Sta/Elev= 30
  4614.6  181.11  4666.2  178.51  4751.8  172.17  4781.3  170.37  4905.7  162.53
  4926.4  161.50  4934.2  160.41  4944.5  157.23  4975.4  155.75  4985.7  152.12
  4993.0  150.39  4995.8  149.89  4999.0  150.39  5003.7  151.86  5008.9  154.97
  5016.6  156.11  5024.4  159.48  5037.2  159.61  5122.0  165.12  5173.8  168.92
  5181.6  170.21  5215.1  172.12  5222.8  173.25  5338.7  181.20  5367.1  184.17
  5380.0  184.56  5416.1  187.56  5428.9  187.94  5436.7  191.26  5439.2  191.26
#Mann=7,-1,0
  4614.6     0.1       0  4751.8    0.16       0  4781.3     0.1       0
  4905.7    0.16       0  4993.0    0.07       0  4999.0    0.16       0
  5122.0     0.1       0
Bank Sta=4993,4999
Exp/Cntr=0.3,0.1