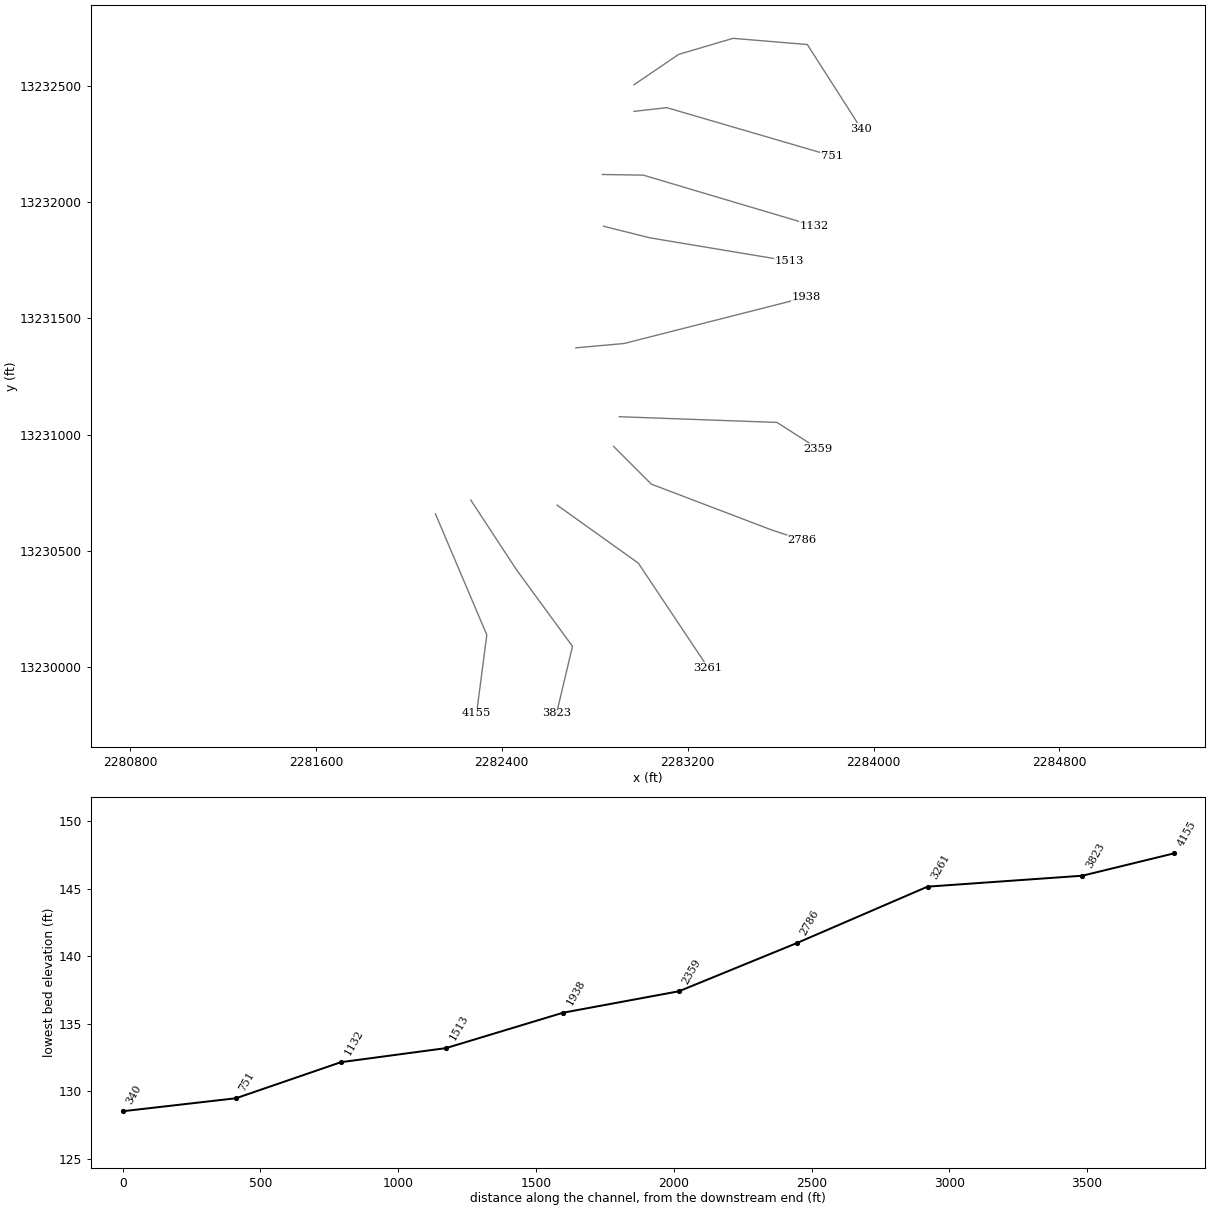
HEC-RAS study UNT 034 IN RACR.prj: UNT 034 IN RACR Base Level Engineering

--- UNT 034 IN RACR.g01 (geometry) --- (continued)

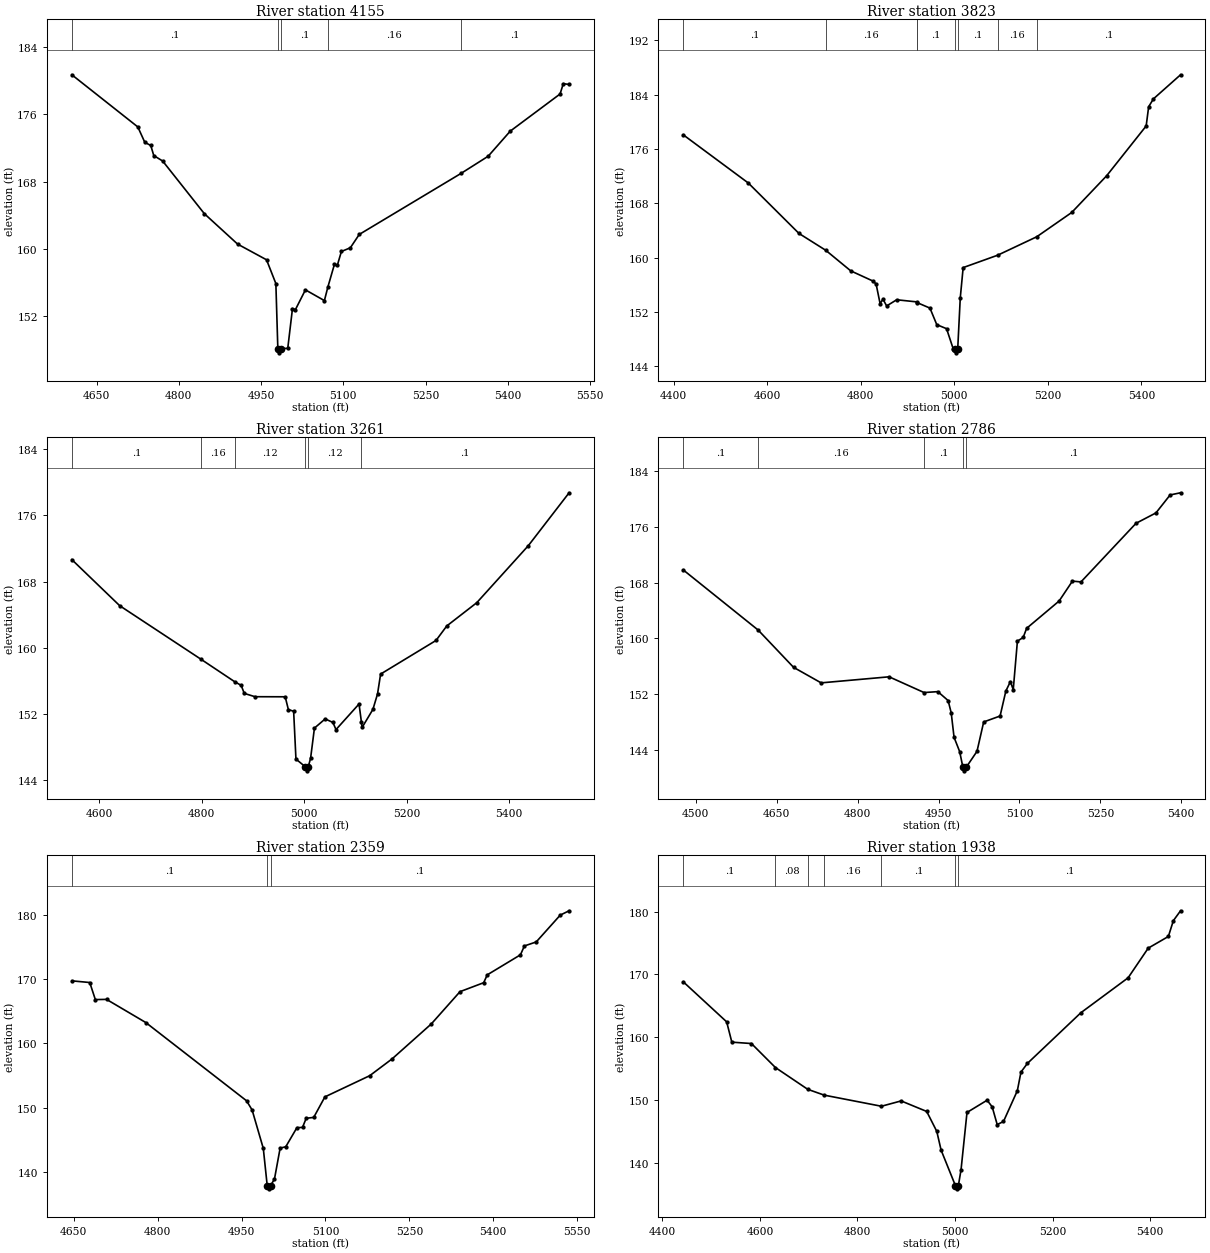
Type RM Length L Ch R = 1,4155,332,332,332
BEGIN DESCRIPTION:
UNT 034 IN RACR 9.0
END DESCRIPTION:
XS GIS Cut Line= 3
      2282114.29     13230659.28      2282335.51     13230138.19
      2282291.46     13229800.45
#Sta/Elev= 30
  4604.9  180.72  4725.2  174.51  4737.9  172.68  4748.8  172.30  4754.3  171.10
  4770.5  170.45  4846.5  164.18  4907.1  160.56  4959.9  158.69  4976.9  155.86
  4980.5  148.11  4983.3  147.61  4986.5  148.11  4998.6  148.15  5007.2  152.88
  5012.6  152.76  5030.8  155.11  5065.4  153.83  5071.7  155.44  5083.6  158.13
  5089.0  158.04  5096.4  159.68  5112.7  160.12  5129.0  161.71  5314.4  168.97
  5364.0  171.02  5404.3  174.01  5495.1  178.43  5501.0  179.66  5511.6  179.57
#Mann=5,-1,0
  4604.9     0.1       0  4980.5    0.07       0  4986.5     0.1       0
  5071.7    0.16       0  5314.4     0.1       0
Bank Sta=4980.5,4986.5
Exp/Cntr=0.3,0.1

Type RM Length L Ch R = 1,3823,562,562,562
BEGIN DESCRIPTION:
UNT 034 IN RACR 8.0
END DESCRIPTION:
XS GIS Cut Line= 4
      2282266.68     13230718.25      2282463.32     13230418.38
      2282704.18     13230089.04      2282635.71     13229800.46
#Sta/Elev= 30
  4420.4  178.08  4559.3  170.99  4667.8  163.55  4725.0  161.07  4778.4  158.04
  4826.5  156.52  4832.7  156.09  4841.2  153.21  4847.4  153.86  4855.2  152.87
  4876.7  153.78  4919.2  153.47  4920.4  153.36  4947.8  152.55  4962.4  150.11
  4983.3  149.52  4997.9  146.47  5001.1  146.46  5003.9  145.96  5007.1  146.46
  5012.6  154.05  5018.8  158.52  5092.4  160.34  5176.1  163.06  5250.9  166.64
  5325.6  172.05  5410.1  179.39  5415.4  182.22  5425.6  183.38  5483.6  186.93
#Mann=8,-1,0
  4420.4     0.1       0  4725.0    0.16       0  4919.2    0.12       0
  4920.4     0.1       0  5001.1    0.07       0  5007.1     0.1       0
  5092.4    0.16       0  5176.1     0.1       0
Bank Sta=5001.1,5007.1
Exp/Cntr=0.3,0.1

Type RM Length L Ch R = 1,3261,475,475,475
BEGIN DESCRIPTION:
UNT 034 IN RACR 7.0
END DESCRIPTION:
XS GIS Cut Line= 3
      2282637.70     13230696.87      2282987.72     13230446.85
      2283287.74     13229996.83
#Sta/Elev= 30
  4546.1  170.65  4639.5  165.09  4798.8  158.60  4863.8  155.92  4876.7  155.47
  4882.8  154.50  4903.7  154.10  4962.7  154.09  4968.9  152.55  4979.2  152.34
  4983.7  146.57  5001.8  145.65  5004.5  145.15  5007.8  145.65  5012.3  146.67
  5019.8  150.31  5040.8  151.42  5055.9  150.99  5061.9  150.13  5106.9  153.22
  5111.5  151.05  5112.9  150.39  5134.0  152.57  5143.0  154.43  5149.0  156.83
  5257.2  160.89  5278.2  162.64  5336.8  165.45  5437.4  172.33  5517.1  178.72
#Mann=6,-1,0
  4546.1     0.1       0  4798.8    0.16       0  4863.8    0.12       0
  5001.8    0.07       0  5007.8    0.12       0  5111.5     0.1       0
Bank Sta=5001.8,5007.8
Exp/Cntr=0.3,0.1

Type RM Length L Ch R = 1,2786,427,427,427
BEGIN DESCRIPTION:
UNT 034 IN RACR 6.0
END DESCRIPTION:
XS GIS Cut Line= 4
      2282881.12     13230949.30      2283043.36     13230787.06
      2283559.51     13230590.43      2283692.25     13230546.18
#Sta/Elev= 30
  4476.9  169.81  4615.7  161.18  4681.3  155.83  4732.4  153.60  4858.4  154.47
  4923.2  152.21  4948.7  152.34  4967.8  151.06  4973.5  149.30  4978.8  145.78
  4989.2  143.73  4995.2  141.47  4998.0  140.97  5001.2  141.47  5021.3  143.77
  5033.7  147.99  5064.1  148.84  5074.8  152.43  5083.2  153.78  5088.5  152.63
  5096.2  159.59  5106.9  160.12  5113.3  161.43  5173.5  165.35  5198.2  168.21
  5214.0  168.09  5316.1  176.51  5353.0  178.00  5379.3  180.58  5398.6  180.89
#Mann=5,-1,0
  4476.9     0.1       0  4615.7    0.16       0  4923.2     0.1       0
  4995.2    0.07       0  5001.2     0.1       0
Bank Sta=4995.2,5001.2
Exp/Cntr=0.3,0.1

Type RM Length L Ch R = 1,2359,421,421,421
BEGIN DESCRIPTION:
UNT 034 IN RACR 5.0
END DESCRIPTION:
XS GIS Cut Line= 3
      2282905.71     13231077.08      2283584.08     13231052.50
      2283761.04     13230939.45
#Sta/Elev= 30
  4646.7  169.71  4678.7  169.45  4688.7  166.80  4708.7  166.83  4778.8  163.24
  4958.9  151.09  4968.9  149.66  4988.9  143.69  4995.9  137.91  4998.7  137.41
  5001.9  137.91  5008.9  138.94  5019.0  143.74  5029.0  143.94  5049.0  146.91
  5059.0  146.95  5065.6  148.37  5079.0  148.50  5099.0  151.69  5179.1  154.98
  5219.1  157.59  5289.1  163.01  5340.5  168.03  5382.8  169.42  5389.2  170.64
  5448.5  173.75  5455.6  175.13  5476.7  175.75  5519.7  179.92  5535.5  180.59
#Mann=3,-1,0
  4646.7     0.1       0  4995.9    0.07       0  5001.9     0.1       0
Bank Sta=4995.9,5001.9
Exp/Cntr=0.3,0.1

Type RM Length L Ch R = 1,1938,425,425,425
BEGIN DESCRIPTION:
UNT 034 IN RACR 4.0
END DESCRIPTION:
XS GIS Cut Line= 3
      2282718.58     13231373.52      2282926.37     13231392.16
      2283711.95     13231591.89
#Sta/Elev= 30
  4443.0  168.83  4531.9  162.45  4542.5  159.21  4582.7  158.99  4631.9  155.16
  4698.1  151.69  4731.9  150.76  4849.1  148.99  4889.5  149.84  4941.9  148.16
  4962.6  144.98  4971.4  142.00  5000.8  136.32  5003.6  135.82  5006.8  136.32
  5012.3  138.87  5024.5  148.00  5065.7  149.95  5076.1  148.90  5086.4  146.07
  5099.3  146.56  5127.7  151.47  5135.1  154.44  5148.3  155.82  5257.9  163.90
  5354.7  169.47  5395.9  174.20  5437.2  176.06  5447.5  178.59  5462.2  180.16
#Mann=7,-1,0
  4443.0     0.1       0  4631.9    0.08       0  4698.1     0.1       0
  4731.9    0.16       0  4849.1     0.1       0  5000.8    0.07       0
  5006.8     0.1       0
Bank Sta=5000.8,5006.8
Exp/Cntr=0.3,0.1

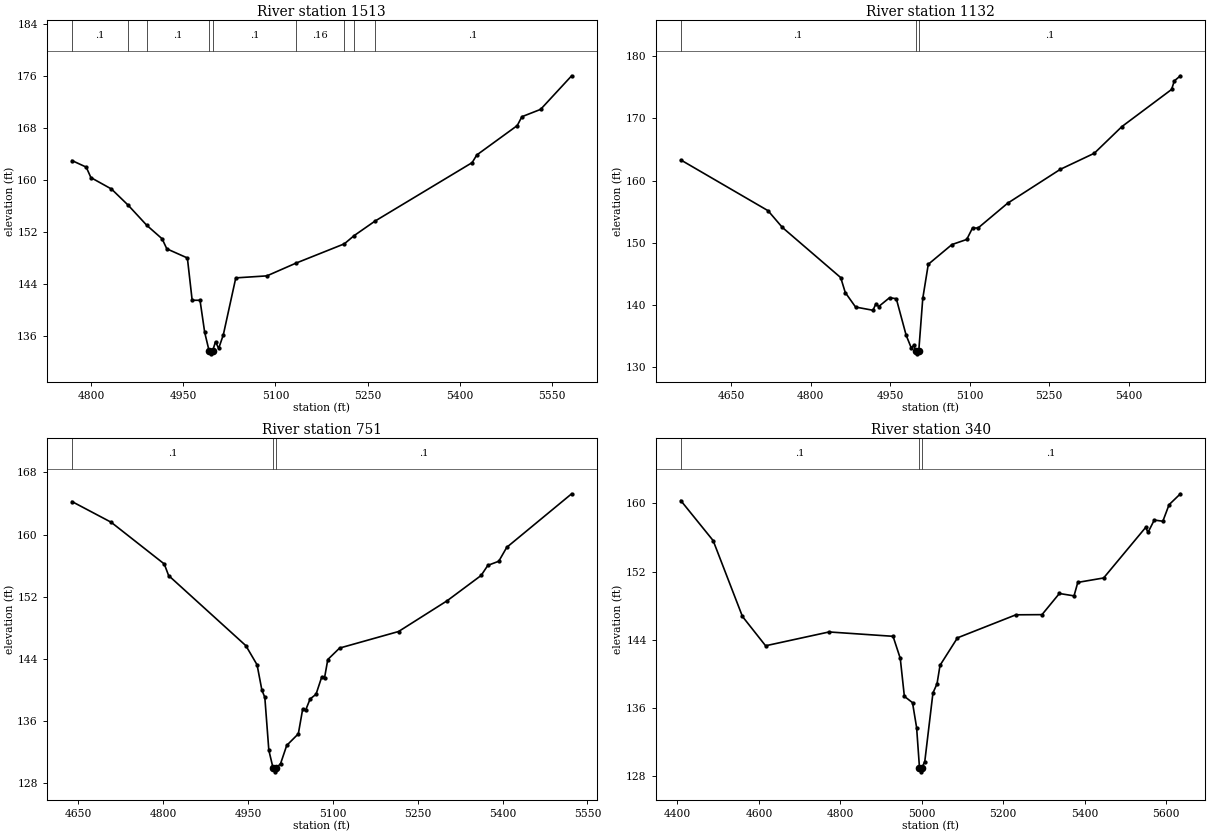
Type RM Length L Ch R = 1,1513,381,381,381
BEGIN DESCRIPTION:
UNT 034 IN RACR 3.0
END DESCRIPTION:
XS GIS Cut Line= 3
      2282837.71     13231896.86      2283037.72     13231846.85
      2283637.68     13231746.86
#Sta/Elev= 30
  4768.3  163.00  4791.5  161.99  4799.2  160.37  4832.7  158.61  4860.1  156.10
  4890.4  153.00  4915.2  150.94  4922.9  149.39  4956.4  147.98  4964.2  141.46
  4977.0  141.46  4984.6  136.52  4991.7  133.70  4994.5  133.20  4997.7  133.70
  5002.3  135.08  5007.4  134.03  5015.0  136.14  5035.3  144.91  5086.0  145.22
  5133.3  147.18  5212.2  150.16  5228.1  151.42  5262.1  153.66  5420.5  162.68
  5428.1  163.86  5494.0  168.39  5501.6  169.76  5532.1  170.89  5582.7  176.07
#Mann=9,-1,0
  4768.3     0.1       0  4860.1    0.16       0  4890.4     0.1       0
  4991.7    0.07       0  4997.7     0.1       0  5133.3    0.16       0
  5212.2     0.1       0  5228.1    0.16       0  5262.1     0.1       0
Bank Sta=4991.7,4997.7
Exp/Cntr=0.3,0.1

Type RM Length L Ch R = 1,1132,381,381,381
BEGIN DESCRIPTION:
UNT 034 IN RACR 2.0
END DESCRIPTION:
XS GIS Cut Line= 3
      2282833.09     13232119.36      2283008.94     13232116.69
      2283743.44     13231898.47
#Sta/Elev= 30
  4555.2  163.32  4719.8  155.16  4746.7  152.48  4856.8  144.41  4865.4  142.01
  4884.8  139.68  4917.6  139.16  4923.2  140.21  4928.4  139.76  4948.9  141.18
  4961.6  141.02  4980.2  135.14  4989.6  133.16  4994.8  133.51  4998.0  132.66
  5000.8  132.16  5004.0  132.66  5011.5  141.06  5021.9  146.55  5066.5  149.72
  5094.4  150.54  5105.3  152.38  5115.8  152.38  5171.3  156.35  5270.9  161.81
  5334.9  164.39  5387.0  168.68  5480.6  174.64  5485.8  176.02  5497.3  176.84
#Mann=3,-1,0
  4555.2     0.1       0  4998.0    0.07       0  5004.0     0.1       0
Bank Sta=4998,5004
Exp/Cntr=0.3,0.1

Type RM Length L Ch R = 1,751,411,411,411
BEGIN DESCRIPTION:
Mapping XS dbfaf2db
END DESCRIPTION:
XS GIS Cut Line= 3
      2282968.97     13232391.05      2283110.16     13232407.04
      2283821.34     13232199.28
#Sta/Elev= 30
  4639.0  164.26  4708.2  161.60  4802.1  156.23  4809.8  154.74  4946.3  145.72
  4966.1  143.26  4974.6  140.01  4979.8  139.07  4986.9  132.27  4994.3  129.99
  4997.1  129.49  5000.3  129.99  5007.7  130.56  5018.5  132.89  5039.0  134.38
  5046.7  137.56  5051.9  137.42  5059.8  138.86  5070.3  139.47  5080.2  141.66
  5085.4  141.61  5091.1  143.94  5111.9  145.41  5216.1  147.54  5301.8  151.49
  5362.0  154.75  5373.9  156.05  5393.2  156.58  5407.3  158.37  5522.0  165.26
#Mann=3,-1,0
  4639.0     0.1       0  4994.3    0.07       0  5000.3     0.1       0
Bank Sta=4994.3,5000.3
Exp/Cntr=0.3,0.1

Type RM Length L Ch R = 1,340,0,0,0
BEGIN DESCRIPTION:
UNT 034 IN RACR 1.0
END DESCRIPTION:
XS GIS Cut Line= 5
      2282969.02     13232505.61      2283160.78     13232636.12
      2283395.18     13232705.37      2283714.83     13232678.74
      2283946.58     13232316.45
#Sta/Elev= 30
  4408.1  160.34  4487.7  155.64  4559.6  146.75  4616.5  143.31  4772.4  144.93
  4929.5  144.42  4947.2  141.84  4957.3  137.38  4977.3  136.64  4987.4  133.71
  4994.4  129.03  4997.2  128.53  5000.4  129.03  5007.4  129.72  5027.5  137.78
  5037.5  138.85  5044.9  141.02  5087.7  144.24  5231.2  146.94  5295.3  146.96
  5338.0  149.44  5374.0  149.16  5383.2  150.74  5446.7  151.26  5549.8  157.18
  5555.8  156.61  5571.0  158.05  5592.1  157.91  5607.4  159.85  5635.3  161.13
#Mann=3,-1,0
  4408.1     0.1       0  4994.4    0.07       0  5000.4     0.1       0
Bank Sta=4994.4,5000.4
Exp/Cntr=0.3,0.1

Chan Stop Cuts=-1