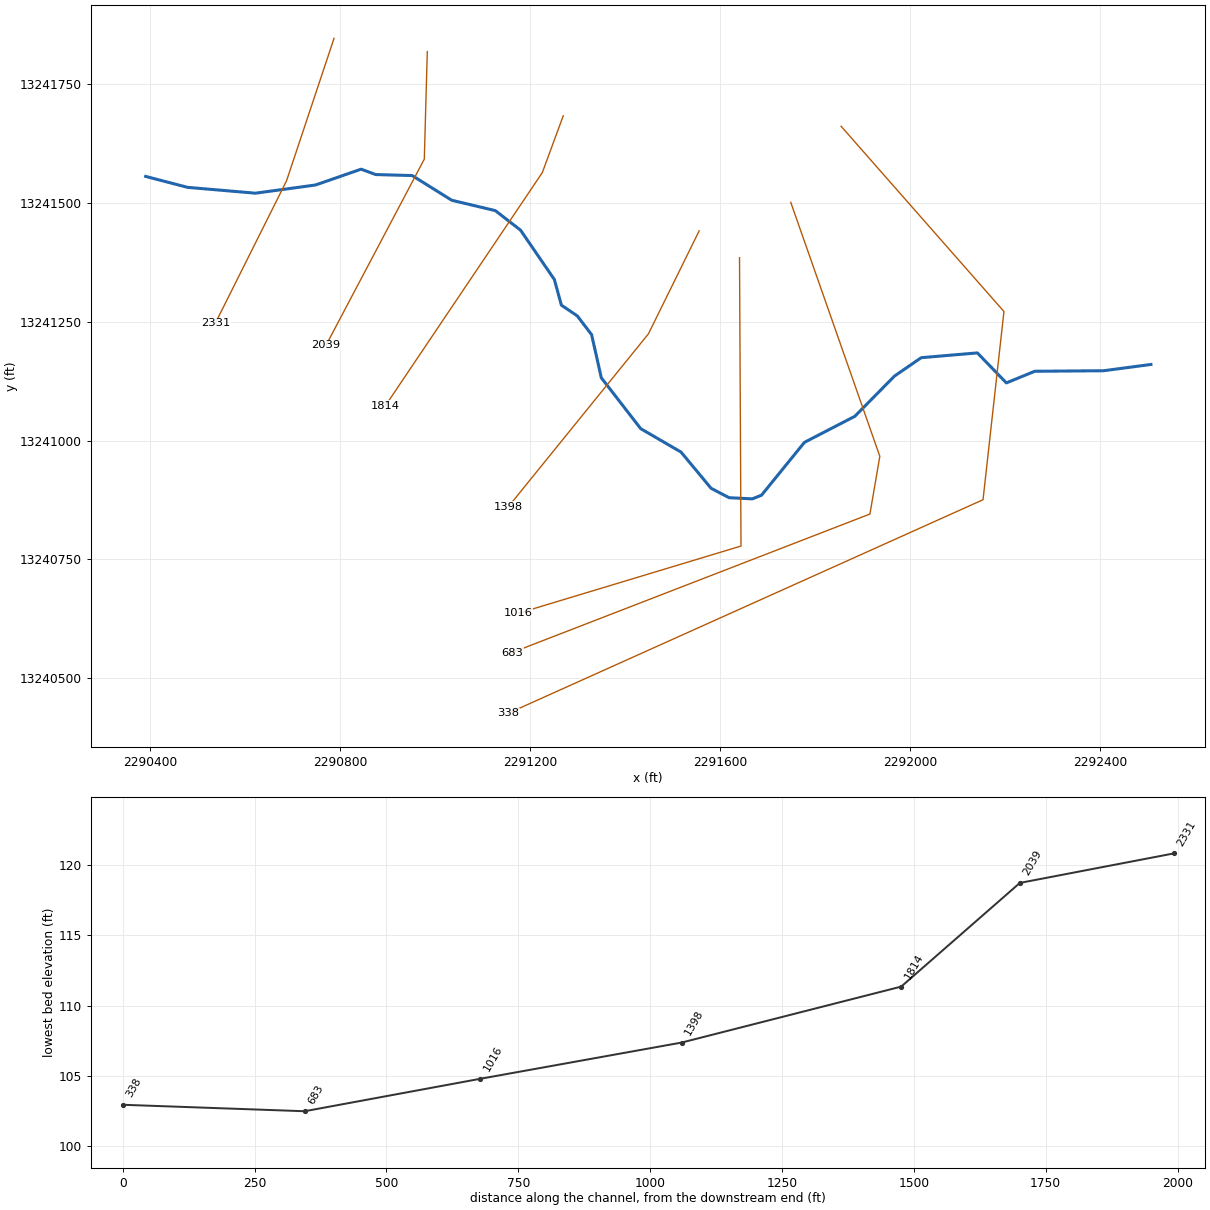
--- UNT 036 IN RACR.prj (project) ---

Proj Title=UNT 036 IN RACR Base Level Engineering
Current Plan=p01
Default Exp/Contr=0.3,0.1
English Units
Geom File=g01
Flow File=f01
Plan File=p01
BEGIN DESCRIPTION:
UNT 036 IN RACR
END DESCRIPTION:

--- UNT 036 IN RACR.p01 (plan) ---

Plan Title=Multiple Run
Short Identifier=Multiple
Geom File=g01
Flow File=f01
Subcritical Flow
K Sum by GR= 0
Std Step Tol= 0.01
Critical Tol= 0.01
Num of Std Step Trials= 20
Max Error Tol= 0.3
Flow Tol Ratio= 0.001
Split Flow NTrial= 30
Split Flow Tol= 0.02
Split Flow Ratio= 0.02
Log Output Level= 0
Friction Slope Method= 1
Unsteady Friction Slope Method= 2
Unsteady Bridges Friction Slope Method= 1
Parabolic Critical Depth
Global Vel Dist=  1 , 1 , 1
Global Log Level= 0
CheckData=True
Encroach Param= -1, 0, 0, 0
BEGIN DESCRIPTION:
Multiple Run
END DESCRIPTION:

--- UNT 036 IN RACR.f01 (steady flow) ---

Flow Title=Multiple
Number of Profiles=7
Profile Names=10-year,25-year,50-year,1pct_min,100-year,1pct_plu,500-year
River Rch & RM= UNT 036 IN RACR,Reach-1,2331
     263     365     450     408     552     746     839
Boundary for River Rch & Prof#=UNT 036 IN RACR,Reach-1,1
Up Type=0
Dn Type=3
Dn Slope=0.005
Boundary for River Rch & Prof#=UNT 036 IN RACR,Reach-1,2
Up Type=0
Dn Type=3
Dn Slope=0.005
Boundary for River Rch & Prof#=UNT 036 IN RACR,Reach-1,3
Up Type=0
Dn Type=3
Dn Slope=0.005
Boundary for River Rch & Prof#=UNT 036 IN RACR,Reach-1,4
Up Type=0
Dn Type=3
Dn Slope=0.005
Boundary for River Rch & Prof#=UNT 036 IN RACR,Reach-1,5
Up Type=0
Dn Type=3
Dn Slope=0.005
Boundary for River Rch & Prof#=UNT 036 IN RACR,Reach-1,6
Up Type=0
Dn Type=3
Dn Slope=0.005
Boundary for River Rch & Prof#=UNT 036 IN RACR,Reach-1,7
Up Type=0
Dn Type=3
Dn Slope=0.005

--- UNT 036 IN RACR.g01 (geometry) ---

Geom Title=Existing Conditions

River Reach=UNT 036 IN RACR,Reach-1
Reach XY= 30
      2290391.11     13241556.10      2290479.43     13241533.07
      2290622.28     13241520.78      2290748.72     13241538.04
      2290844.82     13241571.37      2290875.33     13241560.04
      2290952.31     13241557.92      2291035.61     13241505.90
      2291127.32     13241484.08      2291180.39     13241443.02
      2291251.61     13241339.11      2291266.45     13241284.97
      2291299.95     13241262.42      2291330.09     13241222.87
      2291350.52     13241132.07      2291433.49     13241024.97
      2291518.46     13240975.61      2291581.56     13240899.46
      2291619.58     13240879.59      2291668.39     13240877.22
      2291687.80     13240884.89      2291778.21     13240996.17
      2291884.25     13241050.98      2291967.89     13241135.81
      2292024.05     13241174.42      2292142.28     13241184.52
      2292203.33     13241121.34      2292263.22     13241145.85
      2292407.98     13241146.95      2292507.72     13241160.18

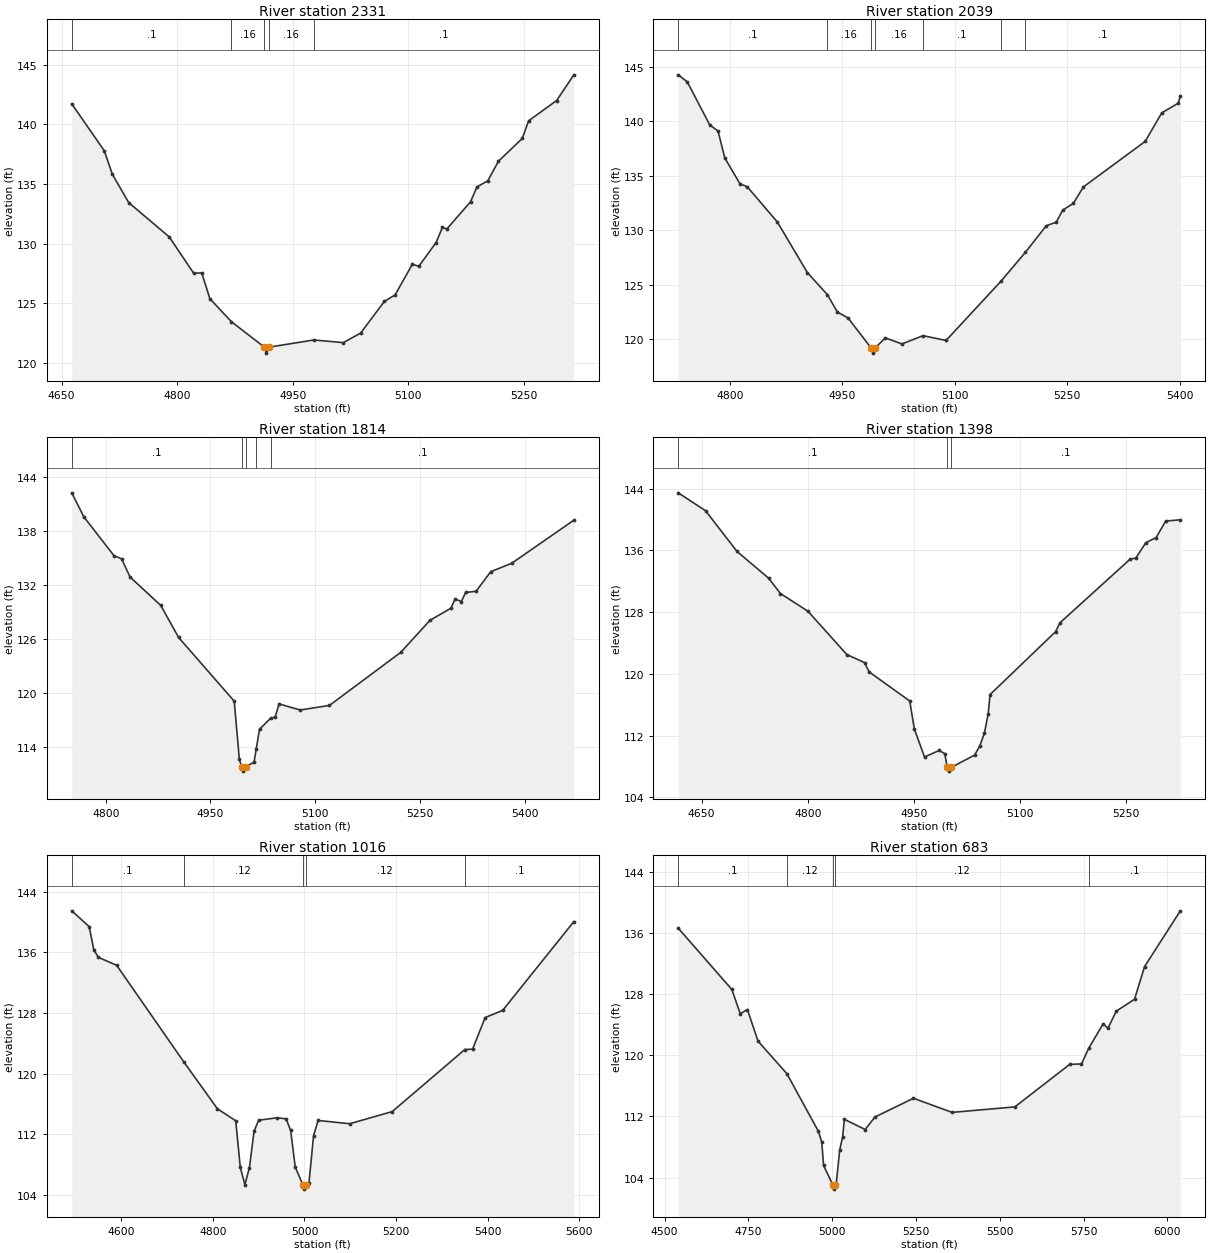
Type RM Length L Ch R = 1,2331,292,292,292
BEGIN DESCRIPTION:
UNT 036 IN RACR 5.0
END DESCRIPTION:
XS GIS Cut Line= 3
      2290787.72     13241846.85      2290687.72     13241546.85
      2290537.74     13241246.89
#Sta/Elev= 30
  4663.2  141.71  4705.4  137.78  4715.9  135.81  4737.0  133.45  4789.7  130.57
  4821.3  127.54  4831.9  127.55  4842.4  125.40  4870.4  123.47  4913.2  121.34
  4915.9  120.84  4919.2  121.34  4977.2  121.94  5015.8  121.72  5038.1  122.52
  5068.9  125.17  5082.8  125.71  5105.2  128.28  5113.6  128.11  5136.0  130.10
  5144.3  131.37  5149.9  131.23  5180.7  133.51  5189.1  134.76  5203.0  135.26
  5217.0  136.91  5247.8  138.81  5256.1  140.29  5292.5  141.99  5314.8  144.14
#Mann=5,-1,0
  4663.2     0.1       0  4870.4    0.16       0  4913.2    0.07       0
  4919.2    0.16       0  4977.2     0.1       0
Bank Sta=4913.2,4919.2
Exp/Cntr=0.3,0.1

Type RM Length L Ch R = 1,2039,225,225,225
BEGIN DESCRIPTION:
Mapping XS 041021a6
END DESCRIPTION:
XS GIS Cut Line= 3
      2290984.09     13241818.98      2290977.79     13241592.51
      2290770.84     13241200.55
#Sta/Elev= 30
  4730.9  144.25  4743.0  143.60  4773.0  139.65  4784.0  139.10  4793.0  136.63
  4813.1  134.28  4823.1  133.98  4863.1  130.76  4903.1  126.13  4930.0  124.09
  4943.1  122.51  4957.5  121.96  4987.9  119.24  4990.7  118.74  4993.9  119.24
  5007.3  120.14  5029.3  119.58  5057.5  120.34  5088.2  119.90  5161.4  125.33
  5193.9  127.97  5221.8  130.41  5235.3  130.75  5243.8  131.85  5257.9  132.46
  5271.5  133.98  5353.9  138.15  5375.9  140.76  5397.9  141.65  5400.7  142.32
#Mann=7,-1,0
  4730.9     0.1       0  4930.0    0.16       0  4987.9    0.07       0
  4993.9    0.16       0  5057.5     0.1       0  5161.4    0.16       0
  5193.9     0.1       0
Bank Sta=4987.9,4993.9
Exp/Cntr=0.3,0.1

Type RM Length L Ch R = 1,1814,416,416,416
BEGIN DESCRIPTION:
UNT 036 IN RACR 4.0
END DESCRIPTION:
XS GIS Cut Line= 3
      2291270.32     13241683.70      2291226.29     13241564.20
      2290896.04     13241073.54
#Sta/Elev= 30
  4751.4  142.28  4768.7  139.61  4812.0  135.28  4822.6  134.96  4834.9  132.92
  4878.7  129.78  4904.4  126.21  4984.0  119.13  4991.3  112.69  4994.4  111.86
  4997.1  111.36  5000.4  111.86  5012.3  112.34  5015.5  113.83  5020.2  116.01
  5036.6  117.28  5042.3  117.33  5048.3  118.83  5078.3  118.15  5120.3  118.66
  5222.3  124.55  5264.3  128.12  5294.2  129.46  5300.3  130.49  5309.2  130.20
  5315.2  131.21  5330.2  131.34  5351.2  133.52  5381.2  134.45  5470.2  139.24
#Mann=5,-1,0
  4751.4     0.1       0  4994.4    0.07       0  5000.4     0.1       0
  5015.5    0.16       0  5036.6     0.1       0
Bank Sta=4994.4,5000.4
Exp/Cntr=0.3,0.1

Type RM Length L Ch R = 1,1398,382,382,382
BEGIN DESCRIPTION:
UNT 036 IN RACR 3.0
END DESCRIPTION:
XS GIS Cut Line= 3
      2291556.56     13241441.51      2291449.62     13241224.49
      2291154.88     13240860.76
#Sta/Elev= 30
  4616.9  143.48  4655.5  141.16  4700.1  135.87  4744.7  132.41  4761.4  130.42
  4800.5  128.11  4855.3  122.50  4880.4  121.46  4886.8  120.26  4944.3  116.48
  4950.8  112.86  4965.2  109.22  4986.0  110.06  4993.9  109.64  4997.3  107.88
  5000.1  107.38  5003.3  107.88  5036.0  109.45  5043.5  110.67  5049.9  112.31
  5055.3  114.81  5057.9  117.31  5150.6  125.47  5157.0  126.64  5256.1  134.88
  5264.1  135.02  5278.4  137.03  5292.8  137.67  5306.3  139.82  5327.0  139.98
#Mann=3,-1,0
  4616.9     0.1       0  4997.3    0.07       0  5003.3     0.1       0
Bank Sta=4997.3,5003.3
Exp/Cntr=0.3,0.1

Type RM Length L Ch R = 1,1016,333,333,333
BEGIN DESCRIPTION:
UNT 036 IN RACR 2.0
END DESCRIPTION:
XS GIS Cut Line= 3
      2291641.50     13241384.93      2291644.64     13240777.82
      2291175.97     13240636.28
#Sta/Elev= 30
  4491.7  141.48  4529.8  139.39  4539.8  136.35  4549.8  135.35  4589.8  134.30
  4735.8  121.62  4809.8  115.39  4849.8  113.81  4859.8  107.69  4869.8  105.38
  4879.8  107.65  4889.8  112.41  4899.8  113.88  4939.8  114.20  4959.8  114.07
  4969.8  112.54  4979.8  107.72  4996.8  105.30  4999.5  104.80  5002.8  105.30
  5009.8  105.59  5019.8  111.82  5029.8  113.85  5098.8  113.42  5191.7  115.02
  5350.3  123.20  5367.2  123.25  5394.7  127.41  5432.9  128.36  5588.4  140.06
#Mann=5,-1,0
  4491.7     0.1       0  4735.8    0.12       0  4996.8    0.07       0
  5002.8    0.12       0  5350.3     0.1       0
Bank Sta=4996.8,5002.8
Exp/Cntr=0.3,0.1

Type RM Length L Ch R = 1,683,345,345,345
BEGIN DESCRIPTION:
Mapping XS 6ded7f2d
END DESCRIPTION:
XS GIS Cut Line= 4
      2291749.39     13241501.52      2291936.90     13240966.77
      2291916.06     13240845.24      2291162.61     13240553.58
#Sta/Elev= 30
  4540.9  136.63  4700.8  128.61  4726.0  125.43  4747.2  125.99  4779.0  121.85
  4865.1  117.59  4959.1  110.05  4969.2  108.62  4974.5  105.59  5002.5  102.99
  5005.3  102.49  5008.5  102.99  5012.1  103.13  5022.7  107.63  5031.3  109.30
  5036.6  111.62  5098.6  110.29  5127.5  111.92  5242.7  114.38  5357.8  112.53
  5545.2  113.25  5708.7  118.81  5744.0  118.87  5765.7  120.93  5808.1  124.09
  5823.1  123.55  5847.7  125.77  5902.2  127.33  5932.1  131.60  6038.8  138.90
#Mann=5,-1,0
  4540.9     0.1       0  4865.1    0.12       0  5002.5    0.07       0
  5008.5    0.12       0  5765.7     0.1       0
Bank Sta=5002.5,5008.5
Exp/Cntr=0.3,0.1

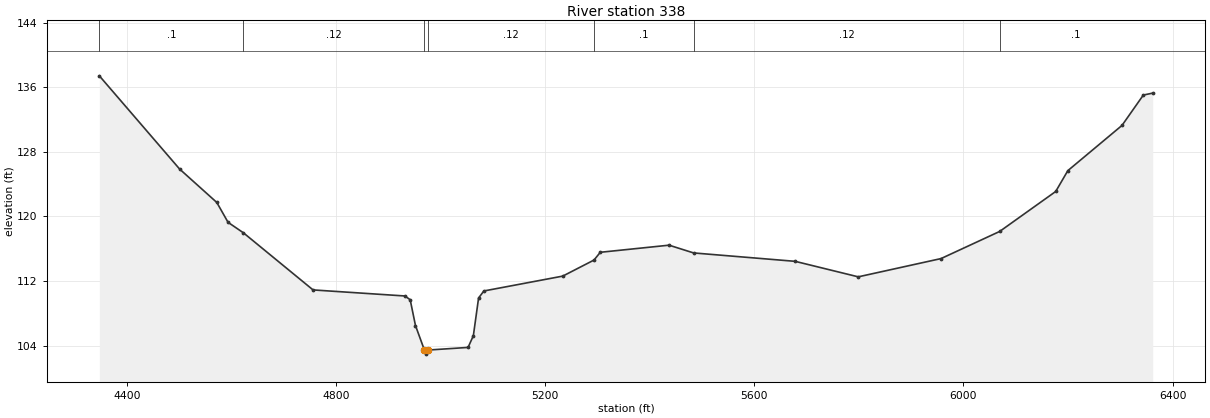
Type RM Length L Ch R = 1,338,0,0,0
BEGIN DESCRIPTION:
UNT 036 IN RACR 1.0
END DESCRIPTION:
XS GIS Cut Line= 4
      2291855.36     13241661.75      2292198.25     13241271.67
      2292154.22     13240875.33      2291153.93     13240425.52
#Sta/Elev= 30
  4347.1  137.41  4500.6  125.87  4571.8  121.73  4593.3  119.27  4622.7  117.97
  4755.9  110.90  4931.7  110.15  4941.7  109.68  4951.8  106.49  4968.9  103.45
  4971.7  102.95  4974.9  103.45  5052.4  103.78  5062.5  105.23  5072.5  109.90
  5082.6  110.77  5233.5  112.61  5293.3  114.60  5305.3  115.56  5436.8  116.44
  5483.8  115.48  5678.0  114.44  5798.7  112.52  5957.0  114.78  6069.2  118.14
  6176.4  123.09  6199.6  125.67  6303.2  131.27  6344.0  135.03  6362.0  135.27
#Mann=7,-1,0
  4347.1     0.1       0  4622.7    0.12       0  4968.9    0.07       0
  4974.9    0.12       0  5293.3     0.1       0  5483.8    0.12       0
  6069.2     0.1       0
Bank Sta=4968.9,4974.9
Exp/Cntr=0.3,0.1

Chan Stop Cuts=-1