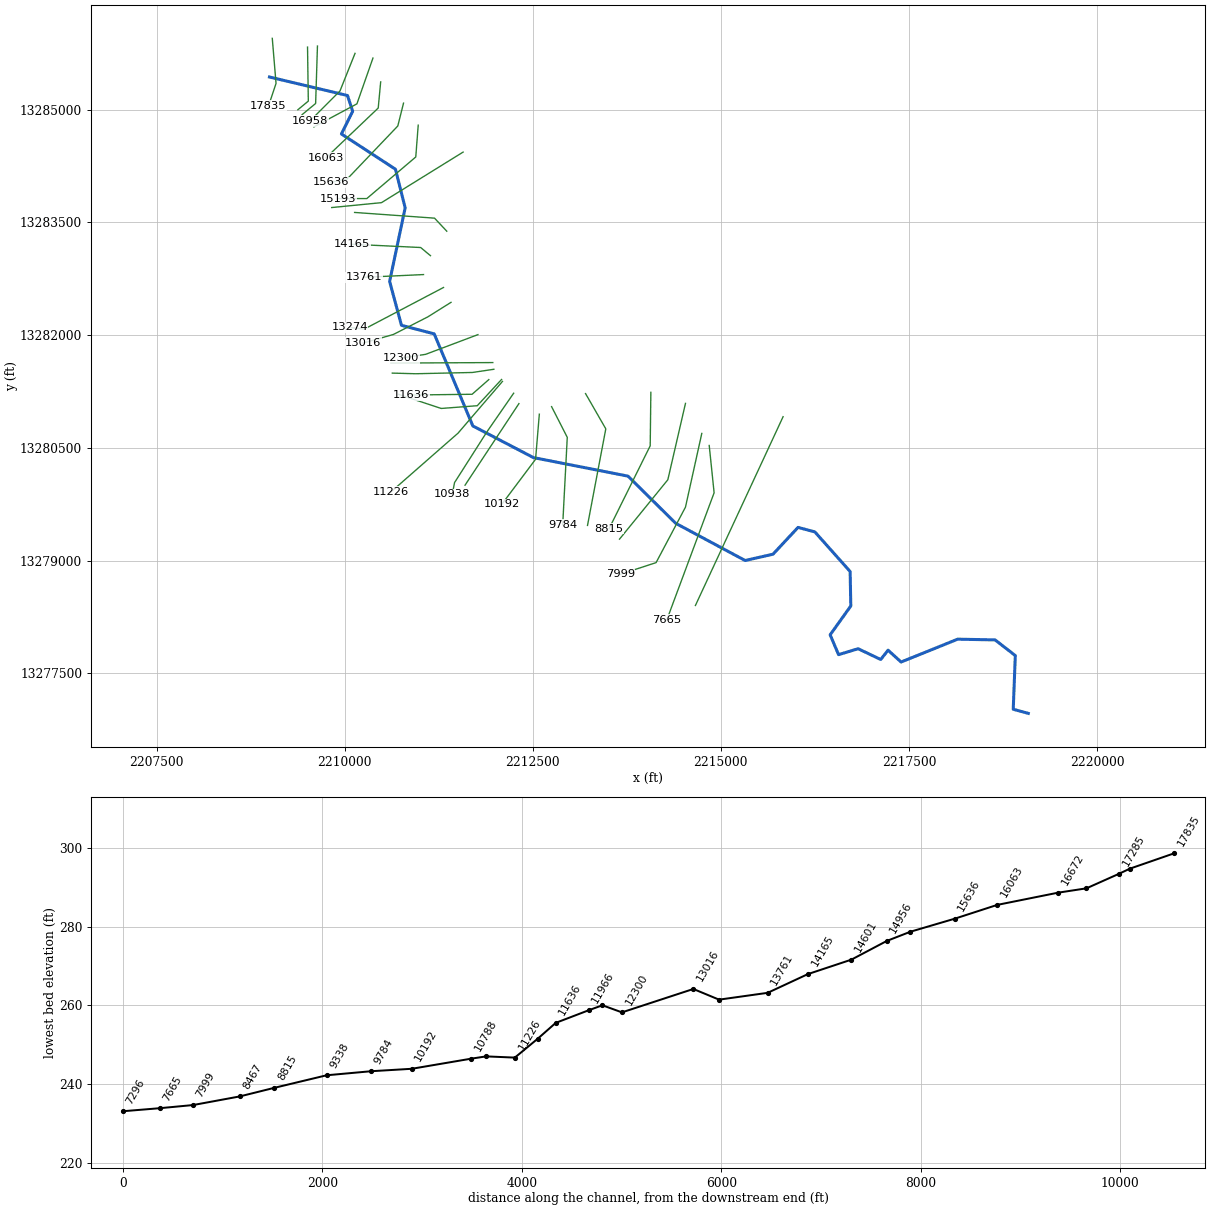
--- HACKBERRY CREEK.prj (project) ---

Proj Title=HACKBERRY CREEK Base Level Engineering
Current Plan=p01
Default Exp/Contr=0.3,0.1
English Units
Geom File=g01
Flow File=f01
Plan File=p01
Y Axis Title=Elevation
X Axis Title(PF)=Main Channel Distance
X Axis Title(XS)=Station
BEGIN DESCRIPTION:
HACKBERRY CREEK
END DESCRIPTION:
DSS File=dss
DSS Export Rating Curves= 0
DSS Export Rating Curve Sorted= 0
DSS Export Volume Flow Curves= 0
DXF OffsetX= 0
DXF OffsetY= 0
DXF ScaleX= 1
DXF ScaleY= 10

--- HACKBERRY CREEK.p01 (plan) ---

Plan Title=Multiple Run
Program Version=4.10
Short Identifier=Multiple Run
Geom File=g01
Flow File=f01
Subcritical Flow
K Sum by GR= 0
Std Step Tol= 0.01
Critical Tol= 0.01
Num of Std Step Trials= 20
Max Error Tol= 0.3
Flow Tol Ratio= 0.001
Split Flow NTrial= 30
Split Flow Tol= 0.02
Split Flow Ratio= 0.02
Log Output Level= 0
Friction Slope Method= 1
Unsteady Friction Slope Method= 2
Unsteady Bridges Friction Slope Method= 1
Parabolic Critical Depth
Global Vel Dist= 1 , 1 , 1
Global Log Level= 0
CheckData=True
Encroach Param=-1 ,0,0, 0
BEGIN DESCRIPTION:
Multiple Run
END DESCRIPTION:
Computation Interval=1HOUR
Output Interval=1HOUR
Run HTab= 0
Run UNet= 0
Run PostProcess= 0
Run WQNet= 0
UNET Theta= 1
UNET Theta Warmup= 1
UNET ZTol= 0.02
UNET ZSATol= 0.05
UNET MxIter= 20
UNET MaxInSteps= 0
UNET DtIC= 0
UNET DtMin= 0
UNET MaxCRTS= 20
UNET WFStab= 2
UNET SFStab= 1
UNET WFX= 1
UNET SFX= 1
UNET DSS MLevel= 4
UNET DZMax Abort= 100
UNET Convert EG Bridges= 0
UNET Use Existing IB Tables=-1
UNET Froude Reduction=False
UNET Froude Limit= 1
UNET Froude Power= 10
UNET Time Slicing=0,0, 5
UNET Junction Losses=0
Instantaneous Interval=1HOUR
DSS File=dss
Write IC File= 0
Write IC File at Sim End=0
Echo Input=False
Echo Parameters=False
Echo Output=False
Write Detailed= 0
WQ AD Non Conservative
WQ ULTIMATE=-1
WQ Max Comp Step=1HOUR
WQ Output Interval=15MIN
WQ Output Selected Increments= 0
WQ Output face flow=0
WQ Output face velocity=0
WQ Output face area=0
WQ Output face dispersion=0
WQ Output cell volume=0
WQ Output cell surface area=0
WQ Output cell continuity=0
WQ Output cumulative cell continuity=0
WQ Output face conc=0
WQ Output face dconc_dx=0
WQ Output face courant=0
WQ Output face peclet=0
WQ Output face adv mass=0
WQ Output face disp mass=0
WQ Output cell mass=0
WQ Output cell source sink temp=0
WQ Output cell source sink nsm=0
WQ Output MaxMinRange=-1
WQ Daily Max Min Mean=-1
WQ Daily Range=0
WQ Daily Time=0
WQ Create Restart=0
WQ Fixed Restart=0
WQ System Summary=0
WQ Use Fixed Temperature=0
Sorting and Armoring Iterations= 10
XS Update Threshold= 0.02
Hydraulics Update Threshold= 0.02
Energy Slope Method= 1
Volume Change Method= 0
XS Weighting Method= 0
Number of US Weighted Cross Sections= 1
Number of DS Weighted Cross Sections= 1
Upstream XS Weight=0.25
Main XS Weight=0.5
Downstream XS Weight=0.25
Number of DS XS's Weighted with US Boundary= 1
Upstream Boundary Weight= 1
Weight of XSs Associated with US Boundary= 0
Number of US XS's Weighted with DS Boundary= 1
Downstream Boundary Weight= 0.5
Weight of XSs Associated with DS Boundary= 0.5
Sediment Output Level= 4
Mass or Volume Output= 0
Output Increment Type= 1
Profile and TS Output Increment= 10
XS Output Flag= 0
XS Output Increment= 10
Disregard all LS=0
Disregard all Conn=0
Disregard all Breaches=0
Disregard all Pumps=0

--- HACKBERRY CREEK.f01 (steady flow) ---

Flow Title=Multiple
Program Version=4.10
Number of Profiles= 7
Profile Names=10-year,25-year,50-year,1pct_min,100-year,1pct_plu,500-year
River Rch & RM=HACKBERRY CREEK,Reach-1         ,17835
     197     272     335     303     410     554     625
River Rch & RM=HACKBERRY CREEK,Reach-1         ,17285
     257     360     447     408     552     746     855
River Rch & RM=HACKBERRY CREEK,Reach-1         ,11226
     750    1098    1402    1312    1774    2399    2890
River Rch & RM=HACKBERRY CREEK,Reach-1         ,7296
     892    1312    1680    1575    2130    2881    3484
River Rch & RM=HACKBERRY CREEK,Reach-1         ,5766
     892    1312    1680    1575    2130    2881    3484
River Rch & RM=HACKBERRY CREEK,Reach-1         ,319
     935    1377    1765    1658    2242    3031    3673
Boundary for River Rch & Prof#=HACKBERRY CREEK,Reach-1         , 1
Up Type= 0
Dn Type= 3
Dn Slope=0.005
Boundary for River Rch & Prof#=HACKBERRY CREEK,Reach-1         , 2
Up Type= 0
Dn Type= 3
Dn Slope=0.005
Boundary for River Rch & Prof#=HACKBERRY CREEK,Reach-1         , 3
Up Type= 0
Dn Type= 3
Dn Slope=0.005
Boundary for River Rch & Prof#=HACKBERRY CREEK,Reach-1         , 4
Up Type= 0
Dn Type= 3
Dn Slope=0.005
Boundary for River Rch & Prof#=HACKBERRY CREEK,Reach-1         , 5
Up Type= 0
Dn Type= 3
Dn Slope=0.005
Boundary for River Rch & Prof#=HACKBERRY CREEK,Reach-1         , 6
Up Type= 0
Dn Type= 3
Dn Slope=0.005
Boundary for River Rch & Prof#=HACKBERRY CREEK,Reach-1         , 7
Up Type= 0
Dn Type= 3
Dn Slope=0.005
DSS Import GetInterval= 0
DSS Import GetPeak= 0
DSS Import FillOption= 0

--- HACKBERRY CREEK.g01 (geometry) ---

Geom Title=Existing Conditions
Program Version=4.10

River Reach=HACKBERRY CREEK ,Reach-1
Reach XY= 30
      2209000.34     13285432.35      2210037.67     13285186.22
      2210106.86      13284977.1      2209956.47     13284674.67
      2210675.17      13284205.8      2210804.24     13283691.62
      2210597.83       13282713.      2210755.09     13282129.08
      2211190.41     13282015.37      2211703.38     13280790.87
      2212508.87     13280369.64      2213765.81     13280123.07
      2214401.08      13279494.9      2215323.48     13279000.46
      2215694.07     13279084.29      2216026.43     13279440.74
      2216250.04     13279381.08      2216719.14     13278853.89
      2216728.17     13278395.89      2216453.51     13278011.87
      2216565.49     13277747.98      2216825.04     13277826.98
      2217125.39     13277683.75      2217223.48     13277807.01
      2217396.44     13277650.11      2218148.91     13277953.98
      2218646.55     13277944.03       2218914.8     13277735.78
      2218887.24     13277021.48      2219087.72     13276966.86

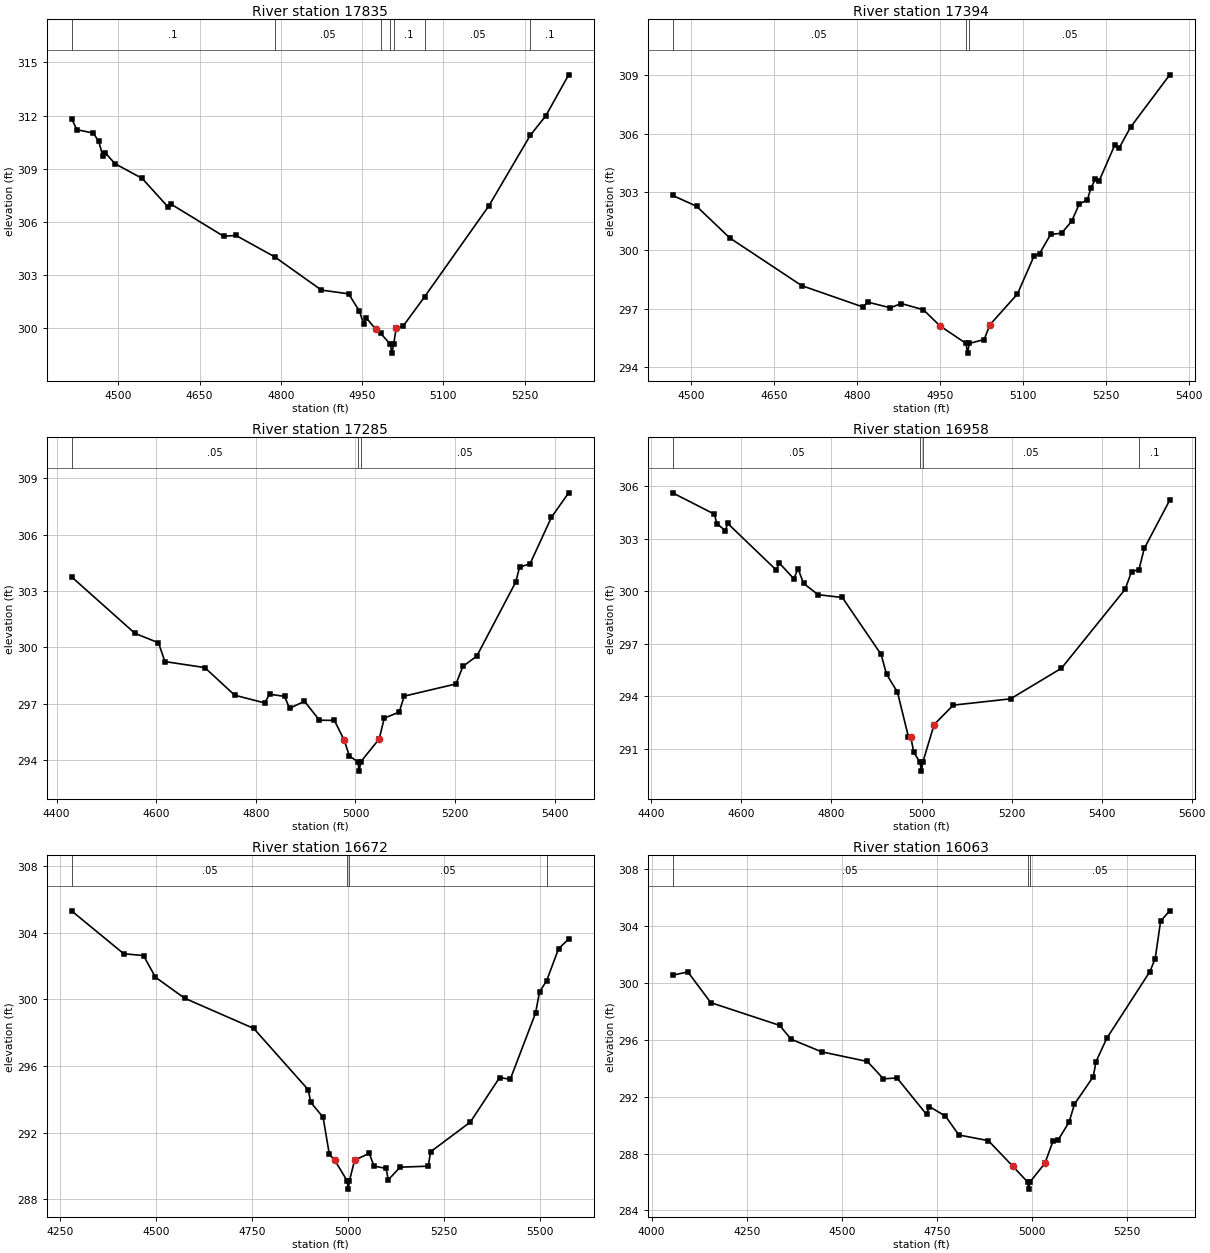
Type RM Length L Ch R = 1 ,17835   ,441,441,441
BEGIN DESCRIPTION:
HACKBERRY CREEK 31.0
END DESCRIPTION:
XS GIS Cut Line= 3
      2209037.72     13285946.86      2209087.72     13285346.85
      2208987.72     13285046.86
#Sta/Elev= 30
  4413.3  311.83  4423.3   311.2  4453.4  311.01  4463.5  310.54    4471  309.73
    4476  309.88  4493.6  309.28  4543.8  308.45  4591.4  306.84  4596.4  307.01
  4694.3  305.18  4716.9  305.23  4788.5  304.02  4874.9  302.14  4925.1  301.93
  4945.1  300.95  4952.7  300.24  4957.7  300.57  4975.2  299.93  4984.4  299.69
  5002.3  299.08  5005.1  298.58  5008.3  299.08  5012.9  299.98  5025.9  300.11
  5065.4  301.76    5184  306.89  5260.6  310.88  5289.4  311.99  5331.6   314.3
#Mann= 7 ,-1 , 0
  4413.3      .1       0  4788.5     .05       0  4984.4      .1       0
  5002.3     .07       0  5008.3      .1       0  5065.4     .05       0
  5260.6      .1       0
Bank Sta=4975.2,5012.9
XS Rating Curve= 0 ,0
Exp/Cntr=0.3,0.1

Type RM Length L Ch R = 1 ,17394   ,109,109,109
BEGIN DESCRIPTION:
HACKBERRY CREEK 30.0
END DESCRIPTION:
XS GIS Cut Line= 3
      2209506.39     13285830.33      2209516.81     13285111.59
      2209377.89     13284996.99
#Sta/Elev= 30
    4467  302.82  4510.5  302.26  4570.5  300.63  4700.5  298.18  4810.5  297.09
  4820.5  297.33  4860.5  297.04  4880.5  297.26  4920.5  296.94  4950.5  296.11
  4997.5  295.21  5000.3  294.71  5003.5  295.21  5030.5  295.41  5040.5  296.16
  5090.5  297.75  5120.5   299.7  5130.5  299.83  5150.5  300.81  5170.5  300.88
  5188.5  301.49  5202.6  302.39  5216.9  302.58  5223.5  303.21  5231.3  303.65
  5237.8  303.54  5266.4   305.4  5274.3  305.25  5295.1  306.33  5365.9  309.02
#Mann= 3 ,-1 , 0
    4467     .05       0  4997.5     .03       0  5003.5     .05       0
Bank Sta=4950.5,5040.5
XS Rating Curve= 0 ,0
Exp/Cntr=0.3,0.1

Type RM Length L Ch R = 1 ,17285   ,327,327,327
BEGIN DESCRIPTION:
Mapping XS f0c53c88
END DESCRIPTION:
XS GIS Cut Line= 3
      2209638.33     13285844.23      2209614.03     13285080.34
      2209433.99     13284931.46
#Sta/Elev= 30
  4430.1  303.75  4557.5  300.74  4604.6  300.24  4617.6  299.24  4697.6  298.92
  4757.6  297.45  4817.7  297.04  4827.7   297.5  4857.7  297.39  4867.7  296.75
  4897.7  297.13  4927.7  296.12  4957.7  296.11  4977.8  295.04  4987.8  294.21
  5004.8  293.91  5007.5  293.41  5010.8  293.91  5047.8  295.13  5057.8  296.23
  5087.8  296.55  5097.8   297.4  5201.9  298.05  5215.5  298.98  5243.5  299.53
  5321.7  303.47  5329.5  304.27  5350.4  304.44  5393.4  306.92    5428  308.22
#Mann= 3 ,-1 , 0
  4430.1     .05       0  5004.8     .03       0  5010.8     .05       0
Bank Sta=4977.8,5047.8
XS Rating Curve= 0 ,0
Exp/Cntr=0.3,0.1

Type RM Length L Ch R = 1 ,16958   ,286,286,286
BEGIN DESCRIPTION:
HACKBERRY CREEK 29.0
END DESCRIPTION:
XS GIS Cut Line= 3
      2210137.72     13285746.86      2209937.72     13285246.85
      2209537.73     13284846.86
#Sta/Elev= 30
  4447.1  305.61    4540  304.39  4545.4  303.85  4564.2  303.45  4569.6  303.86
  4677.3   301.2  4684.1   301.6  4716.4   300.7  4725.8  301.28  4737.9  300.44
  4770.2  299.79  4824.1  299.63  4910.2  296.38  4922.3  295.25  4946.6  294.22
  4970.8  291.68  4976.2  291.64  4982.9  290.78  4996.8  290.21  4999.5  289.71
  5002.8  290.21    5028  292.37  5070.5  293.48  5197.8  293.84  5310.9  295.59
  5452.3   300.1  5466.5  301.11  5482.9  301.22  5494.7  302.43  5551.3  305.19
#Mann= 4 ,-1 , 0
  4447.1     .05       0  4996.8     .03       0  5002.8     .05       0
  5482.9      .1       0
Bank Sta=4976.2,5028
XS Rating Curve= 0 ,0
Exp/Cntr=0.3,0.1

Type RM Length L Ch R = 1 ,16672   ,609,609,609
BEGIN DESCRIPTION:
Mapping XS 38a16b53
END DESCRIPTION:
XS GIS Cut Line= 3
      2210376.16     13285684.46      2210162.64     13285075.13
      2209591.21     13284768.64
#Sta/Elev= 30
  4280.1  305.33    4416  302.75  4467.5  302.64  4498.5  301.34  4574.3  300.08
  4754.4  298.26  4896.4  294.57  4902.7  293.82  4934.9  292.92  4951.1   290.7
  4965.4  290.33  4997.6   289.1  5000.4   288.6  5003.6   289.1  5016.9  290.34
  5055.1  290.75  5067.5  289.98  5098.9  289.85  5104.6  289.16  5135.6  289.92
  5208.5  289.98    5215  290.85  5318.2  292.63  5394.5  295.31  5422.1   295.2
  5487.9  299.18  5498.5  300.47  5516.7  301.12    5548  303.06  5574.2  303.63
#Mann= 4 ,-1 , 0
  4280.1     .05       0  4997.6     .03       0  5003.6     .05       0
  5516.7      .1       0
Bank Sta=4965.4,5016.9
XS Rating Curve= 0 ,0
Exp/Cntr=0.3,0.1

Type RM Length L Ch R = 1 ,16063   ,427,427,427
BEGIN DESCRIPTION:
HACKBERRY CREEK 28.0
END DESCRIPTION:
XS GIS Cut Line= 3
      2210478.57     13285366.89      2210446.01     13285019.63
      2209752.17     13284358.31
#Sta/Elev= 30
    4055  300.55  4095.2  300.78  4155.5  298.62  4336.6  297.02  4366.4  296.05
  4446.9  295.16  4567.2  294.48  4609.5  293.26  4645.1  293.32  4722.7  290.76
    4730  291.31  4772.5  290.64  4807.7  289.31  4885.4  288.91  4949.2  287.12
  4988.7     286  4991.4   285.5  4994.7     286  5034.1  287.32  5055.2  288.87
  5069.4  288.98  5097.7  290.22  5111.8  291.48  5161.2  293.41  5168.4  294.47
  5196.7  296.11    5310   300.8  5324.1  301.72  5338.3  304.36  5362.3  305.08
#Mann= 3 ,-1 , 0
    4055     .05       0  4988.7     .03       0  4994.7     .05       0
Bank Sta=4949.2,5034.1
XS Rating Curve= 0 ,0
Exp/Cntr=0.3,0.1

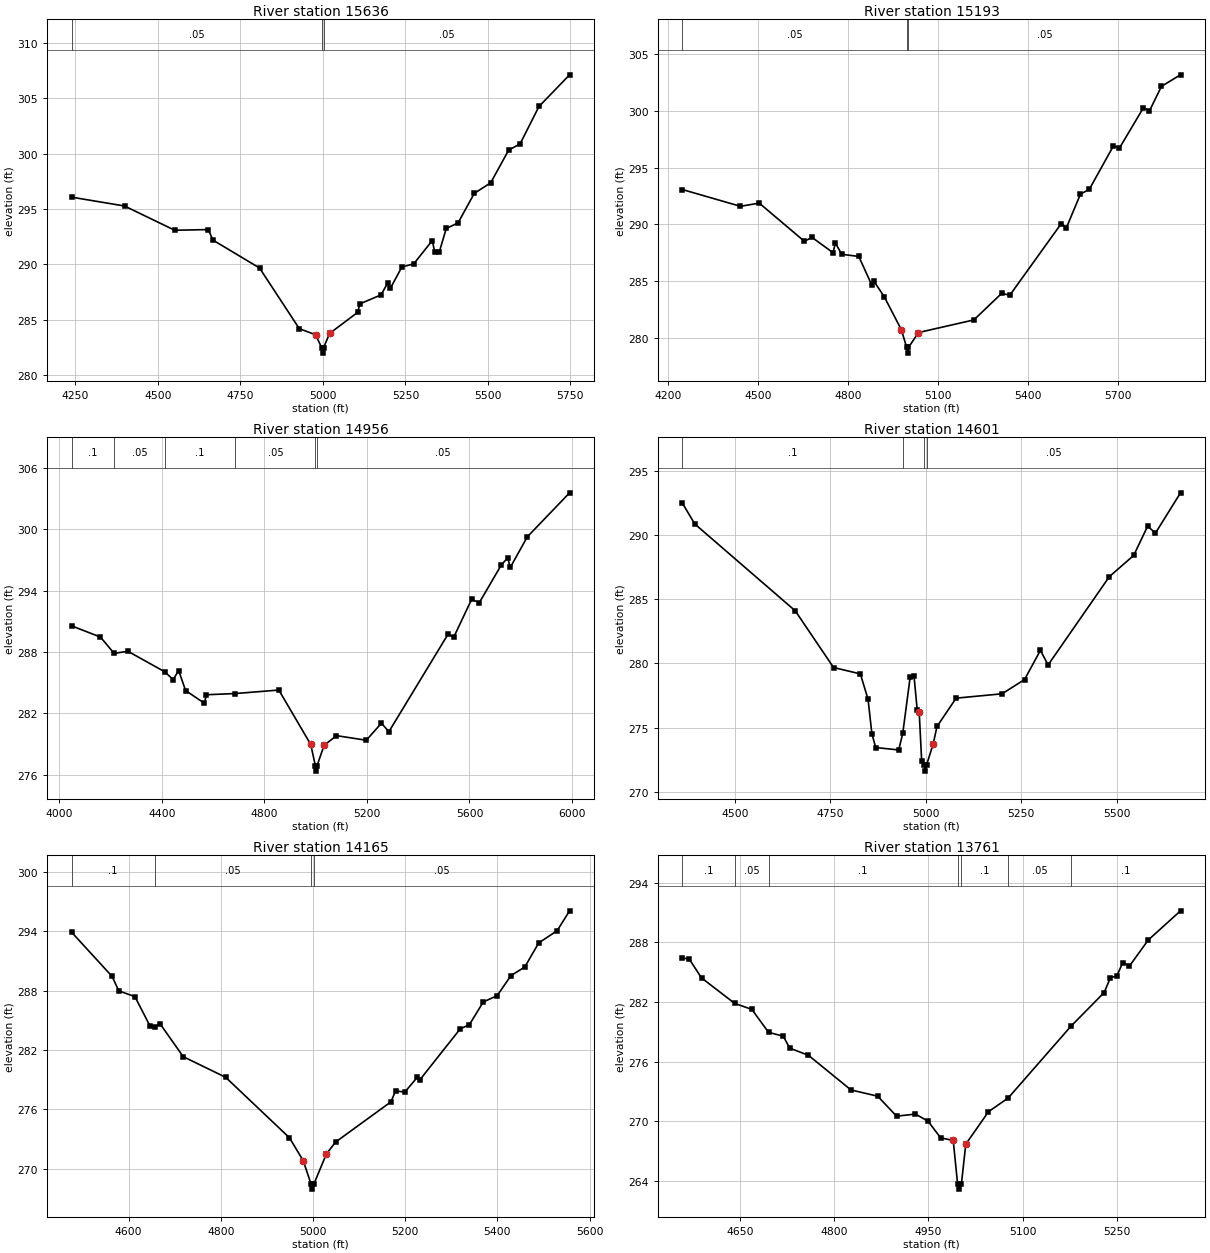
Type RM Length L Ch R = 1 ,15636   ,443,443,443
BEGIN DESCRIPTION:
HACKBERRY CREEK 27.0
END DESCRIPTION:
XS GIS Cut Line= 4
      2210782.37     13285084.69      2210706.43     13284780.92
      2210033.69     13284075.62       2209816.7     13284032.22
#Sta/Elev= 30
  4238.5  296.08    4399  295.28  4551.1  293.09  4652.7  293.15  4666.9   292.2
  4808.1  289.68  4928.6   284.2  4977.9  283.65  4996.3  282.49  4999.1  281.99
  5002.3  282.49  5020.4  283.77  5105.3  285.67  5112.2  286.44  5176.1  287.25
  5197.2  288.37  5204.4  287.84  5239.6  289.78  5275.2  290.05  5331.5  292.16
  5338.7  291.15  5352.9  291.14  5373.9  293.25  5409.5  293.75  5458.8  296.42
  5508.6  297.38    5563  300.33  5597.6  300.89  5654.8  304.27  5747.6  307.13
#Mann= 3 ,-1 , 0
  4238.5     .05       0  4996.3     .03       0  5002.3     .05       0
Bank Sta=4977.9,5020.4
XS Rating Curve= 0 ,0
Exp/Cntr=0.3,0.1

Type RM Length L Ch R = 1 ,15193   ,237,237,237
BEGIN DESCRIPTION:
HACKBERRY CREEK 26.0
END DESCRIPTION:
XS GIS Cut Line= 4
       2210977.7      13284791.8      2210945.15     13284368.59
       2210294.1      13283815.2      2209914.31      13283815.2
#Sta/Elev= 30
  4248.2  293.07  4441.1   291.6  4503.9  291.88  4654.3  288.52  4679.4  288.87
  4749.7  287.52  4757.4  288.38  4778.3  287.38  4835.4  287.19  4878.2   284.7
  4884.8  285.05  4919.9  283.66  4977.1  280.75  4994.9  279.19  4997.7  278.69
  5000.9  279.19  5034.2   280.5  5218.7  281.61    5311  283.94  5338.6  283.79
  5509.2  290.06  5527.1  289.73  5573.5  292.66  5603.5  293.11  5683.5  296.91
  5703.5  296.72  5783.5  300.27  5803.5  299.99  5843.5  302.15  5906.9  303.16
#Mann= 3 ,-1 , 0
  4248.2     .05       0  4994.9     .03       0  5000.9     .05       0
Bank Sta=4977.1,5034.2
XS Rating Curve= 0 ,0
Exp/Cntr=0.3,0.1

Type RM Length L Ch R = 1 ,14956   ,355,355,355
BEGIN DESCRIPTION:
Mapping XS a7cd044d
END DESCRIPTION:
XS GIS Cut Line= 3
      2211574.52     13284433.71      2210489.42     13283760.95
      2209827.55     13283695.85
#Sta/Elev= 30
  4048.5  290.56  4161.2  289.46  4214.4  287.87  4268.3  288.07  4411.4  286.07
  4444.7   285.3    4466  286.19  4493.1  284.23  4566.4  282.99  4574.2  283.82
  4687.5  283.94  4856.6  284.28    4981  278.96  4999.3  276.85    5002  276.35
  5005.3  276.85    5033  278.87  5081.4  279.82  5197.8  279.37  5256.6  281.04
  5285.8  280.21  5516.6  289.75    5538  289.42  5608.3  293.15  5638.4  292.83
  5724.2  296.52    5749  297.21    5759  296.27  5825.6  299.27  5990.3  303.57
#Mann= 6 ,-1 , 0
  4048.5      .1       0  4214.4     .05       0  4411.4      .1       0
  4687.5     .05       0  4999.3     .03       0  5005.3     .05       0
Bank Sta=4981,5033
XS Rating Curve= 0 ,0
Exp/Cntr=0.3,0.1

Type RM Length L Ch R = 1 ,14601   ,436,436,436
BEGIN DESCRIPTION:
HACKBERRY CREEK 25.0
END DESCRIPTION:
XS GIS Cut Line= 3
      2211357.44     13283381.21      2211194.71     13283554.79
      2210132.05     13283630.69
#Sta/Elev= 30
  4363.3  292.48  4395.5  290.87  4658.4   284.1  4758.6  279.68  4828.8  279.18
  4848.9   277.2  4858.9  274.52  4868.9  273.44  4929.1  273.25  4939.7  274.54
  4959.1  278.93  4969.2  279.02  4977.7  276.33  4982.7  276.23  4989.2   272.4
  4996.2   272.1    4999   271.6  5002.2   272.1  5019.3  273.71  5029.3  275.08
  5079.4  277.29  5199.7  277.63  5258.4  278.74    5300  281.02  5320.1  279.88
  5480.5  286.77  5544.1  288.42  5580.7  290.71  5600.8  290.15  5666.6   293.3
#Mann= 4 ,-1 , 0
  4363.3      .1       0  4939.7     .05       0  4996.2     .03       0
  5002.2     .05       0
Bank Sta=4982.7,5019.3
XS Rating Curve= 0 ,0
Exp/Cntr=0.3,0.1

Type RM Length L Ch R = 1 ,14165   ,404,404,404
BEGIN DESCRIPTION:
HACKBERRY CREEK 24.0
END DESCRIPTION:
XS GIS Cut Line= 3
      2211140.45     13283055.66      2211010.25     13283164.16
      2210100.76     13283207.47
#Sta/Elev= 30
  4476.5  293.92  4564.5  289.44  4578.8  287.99  4613.9   287.4    4646  284.48
  4657.2  284.34  4668.5  284.65  4718.6  281.33  4810.7  279.24  4948.9  273.13
  4978.9  270.81  4995.9  268.43  4998.7  267.93  5001.9  268.43  5028.9  271.47
    5049  272.69  5169.1  276.76  5179.1  277.87  5199.1  277.74  5226.2  279.24
  5231.2  278.95  5319.3  284.14  5339.3  284.57  5369.3  286.86  5399.4   287.5
  5429.4  289.53  5459.4   290.4  5489.5  292.83  5529.5  294.07  5556.5  296.08
#Mann= 4 ,-1 , 0
  4476.5      .1       0  4657.2     .05       0  4995.9     .03       0
  5001.9     .05       0
Bank Sta=4978.9,5028.9
XS Rating Curve= 0 ,0
Exp/Cntr=0.3,0.1

Type RM Length L Ch R = 1 ,13761   ,487,487,487
BEGIN DESCRIPTION:
HACKBERRY CREEK 23.0
END DESCRIPTION:
XS GIS Cut Line= 2
      2211048.04      13282804.3      2210256.37     13282767.84
#Sta/Elev= 30
  4558.9  286.39  4569.2  286.36  4589.2  284.42  4641.9  281.86  4669.3  281.25
  4695.8  278.95  4719.4  278.55  4729.4  277.36  4759.4  276.63    4827  273.15
  4869.5  272.52  4899.6  270.51  4929.6  270.72  4949.6  270.01  4969.7  268.33
  4989.7  268.07  4996.7  263.67  4999.4  263.17  5002.7  263.67  5009.7  267.69
  5045.8  270.96  5077.2  272.34  5176.9  279.55  5229.9  282.95  5239.9  284.45
  5249.9   284.6  5259.6  285.97    5270   285.6    5300  288.23  5351.4  291.17
#Mann= 7 ,-1 , 0
  4558.9      .1       0  4641.9     .05       0  4695.8      .1       0
  4996.7     .07       0  5002.7      .1       0  5077.2     .05       0
  5176.9      .1       0
Bank Sta=4989.7,5009.7
XS Rating Curve= 0 ,0
Exp/Cntr=0.3,0.1

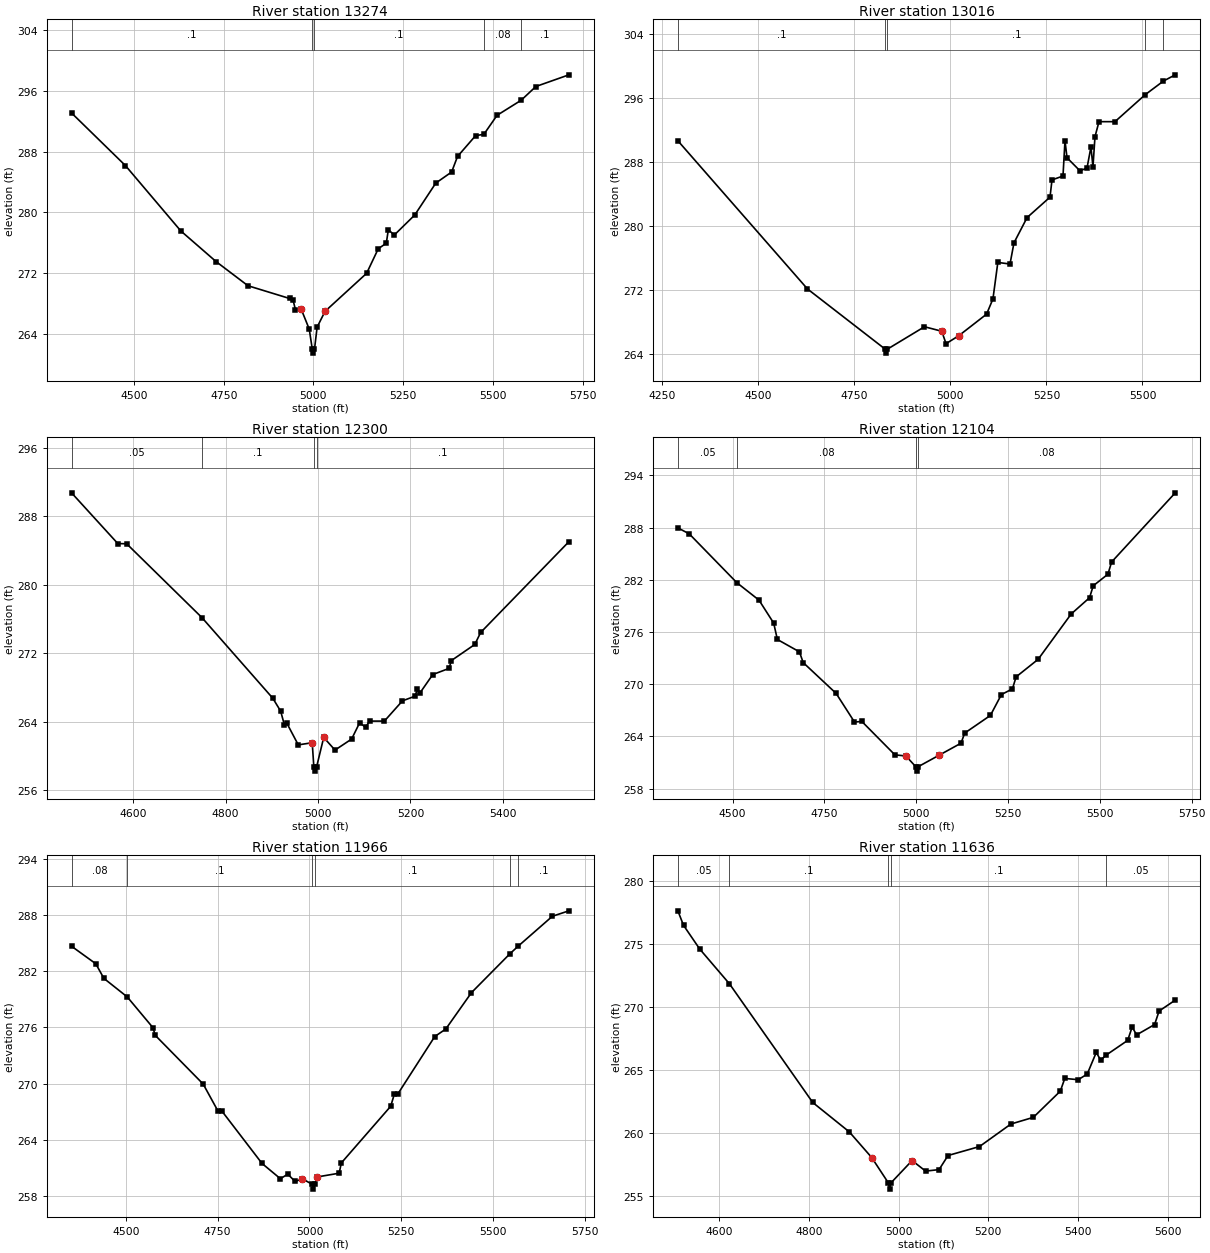
Type RM Length L Ch R = 1 ,13274   ,258,258,258
BEGIN DESCRIPTION:
HACKBERRY CREEK 22.0
END DESCRIPTION:
XS GIS Cut Line= 3
      2211314.08     13282632.48      2210261.55     13282079.09
       2210066.2      13282100.8
#Sta/Elev= 30
  4326.1  293.12  4476.2  286.18  4630.5  277.56  4728.7  273.52  4817.6  270.33
  4933.4  268.65  4943.4  268.42  4949.8  267.17    4966  267.23  4988.3  264.61
  4996.9  261.94  4999.6  261.44  5002.9  261.94  5010.3  264.87  5032.3  266.95
  5148.2  271.97  5180.6  275.21    5203  275.94  5208.7  277.73  5225.1  277.01
  5282.3  279.66  5340.9  283.87    5385  285.33  5401.4  287.38  5451.8  290.13
  5474.8   290.3  5511.6  292.81  5578.8   294.8  5619.7  296.61  5711.8  298.15
#Mann= 5 ,-1 , 0
  4326.1      .1       0  4996.9     .07       0  5002.9      .1       0
  5474.8     .08       0  5578.8      .1       0
Bank Sta=4966,5032.3
XS Rating Curve= 0 ,0
Exp/Cntr=0.3,0.1

Type RM Length L Ch R = 1 ,13016   ,716,716,716
BEGIN DESCRIPTION:
Mapping XS 4a1d0b11
END DESCRIPTION:
XS GIS Cut Line= 4
      2211413.57     13282434.66      2211106.26     13282241.94
      2210647.93     13282007.56       2210246.9     13281892.98
#Sta/Elev= 30
  4290.7  290.63  4628.1  272.15  4830.2  264.65    4833  264.15  4836.2  264.65
  4932.6  267.44  4977.5  266.88  4988.7  265.33  5021.9  266.32  5094.2  269.01
  5110.8  270.91  5123.5  275.46  5155.2  275.26  5165.5   277.9  5199.6  281.05
  5259.3   283.6  5264.5  285.75  5293.1  286.23  5298.3  290.64  5303.6  288.51
  5337.3  286.88  5355.6  287.23  5365.9  289.85  5371.1  287.38  5376.4  291.14
  5386.8  293.01  5428.4  293.01    5507  296.37  5554.7  298.08  5585.3  298.85
#Mann= 5 ,-1 , 0
  4290.7      .1       0  4830.2     .07       0  4836.2      .1       0
    5507     .08       0  5554.7      .1       0
Bank Sta=4977.5,5021.9
XS Rating Curve= 0 ,0
Exp/Cntr=0.3,0.1

Type RM Length L Ch R = 1 ,12300   ,196,196,196
BEGIN DESCRIPTION:
HACKBERRY CREEK 21.0
END DESCRIPTION:
XS GIS Cut Line= 3
      2211771.39     13282005.14      2211075.66     13281742.98
      2210746.27     13281692.56
#Sta/Elev= 30
  4466.5  290.75  4566.6  284.82  4585.9  284.79  4748.8  276.16  4902.2  266.73
  4919.2  265.22  4927.1  263.65  4932.4  263.83  4957.3  261.28  4987.5  261.53
    4991  258.71  4993.8  258.21    4997  258.71  5012.4  262.15  5036.8  260.67
  5072.8  261.96  5090.2  263.87    5103  263.33  5111.6  264.06  5143.7  264.06
  5182.9  266.43    5210  266.97  5215.2  267.82  5220.2  267.31  5248.4   269.5
  5283.6  270.22  5288.8  271.14  5339.4  273.02  5352.1  274.42  5543.2  285.04
#Mann= 4 ,-1 , 0
  4466.5     .05       0  4748.8      .1       0    4991     .07       0
    4997      .1       0
Bank Sta=4987.5,5012.4
XS Rating Curve= 0 ,0
Exp/Cntr=0.3,0.1

Type RM Length L Ch R = 1 ,12104   ,138,138,138
BEGIN DESCRIPTION:
HACKBERRY CREEK 20.0
END DESCRIPTION:
XS GIS Cut Line= 2
      2211968.63     13281633.58      2210614.45     13281626.64
#Sta/Elev= 30
  4351.2  287.96  4382.1  287.28  4511.9  281.66  4572.1  279.66  4612.1  277.02
  4622.1  275.14  4682.1  273.72  4692.5  272.48  4782.1  268.94  4832.1  265.65
  4852.1  265.72  4942.1  261.88  4972.1  261.75  4999.1  260.51  5001.9  260.01
  5005.1  260.51  5062.1  261.83  5122.1  263.22  5132.1  264.38  5202.1  266.41
  5232.1  268.81  5262.1  269.46  5272.1  270.84  5332.1  272.86  5422.1  278.07
  5472.1  279.94  5482.1  281.31  5522.1  282.64  5532.1  284.04  5705.4  291.99
#Mann= 4 ,-1 , 0
  4351.2     .05       0  4511.9     .08       0  4999.1     .07       0
  5005.1     .08       0
Bank Sta=4972.1,5062.1
XS Rating Curve= 0 ,0
Exp/Cntr=0.3,0.1

Type RM Length L Ch R = 1 ,11966   ,330,330,330
BEGIN DESCRIPTION:
HACKBERRY CREEK 19.0
END DESCRIPTION:
XS GIS Cut Line= 4
      2211982.99     13281544.37      2211698.45      13281501.9
      2210942.58     13281484.91      2210632.65      13281493.4
#Sta/Elev= 30
  4352.4  284.67  4418.4   282.8  4440.4  281.24    4504  279.26  4573.9  275.98
  4580.2  275.16  4710.8  269.95  4750.9  267.08  4760.9  267.11  4870.9  261.48
  4920.9  259.85  4940.9  260.34  4960.9  259.56  4980.9  259.84  5007.9  259.24
  5010.7  258.74  5013.9  259.24  5020.9  260.04  5080.9  260.44  5086.6  261.53
    5221  267.58    5231  268.88    5241  268.93    5341  275.03    5371  275.83
    5441  279.72  5546.2  283.89  5568.4  284.69  5661.1  287.87  5706.2  288.45
#Mann= 6 ,-1 , 0
  4352.4     .08       0    4504      .1       0  5007.9     .07       0
  5013.9      .1       0  5546.2     .05       0  5568.4      .1       0
Bank Sta=4980.9,5020.9
XS Rating Curve= 0 ,0
Exp/Cntr=0.3,0.1

Type RM Length L Ch R = 1 ,11636   ,180,180,180
BEGIN DESCRIPTION:
HACKBERRY CREEK 18.0
END DESCRIPTION:
XS GIS Cut Line= 3
       2211915.9     13281406.92      2211694.06     13281211.96
      2210881.75      13281201.9
#Sta/Elev= 30
  4508.5  277.64  4521.1  276.49  4557.1  274.61  4623.5  271.84  4808.9  262.42
  4890.2  260.09  4940.2  258.05  4977.2  256.04  4979.9  255.54  4983.2  256.04
  5030.2  257.81  5060.2  256.97  5090.2  257.09  5110.2  258.21  5180.2  258.92
  5250.2  260.71  5300.2  261.24  5360.2  263.32  5370.2  264.33  5400.2  264.23
  5420.2  264.68  5440.2  266.39  5450.2  265.79  5462.6  266.19  5510.2  267.35
  5520.2  268.41  5530.2  267.79  5570.2  268.61  5580.2  269.68  5616.2  270.55
#Mann= 5 ,-1 , 0
  4508.5     .05       0  4623.5      .1       0  4977.2     .07       0
  4983.2      .1       0  5462.6     .05       0
Bank Sta=4940.2,5030.2
XS Rating Curve= 0 ,0
Exp/Cntr=0.3,0.1

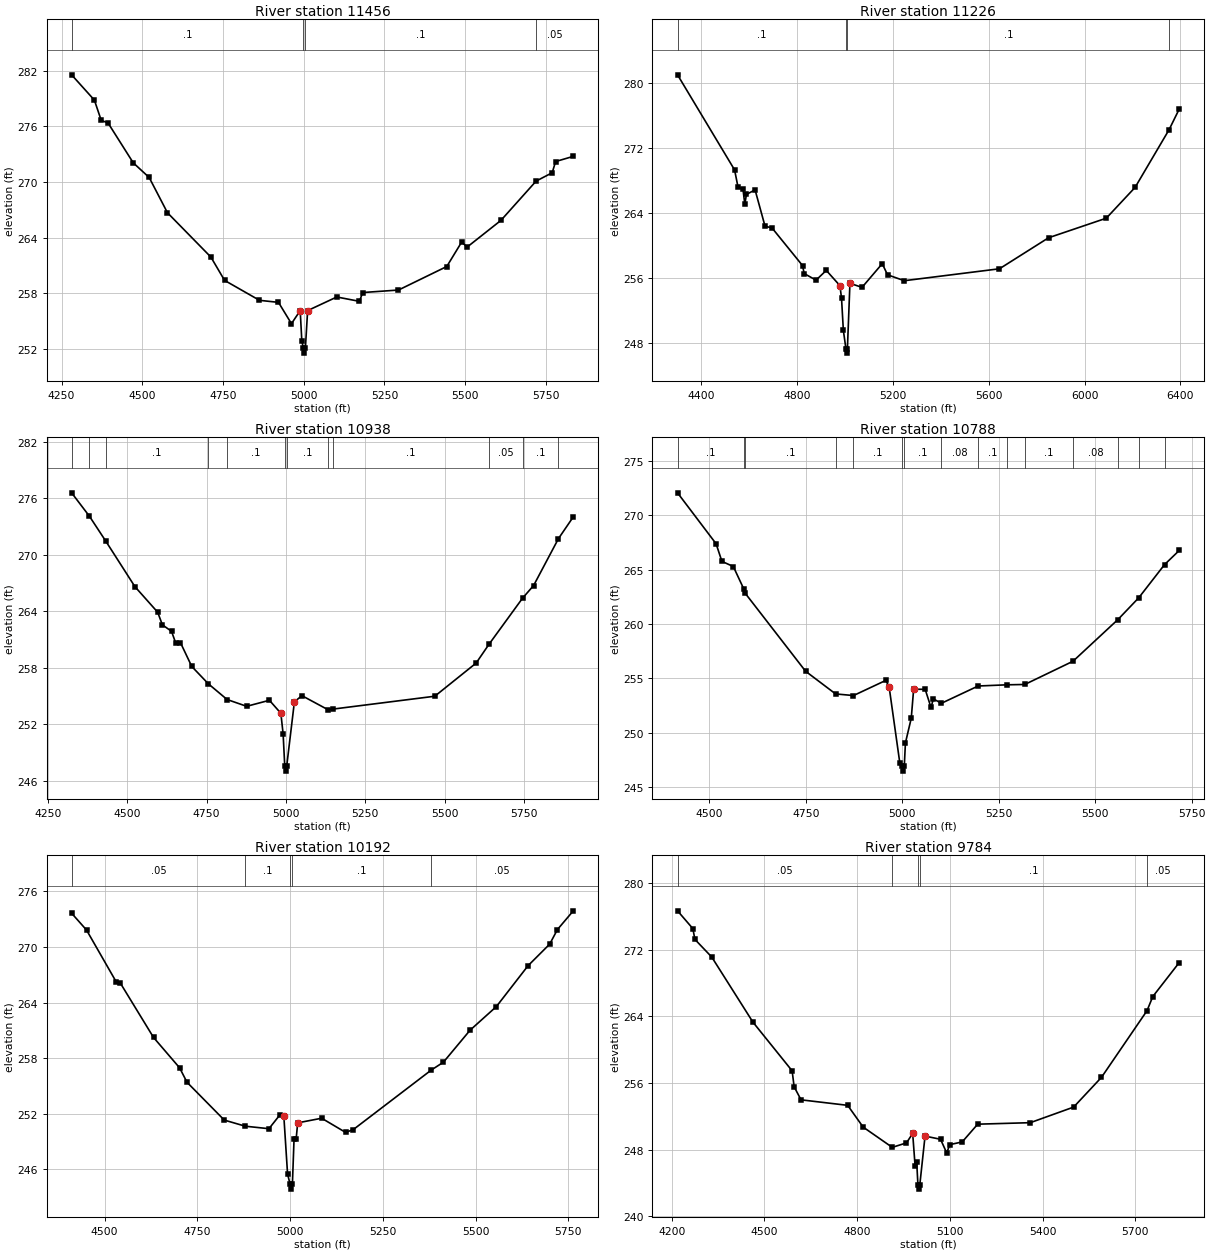
Type RM Length L Ch R = 1 ,11456   ,230,230,230
BEGIN DESCRIPTION:
Mapping XS 6355bb49
END DESCRIPTION:
XS GIS Cut Line= 4
      2212085.45     13281408.63      2211762.51     13281059.65
      2211283.34     13281023.19      2210715.63     13281210.69
#Sta/Elev= 30
  4281.1  281.57  4351.6  278.84  4372.8  276.65  4393.8  276.38    4472  272.07
  4521.3  270.49    4578  266.68  4712.4   261.9  4754.9  259.38    4863  257.23
  4921.8  257.01    4962  254.71  4989.1  256.12  4994.1  252.85  4999.1  252.03
  5001.8  251.53  5005.1  252.03  5012.1  256.12  5102.4  257.59  5172.6  257.12
  5182.6  258.07  5293.5  258.34  5443.1  260.88  5489.2  263.52  5506.3  262.98
  5610.9  265.86  5719.8   270.1  5769.6     271  5780.2  272.21    5835  272.77
#Mann= 4 ,-1 , 0
  4281.1      .1       0  4999.1     .07       0  5005.1      .1       0
  5719.8     .05       0
Bank Sta=4989.1,5012.1
XS Rating Curve= 0 ,0
Exp/Cntr=0.3,0.1

Type RM Length L Ch R = 1 ,11226   ,288,288,288
BEGIN DESCRIPTION:
Mapping XS d39a0282
END DESCRIPTION:
XS GIS Cut Line= 3
      2212097.63     13281383.01      2211507.36     13280695.07
      2210613.38     13279911.25
#Sta/Elev= 30
    4300     281  4538.3  269.29  4552.6  267.18  4573.4   266.9  4581.1  265.05
  4587.7  266.27  4623.9  266.83  4665.6  262.34  4694.1  262.16    4822  257.51
  4829.1  256.52  4878.5  255.71  4921.3  256.91  4978.4  255.03    4985  253.47
  4992.6  249.53  5003.5  247.22  5006.2  246.72  5009.5  247.22  5020.1  255.32
  5070.6  254.82  5155.1  257.74    5177  256.37  5247.1  255.64  5644.7  257.11
  5849.7  260.93  6090.8  263.34  6211.3  267.14  6353.4  274.26  6395.4  276.78
#Mann= 4 ,-1 , 0
    4300      .1       0  5003.5     .07       0  5009.5      .1       0
  6353.4     .05       0
Bank Sta=4978.4,5020.1
XS Rating Curve= 0 ,0
Exp/Cntr=0.3,0.1

Type RM Length L Ch R = 1 ,10938   ,150,150,150
BEGIN DESCRIPTION:
Mapping XS d8b4e2e8
END DESCRIPTION:
XS GIS Cut Line= 4
      2212246.22     13281225.84       2211885.3     13280703.56
      2211460.65     13280036.86      2211430.93     13279884.04
#Sta/Elev= 30
  4324.8  276.57    4381  274.08  4432.1  271.46  4524.3  266.61  4595.9   263.9
  4610.8  262.56  4639.6  261.87  4652.7  260.64  4667.6  260.68  4703.4  258.14
  4755.6   256.3  4814.8  254.63  4876.4  253.91  4948.1  254.55  4984.2  253.17
  4991.3  250.98  4996.5  247.53  4999.2  247.03  5002.5  247.53  5026.9  254.39
  5050.6  255.04  5132.7  253.55  5147.4  253.61  5469.3  254.98  5599.6   258.5
  5639.8  260.48  5745.9  265.39  5780.7  266.73    5859  271.71  5905.8  274.02
#Mann= 12 ,-1 , 0
  4324.8      .1       0    4381     .05       0  4432.1      .1       0
  4755.6     .08       0  4814.8      .1       0  4996.5     .07       0
  5002.5      .1       0  5132.7     .08       0  5147.4      .1       0
  5639.8     .05       0  5745.9      .1       0    5859     .08       0
Bank Sta=4984.2,5026.9
XS Rating Curve= 0 ,0
Exp/Cntr=0.3,0.1

Type RM Length L Ch R = 1 ,10788   ,596,596,596
BEGIN DESCRIPTION:
Mapping XS 8aa1d797
END DESCRIPTION:
XS GIS Cut Line= 2
      2212316.27     13281087.55      2211600.12     13280002.47
#Sta/Elev= 30
  4417.7  272.08  4517.6  267.39  4532.7  265.77  4562.3  265.29    4590  263.18
  4593.1  262.83  4749.5  255.65  4827.3  253.56  4873.7  253.41  4957.7  254.81
  4966.2  254.17  4993.6  247.24  4999.4  246.95  5002.1  246.45  5005.4  246.95
  5008.3  249.05  5023.4  251.32  5029.6     254  5059.5  253.98  5074.6  252.31
  5080.6   253.1  5101.6   252.7  5196.8  254.29  5272.1   254.4  5317.6  254.43
  5442.6  256.57    5559  260.41  5613.1  262.42  5679.8  265.47  5717.8  266.77
#Mann= 15 ,-1 , 0
  4417.7      .1       0    4590     .08       0  4593.1      .1       0
  4827.3     .08       0  4873.7      .1       0  4999.4     .07       0
  5005.4      .1       0  5101.6     .08       0  5196.8      .1       0
  5272.1     .08       0  5317.6      .1       0  5442.6     .08       0
    5559      .1       0  5613.1     .08       0  5679.8     .05       0
Bank Sta=4966.2,5029.6
XS Rating Curve= 0 ,0
Exp/Cntr=0.3,0.1

Type RM Length L Ch R = 1 ,10192   ,408,408,408
BEGIN DESCRIPTION:
HACKBERRY CREEK 15.0
END DESCRIPTION:
XS GIS Cut Line= 3
      2212587.72     13280946.83      2212537.72     13280346.85
      2212087.69     13279746.82
#Sta/Elev= 30
  4411.1  273.65  4451.2  271.84  4531.5  266.23  4541.5  266.17  4631.8  260.25
  4702.1  256.97  4722.1  255.41  4822.5  251.33  4879.2  250.67  4942.9   250.4
    4973  251.92    4983  251.78  4993.1  245.51  5000.1  244.38  5002.9  243.88
  5006.1  244.38  5010.6  249.33  5016.3  249.33  5020.4  251.03    5085  251.53
  5149.6     250  5170.4  250.31  5380.1  256.72  5413.2  257.58    5485  261.03
  5555.9  263.58  5641.3  267.99  5699.6  270.32  5720.4  271.89  5763.2  273.91
#Mann= 5 ,-1 , 0
  4411.1     .05       0  4879.2      .1       0  5000.1     .07       0
  5006.1      .1       0  5380.1     .05       0
Bank Sta=4983,5020.4
XS Rating Curve= 0 ,0
Exp/Cntr=0.3,0.1

Type RM Length L Ch R = 1 ,9784    ,446,446,446
BEGIN DESCRIPTION:
HACKBERRY CREEK 14.0
END DESCRIPTION:
XS GIS Cut Line= 3
      2212750.74     13281047.01      2212959.07     13280639.03
      2212898.31     13279475.81
#Sta/Elev= 30
  4218.7  276.64  4268.2  274.51    4275  273.21  4329.3   271.1  4462.6  263.29
  4589.4  257.45  4595.9  255.54  4618.2  253.97  4769.1  253.31  4819.2   250.7
  4913.4  248.27  4959.4  248.81  4979.4  249.94  4987.3  245.99  4992.3  246.56
  4996.4  243.76  4999.2  243.26  5002.4  243.76  5019.4  249.62  5069.5  249.24
  5089.5   247.6  5099.5   248.6  5139.6  248.92  5189.7  251.05  5359.9  251.23
  5500.1   253.1  5590.2  256.67  5737.4  264.66  5756.2  266.36  5841.6  270.43
#Mann= 5 ,-1 , 0
  4218.7     .05       0  4913.4      .1       0  4996.4     .07       0
  5002.4      .1       0  5737.4     .05       0
Bank Sta=4979.4,5019.4
XS Rating Curve= 0 ,0
Exp/Cntr=0.3,0.1

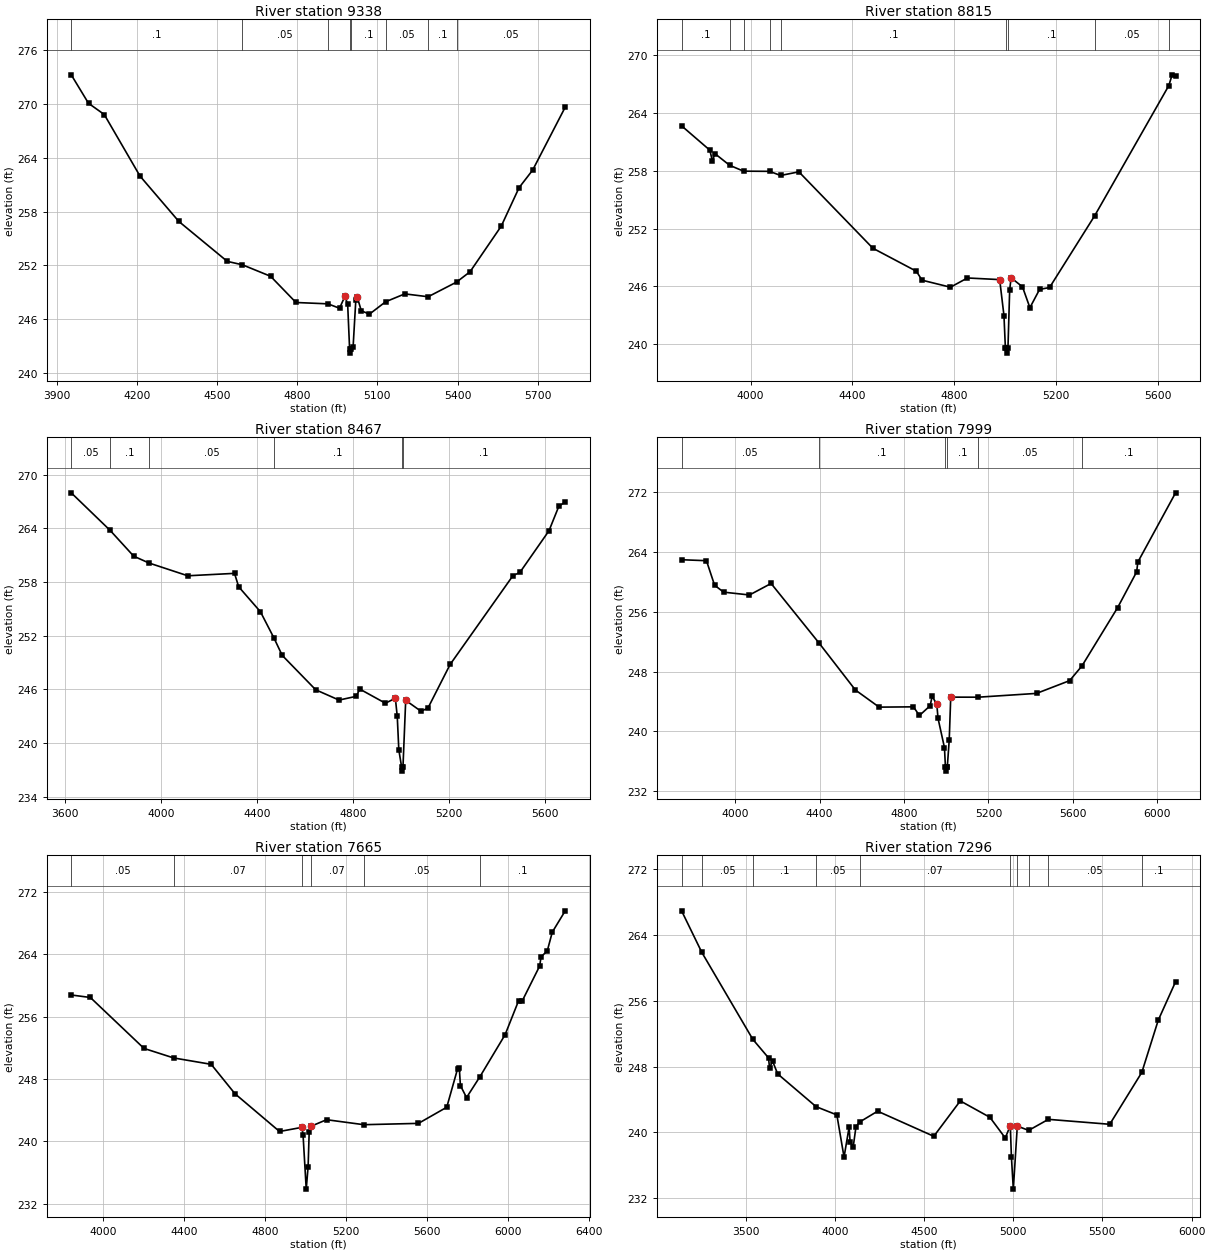
Type RM Length L Ch R = 1 ,9338    ,523,523,523
BEGIN DESCRIPTION:
HACKBERRY CREEK 13.0
END DESCRIPTION:
XS GIS Cut Line= 3
      2213202.14     13281220.61      2213471.23     13280751.88
      2213228.17     13279467.15
#Sta/Elev= 30
  3954.9  273.23  4019.5  270.06  4078.4  268.81  4212.2  261.95  4357.4   256.9
  4538.6  252.45  4595.1  252.07  4700.7  250.79  4795.6  247.87  4915.2  247.72
  4958.5  247.23  4978.8  248.56    4989  247.67  4996.2  242.73  4998.9  242.23
  5002.2  242.73  5009.4  242.96  5019.5  248.15    5025  248.46  5039.9  246.95
  5070.4  246.57  5130.9  247.95  5202.7  248.83    5290  248.51  5396.2  250.14
    5447   251.3  5563.6  256.38  5630.2  260.66  5681.1  262.62  5802.9  269.63
#Mann= 8 ,-1 , 0
  3954.9      .1       0  4595.1     .05       0  4915.2      .1       0
  4996.2     .07       0  5002.2      .1       0  5130.9     .05       0
    5290      .1       0  5396.2     .05       0
Bank Sta=4978.8,5025
XS Rating Curve= 0 ,0
Exp/Cntr=0.3,0.1

Type RM Length L Ch R = 1 ,8815    ,348,348,348
BEGIN DESCRIPTION:
HACKBERRY CREEK 12.0
END DESCRIPTION:
XS GIS Cut Line= 3
      2214070.19     13281237.99       2214061.5     13280526.18
      2213514.62     13279423.73
#Sta/Elev= 30
  3728.4  262.67  3839.5  260.14  3849.5  259.02  3859.5  259.78  3917.3  258.57
  3971.9  257.96  4074.6  257.94  4117.7  257.51  4189.6  257.89  4480.6  249.95
  4651.6  247.56  4673.9  246.63  4785.6   245.9  4852.5  246.86  4979.2  246.69
  4996.1  242.95  5001.7  239.57  5005.8  239.55  5008.6  239.05  5011.8  239.55
  5018.5   245.6  5024.1  246.88  5068.9  245.94  5098.1  243.77  5136.1  245.67
  5175.4  245.87  5352.9  253.33  5644.3  266.85  5657.3  267.97  5670.9  267.81
#Mann= 9 ,-1 , 0
  3728.4      .1       0  3917.3     .05       0  3971.9      .1       0
  4074.6     .05       0  4117.7      .1       0  5005.8     .07       0
  5011.8      .1       0  5352.9     .05       0  5644.3      .1       0
Bank Sta=4979.2,5024.1
XS Rating Curve= 0 ,0
Exp/Cntr=0.3,0.1

Type RM Length L Ch R = 1 ,8467    ,468,468,468
BEGIN DESCRIPTION:
HACKBERRY CREEK 11.0
END DESCRIPTION:
XS GIS Cut Line= 3
      2214530.24     13281090.37      2214295.88     13280074.79
      2213653.53     13279284.87
#Sta/Elev= 30
  3624.6  267.96  3786.9  263.76  3885.2  260.88  3948.6  260.12  4110.6  258.69
  4305.6  258.96    4323  257.46  4413.7  254.67    4471  251.69  4504.4   249.8
  4644.2  245.95  4741.6   244.8  4813.5  245.22  4827.9  246.03  4934.9  244.45
  4976.5     245  4984.4  242.97  4990.9  239.24  5002.3  237.36    5005  236.86
  5008.3  237.36  5019.6  244.77  5083.5  243.55  5112.3   243.9  5204.9  248.78
  5467.1  258.71  5495.8  259.06  5617.2  263.72  5658.8  266.49    5685  266.92
#Mann= 6 ,-1 , 0
  3624.6     .05       0  3786.9      .1       0  3948.6     .05       0
    4471      .1       0  5002.3     .07       0  5008.3      .1       0
Bank Sta=4976.5,5019.6
XS Rating Curve= 0 ,0
Exp/Cntr=0.3,0.1

Type RM Length L Ch R = 1 ,7999    ,334,334,334
BEGIN DESCRIPTION:
HACKBERRY CREEK 10.0
END DESCRIPTION:
XS GIS Cut Line= 4
      2214747.28     13280691.15      2214530.25     13279710.21
      2214139.63     13278972.36      2213662.47      13278816.2
#Sta/Elev= 30
  3745.4  262.98  3863.3  262.85  3901.8  259.57  3944.4  258.64  4067.3  258.26
  4169.7   259.8  4395.7  251.87  4569.1  245.54  4681.8  243.24  4844.4  243.28
  4872.8  242.12  4923.6  243.43  4933.2  244.69  4955.2  243.63  4960.9  241.76
  4991.5  237.81  4996.2  235.17  4998.9  234.67  5002.2  235.17  5004.9   235.2
  5014.1  238.85  5021.2  244.58  5150.6  244.57  5427.9  245.08  5584.9  246.79
  5643.5  248.77  5812.4  256.57  5902.6  261.36    5908  262.66    6087  271.94
#Mann= 6 ,-1 , 0
  3745.4     .05       0  4395.7      .1       0  4996.2     .07       0
  5002.2      .1       0  5150.6     .05       0  5643.5      .1       0
Bank Sta=4955.2,5021.2
XS Rating Curve= 0 ,0
Exp/Cntr=0.3,0.1

Type RM Length L Ch R = 1 ,7665    ,369,369,369
BEGIN DESCRIPTION:
Mapping XS c471bb1d
END DESCRIPTION:
XS GIS Cut Line= 3
      2214845.94     13280530.77      2214911.04     13279901.39
      2214281.69     13278208.64
#Sta/Elev= 30
  3843.6  258.76    3938  258.44  4202.8  251.91    4349  250.69  4534.5  249.87
  4651.9   246.1  4871.9  241.26  4982.6  241.79    4988  240.82  5003.7  233.87
    5013  236.76  5018.3  241.25  5025.3  241.91  5104.1  242.77  5288.2  242.13
  5557.7   242.3  5697.4  244.37  5750.8  249.29  5759.5  249.35  5764.8  247.15
  5795.1  245.61  5861.1  248.28  5985.5  253.67  6052.3  258.04  6070.8  258.04
  6156.2  262.48    6163  263.67  6193.4  264.39  6218.4  266.82  6282.3  269.55
#Mann= 6 ,-1 , 0
  3843.6     .05       0    4349     .07       0  4982.6    .035       0
  5025.3     .07       0  5288.2     .05       0  5861.1      .1       0
Bank Sta=4982.6,5025.3
XS Rating Curve= 0 ,0
Exp/Cntr=0.3,0.1

Type RM Length L Ch R = 1 ,7296    ,455,455,455
BEGIN DESCRIPTION:
HACKBERRY CREEK 9.0
END DESCRIPTION:
XS GIS Cut Line= 2
      2215827.99      13280913.5      2214662.55     13278402.26
#Sta/Elev= 30
  3141.4  266.92  3254.8  261.87  3540.7   251.3  3628.7  249.05  3634.2  247.84
  3651.6  248.64    3680   247.1  3895.3  243.12  4011.6  242.12  4051.9  236.99
  4080.3  240.63  4085.8  238.86  4103.2  238.23  4118.9   240.7    4141  241.28
  4240.1  242.57  4554.9  239.52  4703.3  243.82  4869.2  241.83  4955.3  239.32
  4983.7  240.81  4989.8  237.06  5000.6   233.1  5022.9  240.76  5086.7  240.24
  5197.1  241.58    5541  240.98  5720.8  247.29  5812.8  253.63  5909.9   258.3
#Mann= 10 ,-1 , 0
  3141.4      .1       0  3254.8     .05       0  3540.7      .1       0
  3895.3     .05       0    4141     .07       0  4983.7    .035       0
  5022.9     .07       0  5086.7     .08       0  5197.1     .05       0
  5720.8      .1       0
#XS Ineff= 1 ,-1
 4010.54 4205.66 241.683
Permanent Ineff=
       F
Bank Sta=4983.7,5022.9
XS Rating Curve= 0 ,0
Exp/Cntr=0.3,0.1