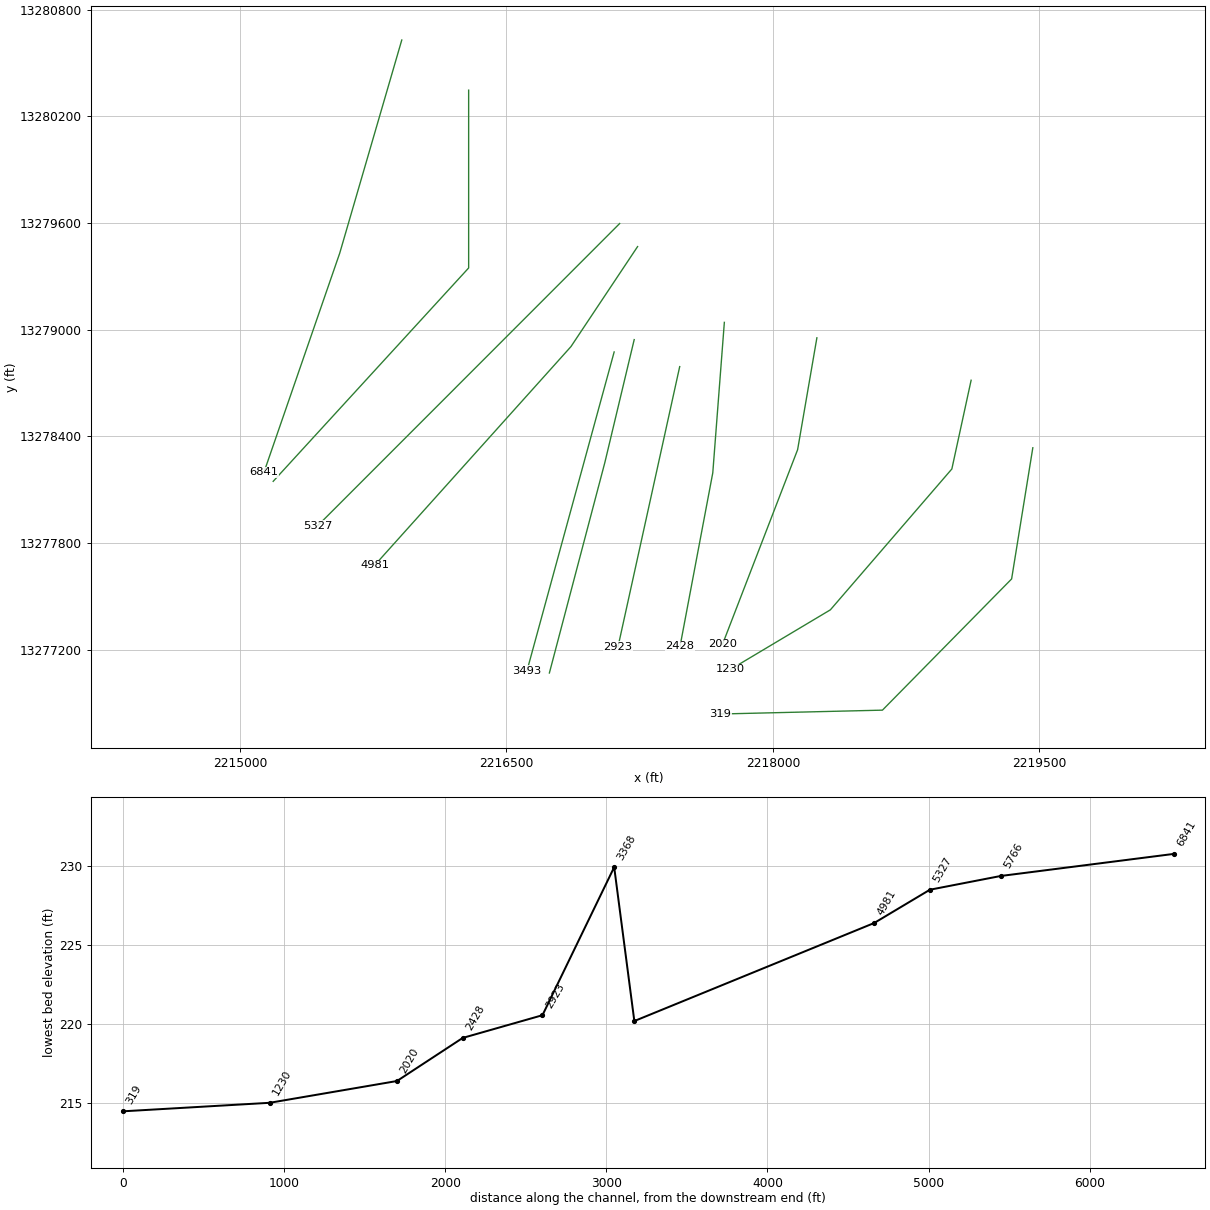
HEC-RAS study HACKBERRY CREEK.prj: HACKBERRY CREEK Base Level Engineering

--- HACKBERRY CREEK.g01 (geometry) --- (continued)

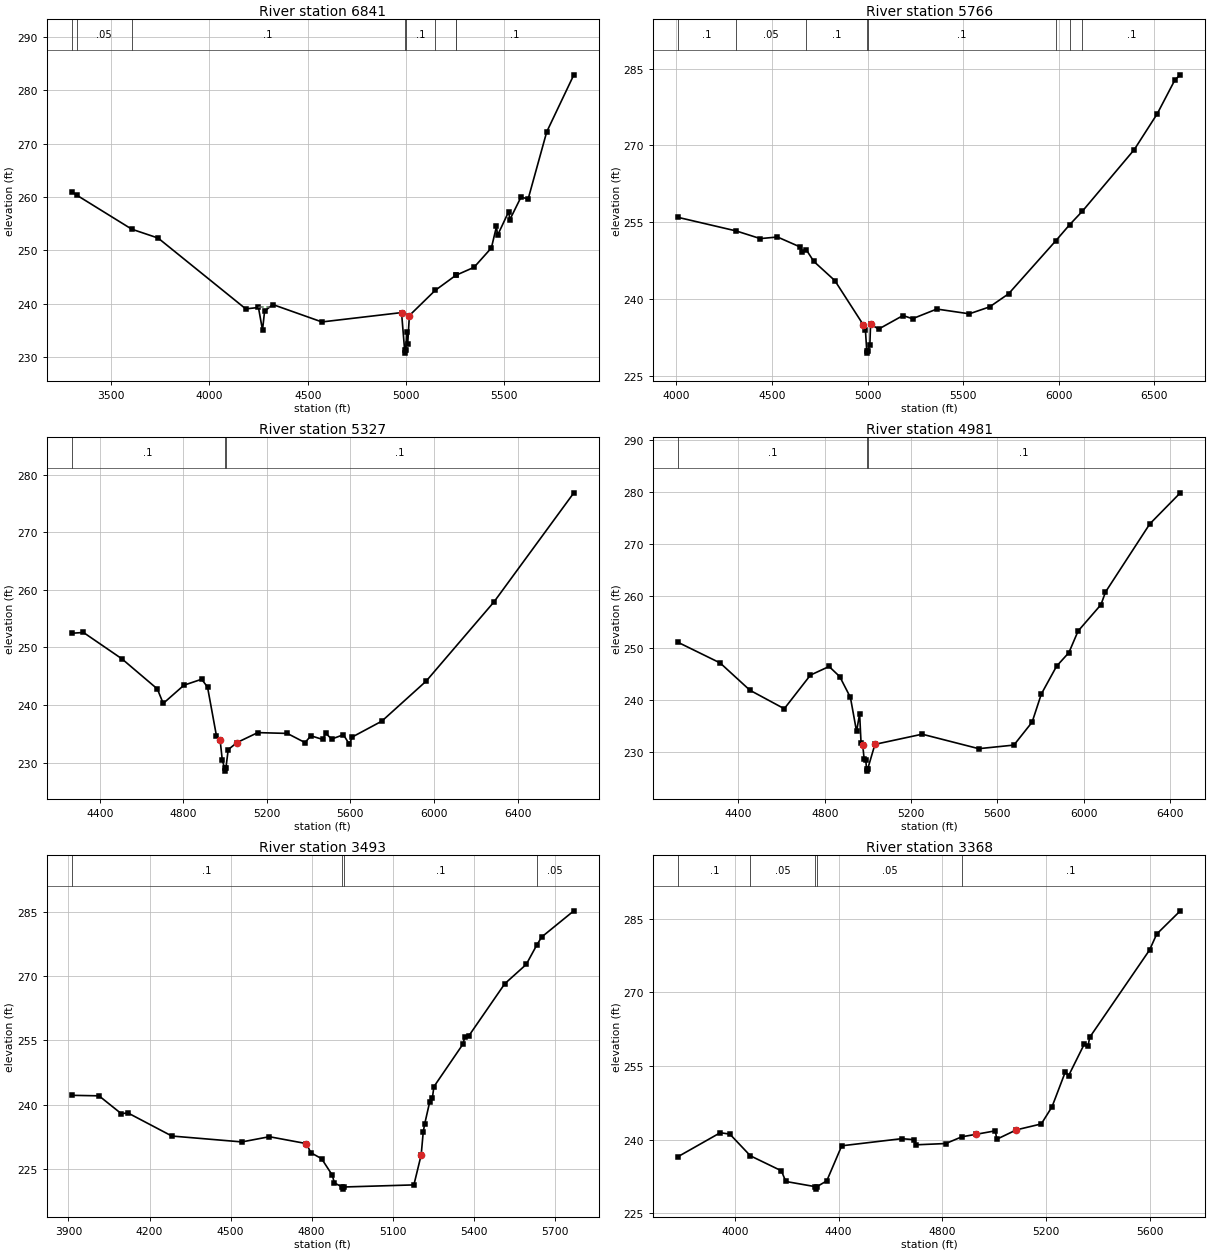
Type RM Length L Ch R = 1 ,6841    ,1075,1075,1075
BEGIN DESCRIPTION:
HACKBERRY CREEK 8.0
END DESCRIPTION:
XS GIS Cut Line= 3
      2215911.35     13280628.85      2215562.38     13279430.89
       2215135.3     13278196.54
#Sta/Elev= 30
  3299.5  261.04  3325.4  260.36  3605.1  253.99    3739  252.33  4185.1  239.06
  4249.4  239.33  4270.2   235.1  4280.7  238.64  4322.3  239.88  4572.1  236.62
  4977.2  238.37    4993  231.28  4995.7  230.78    4999  231.28  5003.1  234.65
  5008.4   232.5  5017.1  237.82  5147.7  242.51  5253.3  245.35  5256.4   245.4
  5345.9  246.85  5434.1  250.48    5460   254.5  5465.3  252.83  5522.3  257.29
  5527.6  255.74  5584.6  259.99  5621.1  259.65  5715.5  272.21  5853.4  282.89
#Mann= 8 ,-1 , 0
  3299.5      .1       0  3325.4     .05       0  3605.1      .1       0
    4993     .07       0    4999      .1       0  5147.7     .08       0
  5253.3     .05       0  5256.4      .1       0
#XS Ineff= 1 ,-1
    4250 4301.41  239.33
Permanent Ineff=
       F
Bank Sta=4977.2,5017.1
XS Rating Curve= 0 ,0
Exp/Cntr=0.3,0.1

Type RM Length L Ch R = 1 ,5766    ,439,439,439
BEGIN DESCRIPTION:
HACKBERRY CREEK 7.0
END DESCRIPTION:
XS GIS Cut Line= 3
      2216287.72     13280346.85      2216287.72     13279346.85
      2215187.71     13278146.84
#Sta/Elev= 30
  4008.5  255.93  4312.1  253.28  4438.5  251.78  4528.5  252.09  4648.5  250.12
  4658.5  249.21  4679.5  249.57  4718.5  247.32  4828.5  243.57  4978.5  234.86
  4988.5  233.99  4995.5  229.88  4998.2  229.38  5001.5  229.88  5011.9  231.04
  5015.6  235.02  5058.1  234.09  5185.2  236.73  5235.1  236.11  5362.1     238
  5532.3  237.07  5638.4  238.42  5737.7  240.98  5983.3  251.29  6057.4   254.5
    6124  257.14  6395.6  269.19  6515.8   276.2  6608.3  282.82  6636.4  283.81
#Mann= 8 ,-1 , 0
  4008.5      .1       0  4312.1     .05       0  4679.5      .1       0
  4995.5     .07       0  5001.5      .1       0  5983.3     .08       0
  6057.4     .05       0    6124      .1       0
Bank Sta=4978.5,5015.6
XS Rating Curve= 0 ,0
Exp/Cntr=0.3,0.1

Type RM Length L Ch R = 1 ,5327    ,346,346,346
BEGIN DESCRIPTION:
HACKBERRY CREEK 6.0
END DESCRIPTION:
XS GIS Cut Line= 3
      2217137.73     13279596.86      2216637.72     13279096.85
       2215437.7     13277896.84
#Sta/Elev= 30
  4265.4  252.46    4322  252.59  4505.8  248.02  4675.5  242.79  4703.8  240.27
  4802.8  243.43  4887.7  244.47  4915.9  243.11  4958.4  234.68  4976.1  233.92
  4986.7   230.4  4997.8  229.01  5000.6  228.51  5003.8  229.01  5014.9  232.25
  5057.4  233.48  5156.4   235.2  5297.8  235.06  5382.6  233.47  5410.9  234.65
  5467.5  234.01  5481.6   235.1  5509.9  234.08  5566.5  234.83  5594.8  233.19
  5608.9  234.44  5750.3  237.19  5962.5  244.14  6287.7  257.92  6669.6  276.85
#Mann= 3 ,-1 , 0
  4265.4      .1       0  4997.8     .07       0  5003.8      .1       0
Bank Sta=4976.1,5057.4
XS Rating Curve= 0 ,0
Exp/Cntr=0.3,0.1

Type RM Length L Ch R = 1 ,4981    ,1488,1488,1488
BEGIN DESCRIPTION:
Mapping XS fd2773a4
END DESCRIPTION:
XS GIS Cut Line= 3
      2217238.56     13279467.12      2216863.59     13278904.65
      2215759.41     13277675.47
#Sta/Elev= 30
  4120.4  251.12  4315.1  247.17  4453.3  241.93  4612.6  238.38  4733.7  244.83
  4820.3  246.49  4869.9  244.54  4919.3  240.54  4947.7  234.02  4961.9  237.41
  4968.6  231.74  4976.1  231.41  4982.8  228.78  4990.3  228.54    4994   226.9
  4996.8   226.4    5000   226.9  5032.9  231.54  5251.9  233.49  5514.3  230.71
  5677.2   231.4  5761.7  235.81  5804.3   241.2  5875.3  246.56  5932.1  249.15
  5974.7  253.29  6080.9  258.36  6101.8  260.78  6307.4  273.87  6448.7  279.83
#Mann= 3 ,-1 , 0
  4120.4      .1       0    4994     .07       0    5000      .1       0
Bank Sta=4976.1,5032.9
XS Rating Curve= 0 ,0
Exp/Cntr=0.3,0.1

Type RM Length L Ch R = 1 ,3493    ,125,125,125
BEGIN DESCRIPTION:
Mapping XS 7ce52e50
END DESCRIPTION:
XS GIS Cut Line= 2
      2217106.65     13278874.49      2216616.21     13277081.97
#Sta/Elev= 30
  3911.8  242.15    4013  242.03    4096  237.83    4119  238.06  4282.6  232.62
  4541.8  231.24  4643.5  232.46  4780.2  230.85    4797  228.71  4836.7  227.32
  4876.4  223.45  4883.9  221.64    4913  220.69  4915.8  220.19    4919  220.69
  5178.3  221.18  5205.3  228.21  5212.8  233.53  5217.9  235.35  5236.4   240.5
  5246.8  241.59  5252.4  244.18  5360.8  254.22  5366.3  255.89  5381.5  256.06
  5514.7  268.28    5594  272.79  5632.9  277.31  5651.1  279.21  5770.2  285.34
#Mann= 4 ,-1 , 0
  3911.8      .1       0    4913     .07       0    4919      .1       0
  5632.9     .05       0
Bank Sta=4780.2,5205.3
XS Rating Curve= 0 ,0
Exp/Cntr=0.3,0.1

Type RM Length L Ch R = 1 ,3368    ,445,445,445
BEGIN DESCRIPTION:
Mapping XS f3fff1db
END DESCRIPTION:
XS GIS Cut Line= 3
      2217219.49      13278943.9      2217054.57     13278253.81
      2216742.08     13277068.95
#Sta/Elev= 30
  3781.7  236.56  3944.1  241.42    3981  241.14  4060.2  236.72  4179.6  233.67
  4196.5   231.5  4310.3  230.44  4313.1  229.94  4316.3  230.44  4354.4  231.62
  4412.1  238.76  4643.2  240.21  4692.1     240  4697.3  238.96    4813  239.22
  4874.8  240.59  4928.7  241.09  5004.1  241.81  5009.3  240.09  5084.7     242
    5181  243.21  5222.4  246.71  5274.1  253.88  5286.2  253.03  5346.5  259.45
  5361.6  259.15  5367.1  260.81  5598.1  278.61  5625.7  281.86  5716.6  286.59
#Mann= 5 ,-1 , 0
  3781.7      .1       0  4060.2     .05       0  4310.3     .07       0
  4316.3     .05       0  4874.8      .1       0
Bank Sta=4928.7,5084.7
XS Rating Curve= 0 ,0
Exp/Cntr=0.3,0.1

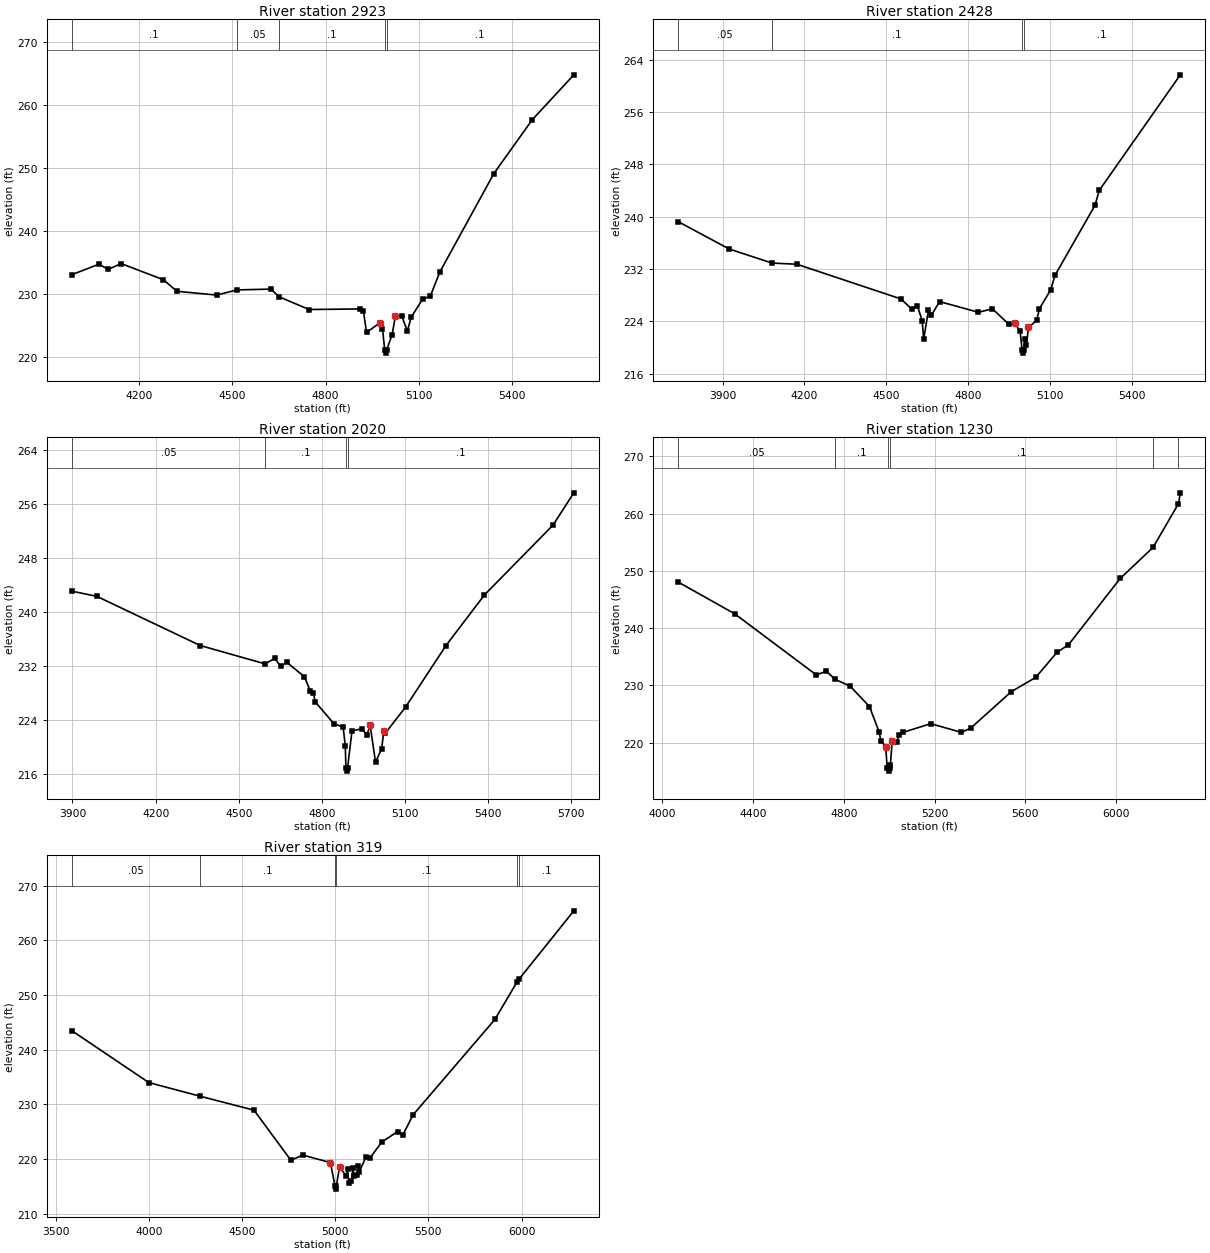
Type RM Length L Ch R = 1 ,2923    ,495,495,495
BEGIN DESCRIPTION:
Mapping XS 1b2a94c2
END DESCRIPTION:
XS GIS Cut Line= 2
      2217475.57     13278792.01      2217128.36     13277216.51
#Sta/Elev= 30
  3984.5     233  4071.7  234.66  4102.4  233.85  4143.4  234.77  4279.1  232.21
  4322.8  230.37  4450.6  229.77  4515.2  230.59  4624.7  230.72    4651  229.49
  4747.5  227.48  4911.4  227.57  4921.6  227.26    4932  223.85  4975.7   225.4
  4983.1  224.44  4990.3  221.06    4993  220.56  4996.3  221.06  5013.8  223.45
  5024.5  226.45  5044.5   226.5  5063.1  224.07  5075.2  226.25    5112  229.13
  5136.7   229.6  5167.4  233.44  5340.8  249.05  5464.3   257.6  5597.8  264.72
#Mann= 5 ,-1 , 0
  3984.5      .1       0  4515.2     .05       0    4651      .1       0
  4990.3     .07       0  4996.3      .1       0
Bank Sta=4975.7,5024.5
XS Rating Curve= 0 ,0
Exp/Cntr=0.3,0.1

Type RM Length L Ch R = 1 ,2428    ,408,408,408
BEGIN DESCRIPTION:
Mapping XS 40bc24ba
END DESCRIPTION:
XS GIS Cut Line= 3
      2217726.83     13279040.86      2217661.73     13278194.54
      2217477.63      13277219.9
#Sta/Elev= 30
  3736.9  239.23  3923.6  235.05  4080.9  232.89  4172.2  232.71  4553.3  227.41
  4593.5  225.85  4613.9  226.34  4631.7  224.05  4636.8  221.21  4654.6  225.69
  4664.8  224.89  4695.3     227  4837.8  225.36  4888.7   225.9  4949.7  223.51
  4970.1  223.66  4990.4  222.54  4997.6  219.62  5000.4  219.12  5003.6  219.62
  5008.5  221.32  5013.6  220.35    5021  223.04  5051.5  224.15  5060.9  225.89
  5102.4  228.79  5118.4  231.02  5265.2  241.75  5280.6  244.01  5577.6  261.67
#Mann= 4 ,-1 , 0
  3736.9     .05       0  4080.9      .1       0  4997.6     .07       0
  5003.6      .1       0
Bank Sta=4970.1,5021
XS Rating Curve= 0 ,0
Exp/Cntr=0.3,0.1

Type RM Length L Ch R = 1 ,2020    ,790,790,790
BEGIN DESCRIPTION:
HACKBERRY CREEK 3.0
END DESCRIPTION:
XS GIS Cut Line= 3
      2218247.66     13278954.05      2218139.16     13278324.75
      2217716.55      13277230.3
#Sta/Elev= 30
    3897   243.1  3987.7  242.33  4360.9  235.03  4594.7  232.31  4629.8  233.12
  4651.2  231.94  4672.7  232.55    4737   230.4  4758.4  228.21  4769.2  228.05
    4775  226.71  4844.2  223.38  4876.4  222.95  4884.2  220.15  4886.5  216.89
  4889.3  216.39  4892.5  216.89  4908.5  222.38  4944.1  222.67  4962.1   221.8
    4974  223.17  4993.3  217.73  5015.7  219.73  5023.2  222.41  5028.6  222.03
  5101.5  225.88  5246.8  234.99  5385.9  242.52  5634.1  252.92  5708.8  257.69
#Mann= 4 ,-1 , 0
    3897     .05       0  4594.7      .1       0  4886.5     .07       0
  4892.5      .1       0
Bank Sta=4974,5023.2
XS Rating Curve= 0 ,0
Exp/Cntr=0.3,0.1

Type RM Length L Ch R = 1 ,1230    ,911,911,911
BEGIN DESCRIPTION:
HACKBERRY CREEK 2.0
END DESCRIPTION:
XS GIS Cut Line= 4
      2219115.73     13278715.42      2219007.21     13278216.25
      2218323.62     13277424.14      2217761.03     13277088.76
#Sta/Elev= 30
  4070.3  248.05  4319.7  242.49  4679.6   231.8  4722.4  232.47    4763  231.03
  4828.8  229.83  4913.3  226.28  4956.1  221.82  4963.4  220.28  4984.6  219.29
  4991.2  215.63  4995.8  215.51  4998.6  215.01  5001.8  215.51  5005.4  216.14
  5013.1   220.2    5034  220.07  5041.6  221.26  5062.5   221.8  5183.1   223.3
  5318.1  221.78  5359.8  222.54  5537.5  228.88  5645.8  231.39  5739.1  235.76
  5789.8  237.08  6017.6  248.67  6162.3  254.09  6274.3  261.73  6282.4  263.63
#Mann= 6 ,-1 , 0
  4070.3     .05       0    4763      .1       0  4995.8     .07       0
  5001.8      .1       0  6162.3     .05       0  6274.3      .1       0
Bank Sta=4984.6,5013.1
XS Rating Curve= 0 ,0
Exp/Cntr=0.3,0.1

Type RM Length L Ch R = 1 ,319     ,0,0,0
BEGIN DESCRIPTION:
HACKBERRY CREEK 1.0
END DESCRIPTION:
XS GIS Cut Line= 4
      2219462.94     13278335.58      2219343.58     13277597.76
      2218616.59     13276859.91      2217705.09     13276838.21
#Sta/Elev= 30
  3585.4  243.47  3999.4  233.96  4273.9  231.47  4563.9  228.91  4761.9  219.75
  4825.5   220.7    4974  219.32  4999.3  214.97  5002.1  214.47  5005.3  214.97
  5023.5  218.59  5058.9  216.82  5065.9  218.16    5073  215.53  5087.2  215.89
  5094.2  218.35  5101.3  216.79  5115.5  217.06  5122.5   218.7  5129.6  217.68
  5164.9  220.35  5186.2  220.15  5249.8  223.08  5334.6     225  5362.9  224.39
  5417.5  228.05  5857.6  245.54  5975.7  252.37  5986.7  252.89  6280.4  265.37
#Mann= 6 ,-1 , 0
  3585.4     .05       0  4273.9      .1       0  4999.3     .07       0
  5005.3      .1       0  5975.7     .05       0  5986.7      .1       0
Bank Sta=4974,5023.5
XS Rating Curve= 0 ,0
Exp/Cntr=0.3,0.1

Chan Stop Cuts=-1
Use User Specified Reach Order=0
Composite Channel Slope=5