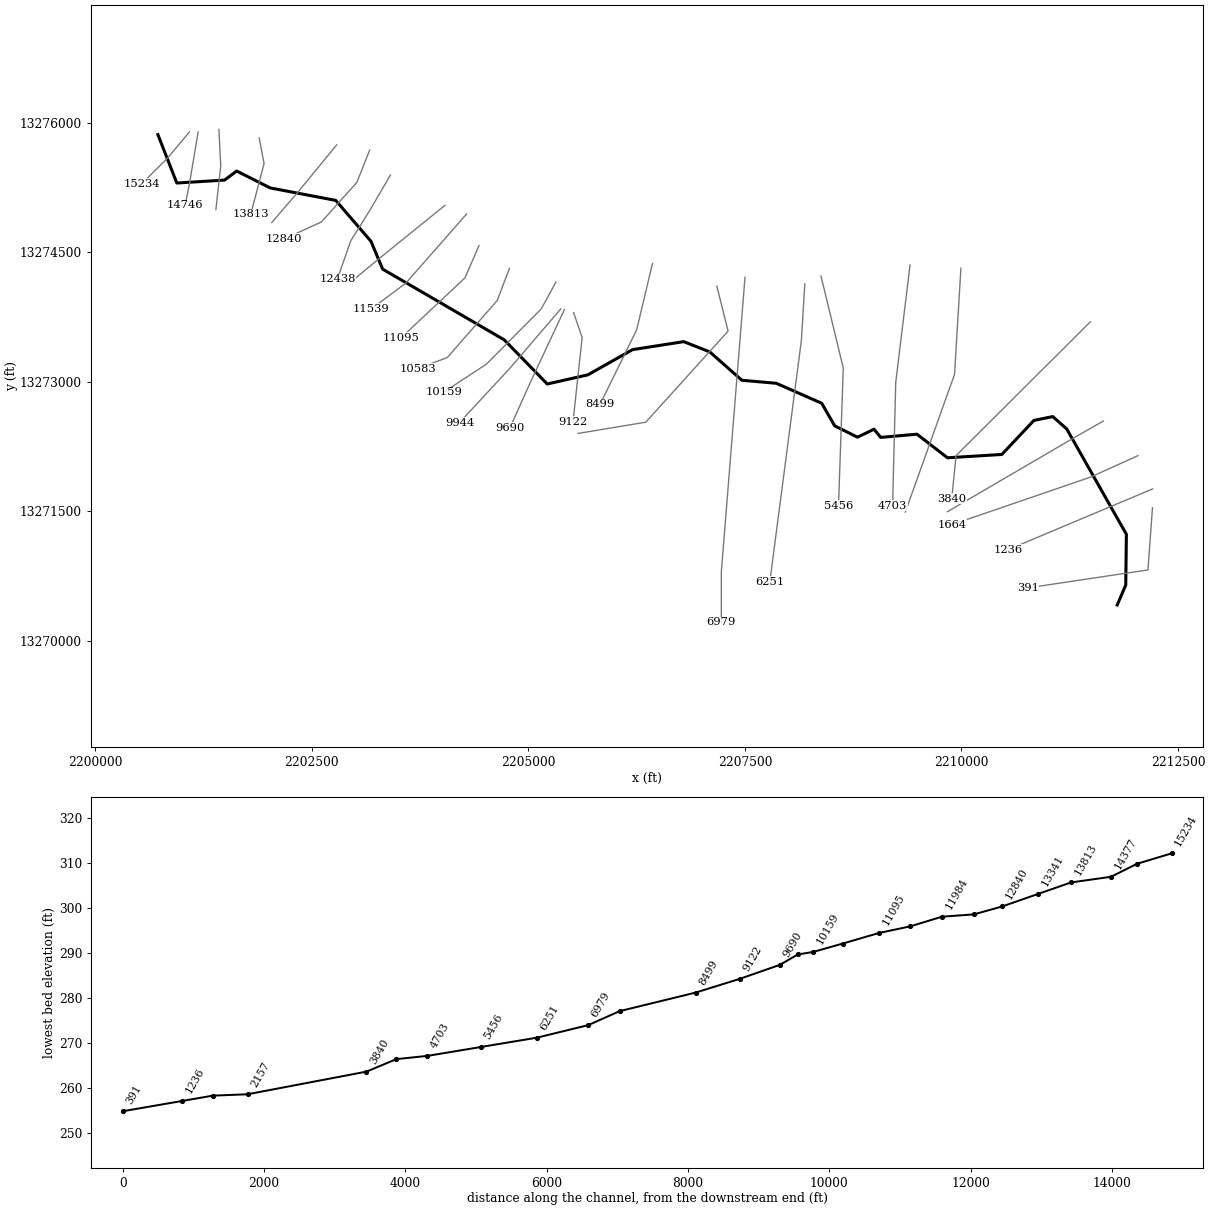
--- LEOPARD BRANCH.prj (project) ---

Proj Title=LEOPARD BRANCH Base Level Engineering
Current Plan=p01
Default Exp/Contr=0.3,0.1
English Units
Geom File=g01
Flow File=f01
Plan File=p01
Y Axis Title=Elevation
X Axis Title(PF)=Main Channel Distance
X Axis Title(XS)=Station
BEGIN DESCRIPTION:
LEOPARD BRANCH
END DESCRIPTION:
DSS Export Rating Curves= 0
DSS Export Rating Curve Sorted= 0
DSS Export Volume Flow Curves= 0
DXF OffsetX= 0
DXF OffsetY= 0
DXF ScaleX= 1
DXF ScaleY= 10

--- LEOPARD BRANCH.p01 (plan) ---

Plan Title=Multiple Run
Short Identifier=Multiple
Geom File=g01
Flow File=f01
Subcritical Flow
K Sum by GR= 0
Std Step Tol= 0.01
Critical Tol= 0.01
Num of Std Step Trials= 20
Max Error Tol= 0.3
Flow Tol Ratio= 0.001
Split Flow NTrial= 30
Split Flow Tol= 0.02
Split Flow Ratio= 0.02
Log Output Level= 0
Friction Slope Method= 1
Unsteady Friction Slope Method= 2
Unsteady Bridges Friction Slope Method= 1
Parabolic Critical Depth
Global Vel Dist=  1 , 1 , 1
Global Log Level= 0
CheckData=True
Encroach Param= -1, 0, 0, 0
BEGIN DESCRIPTION:
Multiple Run
END DESCRIPTION:

--- LEOPARD BRANCH.f01 (steady flow) ---

Flow Title=Multiple
Program Version=4.10
Number of Profiles= 7
Profile Names=10-year,25-year,50-year,1pct_min,100-year,1pct_plu,500-year
River Rch & RM=LEOPARD BRANCH,Reach-1         ,15234
     195     270     332     300     406     549     619
River Rch & RM=LEOPARD BRANCH,Reach-1         ,14377
     306     432     539     494     668     904    1044
River Rch & RM=LEOPARD BRANCH,Reach-1         ,8499
     356     507     635     584     790    1068    1244
River Rch & RM=LEOPARD BRANCH,Reach-1         ,6979
    1221    1823    2357    2232    3019    4083    5034
River Rch & RM=LEOPARD BRANCH,Reach-1         ,5456
    1221    1823    2357    2232    3019    4083    5034
Boundary for River Rch & Prof#=LEOPARD BRANCH,Reach-1         , 1
Up Type= 0
Dn Type= 3
Dn Slope=0.005
Boundary for River Rch & Prof#=LEOPARD BRANCH,Reach-1         , 2
Up Type= 0
Dn Type= 3
Dn Slope=0.005
Boundary for River Rch & Prof#=LEOPARD BRANCH,Reach-1         , 3
Up Type= 0
Dn Type= 3
Dn Slope=0.005
Boundary for River Rch & Prof#=LEOPARD BRANCH,Reach-1         , 4
Up Type= 0
Dn Type= 3
Dn Slope=0.005
Boundary for River Rch & Prof#=LEOPARD BRANCH,Reach-1         , 5
Up Type= 0
Dn Type= 3
Dn Slope=0.005
Boundary for River Rch & Prof#=LEOPARD BRANCH,Reach-1         , 6
Up Type= 0
Dn Type= 3
Dn Slope=0.005
Boundary for River Rch & Prof#=LEOPARD BRANCH,Reach-1         , 7
Up Type= 0
Dn Type= 3
Dn Slope=0.005
DSS Import GetInterval= 0
DSS Import GetPeak= 0
DSS Import FillOption= 0

--- LEOPARD BRANCH.g01 (geometry) ---

Geom Title=Existing Conditions
Program Version=4.10

River Reach=LEOPARD BRANCH  ,Reach-1
Reach XY= 30
      2200723.32     13275865.36      2200941.46     13275304.74
      2201492.53     13275338.45      2201632.92     13275443.74
       2202019.3     13275247.93      2202776.36     13275103.56
      2203183.04     13274629.67      2203317.79     13274307.34
      2204722.03     13273487.84      2205217.91     13272976.77
      2205685.58     13273082.03      2206203.49     13273374.59
      2206793.91     13273467.29      2207094.29     13273348.26
      2207465.26     13273019.74      2207862.11      13272984.9
      2208386.45     13272753.64      2208536.12     13272492.11
      2208799.32     13272360.47      2208990.73      13272452.8
      2209067.78     13272358.08      2209486.27     13272394.96
      2209838.69     13272121.68      2210466.43     13272160.31
      2210836.11     13272554.47      2211053.94      13272599.1
      2211215.17     13272455.91      2211903.93     13271235.29
       2211896.5     13270647.06      2211797.72     13270416.86

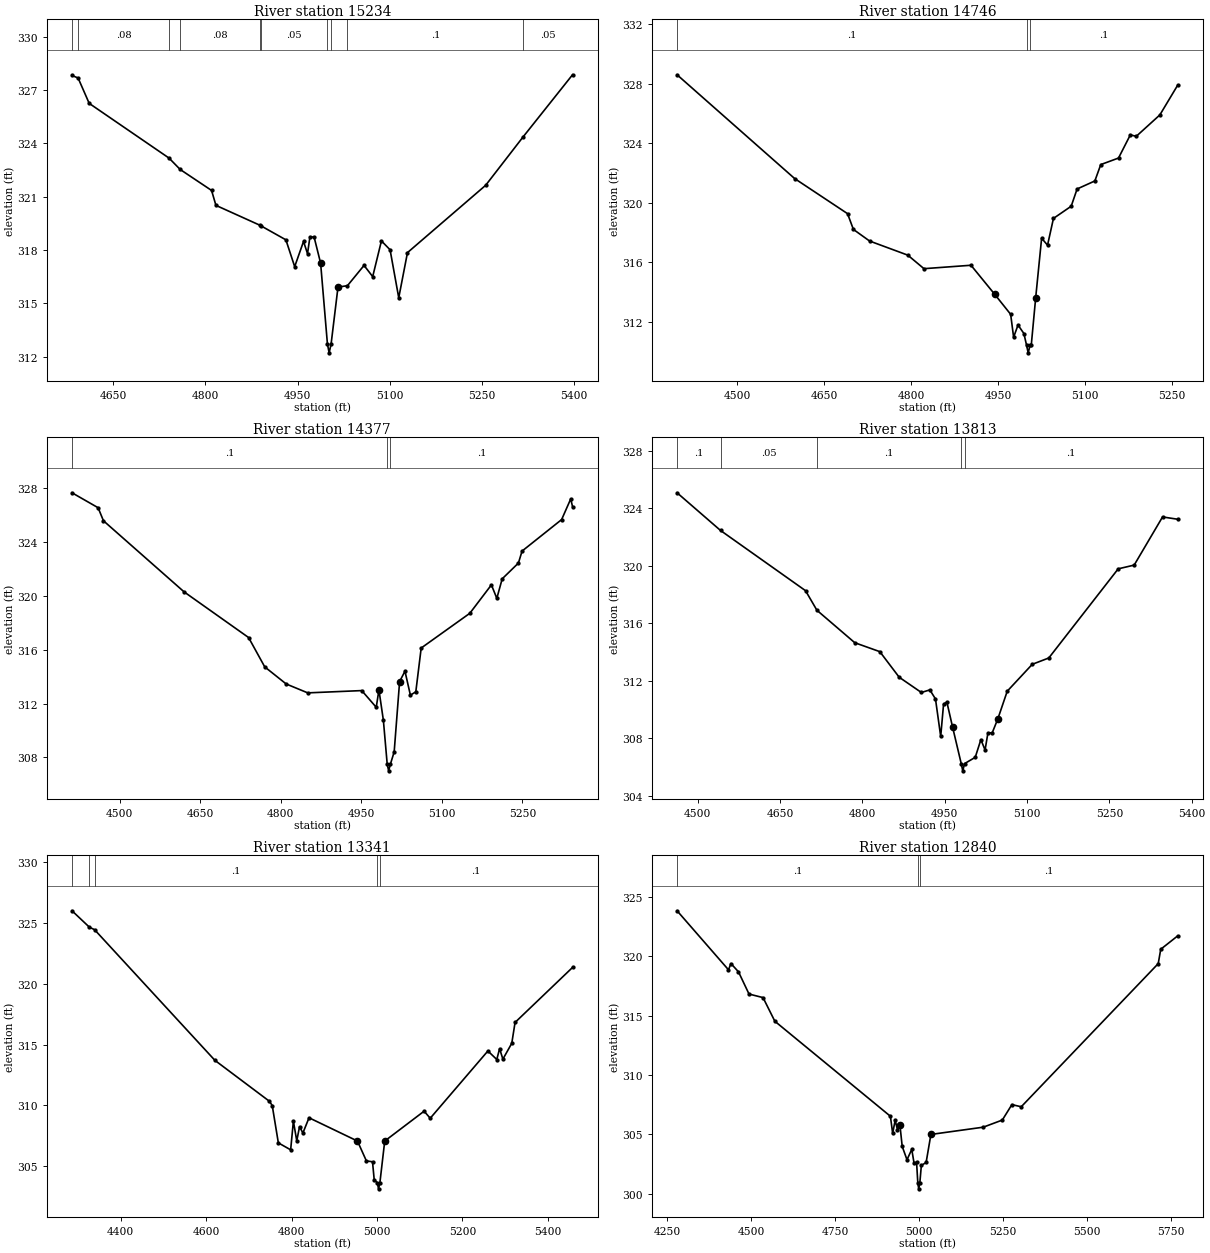
Type RM Length L Ch R = 1 ,15234   ,488,488,488
BEGIN DESCRIPTION:
LEOPARD BRANCH 27.0
END DESCRIPTION:
XS GIS Cut Line= 3
      2201087.73     13275896.87      2200837.72     13275596.85
      2200537.71     13275296.85
#Sta/Elev= 30
  4582.8  327.82  4592.7  327.68  4610.8  326.25  4740.8  323.17  4758.9  322.53
    4810  321.35  4817.1  320.51  4888.8  319.39  4890.8  319.35    4931  318.57
  4945.3  317.06  4959.7  318.48  4966.2  317.79  4970.1  318.73  4976.9  318.73
  4987.5  317.26  4998.6  312.71  5001.4  312.21  5004.6  312.71  5015.8  315.91
  5031.2  315.99  5058.2  317.13  5072.3   316.5  5086.5  318.51  5100.6  318.01
  5114.7  315.31  5128.9  317.85  5256.2  321.64  5317.5  324.38  5397.6  327.86
#Mann= 10 ,-1 , 0
  4582.8      .1       0  4592.7     .08       0  4740.8      .1       0
  4758.9     .08       0  4888.8      .1       0  4890.8     .05       0
  4998.6     .04       0  5004.6     .05       0  5031.2      .1       0
  5317.5     .05       0
Bank Sta=4987.5,5015.8
XS Rating Curve= 0 ,0
Exp/Cntr=0.3,0.1

Type RM Length L Ch R = 1 ,14746   ,369,369,369
BEGIN DESCRIPTION:
LEOPARD BRANCH 26.0
END DESCRIPTION:
XS GIS Cut Line= 3
      2201187.72     13275896.87      2201087.72     13275296.85
      2201037.73     13275046.89
#Sta/Elev= 30
  4396.6   328.6  4599.4  321.62  4690.6  319.26  4700.7   318.2  4728.6  317.42
  4794.5  316.47  4822.4  315.56  4903.5  315.79  4944.1  313.85  4971.9  312.49
    4977  310.95  4984.6  311.77  4994.7   311.2  4999.4   310.4  5002.1   309.9
  5005.4   310.4  5007.4   310.4  5015.1  313.62  5025.3  317.61  5035.5  317.14
  5045.7  318.94  5076.3  319.76  5086.5  320.92  5117.1  321.46  5127.3  322.56
  5157.9     323  5178.3  324.56  5188.5  324.46  5229.2   325.9  5259.8  327.89
#Mann= 3 ,-1 , 0
  4396.6      .1       0  4999.4     .07       0  5005.4      .1       0
Bank Sta=4944.1,5015.1
XS Rating Curve= 0 ,0
Exp/Cntr=0.3,0.1

Type RM Length L Ch R = 1 ,14377   ,564,564,564
BEGIN DESCRIPTION:
LEOPARD BRANCH 25.0
END DESCRIPTION:
XS GIS Cut Line= 3
       2201427.6     13275925.36      2201448.74     13275502.52
      2201392.54      13274996.7
#Sta/Elev= 30
  4411.1  327.65  4459.7  326.54  4469.7  325.57  4619.9  320.29    4740   316.9
  4770.1  314.72  4810.1  313.45  4850.2  312.79  4950.8  312.96  4977.8  311.72
  4982.8  313.01  4991.1  310.75  4998.2   307.5  5000.9     307  5004.2   307.5
  5011.2  308.41  5021.3  313.63  5031.3   314.4  5041.4  312.62  5051.5  312.87
  5061.5  316.12  5152.1   318.7  5192.3  320.81  5202.4  319.81  5212.4  321.26
  5242.6  322.43  5249.4  323.32  5323.1  325.66    5340  327.19  5343.4  326.63
#Mann= 3 ,-1 , 0
  4411.1      .1       0  4998.2     .07       0  5004.2      .1       0
Bank Sta=4982.8,5021.3
XS Rating Curve= 0 ,0
Exp/Cntr=0.3,0.1

Type RM Length L Ch R = 1 ,13813   ,472,472,472
BEGIN DESCRIPTION:
LEOPARD BRANCH 24.0
END DESCRIPTION:
XS GIS Cut Line= 3
      2201892.73     13275826.75      2201949.12     13275530.71
      2201794.49     13274940.29
#Sta/Elev= 30
  4462.6  325.09  4541.7  322.47  4696.6  318.28  4717.3  316.92  4786.3  314.66
  4831.9  314.04  4867.2  312.26  4907.6   311.2    4923  311.38  4933.3  310.75
  4942.8  308.14    4948  310.38    4954  310.54  4964.4   308.8  4980.2  306.25
    4983  305.75  4986.2  306.25  5005.7  306.69    5016  307.92  5023.6   307.2
  5028.8  308.38  5036.7   308.4  5047.1  309.39    5064  311.29  5109.6  313.16
  5139.7   313.6  5266.1   319.8  5295.2  320.06  5346.9  323.41  5374.3  323.25
#Mann= 5 ,-1 , 0
  4462.6      .1       0  4541.7     .05       0  4717.3      .1       0
  4980.2     .07       0  4986.2      .1       0
Bank Sta=4964.4,5047.1
XS Rating Curve= 0 ,0
Exp/Cntr=0.3,0.1

Type RM Length L Ch R = 1 ,13341   ,501,501,501
BEGIN DESCRIPTION:
LEOPARD BRANCH 23.0
END DESCRIPTION:
XS GIS Cut Line= 3
      2202787.69     13275746.82      2202337.72     13275196.85
       2202037.7     13274846.83
#Sta/Elev= 30
    4286  325.97  4326.8  324.62  4338.8  324.42  4620.5   313.7  4748.2  310.34
  4754.7  309.99    4769  306.93  4797.8  306.36  4804.2  308.71  4812.1   307.1
  4818.6  308.26  4826.5  307.74  4840.8  308.99  4954.2  307.08  4975.1  305.45
  4989.4  305.38  4993.4   303.9  5000.7  303.66  5003.5  303.16  5006.7  303.66
    5018  307.08  5110.2  309.53  5124.5  308.95  5259.5  314.47  5280.3  313.77
  5286.9  314.66  5294.6   313.8  5315.4   315.1  5323.1  316.81  5457.6  321.32
#Mann= 5 ,-1 , 0
    4286      .1       0  4326.8     .05       0  4338.8      .1       0
  5000.7     .07       0  5006.7      .1       0
Bank Sta=4954.2,5018
XS Rating Curve= 0 ,0
Exp/Cntr=0.3,0.1

Type RM Length L Ch R = 1 ,12840   ,402,402,402
BEGIN DESCRIPTION:
LEOPARD BRANCH 22.0
END DESCRIPTION:
XS GIS Cut Line= 4
      2203168.35     13275685.72      2203020.36     13275312.23
       2202611.6     13274854.14      2202182.17     13274657.02
#Sta/Elev= 30
  4280.4  323.82  4433.3  318.85  4440.5  319.38    4463  318.68  4494.3  316.81
    4536  316.51  4571.1  314.52  4914.7  306.52  4921.4  305.08  4928.9  306.19
  4935.6  305.39  4943.1  305.75  4949.8  303.98    4964  302.86  4978.2  303.73
  4984.9  302.59  4992.5  302.65  4996.2  300.91  4998.9  300.41  5002.2  300.91
  5006.7  302.38  5020.9  302.63  5035.1  304.99  5190.6   305.6  5247.4   306.2
  5275.9   307.5  5303.7  307.32    5711  319.37  5718.5  320.58  5768.6   321.7
#Mann= 3 ,-1 , 0
  4280.4      .1       0  4996.2     .07       0  5002.2      .1       0
Bank Sta=4943.1,5035.1
XS Rating Curve= 0 ,0
Exp/Cntr=0.3,0.1

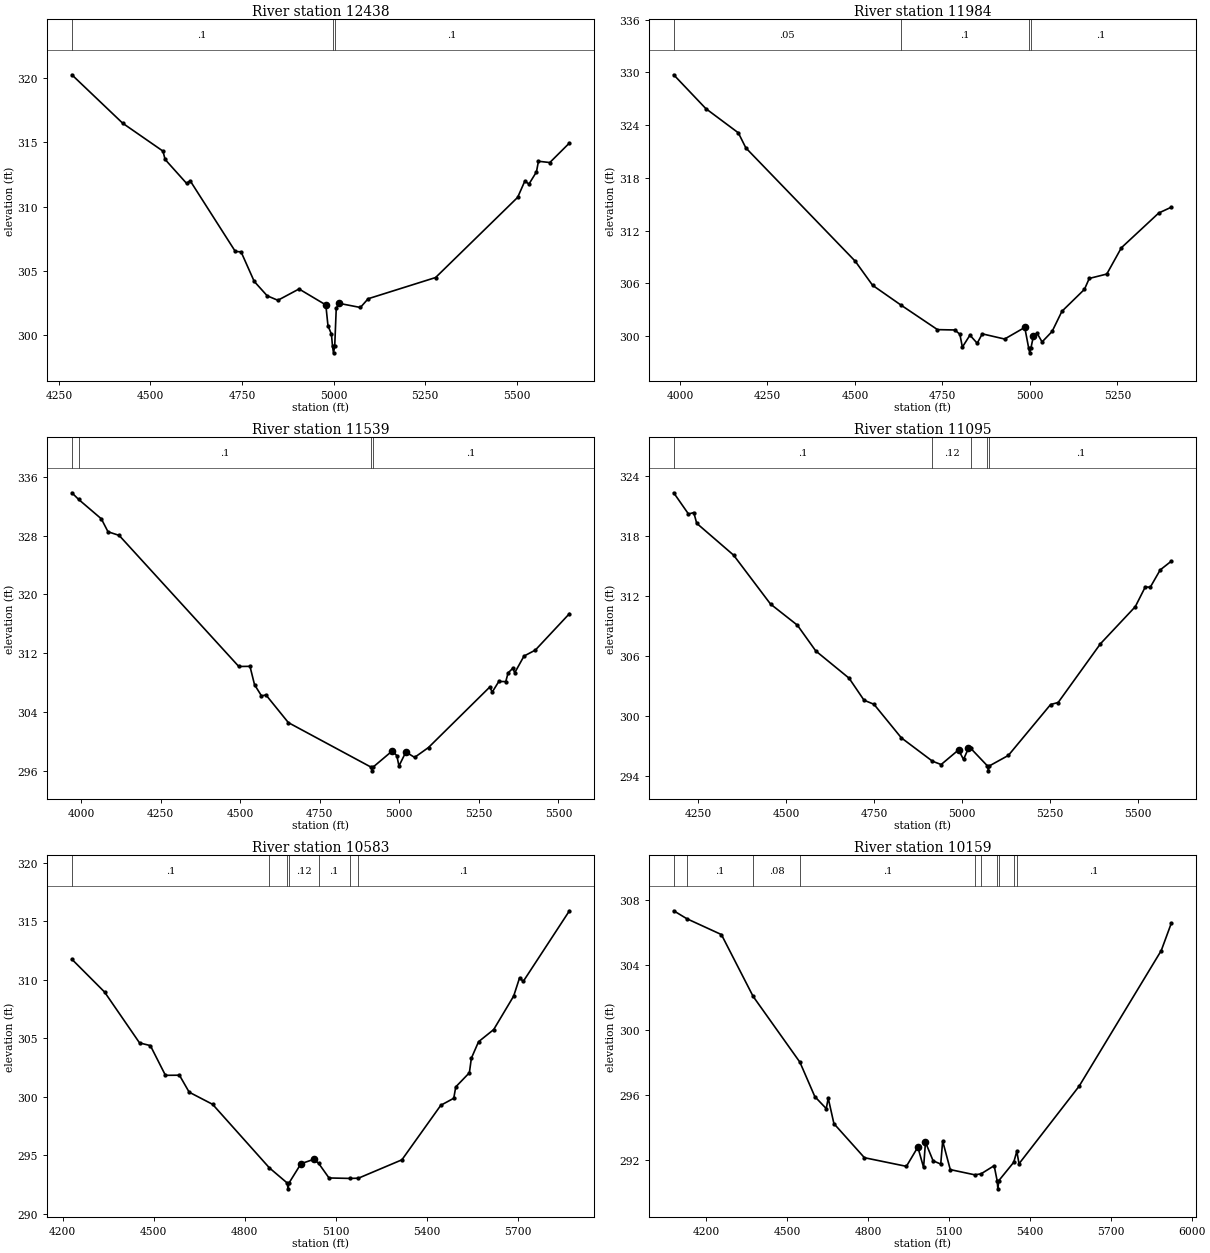
Type RM Length L Ch R = 1 ,12438   ,454,454,454
BEGIN DESCRIPTION:
Mapping XS 242bbf87
END DESCRIPTION:
XS GIS Cut Line= 4
      2203407.97     13275396.79      2203161.31     13274973.95
      2202949.88     13274635.66      2202794.88     13274191.79
#Sta/Elev= 30
  4285.6  320.27  4424.4   316.5  4534.3  314.33  4540.2  313.68  4598.8  311.82
  4608.7  312.02  4731.9  306.52  4747.6  306.49  4783.5  304.19  4818.9  303.07
  4848.1  302.72  4905.9   303.6    4979  302.36  4984.9  300.74  4994.4  300.08
  4997.3  299.13    5000  298.63  5003.3  299.13  5007.5   302.1  5015.6  302.48
  5073.4  302.16  5094.6  302.84  5278.7  304.49  5502.8  310.73  5522.3  311.99
  5533.8  311.77  5554.1  312.71  5559.6  313.54  5590.6  313.44  5644.2  314.96
#Mann= 3 ,-1 , 0
  4285.6      .1       0  4997.3     .07       0  5003.3      .1       0
Bank Sta=4979,5015.6
XS Rating Curve= 0 ,0
Exp/Cntr=0.3,0.1

Type RM Length L Ch R = 1 ,11984   ,445,445,445
BEGIN DESCRIPTION:
LEOPARD BRANCH 20.0
END DESCRIPTION:
XS GIS Cut Line= 3
      2204037.74     13275046.87      2203237.72     13274396.85
      2202937.73     13274146.86
#Sta/Elev= 30
  3982.3  329.73  4074.2  325.88  4166.9  323.13  4188.5  321.41  4500.9  308.53
  4550.5  305.79  4631.2  303.55  4735.8  300.75  4785.4  300.71  4799.8  300.22
  4806.9  298.76  4828.5  300.12  4849.3   299.2  4863.7  300.27  4927.6  299.68
  4985.1     301  4996.5  298.61  4999.2  298.11  5002.5  298.61  5009.9  300.02
  5020.3  300.34  5034.6  299.35  5063.2  300.54  5091.2  302.83  5155.6  305.33
  5169.3  306.57  5219.4  307.07  5261.1  310.06  5367.8  314.01  5403.6  314.67
#Mann= 4 ,-1 , 0
  3982.3     .05       0  4631.2      .1       0  4996.5     .07       0
  5002.5      .1       0
Bank Sta=4985.1,5009.9
XS Rating Curve= 0 ,0
Exp/Cntr=0.3,0.1

Type RM Length L Ch R = 1 ,11539   ,444,444,444
BEGIN DESCRIPTION:
LEOPARD BRANCH 19.0
END DESCRIPTION:
XS GIS Cut Line= 3
      2204287.74     13274946.88      2203587.72     13274146.85
      2203187.76     13273846.88
#Sta/Elev= 30
  3971.4  333.86  3992.8  332.95    4064  330.31  4084.9  328.55    4120  328.05
  4495.8  310.19  4530.9  310.21  4545.2  307.71    4567  306.19  4581.2  306.31
  4651.5  302.54  4911.4  296.47  4914.1  295.97  4917.4  296.47    4978  298.69
  4992.2  298.04  4998.9  296.63  5020.7  298.54    5048   297.8  5091.7  299.15
  5284.4   307.4  5291.7  306.69  5312.6  308.15  5334.4  308.13  5341.7  309.31
  5356.3  309.94  5362.6  309.34  5391.7  311.61  5427.2  312.42  5534.4  317.39
#Mann= 4 ,-1 , 0
  3971.4     .05       0  3992.8      .1       0  4911.4     .07       0
  4917.4      .1       0
Bank Sta=4978,5020.7
XS Rating Curve= 0 ,0
Exp/Cntr=0.3,0.1

Type RM Length L Ch R = 1 ,11095   ,512,512,512
BEGIN DESCRIPTION:
LEOPARD BRANCH 18.0
END DESCRIPTION:
XS GIS Cut Line= 3
      2204429.89     13274579.28      2204267.79     13274205.76
      2203534.82     13273515.07
#Sta/Elev= 30
  4179.9  322.28  4221.9  320.16  4237.1   320.3  4245.3  319.23  4350.1  316.05
  4455.1  311.16  4531.4  309.05  4583.8  306.47  4678.4  303.75  4720.9  301.55
  4749.2  301.14  4826.9  297.79  4915.5  295.45  4940.1  295.12  4989.5  296.58
  5003.7  295.63  5017.8  296.75  5024.2  296.74  5071.5  294.99  5074.2  294.49
  5077.5  294.99  5131.1  296.03  5251.3  301.12  5272.7  301.32  5392.9  307.19
    5492   310.9  5520.3  312.87  5534.5  312.84  5562.7  314.57  5594.2  315.44
#Mann= 5 ,-1 , 0
  4179.9      .1       0  4915.5     .12       0  5024.2      .1       0
  5071.5     .07       0  5077.5      .1       0
Bank Sta=4989.5,5017.8
XS Rating Curve= 0 ,0
Exp/Cntr=0.3,0.1

Type RM Length L Ch R = 1 ,10583   ,424,424,424
BEGIN DESCRIPTION:
LEOPARD BRANCH 17.0
END DESCRIPTION:
XS GIS Cut Line= 4
      2204782.28     13274318.56      2204641.31     13273944.99
      2204063.41     13273282.52      2203725.11     13273155.65
#Sta/Elev= 30
  4230.8  311.76  4338.5  308.96  4453.9  304.61  4489.5  304.38  4539.2  301.84
  4585.3  301.85  4617.4   300.4  4694.7  299.36  4881.8  293.93  4940.4  292.64
  4943.2  292.14  4946.4  292.64  4985.9  294.29  5027.9  294.66    5044  294.32
  5078.2  293.07    5147  293.03  5175.1  293.05  5318.4  294.62  5446.6  299.28
  5489.3  299.88  5495.9  300.85  5540.8  302.06  5547.3   303.3    5571  304.71
  5620.9  305.75  5686.7  308.61  5706.3  310.18  5718.2  309.86  5870.5   315.9
#Mann= 7 ,-1 , 0
  4230.8      .1       0  4881.8     .12       0  4940.4     .07       0
  4946.4     .12       0    5044      .1       0    5147     .12       0
  5175.1      .1       0
Bank Sta=4985.9,5027.9
XS Rating Curve= 0 ,0
Exp/Cntr=0.3,0.1

Type RM Length L Ch R = 1 ,10159   ,215,215,215
BEGIN DESCRIPTION:
LEOPARD BRANCH 16.0
END DESCRIPTION:
XS GIS Cut Line= 4
      2205317.88     13274156.41      2205148.74     13273846.33
      2204514.46     13273204.99      2204021.92     13272881.32
#Sta/Elev= 30
  4079.8  307.31  4128.9  306.82  4256.7  305.85  4374.2  302.06  4547.7  298.02
    4603  295.91  4645.5  295.17  4652.6  295.82  4673.8  294.25  4786.9  292.16
  4942.5  291.63  4984.9  292.81  5006.2  291.56  5013.2  293.11  5041.5  291.97
  5069.8  291.77  5076.9  293.18  5105.2  291.43  5195.9  291.11  5219.2  291.17
  5267.8  291.67  5278.9  290.75  5281.6  290.25  5284.9  290.75  5340.4  291.88
  5351.8  292.55    5360  291.79  5582.9  296.55  5887.3  304.87  5924.4  306.54
#Mann= 10 ,-1 , 0
  4079.8     .08       0  4128.9      .1       0  4374.2     .08       0
  4547.7      .1       0  5195.9     .08       0  5219.2     .12       0
  5278.9     .07       0  5284.9     .12       0  5340.4     .08       0
  5351.8      .1       0
Bank Sta=4984.9,5013.2
XS Rating Curve= 0 ,0
Exp/Cntr=0.3,0.1

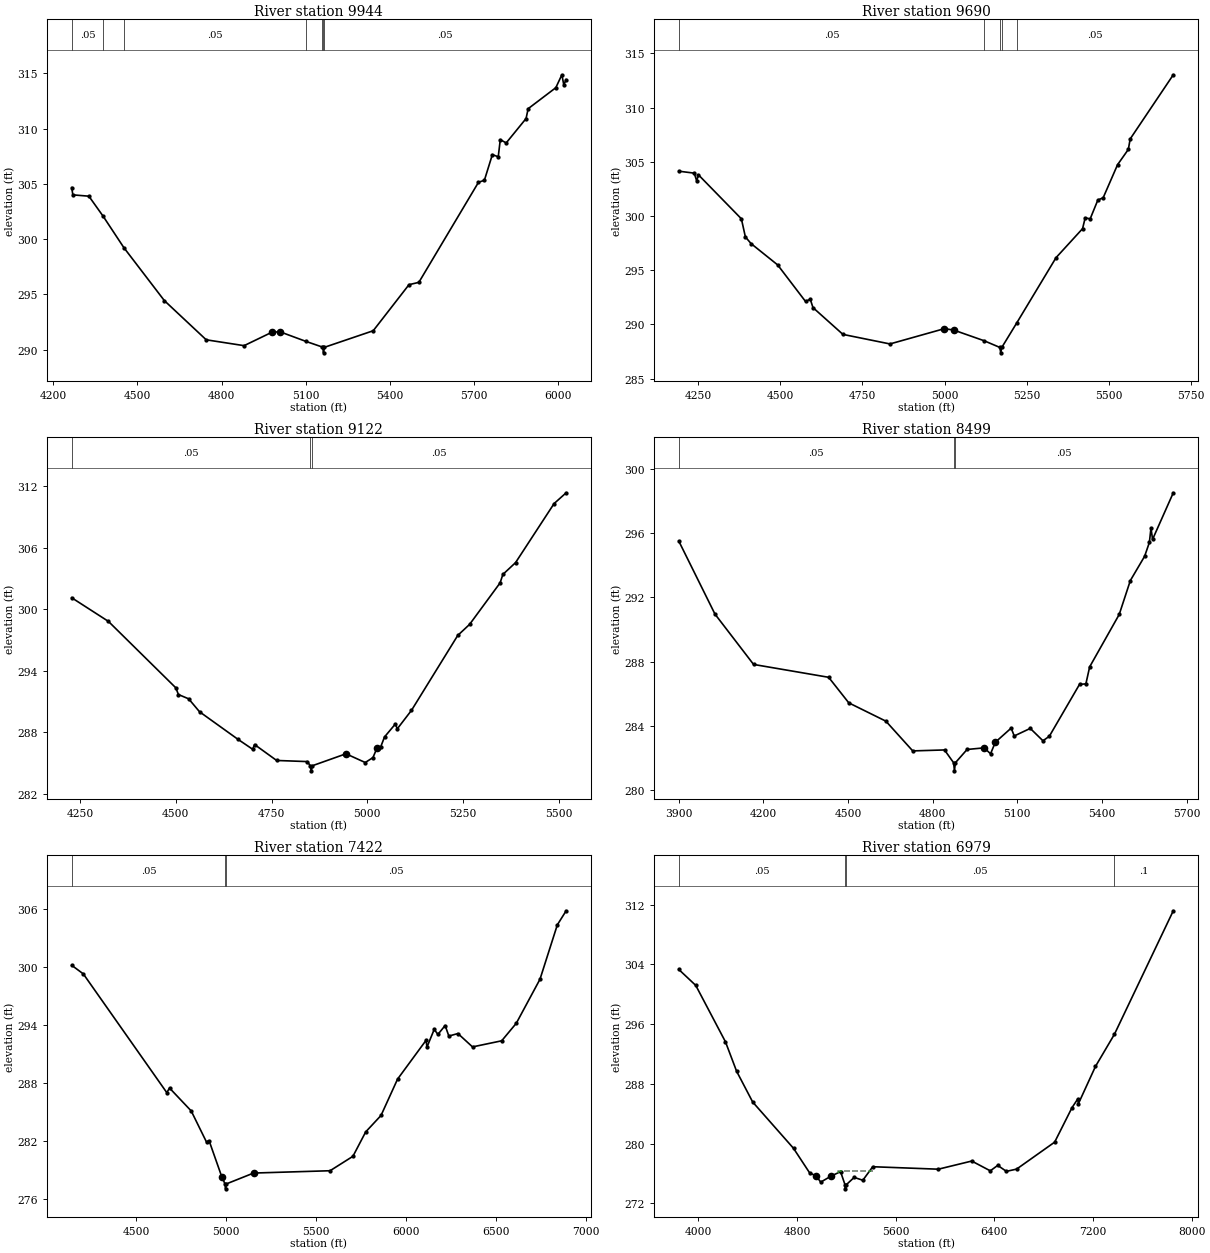
Type RM Length L Ch R = 1 ,9944    ,254,254,254
BEGIN DESCRIPTION:
Mapping XS 9e6a4136
END DESCRIPTION:
XS GIS Cut Line= 3
      2205374.26     13273846.32      2204796.36     13273169.76
      2204204.34      13272528.4
#Sta/Elev= 30
  4265.6  304.66  4269.7     304  4326.8  303.88  4377.8  302.06  4451.6  299.22
  4595.8  294.43  4745.1  290.88  4880.1  290.35  4978.9  291.56  5007.5  291.61
  5100.1  290.74  5156.2  290.25  5160.4   290.2  5163.2   289.7  5166.4   290.2
  5340.4   291.7  5467.9  295.87  5503.1  296.08  5715.7  305.14  5736.7  305.32
  5765.1  307.64  5786.1  307.45  5793.4     309  5814.4   308.7  5885.3  310.91
  5892.7   311.8  5991.3   313.7  6012.9  314.87  6019.7  313.97  6028.2  314.43
#Mann= 7 ,-1 , 0
  4265.6     .05       0  4377.8     .08       0  4451.6     .05       0
  5100.1      .1       0  5156.2     .05       0  5160.4     .03       0
  5166.4     .05       0
Bank Sta=4978.9,5007.5
XS Rating Curve= 0 ,0
Exp/Cntr=0.3,0.1

Type RM Length L Ch R = 1 ,9690    ,568,568,568
BEGIN DESCRIPTION:
LEOPARD BRANCH 15.0
END DESCRIPTION:
XS GIS Cut Line= 3
      2205416.55     13273839.27      2205021.88     13272993.57
      2204789.31     13272472.03
#Sta/Elev= 30
  4191.3  304.13  4238.1  303.95  4245.6  303.25  4251.1  303.79  4381.6  299.74
  4393.8  298.07  4411.2  297.45  4491.9  295.49  4576.7  292.12  4591.2  292.32
  4599.5  291.55  4690.6  289.08  4833.7   288.2  4999.2  289.61  5027.6  289.48
  5119.7   288.5  5167.9  287.88  5170.7  287.38  5173.9  287.88  5218.8  290.11
    5339  296.16  5419.6  298.83  5427.5  299.82  5442.8  299.74  5466.1  301.47
  5482.3  301.68  5526.1  304.73  5558.9  306.14  5564.4   307.1  5695.6  313.02
#Mann= 5 ,-1 , 0
  4191.3     .05       0  5119.7      .1       0  5167.9     .03       0
  5173.9      .1       0  5218.8     .05       0
Bank Sta=4999.2,5027.6
XS Rating Curve= 0 ,0
Exp/Cntr=0.3,0.1

Type RM Length L Ch R = 1 ,9122    ,623,623,623
BEGIN DESCRIPTION:
LEOPARD BRANCH 14.0
END DESCRIPTION:
XS GIS Cut Line= 3
      2205522.27     13273804.03      2205620.93     13273515.09
      2205515.22      13272535.5
#Sta/Elev= 30
  4228.4  301.11  4324.2  298.81  4500.2  292.34  4506.9  291.69  4533.7  291.27
  4562.1  290.01  4662.7  287.32  4700.7  286.36  4705.7  286.82  4763.3  285.27
  4843.7  285.16  4850.8  284.76  4853.6  284.26  4856.8  284.76  4944.3  285.92
  4994.6  285.07  5014.7  285.55  5024.8  286.44  5034.8  286.58  5044.9  287.56
  5073.2  288.82  5078.2  288.35  5115.3  290.15    5236  297.44    5267  298.52
  5346.6  302.56  5353.8  303.38  5386.9  304.53  5487.5  310.28    5519  311.33
#Mann= 3 ,-1 , 0
  4228.4     .05       0  4850.8     .03       0  4856.8     .05       0
Bank Sta=4944.3,5024.8
XS Rating Curve= 0 ,0
Exp/Cntr=0.3,0.1

Type RM Length L Ch R = 1 ,8499    ,1077,1077,1077
BEGIN DESCRIPTION:
LEOPARD BRANCH 13.0
END DESCRIPTION:
XS GIS Cut Line= 3
      2206433.18      13274373.1      2206249.64     13273602.23
      2205828.07     13272740.77
#Sta/Elev= 30
    3901   295.5  4029.1  290.96  4165.8  287.83  4431.7  287.03    4503  285.44
  4634.5   284.3  4729.6  282.45  4842.1  282.51  4874.5  281.71  4877.3  281.21
  4880.5  281.71  4922.1  282.54  4982.7  282.64  5005.2  282.27  5022.2  282.99
  5078.3  283.87  5089.1  283.38  5145.9  283.85  5190.9  283.08  5213.4  283.36
  5320.4  286.59  5342.9  286.62  5356.3  287.68    5461  290.94  5500.4  293.05
    5551  294.56  5567.8  295.42  5573.5  296.32  5579.1  295.61  5652.5  298.51
#Mann= 3 ,-1 , 0
    3901     .05       0  4874.5     .03       0  4880.5     .05       0
Bank Sta=4982.7,5022.2
XS Rating Curve= 0 ,0
Exp/Cntr=0.3,0.1

Type RM Length L Ch R = 1 ,7422    ,443,443,443
BEGIN DESCRIPTION:
LEOPARD BRANCH 12.0
END DESCRIPTION:
XS GIS Cut Line= 4
      2207175.78     13274109.55      2207305.97     13273588.76
      2206355.45     13272534.07      2205574.16     13272403.85
#Sta/Elev= 30
  4141.9  300.16  4206.5  299.27  4670.4  287.01  4685.8  287.48  4806.1  285.12
  4891.3   281.9  4905.5  282.05  4976.5   278.3  4994.4  277.57  4997.2  277.07
  5000.4  277.57  5152.9   278.7  5578.2  278.94  5705.2  280.43  5776.2  282.95
  5861.4  284.65  5953.3   288.4  6111.7  292.41  6116.8  291.71  6157.1  293.54
  6177.6  293.02  6217.9  293.94  6238.4  292.85  6288.9  293.11    6370  291.73
  6532.2  292.36  6613.3  294.17  6745.1  298.72  6841.6  304.34  6890.6  305.79
#Mann= 3 ,-1 , 0
  4141.9     .05       0  4994.4     .03       0  5000.4     .05       0
Bank Sta=4976.5,5152.9
XS Rating Curve= 0 ,0
Exp/Cntr=0.3,0.1

Type RM Length L Ch R = 1 ,6979    ,728,728,728
BEGIN DESCRIPTION:
LEOPARD BRANCH 11.0
END DESCRIPTION:
XS GIS Cut Line= 3
      2207501.28     13274213.73      2207227.85      13270802.3
      2207227.85     13270216.38
#Sta/Elev= 30
  3842.8  303.32  3980.1  301.19  4220.9  293.64  4311.2   289.7  4441.6  285.58
  4772.7  279.38  4903.1   276.1  4954.8  275.69  4993.4  274.86  5077.5  275.67
  5153.9  276.26    5191  274.46  5193.7  273.96    5197  274.46  5264.2  275.49
  5334.4  275.11  5414.7  276.92  5946.4  276.59  6217.3  277.68  6367.8  276.37
  6427.9   277.1  6498.2   276.3  6580.9   276.6  6889.4  280.21  7029.9  284.82
    7077     286    7082  285.36  7220.5  290.35    7374  294.65  7851.1  311.18
#Mann= 4 ,-1 , 0
  3842.8     .05       0    5191     .03       0    5197     .05       0
    7374      .1       0
#XS Ineff= 1 ,-1
 5132.32 5414.67  276.38
Permanent Ineff=
       F
Bank Sta=4954.8,5077.5
XS Rating Curve= 0 ,0
Exp/Cntr=0.3,0.1

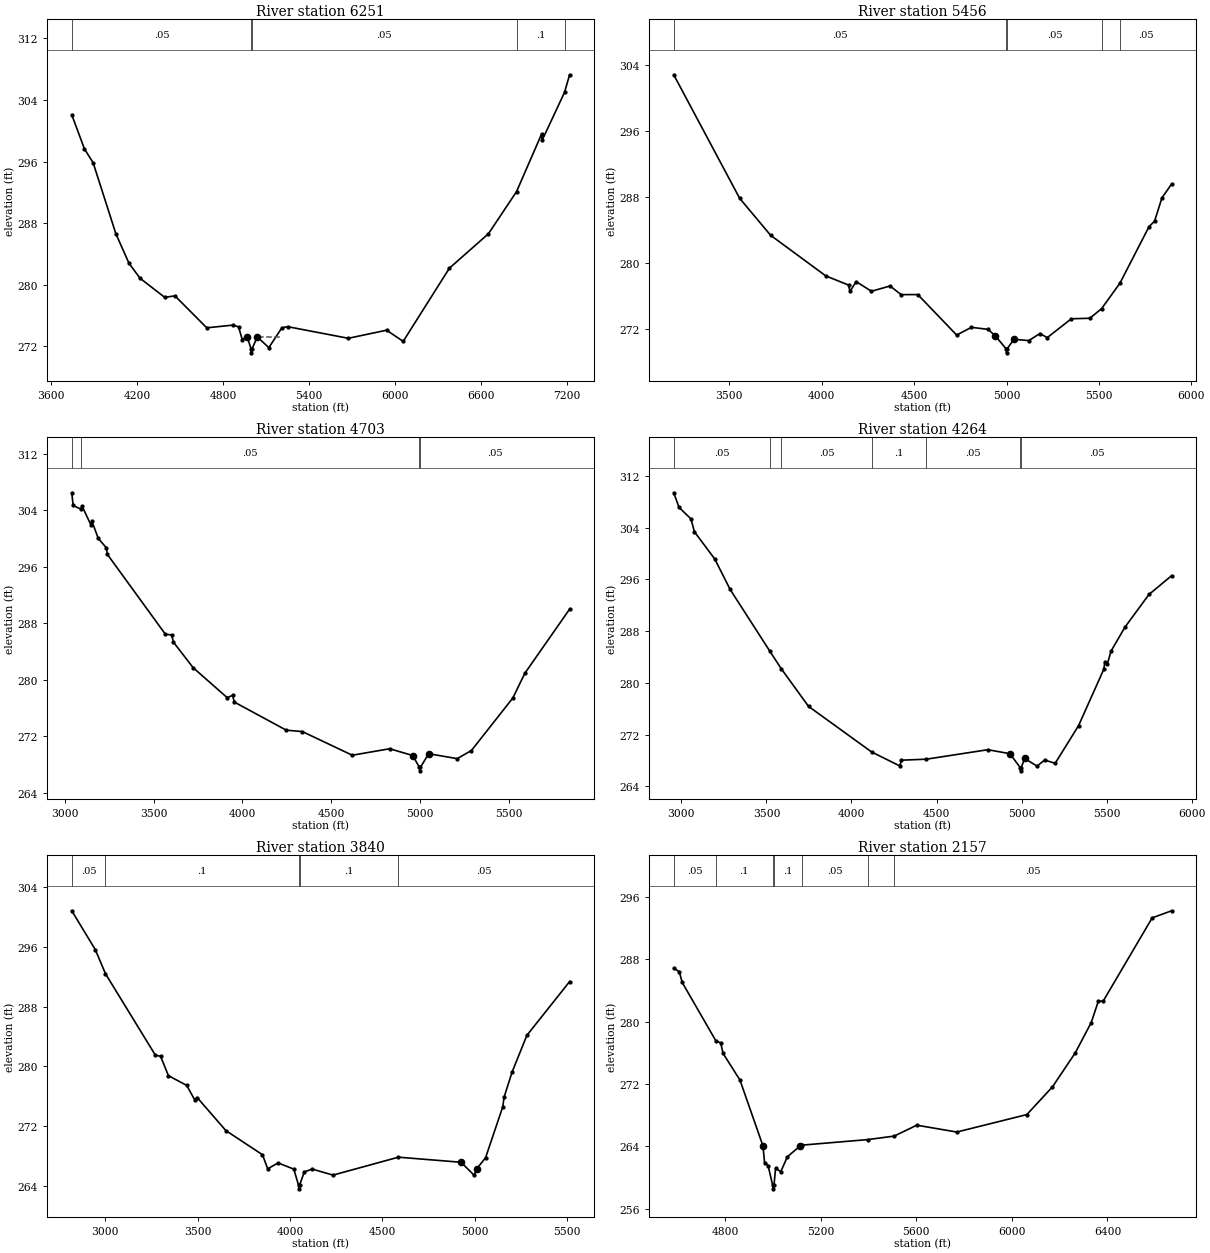
Type RM Length L Ch R = 1 ,6251    ,795,795,795
BEGIN DESCRIPTION:
LEOPARD BRANCH 8.0
END DESCRIPTION:
XS GIS Cut Line= 3
      2208191.39     13274135.61      2208152.33     13273484.59
      2207787.75     13270685.12
#Sta/Elev= 30
  3742.6  302.09  3831.5  297.64    3892  295.85  4050.6  286.63  4142.1   282.8
  4219.2  280.85  4391.5  278.37  4463.1  278.56    4685  274.41  4866.5  274.76
  4906.8  274.54  4932.9  272.89  4967.3  273.23  4994.6  271.66  4997.3  271.16
  5000.6  271.66  5037.9  273.22  5118.6  271.84  5209.3  274.41  5249.7  274.56
  5673.2  273.05  5940.4   274.1  6056.4  272.65  6379.1  282.16  6651.4  286.63
  6847.6   292.1    7022  299.56    7027   298.8  7183.2  305.02  7217.9  307.28
#Mann= 5 ,-1 , 0
  3742.6     .05       0  4994.6     .03       0  5000.6     .05       0
  6847.6      .1       0  7183.2     .05       0
#XS Ineff= 1 ,-1
 5046.67 5200.16  273.24
Permanent Ineff=
       F
Bank Sta=4967.3,5037.9
XS Rating Curve= 0 ,0
Exp/Cntr=0.3,0.1

Type RM Length L Ch R = 1 ,5456    ,753,753,753
BEGIN DESCRIPTION:
LEOPARD BRANCH 7.0
END DESCRIPTION:
XS GIS Cut Line= 3
       2208378.6     13274226.29      2208635.55     13273161.75
      2208580.49     13271565.01
#Sta/Elev= 30
  3199.7  302.86  3556.1  287.86  3723.7  283.36    4022  278.43  4145.5  277.31
  4152.8  276.54  4186.7  277.73    4269  276.56  4369.7   277.2  4429.8  276.15
  4519.8  276.16    4730  271.24    4810  272.18  4900.1  271.93  4940.1  271.12
  4997.1  269.58  4999.9  269.08  5003.1  269.58  5040.1  270.72  5120.2  270.57
  5180.2  271.42  5220.3  270.93  5350.3  273.22  5450.4  273.28  5514.4  274.46
  5613.3  277.55  5770.6  284.41  5800.6  285.08  5840.6  287.92  5892.5  289.58
#Mann= 5 ,-1 , 0
  3199.7     .05       0  4997.1     .03       0  5003.1     .05       0
  5514.4     .08       0  5613.3     .05       0
Bank Sta=4940.1,5040.1
XS Rating Curve= 0 ,0
Exp/Cntr=0.3,0.1

Type RM Length L Ch R = 1 ,4703    ,439,439,439
BEGIN DESCRIPTION:
LEOPARD BRANCH 6.0
END DESCRIPTION:
XS GIS Cut Line= 3
      2209406.39     13274354.72      2209241.21     13272996.58
       2209204.5       13271565.
#Sta/Elev= 30
  3039.8   306.5  3047.7   304.7  3090.1   304.2  3098.1   304.6  3148.2  301.92
  3153.2  302.47  3188.8  300.04  3234.9  298.69    3240  297.78  3566.8  286.45
  3601.8  286.37  3611.8  285.34  3722.7  281.72  3914.1  277.48  3944.3   277.8
  3954.4  276.85  4246.5  272.87  4337.2  272.67  4617.7  269.32  4827.8  270.24
  4957.9  269.28  4994.9  267.61  4997.6  267.11  5000.9  267.61  5047.9  269.53
  5207.9  268.84    5288  269.99  5521.1  277.44  5588.1  280.92    5840  290.01
#Mann= 4 ,-1 , 0
  3039.8      .1       0  3090.1     .05       0  4994.9     .03       0
  5000.9     .05       0
Bank Sta=4957.9,5047.9
XS Rating Curve= 0 ,0
Exp/Cntr=0.3,0.1

Type RM Length L Ch R = 1 ,4264    ,424,424,424
BEGIN DESCRIPTION:
LEOPARD BRANCH 5.0
END DESCRIPTION:
XS GIS Cut Line= 3
      2209993.68     13274317.98      2209920.27     13273088.34
      2209351.36      13271491.7
#Sta/Elev= 30
  2955.1   309.4  2986.3  307.14  3056.4  305.36  3076.4  303.38  3196.7  299.14
  3286.8  294.44  3521.3  284.85  3587.6  282.17  3747.6  276.36  4118.4  269.31
    4284  267.15  4294.1  268.04  4439.6  268.19  4802.1  269.66  4931.6  269.04
  4992.3  266.89  4995.1  266.39  4998.3  266.89  5017.8  268.31  5090.9  267.12
  5135.8  268.06  5197.5  267.55    5335  273.38  5483.6  282.11  5489.7  283.26
  5504.9  282.97  5526.1  284.91  5607.7  288.61    5749  293.67  5881.9  296.57
#Mann= 7 ,-1 , 0
  2955.1     .05       0  3521.3      .1       0  3587.6     .05       0
  4118.4      .1       0  4439.6     .05       0  4992.3     .03       0
  4998.3     .05       0
Bank Sta=4931.6,5017.8
XS Rating Curve= 0 ,0
Exp/Cntr=0.3,0.1

Type RM Length L Ch R = 1 ,3840    ,1683,1683,1683
BEGIN DESCRIPTION:
LEOPARD BRANCH 4.0
END DESCRIPTION:
XS GIS Cut Line= 3
      2211487.69     13273696.82      2209937.72     13272146.85
      2209887.72     13271646.83
#Sta/Elev= 30
  2818.6  300.85  2945.8  295.66  3001.1  292.42  3271.1  281.51  3299.4  281.36
  3341.8  278.76  3440.8  277.46  3483.2  275.56  3497.4  275.83  3652.9   271.4
  3850.9  268.17  3879.2  266.29  3935.8  267.07  4020.6  266.24  4045.9   264.1
  4048.7   263.6  4051.9   264.1  4077.2  265.86  4119.6  266.25  4232.8  265.44
  4586.6  267.84  4925.7  267.16  4996.4  265.42  5010.6  266.29  5058.3  267.76
  5151.3  274.58  5158.8  275.89  5201.5  279.21  5281.9  284.16  5513.1  291.36
#Mann= 5 ,-1 , 0
  2818.6     .05       0  3001.1      .1       0  4045.9     .03       0
  4051.9      .1       0  4586.6     .05       0
Bank Sta=4925.7,5010.6
XS Rating Curve= 0 ,0
Exp/Cntr=0.3,0.1

Type RM Length L Ch R = 1 ,2157    ,493,493,493
BEGIN DESCRIPTION:
LEOPARD BRANCH 3.0
END DESCRIPTION:
XS GIS Cut Line= 3
       2211637.7     13272546.84      2211287.72     13272346.85
      2209837.69     13271496.84
#Sta/Elev= 30
  4584.4  286.86  4607.4  286.45  4619.7  285.06  4761.3  277.53  4780.9   277.3
    4791  275.94  4861.5  272.53    4958  264.06  4964.5  261.94  4979.6  261.52
  4998.1  259.06  5000.9  258.56  5004.1  259.06  5010.7  261.19  5032.5  260.76
  5059.8  262.66  5112.6  264.05  5121.2  264.17  5396.3  264.88  5507.3  265.33
  5601.8  266.73  5769.2  265.85  6062.4  268.09  6169.8  271.65  6265.6  276.04
  6332.1  279.91  6361.4  282.61  6382.9   282.7  6587.1  293.34  6668.3  294.25
#Mann= 7 ,-1 , 0
  4584.4     .05       0  4761.3      .1       0  4998.1     .07       0
  5004.1      .1       0  5121.2     .05       0  5396.3      .1       0
  5507.3     .05       0
Bank Sta=4958,5112.6
XS Rating Curve= 0 ,0
Exp/Cntr=0.3,0.1

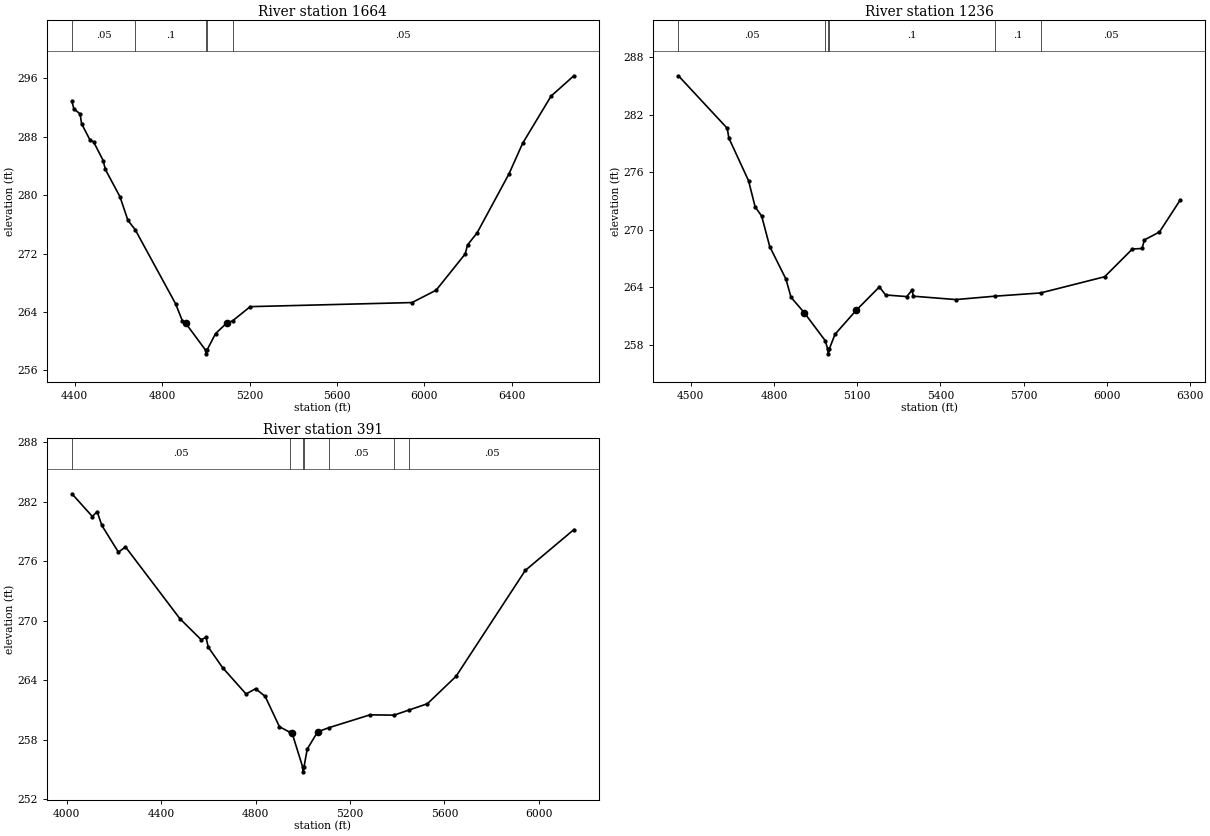
Type RM Length L Ch R = 1 ,1664    ,428,428,428
BEGIN DESCRIPTION:
LEOPARD BRANCH 2.0
END DESCRIPTION:
XS GIS Cut Line= 3
      2212037.76     13272146.87      2211487.72     13271896.85
       2209887.7     13271346.85
#Sta/Elev= 30
  4387.3  292.85  4396.1  291.84  4424.7  291.13  4431.3  289.81  4470.8  287.51
  4486.2  287.32  4530.1  284.75    4540  283.54    4607  279.79  4643.3  276.55
  4676.3  275.29  4861.9  265.09  4892.6  262.76    4908  262.43  4998.8  258.75
  5001.6  258.25  5004.8  258.75  5044.4  261.03  5095.6  262.48  5122.3  262.78
    5203  264.72  5943.2  265.28  6053.5  266.98  6186.4  271.95    6197  273.18
  6240.9  274.84  6386.6  282.92  6449.1  287.11  6579.3  293.59  6683.4  296.37
#Mann= 5 ,-1 , 0
  4387.3     .05       0  4676.3      .1       0  4998.8     .07       0
  5004.8      .1       0  5122.3     .05       0
Bank Sta=4908,5095.6
XS Rating Curve= 0 ,0
Exp/Cntr=0.3,0.1

Type RM Length L Ch R = 1 ,1236    ,845,845,845
BEGIN DESCRIPTION:
Mapping XS bedc91b8
END DESCRIPTION:
XS GIS Cut Line= 2
      2212205.07     13271760.25      2210538.41     13271057.13
#Sta/Elev= 30
  4455.9  286.08    4632   280.6  4637.5   279.6  4708.6  275.14  4732.3  272.42
    4756  271.44  4785.1  268.26  4843.7  264.86  4861.7  262.98  4908.9  261.39
  4985.6  258.43  4993.6  257.58  4996.3  257.08  4999.6  257.58  5020.3  259.12
  5096.9  261.63  5180.2  264.06  5202.6  263.22  5279.2  263.05  5297.5  263.72
  5302.9  263.09    5456  262.74  5595.4  263.09  5761.1  263.43  5992.1  265.12
  6091.9  268.01  6126.9  268.07  6135.3  268.96  6189.6  269.79  6264.8  273.14
#Mann= 6 ,-1 , 0
  4455.9     .05       0  4985.6      .1       0  4993.6     .03       0
  4999.6      .1       0  5595.4      .1       0  5761.1     .05       0
Bank Sta=4908.9,5096.9
XS Rating Curve= 0 ,0
Exp/Cntr=0.3,0.1

Type RM Length L Ch R = 1 ,391     ,0,0,0
BEGIN DESCRIPTION:
LEOPARD BRANCH 1.0
END DESCRIPTION:
XS GIS Cut Line= 3
      2212205.06      13271543.2      2212152.98     13270822.75
      2210764.06     13270614.41
#Sta/Elev= 30
  4021.6  282.78  4108.2  280.49  4128.2  280.99  4148.3  279.59  4218.5   276.9
  4248.5  277.43  4479.1   270.2  4569.4  268.08  4589.4  268.33  4599.5  267.33
  4659.6  265.28  4759.4  262.62  4799.8  263.15  4840.3  262.38  4900.9  259.32
  4946.7  258.75  4954.4  258.68  4999.1  255.28  5001.8  254.78  5005.1  255.28
  5018.4  257.06  5062.7  258.81  5109.7  259.22  5284.7  260.52  5386.3  260.49
  5449.5     261  5527.9  261.64  5649.2   264.4  5942.5  275.06  6148.4  279.17
#Mann= 7 ,-1 , 0
  4021.6     .05       0  4946.7      .1       0  4999.1     .07       0
  5005.1      .1       0  5109.7     .05       0  5386.3      .1       0
  5449.5     .05       0
Bank Sta=4954.4,5062.7
XS Rating Curve= 0 ,0
Exp/Cntr=0.3,0.1

Chan Stop Cuts=-1
Use User Specified Reach Order=0
Composite Channel Slope=5