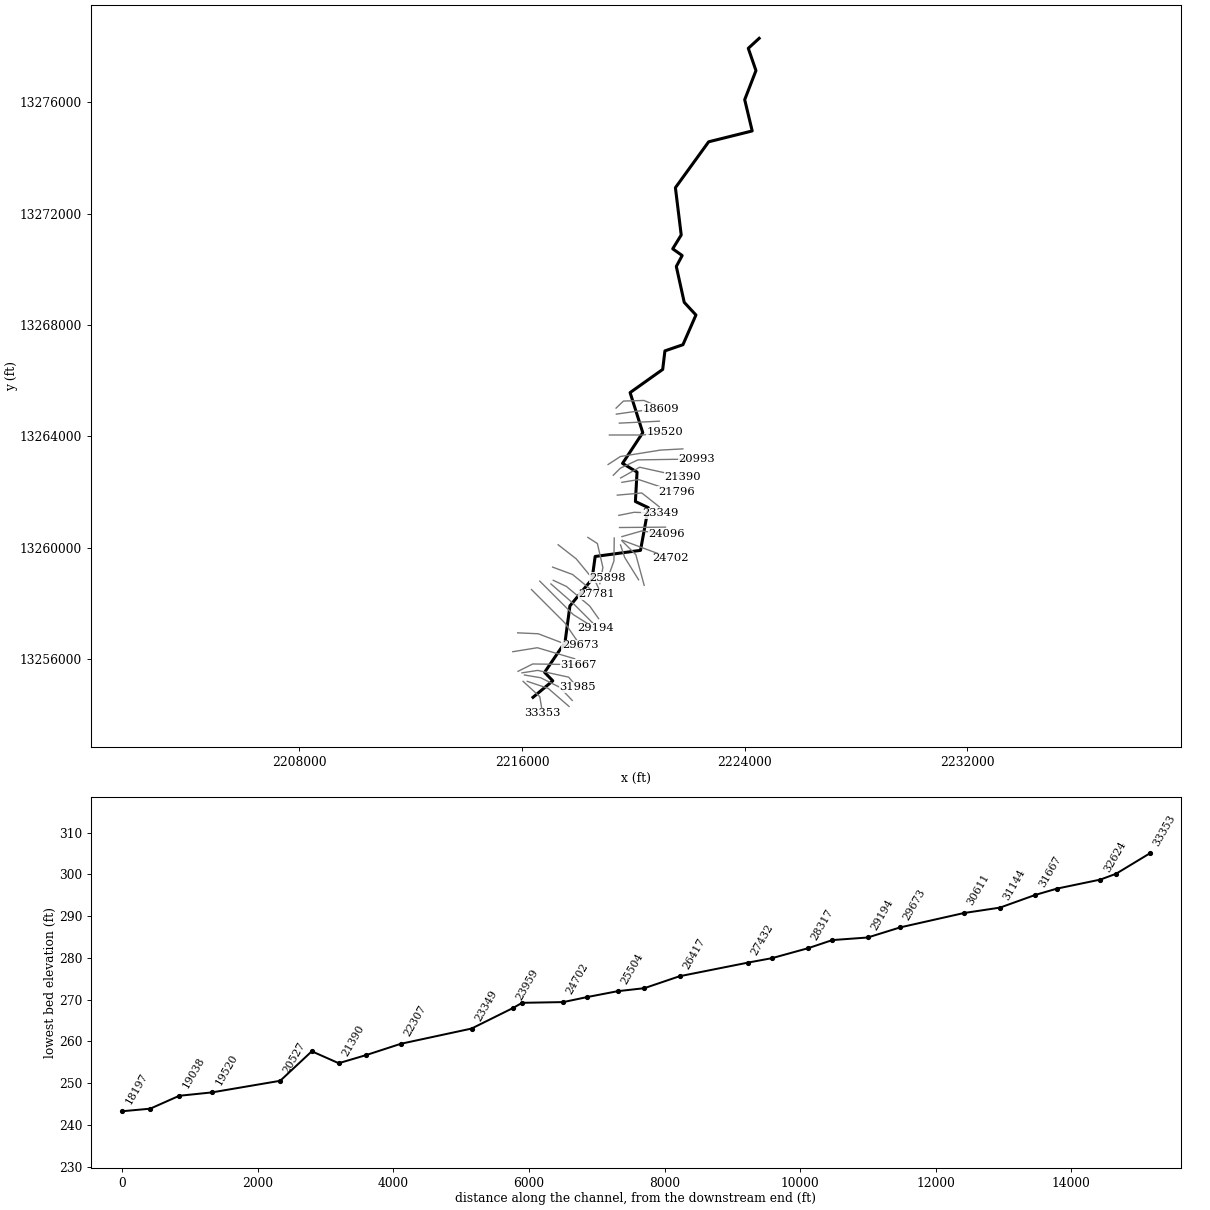
--- LEOPARD CREEK.prj (project) ---

Proj Title=LEOPARD CREEK Base Level Engineering
Current Plan=p01
Default Exp/Contr=0.3,0.1
English Units
Geom File=g01
Flow File=f01
Plan File=p01
Y Axis Title=Elevation
X Axis Title(PF)=Main Channel Distance
X Axis Title(XS)=Station
BEGIN DESCRIPTION:
LEOPARD CREEK
END DESCRIPTION:
DSS Export Rating Curves= 0
DSS Export Rating Curve Sorted= 0
DSS Export Volume Flow Curves= 0
DXF OffsetX= 0
DXF OffsetY= 0
DXF ScaleX= 1
DXF ScaleY= 10

--- LEOPARD CREEK.p01 (plan) ---

Plan Title=Multiple Run
Short Identifier=Multiple
Geom File=g01
Flow File=f01
Subcritical Flow
K Sum by GR= 0
Std Step Tol= 0.01
Critical Tol= 0.01
Num of Std Step Trials= 20
Max Error Tol= 0.3
Flow Tol Ratio= 0.001
Split Flow NTrial= 30
Split Flow Tol= 0.02
Split Flow Ratio= 0.02
Log Output Level= 0
Friction Slope Method= 1
Unsteady Friction Slope Method= 2
Unsteady Bridges Friction Slope Method= 1
Parabolic Critical Depth
Global Vel Dist=  1 , 1 , 1
Global Log Level= 0
CheckData=True
Encroach Param= -1, 0, 0, 0
BEGIN DESCRIPTION:
Multiple Run
END DESCRIPTION:

--- LEOPARD CREEK.f01 (steady flow) ---

Flow Title=Multiple
Program Version=4.10
Number of Profiles= 7
Profile Names=10-year,25-year,50-year,1pct_min,100-year,1pct_plu,500-year
River Rch & RM=LEOPARD CREEK,Reach-1         ,33353
     356     513     648     603     815    1103    1311
River Rch & RM=LEOPARD CREEK,Reach-1         ,32856
     367     526     663     615     831    1124    1328
River Rch & RM=LEOPARD CREEK,Reach-1         ,29673
     568     829    1057     989    1338    1809    2178
River Rch & RM=LEOPARD CREEK,Reach-1         ,28317
     568     829    1057     989    1338    1809    2178
River Rch & RM=LEOPARD CREEK,Reach-1         ,25504
     818    1210    1554    1465    1981    2679    3271
River Rch & RM=LEOPARD CREEK,Reach-1         ,25059
     818    1210    1554    1465    1981    2679    3271
River Rch & RM=LEOPARD CREEK,Reach-1         ,19520
     909    1350    1740    1645    2225    3009    3695
River Rch & RM=LEOPARD CREEK,Reach-1         ,19038
     942    1395    1794    1692    2288    3094    3780
River Rch & RM=LEOPARD CREEK,Reach-1         ,13132
    1026    1523    1962    1853    2506    3389    4153
River Rch & RM=LEOPARD CREEK,Reach-1         ,11586
    1048    1551    1994    1879    2541    3437    4193
River Rch & RM=LEOPARD CREEK,Reach-1         ,3165
    1076    1592    2047    1927    2607    3525    4296
Boundary for River Rch & Prof#=LEOPARD CREEK,Reach-1         , 1
Up Type= 0
Dn Type= 3
Dn Slope=0.005
Boundary for River Rch & Prof#=LEOPARD CREEK,Reach-1         , 2
Up Type= 0
Dn Type= 3
Dn Slope=0.005
Boundary for River Rch & Prof#=LEOPARD CREEK,Reach-1         , 3
Up Type= 0
Dn Type= 3
Dn Slope=0.005
Boundary for River Rch & Prof#=LEOPARD CREEK,Reach-1         , 4
Up Type= 0
Dn Type= 3
Dn Slope=0.005
Boundary for River Rch & Prof#=LEOPARD CREEK,Reach-1         , 5
Up Type= 0
Dn Type= 3
Dn Slope=0.005
Boundary for River Rch & Prof#=LEOPARD CREEK,Reach-1         , 6
Up Type= 0
Dn Type= 3
Dn Slope=0.005
Boundary for River Rch & Prof#=LEOPARD CREEK,Reach-1         , 7
Up Type= 0
Dn Type= 3
Dn Slope=0.005
DSS Import GetInterval= 0
DSS Import GetPeak= 0
DSS Import FillOption= 0

--- LEOPARD CREEK.g01 (geometry) ---

Geom Title=Existing Conditions
Program Version=4.10

River Reach=LEOPARD CREEK   ,Reach-1
Reach XY= 30
      2216393.97     13254623.39      2217104.13     13255216.32
       2216809.9     13255521.15      2217543.84     13256598.46
      2217719.38     13257908.02      2218515.23     13258867.91
      2218626.72     13259683.43      2220255.63     13259902.83
      2220536.59     13261436.69      2220072.52     13261657.41
      2220131.28     13262714.58      2219611.39     13263027.38
      2220336.95      13264131.4      2219882.05      13265570.3
      2221052.88     13266402.94      2221132.95     13267069.41
      2221780.03     13267290.73      2222247.13      13268357.6
      2221826.49     13268812.48        2221542.     13270101.45
      2221752.88     13270495.12       2221412.6      13270735.4
      2221718.16     13271231.79      2221509.42     13272931.06
      2222703.57     13274579.85      2224268.42     13274969.85
      2223998.44     13276093.25      2224403.39     13277138.15
      2224127.59     13277937.86      2224517.72     13278296.85

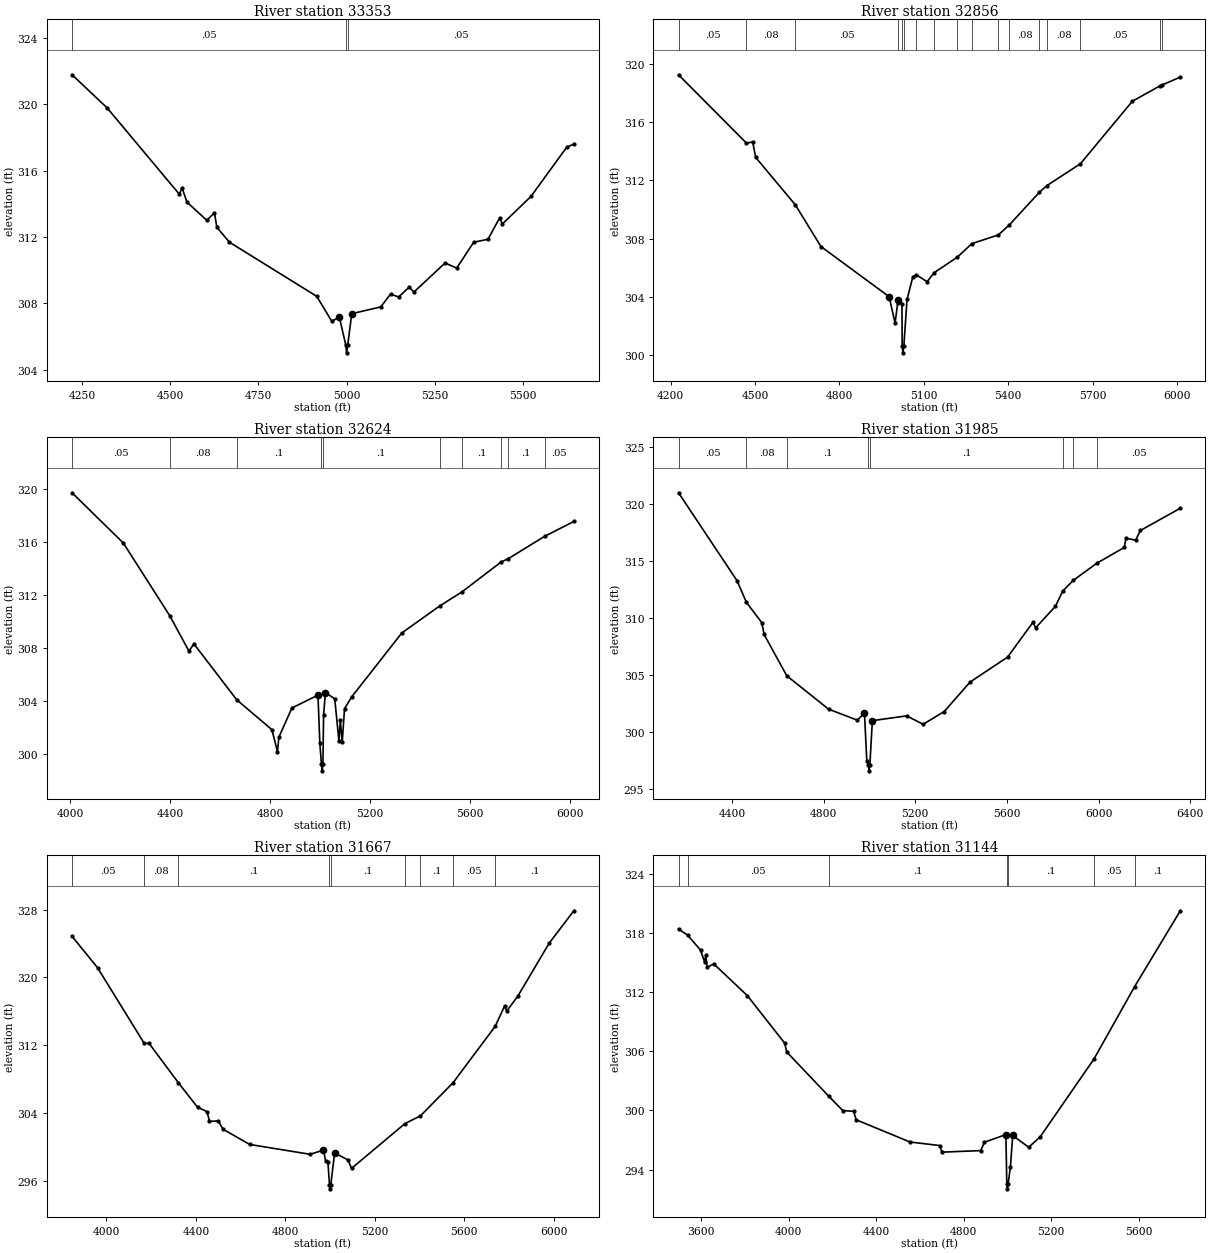
Type RM Length L Ch R = 1 ,33353   ,497,497,497
BEGIN DESCRIPTION:
LEOPARD CREEK 51.0
END DESCRIPTION:
XS GIS Cut Line= 3
      2216037.69     13255196.88      2216637.72     13254646.85
      2216737.73     13254046.81
#Sta/Elev= 30
  4221.8  321.79  4320.8   319.8  4526.1  314.58  4533.5  314.98  4547.4  314.11
  4603.8  313.01  4625.4  313.47  4632.2  312.59    4668  311.69  4915.2  308.43
  4957.8  306.93  4979.4  307.16  4997.3  305.52  5000.1  305.02  5003.3  305.52
  5014.5  307.38  5096.6  307.79  5124.5  308.56  5147.3  308.39  5177.7  308.99
  5190.4  308.68  5279.1  310.44    5312  310.13  5360.2  311.69  5400.7  311.87
  5433.7  313.16  5441.3  312.79  5522.4  314.45  5623.8  317.42  5644.1  317.61
#Mann= 3 ,-1 , 0
  4221.8     .05       0  4997.3     .03       0  5003.3     .05       0
Bank Sta=4979.4,5014.5
XS Rating Curve= 0 ,0
Exp/Cntr=0.3,0.1

Type RM Length L Ch R = 1 ,32856   ,232,232,232
BEGIN DESCRIPTION:
LEOPARD CREEK 50.0
END DESCRIPTION:
XS GIS Cut Line= 3
      2216187.69     13255196.86      2216937.72     13254946.85
      2217687.74     13254296.83
#Sta/Elev= 30
  4228.2  319.26  4469.1  314.57  4491.8  314.63  4502.3  313.58  4642.7  310.33
  4734.2  307.45  4976.6     304  4997.7  302.18    5007  303.59  5008.3  303.79
  5022.1  303.52  5022.9  300.64  5025.7  300.14  5028.9  300.64  5040.2  303.81
    5061  305.38  5073.2  305.51  5111.4  305.03  5137.1  305.66    5219  306.72
  5270.5  307.65  5364.7  308.25  5403.9  308.94  5510.4  311.18  5537.2  311.64
  5656.2  313.14  5840.8  317.44  5937.4  318.48  5947.7  318.57  6011.3   319.1
#Mann= 17 ,-1 , 0
  4228.2     .05       0  4469.1     .08       0  4642.7     .05       0
    5007     .08       0  5022.9     .03       0  5028.9     .08       0
  5073.2     .05       0  5137.1     .08       0    5219     .05       0
  5270.5     .08       0  5364.7     .05       0  5403.9     .08       0
  5510.4     .05       0  5537.2     .08       0  5656.2     .05       0
  5937.4      .1       0  5947.7     .05       0
Bank Sta=4976.6,5008.3
XS Rating Curve= 0 ,0
Exp/Cntr=0.3,0.1

Type RM Length L Ch R = 1 ,32624   ,639,639,639
BEGIN DESCRIPTION:
LEOPARD CREEK 49.0
END DESCRIPTION:
XS GIS Cut Line= 4
      2216086.94     13255425.54      2216670.29     13255326.48
      2217352.76     13254985.25      2217803.36     13254512.66
#Sta/Elev= 30
  4006.9  319.68  4211.9   315.9  4397.3  310.44  4474.3  307.77  4494.6   308.3
  4666.1  304.09  4806.4  301.85  4828.7   300.2  4834.3  301.28  4886.4  303.48
  4990.8  304.45  4998.2  300.84  5004.6  299.25  5007.4  298.75  5010.6  299.25
  5013.2  302.95  5020.6  304.64  5057.9  304.17  5074.7  300.99  5080.3  302.55
  5087.7  300.89  5097.1  303.43    5125   304.3  5326.3  309.13  5477.8  311.16
  5566.3  312.21  5723.4  314.47  5750.5   314.7  5897.4   316.4  6014.6  317.52
#Mann= 10 ,-1 , 0
  4006.9     .05       0  4397.3     .08       0  4666.1      .1       0
  5004.6     .07       0  5010.6      .1       0  5477.8     .05       0
  5566.3      .1       0  5723.4     .05       0  5750.5      .1       0
  5897.4     .05       0
Bank Sta=4990.8,5020.6
XS Rating Curve= 0 ,0
Exp/Cntr=0.3,0.1

Type RM Length L Ch R = 1 ,31985   ,318,318,318
BEGIN DESCRIPTION:
Mapping XS e98cba3b
END DESCRIPTION:
XS GIS Cut Line= 4
      2215998.84      13255502.6      2216560.22     13255590.66
      2217671.98     13255348.49      2217991.16     13254985.28
#Sta/Elev= 30
  4167.1  321.02  4422.2   313.3  4463.4  311.39  4530.4  309.61  4540.5  308.57
  4639.5  304.94  4821.7  302.01  4947.7  301.04  4978.4  301.68  4988.6  297.46
  4995.9  297.09  4998.6  296.59  5001.9  297.09  5012.9     301  5162.6  301.42
  5234.3  300.68  5326.4   301.8  5439.3  304.39  5602.7  306.58  5713.3  309.63
  5725.5  309.16  5811.5  311.04  5843.8  312.39  5889.4  313.32  5992.3  314.83
  6112.5  316.22  6119.2  317.02  6161.8  316.86  6182.7  317.71  6356.7  319.66
#Mann= 8 ,-1 , 0
  4167.1     .05       0  4463.4     .08       0  4639.5      .1       0
  4995.9     .07       0  5001.9      .1       0  5843.8     .05       0
  5889.4      .1       0  5992.3     .05       0
Bank Sta=4978.4,5012.9
XS Rating Curve= 0 ,0
Exp/Cntr=0.3,0.1

Type RM Length L Ch R = 1 ,31667   ,523,523,523
BEGIN DESCRIPTION:
LEOPARD CREEK 48.0
END DESCRIPTION:
XS GIS Cut Line= 3
      2215855.75     13255557.64       2216384.1     13255821.82
      2218037.69     13255796.86
#Sta/Elev= 30
  3846.3  324.84  3960.3  321.14  4169.2  312.22  4190.3  312.24  4321.8  307.59
  4407.5   304.7  4450.6  304.18  4460.6  303.03  4500.6   303.1  4520.6  302.13
  4640.7  300.32  4910.7  299.16  4970.7  299.65  4980.7  298.35  4990.7  298.21
  4997.7  295.59  5000.5  295.09  5003.7  295.59  5020.7  299.32  5080.7  298.49
  5096.4   297.5  5335.4  302.78  5404.6  303.69  5550.4  307.59    5739  314.24
  5780.8  316.62  5790.8  316.04  5840.8  317.82  5980.8  324.05  6090.8  327.85
#Mann= 9 ,-1 , 0
  3846.3     .05       0  4169.2     .08       0  4321.8      .1       0
  4997.7     .07       0  5003.7      .1       0  5335.4     .05       0
  5404.6      .1       0  5550.4     .05       0    5739      .1       0
Bank Sta=4970.7,5020.7
XS Rating Curve= 0 ,0
Exp/Cntr=0.3,0.1

Type RM Length L Ch R = 1 ,31144   ,533,533,533
BEGIN DESCRIPTION:
Mapping XS 6c041af5
END DESCRIPTION:
XS GIS Cut Line= 3
      2215668.57     13256262.11      2216549.21     13256405.21
      2217892.17     13256008.93
#Sta/Elev= 30
  3497.5  318.38  3538.5  317.78  3597.9  316.26  3616.9  315.02  3621.9  315.72
  3628.3  314.51  3658.7  314.85  3811.7  311.64  3982.9   306.8  3991.3  305.93
  4182.7  301.46  4247.7  299.98    4297   299.9  4309.3  299.04    4555  296.79
  4690.5  296.43  4700.9  295.76  4878.2  295.92    4895  296.77  4992.9  297.54
  4997.2  292.54  4999.9  292.04  5003.2  292.54  5013.7  294.27  5024.1  297.45
  5097.1  296.26  5149.3   297.3  5395.7  305.22  5580.8  312.54  5789.9  320.24
#Mann= 7 ,-1 , 0
  3497.5     .08       0  3538.5     .05       0  4182.7      .1       0
  4997.2     .07       0  5003.2      .1       0  5395.7     .05       0
  5580.8      .1       0
Bank Sta=4992.9,5024.1
XS Rating Curve= 0 ,0
Exp/Cntr=0.3,0.1

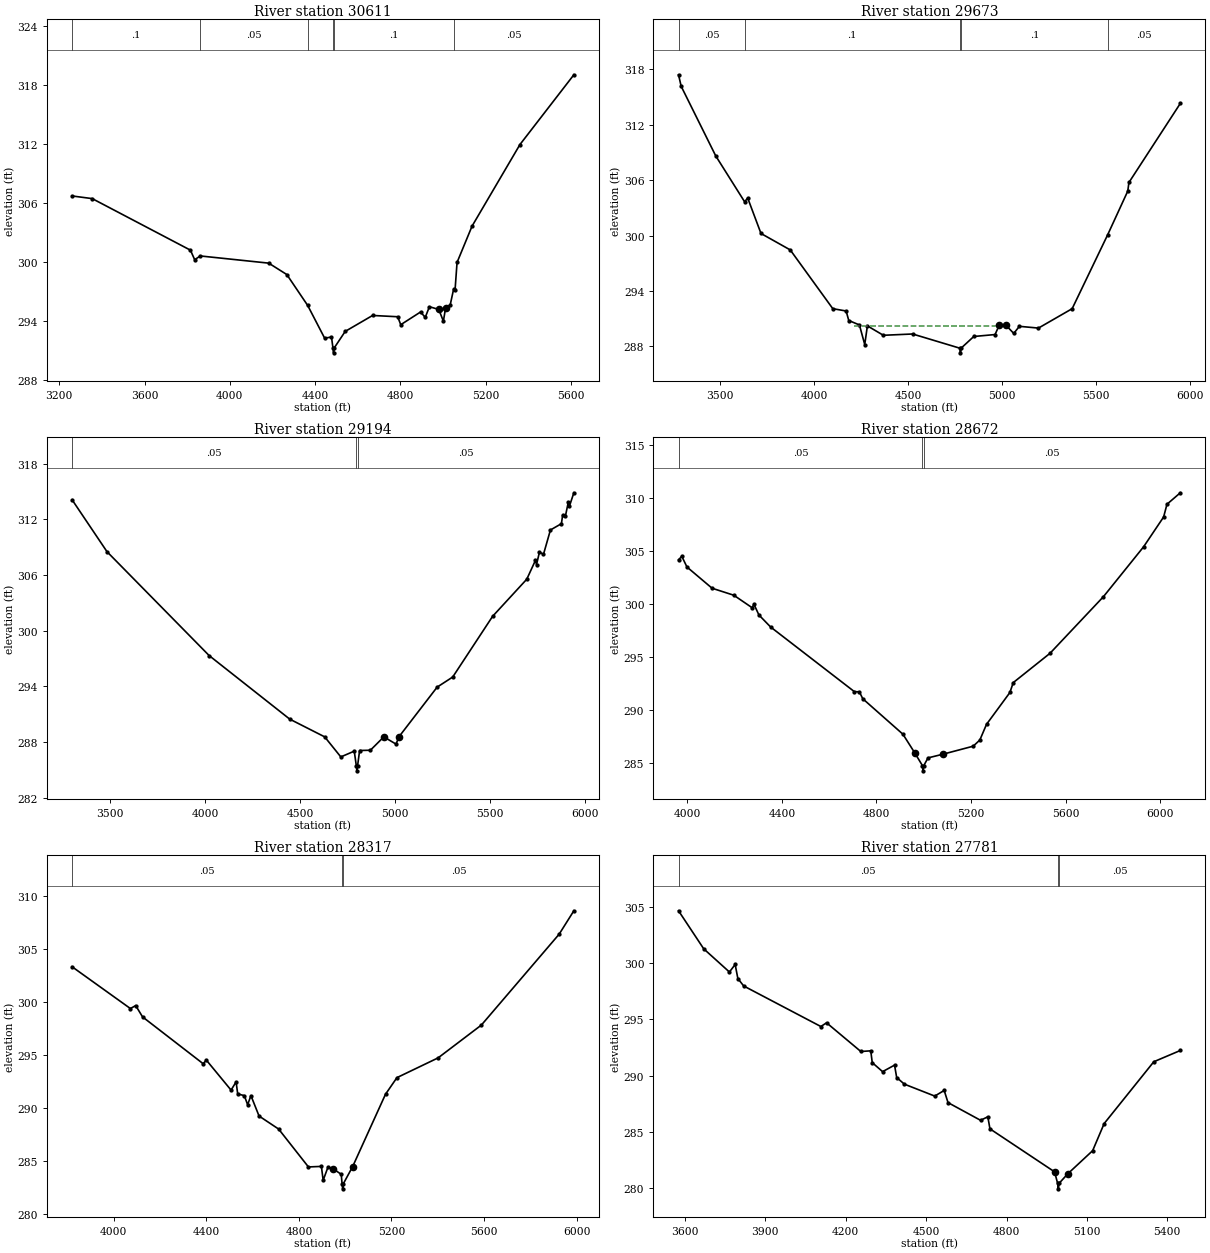
Type RM Length L Ch R = 1 ,30611   ,938,938,938
BEGIN DESCRIPTION:
LEOPARD CREEK 47.0
END DESCRIPTION:
XS GIS Cut Line= 3
      2215843.36     13256939.72      2216581.23     13256907.16
      2218089.52     13256332.06
#Sta/Elev= 30
  3260.2  306.69  3354.7  306.42  3815.1  301.18  3835.1  300.21  3861.4  300.59
  4182.2  299.86  4267.1   298.7  4364.9  295.56  4444.5  292.23  4476.6  292.35
  4483.4  291.24  4486.2  290.74  4489.4  291.24  4540.9  292.92  4669.3  294.54
    4787  294.41  4801.3   293.6    4894  294.89  4916.3  294.35  4935.7  295.43
  4979.6  295.15  5001.2  293.96  5011.8  295.33  5033.2  295.61  5048.8  297.18
  5056.1  297.17  5065.3  299.93  5135.6  303.62  5360.3  311.92    5613  319.01
#Mann= 6 ,-1 , 0
  3260.2      .1       0  3861.4     .05       0  4364.9      .1       0
  4483.4     .07       0  4489.4      .1       0  5048.8     .05       0
Bank Sta=4979.6,5011.8
XS Rating Curve= 0 ,0
Exp/Cntr=0.3,0.1

Type RM Length L Ch R = 1 ,29673   ,479,479,479
BEGIN DESCRIPTION:
LEOPARD CREEK 46.0
END DESCRIPTION:
XS GIS Cut Line= 3
      2216337.72     13258496.86      2217537.72     13257296.85
      2218087.73     13256496.84
#Sta/Elev= 30
  3279.5  317.41  3293.6  316.16  3477.5  308.62  3630.9  303.66  3647.2  304.07
  3717.9  300.23  3873.5  298.45  4099.7  292.09  4170.5  291.84  4184.6  290.81
  4241.2  290.33  4269.5  288.21  4283.6  290.23  4368.4  289.21    4524  289.35
  4775.6  287.81  4778.3  287.31  4781.6  287.81  4849.3  289.08  4962.4  289.29
    4984  290.28  5019.9  290.31  5061.8  289.41  5091.6  290.18  5193.1  289.99
  5372.3  292.09  5560.9  300.08    5668  304.82  5674.1  305.75  5947.4  314.31
#Mann= 5 ,-1 , 0
  3279.5     .05       0  3630.9      .1       0  4775.6     .07       0
  4781.6      .1       0  5560.9     .05       0
#XS Ineff= 1 ,-1
 4212.85 4976.42  290.19
Permanent Ineff=
       F
Bank Sta=4984,5019.9
XS Rating Curve= 0 ,0
Exp/Cntr=0.3,0.1

Type RM Length L Ch R = 1 ,29194   ,522,522,522
BEGIN DESCRIPTION:
LEOPARD CREEK 45.0
END DESCRIPTION:
XS GIS Cut Line= 3
      2216637.71     13258796.87      2217837.72     13257596.85
      2218637.74     13257096.84
#Sta/Elev= 30
  3300.8   314.1  3484.7   308.5  4022.1  297.31  4446.3  290.46  4630.2  288.55
    4715  286.39  4785.7  287.01  4796.9  285.39  4799.6  284.89  4802.9  285.39
    4814  287.08  4870.6  287.11  4941.3  288.55  5005.5  287.77  5020.9  288.56
  5221.9  293.91  5303.9     295  5513.8  301.54  5693.6  305.54    5739  307.56
  5744.9  307.12  5760.3  308.46  5781.5  308.22    5818  310.84  5875.8  311.52
  5882.3  312.44  5897.1  312.36  5912.4  313.87  5918.3  313.43  5941.3  314.85
#Mann= 3 ,-1 , 0
  3300.8     .05       0  4796.9    .035       0  4802.9     .05       0
#XS Ineff= 1 ,-1
 4658.72 4930.02  287.82
Permanent Ineff=
       F
Bank Sta=4941.3,5020.9
XS Rating Curve= 0 ,0
Exp/Cntr=0.3,0.1

Type RM Length L Ch R = 1 ,28672   ,355,355,355
BEGIN DESCRIPTION:
LEOPARD CREEK 44.0
END DESCRIPTION:
XS GIS Cut Line= 3
      2217037.75     13258696.83      2217837.72     13257996.85
       2218587.7     13257246.88
#Sta/Elev= 30
  3962.3  304.14    3976  304.48  3997.9  303.47  4104.2  301.47  4196.2  300.81
    4274  299.63  4281.2  299.97  4302.5  298.95  4351.9  297.82  4706.4  291.73
  4727.7  291.71    4742  291.06  4911.9  287.72  4961.2  285.99  4994.3  284.77
    4997  284.27  5000.3  284.77  5018.2  285.49  5081.8  285.84  5209.1  286.59
  5237.4  287.17  5265.7  288.65  5364.7  291.65  5378.8  292.58  5534.4  295.34
  5760.7  300.68  5930.4  305.37  6015.2  308.18  6029.4  309.38  6085.9  310.46
#Mann= 3 ,-1 , 0
  3962.3     .05       0  4994.3    .035       0  5000.3     .05       0
Bank Sta=4961.2,5081.8
XS Rating Curve= 0 ,0
Exp/Cntr=0.3,0.1

Type RM Length L Ch R = 1 ,28317   ,536,536,536
BEGIN DESCRIPTION:
LEOPARD CREEK 43.0
END DESCRIPTION:
XS GIS Cut Line= 4
      2217121.56     13258826.89      2217594.92     13258606.72
      2218431.49     13257902.24       2218750.4     13257451.37
#Sta/Elev= 30
  3819.9  303.33  4071.9  299.38  4094.8  299.66  4124.5  298.59    4386  294.17
  4400.3   294.5  4506.9  291.67  4528.6  292.45  4535.5  291.31  4564.1  291.15
  4578.4  290.29  4592.7  291.15  4627.8  289.22  4712.4  287.99  4841.1  284.41
  4897.1  284.46  4904.8  283.15  4925.7   284.4    4947  284.25  4982.9  283.71
  4986.4  282.84  4989.1  282.34  4992.4  282.84  5032.3  284.45  5174.1  291.28
  5223.5  292.85  5401.6  294.72  5588.4  297.82  5924.4  306.41  5987.9  308.62
#Mann= 3 ,-1 , 0
  3819.9     .05       0  4986.4    .035       0  4992.4     .05       0
Bank Sta=4947,5032.3
XS Rating Curve= 0 ,0
Exp/Cntr=0.3,0.1

Type RM Length L Ch R = 1 ,27781   ,349,349,349
BEGIN DESCRIPTION:
LEOPARD CREEK 42.0
END DESCRIPTION:
XS GIS Cut Line= 3
      2217099.54     13259300.21      2217815.07     13259036.01
      2218672.99     13258332.08
#Sta/Elev= 30
  3576.1  304.64  3670.1  301.26    3766   299.2  3787.4  299.87  3797.5  298.62
  3819.3  297.96  4107.2  294.36  4128.5  294.69  4256.4  292.14  4293.4   292.2
    4299  291.15  4337.6  290.35  4382.2  290.93  4390.1  289.83  4418.8  289.24
  4532.2  288.18  4567.4  288.68  4581.7   287.6    4703  286.03  4730.3  286.34
  4738.2  285.27  4979.3  281.45  4990.6  280.44  4993.4  279.94  4996.6  280.44
  5028.8  281.28  5121.4  283.33  5164.4  285.74  5349.6  291.23  5448.6  292.23
#Mann= 3 ,-1 , 0
  3576.1     .05       0  4990.6    .035       0  4996.6     .05       0
Bank Sta=4979.3,5028.8
XS Rating Curve= 0 ,0
Exp/Cntr=0.3,0.1

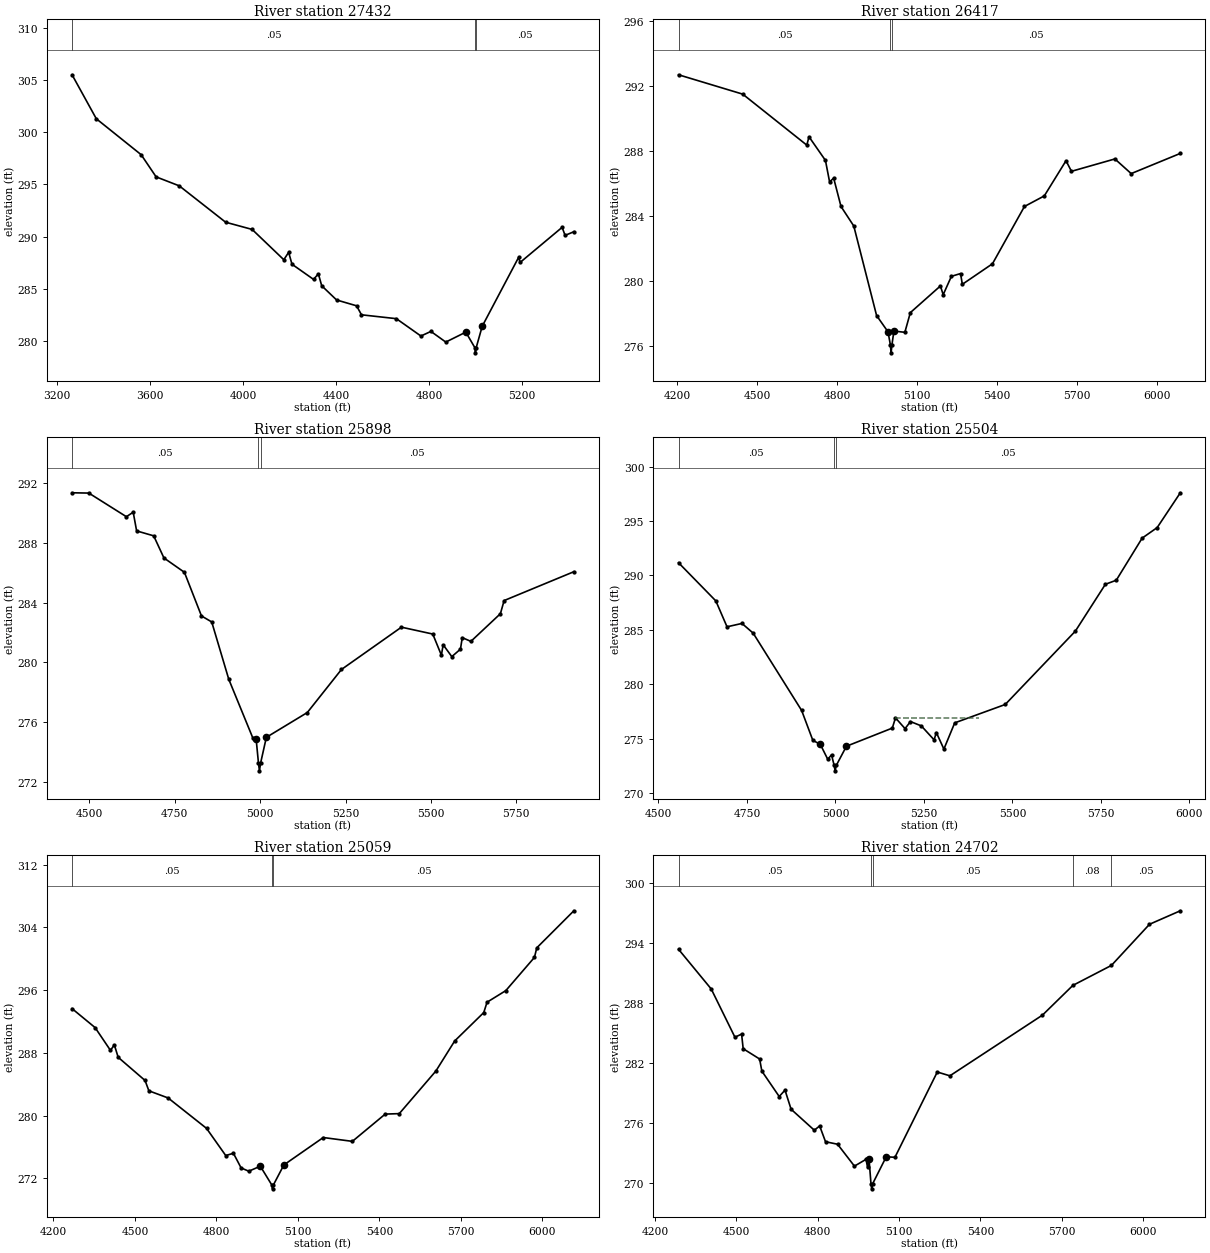
Type RM Length L Ch R = 1 ,27432   ,1015,1015,1015
BEGIN DESCRIPTION:
Mapping XS 39402d0c
END DESCRIPTION:
XS GIS Cut Line= 4
      2217297.72     13260103.74      2217947.16     13259597.39
      2218662.65      13258727.8      2218750.45     13258541.24
#Sta/Elev= 30
  3265.9   305.5  3370.1  301.29  3562.8  297.85    3627  295.73  3726.5  294.87
  3925.6  291.39  4039.5   290.7  4175.6   287.8  4196.4  288.51  4210.7  287.37
  4303.3  285.92  4324.1  286.45  4338.4  285.31  4402.3  283.95  4488.3  283.39
  4509.2  282.53  4659.1  282.16  4764.6   280.5  4807.6  280.94  4871.5  279.92
  4957.5  280.87  4996.2  279.39  4998.9  278.89  5002.2  279.39  5027.9  281.43
  5184.2  288.02  5190.8  287.54  5371.3   290.9    5384  290.13  5421.7  290.48
#Mann= 3 ,-1 , 0
  3265.9     .05       0  4996.2    .035       0  5002.2     .05       0
Bank Sta=4957.5,5027.9
XS Rating Curve= 0 ,0
Exp/Cntr=0.3,0.1

Type RM Length L Ch R = 1 ,26417   ,519,519,519
BEGIN DESCRIPTION:
LEOPARD CREEK 41.0
END DESCRIPTION:
XS GIS Cut Line= 4
      2218365.45     13260367.92      2218706.68     13260147.77
      2218904.82     13259289.18      2218794.75     13258705.82
#Sta/Elev= 30
  4206.1  292.69  4446.8   291.5  4686.8  288.37  4695.2  288.88  4756.8  287.43
  4772.3  286.11  4787.6  286.34  4815.1   284.6    4863   283.4  4948.5   277.9
  4991.3   276.9  5000.1  276.11  5002.9  275.61  5006.1  276.11  5013.4  276.95
  5054.4  276.87    5075  278.08  5187.8  279.72  5198.1  279.18  5228.9  280.31
  5263.2  280.48  5269.9  279.82  5382.8  281.08  5502.7   284.6  5577.1  285.25
  5658.5  287.41  5678.9  286.76  5841.7  287.52  5902.8  286.62    6087  287.86
#Mann= 3 ,-1 , 0
  4206.1     .05       0  5000.1    .035       0  5006.1     .05       0
Bank Sta=4991.3,5013.4
XS Rating Curve= 0 ,0
Exp/Cntr=0.3,0.1

Type RM Length L Ch R = 1 ,25898   ,394,394,394
BEGIN DESCRIPTION:
LEOPARD CREEK 40.0
END DESCRIPTION:
XS GIS Cut Line= 3
       2219312.1     13260345.92      2219301.09     13259520.34
      2219080.92     13258914.88
#Sta/Elev= 30
    4449  291.35  4498.1  291.33  4608.1  289.75  4628.1  290.05  4638.1   288.8
  4688.1  288.47  4718.1  286.99  4778.1  286.03  4828.1  283.11  4858.1  282.71
  4908.1  278.87  4978.1  274.97  4988.1   274.9  4995.1  273.25  4997.9  272.75
  5001.1  273.25  5018.1  274.99  5138.1  276.65  5238.1  279.53  5413.8  282.36
  5505.6   281.9  5530.8  280.49  5536.1  281.18  5561.4  280.39  5586.7  280.89
    5592  281.66  5617.3  281.41  5703.7  283.26  5714.6  284.14  5918.9  286.07
#Mann= 3 ,-1 , 0
    4449     .05       0  4995.1    .035       0  5001.1     .05       0
Bank Sta=4988.1,5018.1
XS Rating Curve= 0 ,0
Exp/Cntr=0.3,0.1

Type RM Length L Ch R = 1 ,25504   ,445,445,445
BEGIN DESCRIPTION:
LEOPARD CREEK 39.0
END DESCRIPTION:
XS GIS Cut Line= 3
      2219537.73     13260096.84      2219687.72     13259646.85
      2220187.71     13258846.87
#Sta/Elev= 30
  4556.7  291.16  4662.1  287.65  4693.7  285.27  4735.9  285.58  4767.5  284.69
  4904.5  277.58  4936.2  274.83  4957.2  274.47  4978.3  273.09  4988.9   273.5
  4996.4  272.53  4999.1  272.03  5002.4  272.53    5031  274.29  5160.7  275.96
  5169.6   276.9  5196.7  275.91    5212  276.56  5242.7  276.16  5278.7  274.88
  5285.1  275.55  5306.4  274.03    5337  276.44  5479.7  278.13  5677.8  284.87
  5762.7  289.18  5793.4  289.55  5866.5  293.42    5909  294.39  5974.4  297.59
#Mann= 3 ,-1 , 0
  4556.7     .05       0  4996.4    .035       0  5002.4     .05       0
#XS Ineff= 1 ,-1
 5169.59 5406.25  276.91
Permanent Ineff=
       F
Bank Sta=4957.2,5031
XS Rating Curve= 0 ,0
Exp/Cntr=0.3,0.1

Type RM Length L Ch R = 1 ,25059   ,357,357,357
BEGIN DESCRIPTION:
LEOPARD CREEK 38.0
END DESCRIPTION:
XS GIS Cut Line= 3
      2219587.72     13260246.85      2220087.72     13259746.85
      2220387.73     13258646.83
#Sta/Elev= 30
  4268.6  293.64  4353.4  291.22    4410  288.31  4424.2  289.02  4438.3  287.43
  4537.3  284.47  4551.4  283.15  4622.2  282.24  4763.6  278.36  4834.3  274.89
  4862.6  275.18  4890.9  273.31  4919.1  272.89  4961.6  273.53  5003.8  271.14
  5006.5  270.64  5009.8  271.14  5048.3  273.69  5193.4  277.19  5300.5   276.7
  5421.4  280.18  5473.2  280.24    5608  285.68  5677.1  289.51  5784.2  293.14
  5796.3  294.46  5865.4  295.94  5970.8  300.18  5979.4   301.4  6115.9  306.13
#Mann= 3 ,-1 , 0
  4268.6     .05       0  5003.8    .035       0  5009.8     .05       0
Bank Sta=4961.6,5048.3
XS Rating Curve= 0 ,0
Exp/Cntr=0.3,0.1

Type RM Length L Ch R = 1 ,24702   ,606,606,606
BEGIN DESCRIPTION:
LEOPARD CREEK 37.0
END DESCRIPTION:
XS GIS Cut Line= 2
      2219599.68      13260265.1      2221334.25     13259619.84
#Sta/Elev= 30
  4286.3  293.37  4406.9   289.4  4494.3  284.58  4518.9  284.89  4524.7  283.43
  4585.4   282.4  4593.6  281.19  4657.6  278.65    4679  279.29  4701.4  277.38
  4787.1  275.28  4806.8  275.71  4828.4  274.13  4872.8  273.88  4935.1  271.69
  4977.7  272.37  4983.5  271.57  4988.8  272.43  4996.1  269.92  4998.8  269.42
  5002.1  269.92  5052.4  272.63  5084.4  272.57  5240.6   281.1  5287.1  280.72
  5628.6  286.79  5740.7  289.76    5883  291.76  6023.3  295.87    6137  297.22
#Mann= 5 ,-1 , 0
  4286.3     .05       0  4996.1    .035       0  5002.1     .05       0
  5740.7     .08       0    5883     .05       0
Bank Sta=4988.8,5052.4
XS Rating Curve= 0 ,0
Exp/Cntr=0.3,0.1

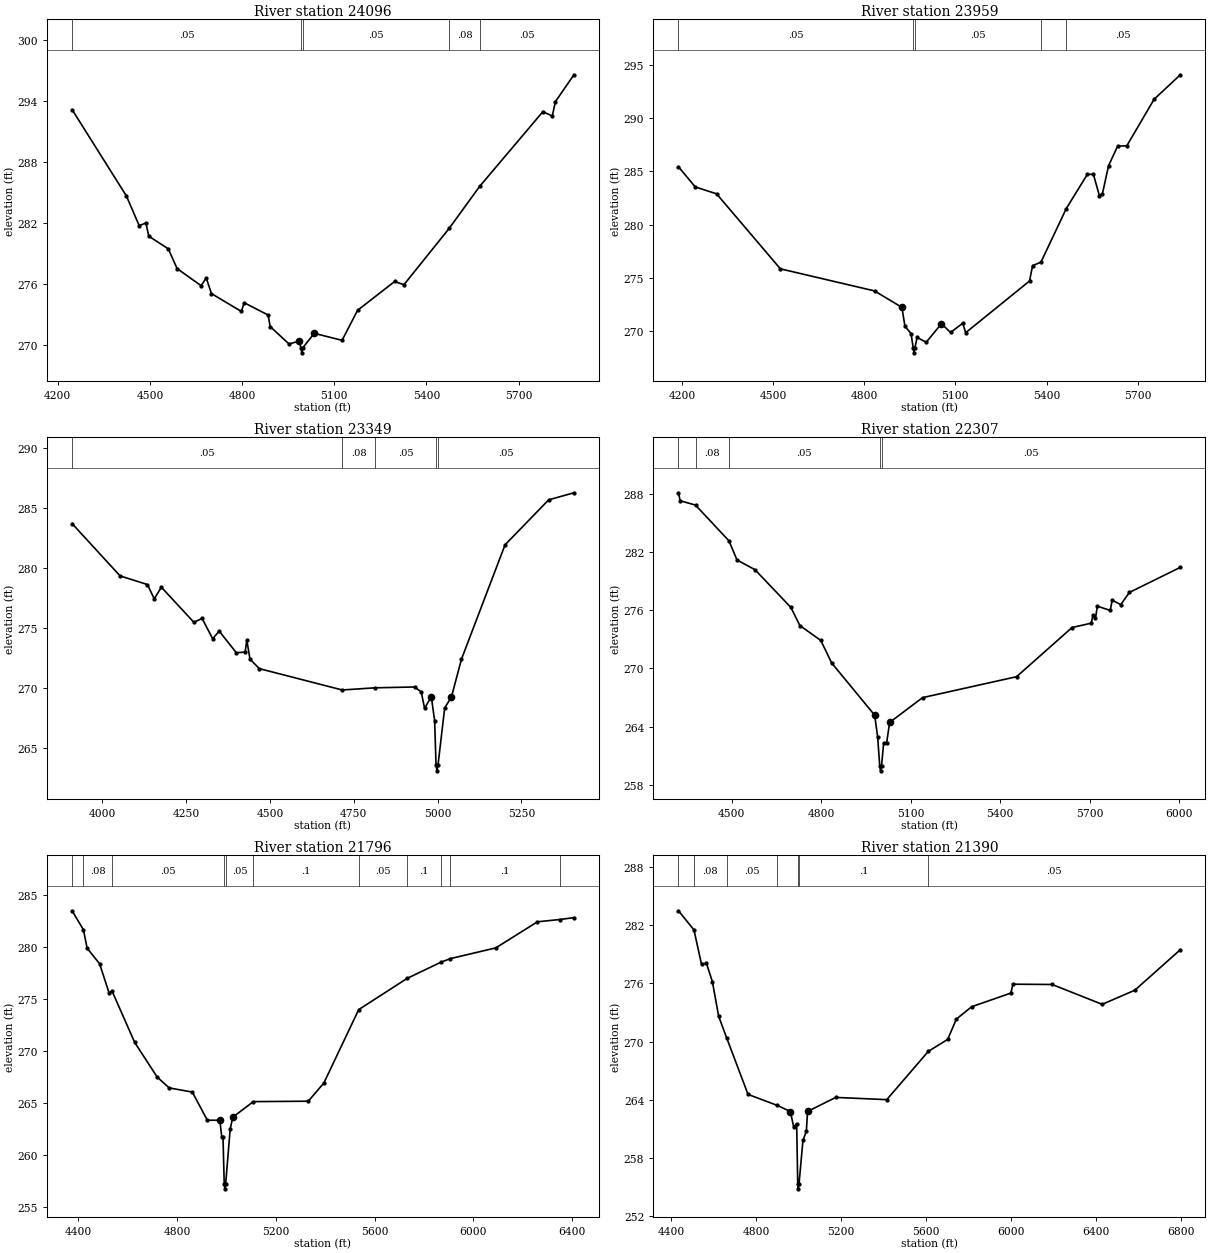
Type RM Length L Ch R = 1 ,24096   ,137,137,137
BEGIN DESCRIPTION:
LEOPARD CREEK 36.0
END DESCRIPTION:
XS GIS Cut Line= 3
      2219587.72     13260396.85      2220287.72     13260596.85
      2221187.77     13260496.85
#Sta/Elev= 30
  4246.7  293.19  4423.5  284.69  4465.1  281.77  4487.2  282.02  4496.3  280.73
    4560  279.48  4588.6  277.54  4666.6  275.86  4683.5  276.61  4700.4  275.08
  4797.9  273.32    4807  274.18    4885  272.97  4891.5  271.84  4952.6  270.13
  4984.8  270.38  4991.8  269.75  4994.6  269.25  4997.8  269.75  5035.1  271.17
  5125.6  270.48  5175.9  273.43  5296.7  276.27  5326.9  275.95  5474.6  281.51
  5573.7  285.64  5779.6  292.99  5809.8  292.54  5819.9  293.96  5880.3  296.61
#Mann= 5 ,-1 , 0
  4246.7     .05       0  4991.8    .035       0  4997.8     .05       0
  5474.6     .08       0  5573.7     .05       0
Bank Sta=4984.8,5035.1
XS Rating Curve= 0 ,0
Exp/Cntr=0.3,0.1

Type RM Length L Ch R = 1 ,23959   ,610,610,610
BEGIN DESCRIPTION:
LEOPARD CREEK 35.0
END DESCRIPTION:
XS GIS Cut Line= 2
      2219502.47     13260723.44      2221153.91     13260737.32
#Sta/Elev= 30
  4188.8  285.42  4244.1  283.53  4314.1  282.89  4524.1  275.86  4834.1  273.79
  4924.1  272.25  4934.1  270.47  4954.1   269.8  4961.1  268.49  4963.8  267.99
  4967.1  268.49  4974.1  269.43  5004.1  268.98  5054.1  270.72  5084.1   269.9
  5124.1  270.76  5134.1  269.88  5344.1  274.72  5354.1  276.16  5381.5  276.48
  5465.1  281.51  5534.1   284.7  5554.1  284.73  5574.1   282.7  5584.1  282.91
  5604.1  285.52  5634.1  287.36  5664.1  287.38  5754.1  291.75  5840.3  294.04
#Mann= 5 ,-1 , 0
  4188.8     .05       0  4961.1    .035       0  4967.1     .05       0
  5381.5     .08       0  5465.1     .05       0
Bank Sta=4924.1,5054.1
XS Rating Curve= 0 ,0
Exp/Cntr=0.3,0.1

Type RM Length L Ch R = 1 ,23349   ,1042,1042,1042
BEGIN DESCRIPTION:
Mapping XS adf83c02
END DESCRIPTION:
XS GIS Cut Line= 3
      2219477.25     13261160.47      2220027.58     13261270.53
      2220962.96     13261237.52
#Sta/Elev= 30
  3909.6  283.72  4052.9  279.35  4134.4  278.63  4154.8  277.44    4176  278.41
  4272.9  275.48  4297.6   275.8    4329  274.11  4348.6  274.74  4399.6  272.94
  4425.8  272.99  4430.9  273.98  4440.4   272.4  4468.4  271.61  4715.5  269.83
  4813.9  270.01  4931.3  270.08  4951.3  269.66  4961.3   268.3  4981.3  269.27
  4991.3  267.26  4995.4  263.58  4998.1  263.08  5001.4  263.58  5021.3  268.34
  5041.3  269.23  5071.3   272.4  5201.4  281.95  5331.5   285.7  5406.8  286.29
#Mann= 5 ,-1 , 0
  3909.6     .05       0  4715.5     .08       0  4813.9     .05       0
  4995.4    .035       0  5001.4     .05       0
Bank Sta=4981.3,5041.3
XS Rating Curve= 0 ,0
Exp/Cntr=0.3,0.1

Type RM Length L Ch R = 1 ,22307   ,511,511,511
BEGIN DESCRIPTION:
LEOPARD CREEK 34.0
END DESCRIPTION:
XS GIS Cut Line= 3
      2219422.16     13261886.95      2220302.77     13261964.01
      2220930.22     13261468.65
#Sta/Elev= 30
  4320.9  288.12  4326.5   287.3  4378.1  286.85  4490.3  283.16  4517.2  281.19
  4577.4  280.19  4697.9   276.3    4728  274.43  4798.3  272.89  4834.7  270.57
    4979  265.18    4989  262.93    4996  259.94  4998.8  259.44    5002  259.94
  5009.1   262.3  5019.1  262.31  5029.2  264.43  5139.6  266.99    5455  269.15
    5641  274.22  5705.2  274.67  5711.5  275.49  5719.6  275.16    5726  276.43
  5769.3  275.98  5775.7  277.05  5804.5  276.58  5833.4  277.84  6004.3  280.43
#Mann= 5 ,-1 , 0
  4320.9     .05       0  4378.1     .08       0  4490.3     .05       0
    4996    .035       0    5002     .05       0
Bank Sta=4979,5029.2
XS Rating Curve= 0 ,0
Exp/Cntr=0.3,0.1

Type RM Length L Ch R = 1 ,21796   ,406,406,406
BEGIN DESCRIPTION:
LEOPARD CREEK 33.0
END DESCRIPTION:
XS GIS Cut Line= 3
      2219587.69     13262346.85      2220187.72     13262446.85
      2221537.69     13261996.87
#Sta/Elev= 30
  4375.3  283.49  4421.4  281.66  4436.2  279.89  4486.8  278.39  4524.9   275.6
  4537.8  275.73  4628.8  270.82    4720  267.49  4768.2  266.45    4862  266.05
  4922.8  263.34  4973.5  263.34  4981.1  261.73  4986.2  261.73  4991.1  257.24
  4993.9  256.74  4997.1  257.24  5015.2  262.48  5025.8  263.63  5108.9  265.13
  5331.5  265.17  5394.7  266.93  5535.4  273.98  5731.8  276.99  5869.1  278.55
    5907  278.89  6090.4  279.92  6259.1  282.43  6349.5  282.65  6406.6  282.83
#Mann= 11 ,-1 , 0
  4375.3     .05       0  4421.4     .08       0  4537.8     .05       0
  4991.1    .035       0  4997.1     .05       0  5108.9      .1       0
  5535.4     .05       0  5731.8      .1       0  5869.1     .05       0
    5907      .1       0  6349.5     .05       0
Bank Sta=4973.5,5025.8
XS Rating Curve= 0 ,0
Exp/Cntr=0.3,0.1

Type RM Length L Ch R = 1 ,21390   ,397,397,397
BEGIN DESCRIPTION:
LEOPARD CREEK 32.0
END DESCRIPTION:
XS GIS Cut Line= 3
      2219543.24     13262503.37      2220225.72     13262888.64
      2221766.78      13262547.4
#Sta/Elev= 30
  4434.6   283.5  4507.4  281.53  4543.1  277.97  4566.1  278.09  4594.5  276.16
  4623.5  272.62  4661.4  270.38    4762  264.54  4900.5   263.4  4961.3  262.77
  4977.2  261.15  4990.9  261.53  4995.9  255.29  4998.6  254.79  5001.9  255.29
  5020.5   259.8  5036.5  260.73  5042.2  262.78  5174.7  264.23    5415     264
  5610.4  268.98  5701.7  270.22  5742.7  272.32  5814.4  273.59  5998.8     275
    6009  275.92  6193.4  275.89  6428.9  273.84  6582.6   275.3  6796.7  279.48
#Mann= 7 ,-1 , 0
  4434.6     .05       0  4507.4     .08       0  4661.4     .05       0
  4900.5      .1       0  4995.9     .07       0  5001.9      .1       0
  5610.4     .05       0
Bank Sta=4961.3,5042.2
XS Rating Curve= 0 ,0
Exp/Cntr=0.3,0.1

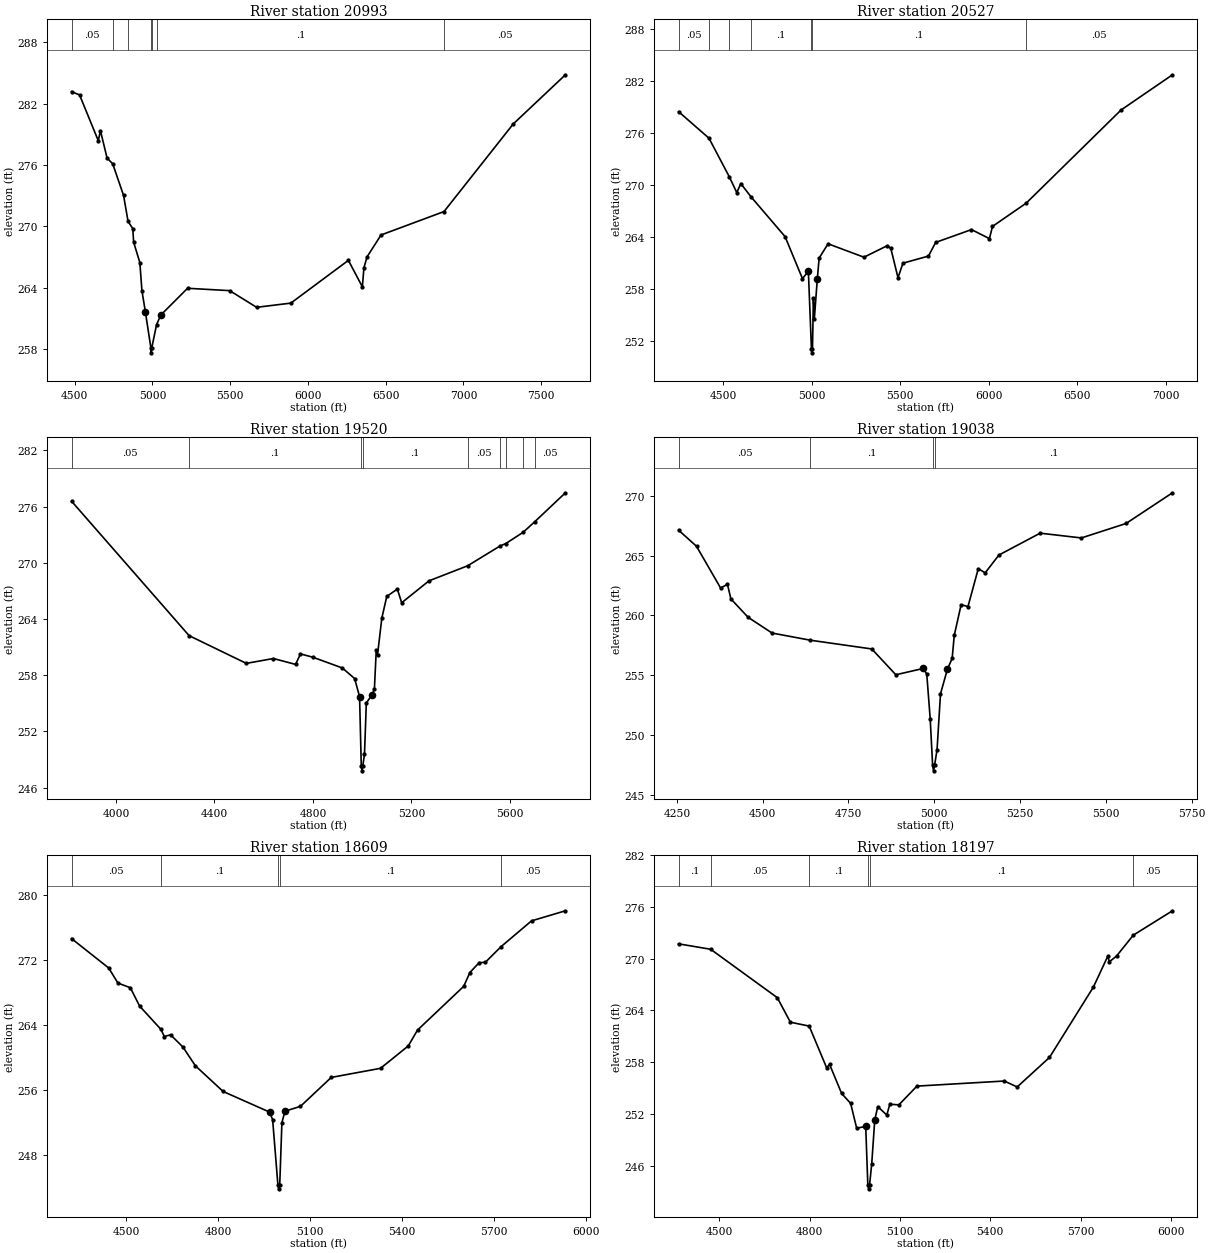
Type RM Length L Ch R = 1 ,20993   ,466,466,466
BEGIN DESCRIPTION:
LEOPARD CREEK 31.0
END DESCRIPTION:
XS GIS Cut Line= 4
       2219279.1     13262602.47      2219532.25     13262855.62
      2220159.67     13263152.82      2222283.45     13263185.83
#Sta/Elev= 30
    4480  283.17  4531.6  282.85  4651.8  278.38    4666  279.35  4708.4  276.68
  4744.6  276.12  4814.5  273.03  4843.4  270.49  4873.8  269.78  4879.4  268.45
  4919.3  266.46  4932.6  263.72  4954.7  261.65  4990.1  258.14  4992.8  257.64
  4996.1  258.14    5027  260.41  5054.3  261.34  5226.1  263.95  5496.9  263.72
  5670.3  262.09  5890.4   262.5  6260.4  266.68  6350.4  264.09  6360.4  265.96
  6380.4  267.02  6470.4  269.16  6875.5  271.45  7320.5  280.01  7656.3  284.82
#Mann= 7 ,-1 , 0
    4480     .05       0  4744.6     .08       0  4843.4     .05       0
  4990.1    .035       0  4996.1     .05       0    5027      .1       0
  6875.5     .05       0
Bank Sta=4954.7,5054.3
XS Rating Curve= 0 ,0
Exp/Cntr=0.3,0.1

Type RM Length L Ch R = 1 ,20527   ,1007,1007,1007
BEGIN DESCRIPTION:
LEOPARD CREEK 30.0
END DESCRIPTION:
XS GIS Cut Line= 4
      2219091.96     13262987.72      2219532.25      13263273.9
      2220974.23     13263505.06      2221777.81     13263549.09
#Sta/Elev= 30
  4248.1  278.45  4419.8  275.38  4534.7  270.92    4577  269.09  4599.6  270.14
  4656.4  268.63  4849.7  264.01  4947.9  259.16  4981.3     260  4998.6  251.08
  5001.3  250.58  5004.6  251.08  5009.8  256.91  5014.9  254.49    5032  259.14
  5042.1  261.53  5092.7  263.18  5295.3  261.63  5426.9  262.96  5447.2  262.65
  5487.7  259.26  5515.7  260.94  5659.9  261.76  5700.4  263.34  5902.9  264.82
  6004.2  263.78  6021.6  265.19  6211.6  267.87  6747.9  278.64  7038.4  282.71
#Mann= 7 ,-1 , 0
  4248.1     .05       0  4419.8     .08       0  4534.7     .05       0
  4656.4      .1       0  4998.6     .07       0  5004.6      .1       0
  6211.6     .05       0
Bank Sta=4981.3,5032
XS Rating Curve= 0 ,0
Exp/Cntr=0.3,0.1

Type RM Length L Ch R = 1 ,19520   ,482,482,482
BEGIN DESCRIPTION:
LEOPARD CREEK 28.0
END DESCRIPTION:
XS GIS Cut Line= 3
       2219137.7     13264046.85      2220337.72     13264046.85
      2221137.77     13264146.86
#Sta/Elev= 30
  3819.5  276.58  4297.1  262.23  4529.5  259.27  4639.5  259.79  4729.5  259.16
  4749.5  260.28  4799.5  259.93  4919.5  258.78  4969.5  257.65  4989.5  255.72
  4996.5   248.3  4999.3   247.8  5002.5   248.3  5009.5  249.56    5017  255.04
  5039.7   255.9  5049.8  256.53  5057.3  260.69  5062.4  260.17    5080  264.11
  5100.1  266.42    5143   267.2  5160.6  265.74  5271.5  268.08  5428.8  269.69
  5560.1   271.8  5583.5  272.06  5654.4  273.27    5702  274.41  5825.8  277.48
#Mann= 9 ,-1 , 0
  3819.5     .05       0  4297.1      .1       0  4996.5     .07       0
  5002.5      .1       0  5428.8     .05       0  5560.1      .1       0
  5583.5     .05       0  5654.4      .1       0    5702     .05       0
Bank Sta=4989.5,5039.7
XS Rating Curve= 0 ,0
Exp/Cntr=0.3,0.1

Type RM Length L Ch R = 1 ,19038   ,429,429,429
BEGIN DESCRIPTION:
LEOPARD CREEK 27.0
END DESCRIPTION:
XS GIS Cut Line= 2
      2219495.49     13264473.44      2220932.82     13264542.88
#Sta/Elev= 30
  4255.1  267.13  4307.4  265.78  4377.5  262.29  4397.5   262.6  4407.5  261.38
  4457.6  259.84  4527.6  258.52  4639.4  257.92    4818  257.19  4888.1  255.03
  4968.2  255.56  4978.2  255.09  4988.2  251.35  4995.2  247.49  4997.9  246.99
  5001.2  247.49  5008.2  248.77  5018.2  253.43  5038.2  255.48  5052.2   256.4
  5058.3  258.33  5078.3  260.89  5098.3  260.74  5128.3  263.91  5148.4  263.56
  5188.4  265.05  5308.6  266.88  5428.7  266.48  5558.8  267.69  5694.1  270.26
#Mann= 4 ,-1 , 0
  4255.1     .05       0  4639.4      .1       0  4995.2     .07       0
  5001.2      .1       0
Bank Sta=4968.2,5038.2
XS Rating Curve= 0 ,0
Exp/Cntr=0.3,0.1

Type RM Length L Ch R = 1 ,18609   ,412,412,412
BEGIN DESCRIPTION:
LEOPARD CREEK 26.0
END DESCRIPTION:
XS GIS Cut Line= 3
       2219387.7     13264796.85      2220087.72     13264896.85
      2220987.76     13264996.86
#Sta/Elev= 30
  4320.9  274.67  4442.1  271.06  4472.4   269.2  4512.8  268.63  4543.2  266.37
  4612.5  263.52    4624  262.63  4644.2  262.84  4684.6  261.34    4725  259.04
  4815.9  255.87  4967.4  253.34  4977.5  252.41  4994.7   244.4  4997.5   243.9
  5000.7   244.4  5007.8  252.05  5017.9  253.45  5068.3  254.04  5168.9   257.6
  5329.9  258.72  5420.4  261.47  5450.6  263.42  5601.5   268.8  5621.7   270.5
  5651.8  271.71    5672  271.75  5723.1  273.67  5822.9  276.85  5933.6  278.09
#Mann= 5 ,-1 , 0
  4320.9     .05       0  4612.5      .1       0  4994.7     .07       0
  5000.7      .1       0  5723.1     .05       0
Bank Sta=4967.4,5017.9
XS Rating Curve= 0 ,0
Exp/Cntr=0.3,0.1

Type RM Length L Ch R = 1 ,18197   ,426,426,426
BEGIN DESCRIPTION:
LEOPARD CREEK 25.0
END DESCRIPTION:
XS GIS Cut Line= 4
      2219378.14     13265013.09      2219642.32     13265266.26
      2220379.82     13265288.28      2220873.95     13265079.65
#Sta/Elev= 30
    4365  271.74  4471.5  271.11  4692.8  265.49  4736.3  262.64  4798.7  262.19
  4856.4  257.37  4866.4  257.74  4906.4  254.37  4936.4  253.21  4956.4  250.33
  4986.4  250.54  4993.4  243.79  4996.2  243.29  4999.4  243.79  5006.4  246.21
  5016.4  251.27  5026.4  252.84  5056.4  251.86  5066.5  253.12  5096.5  253.04
  5156.5  255.22  5446.6  255.81  5489.4  255.12  5596.7  258.55  5742.8  266.74
  5790.2   270.3  5795.6  269.66  5819.3  270.32  5875.1  272.75  6005.1  275.58
#Mann= 6 ,-1 , 0
    4365      .1       0  4471.5     .05       0  4798.7      .1       0
  4993.4     .07       0  4999.4      .1       0  5875.1     .05       0
Bank Sta=4986.4,5016.4
XS Rating Curve= 0 ,0
Exp/Cntr=0.3,0.1