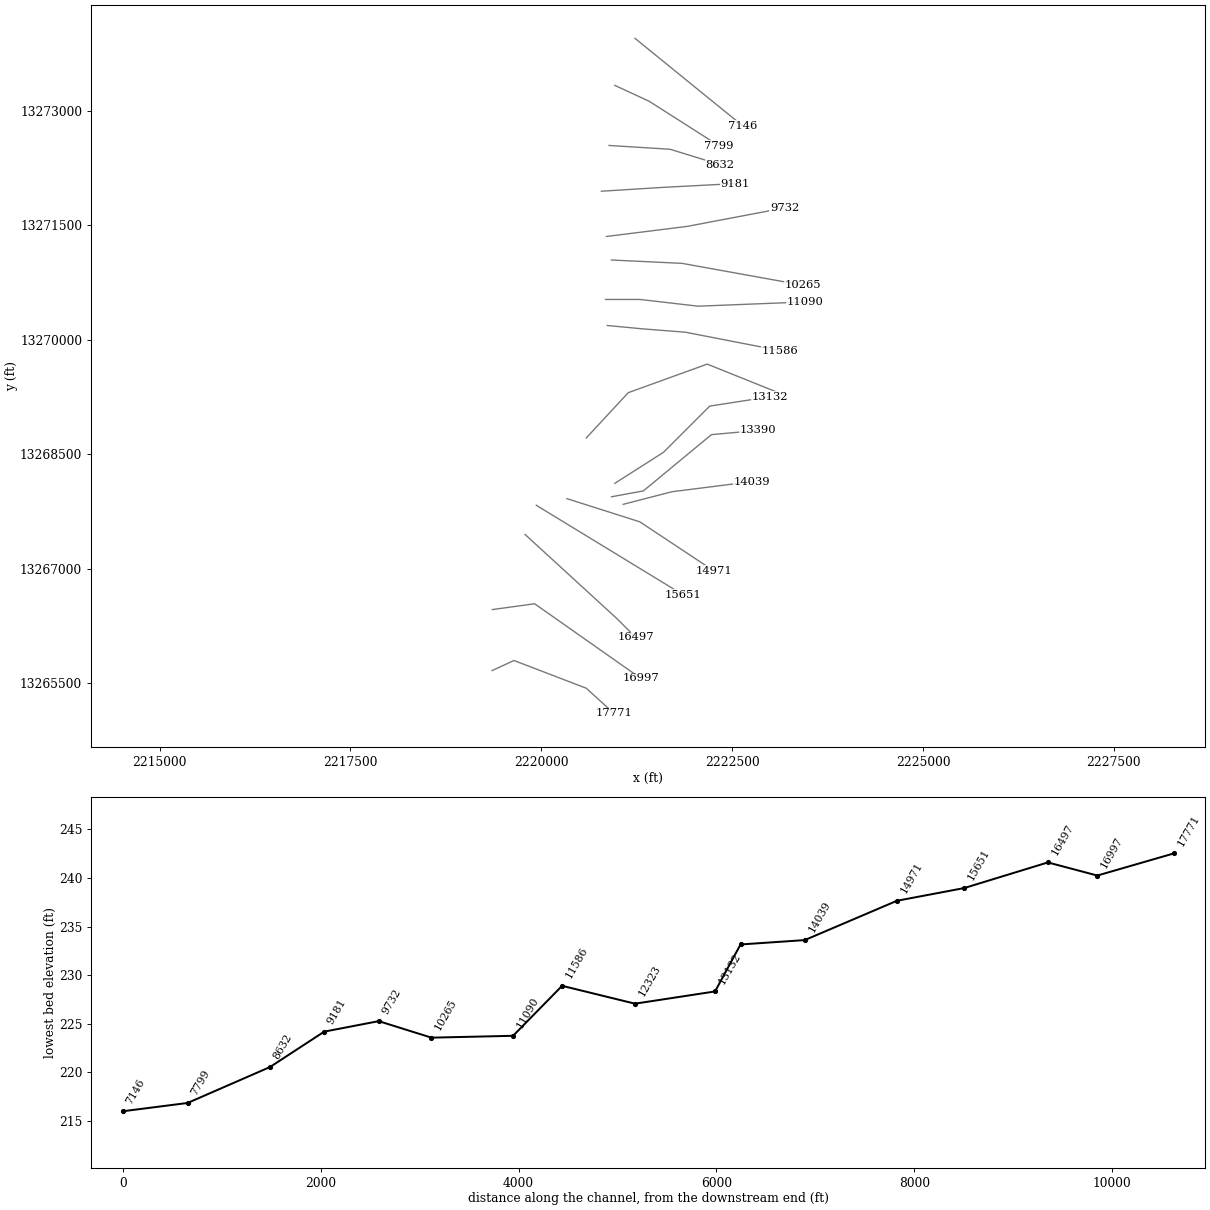
HEC-RAS study LEOPARD CREEK.prj: LEOPARD CREEK Base Level Engineering

--- LEOPARD CREEK.g01 (geometry) --- (continued)

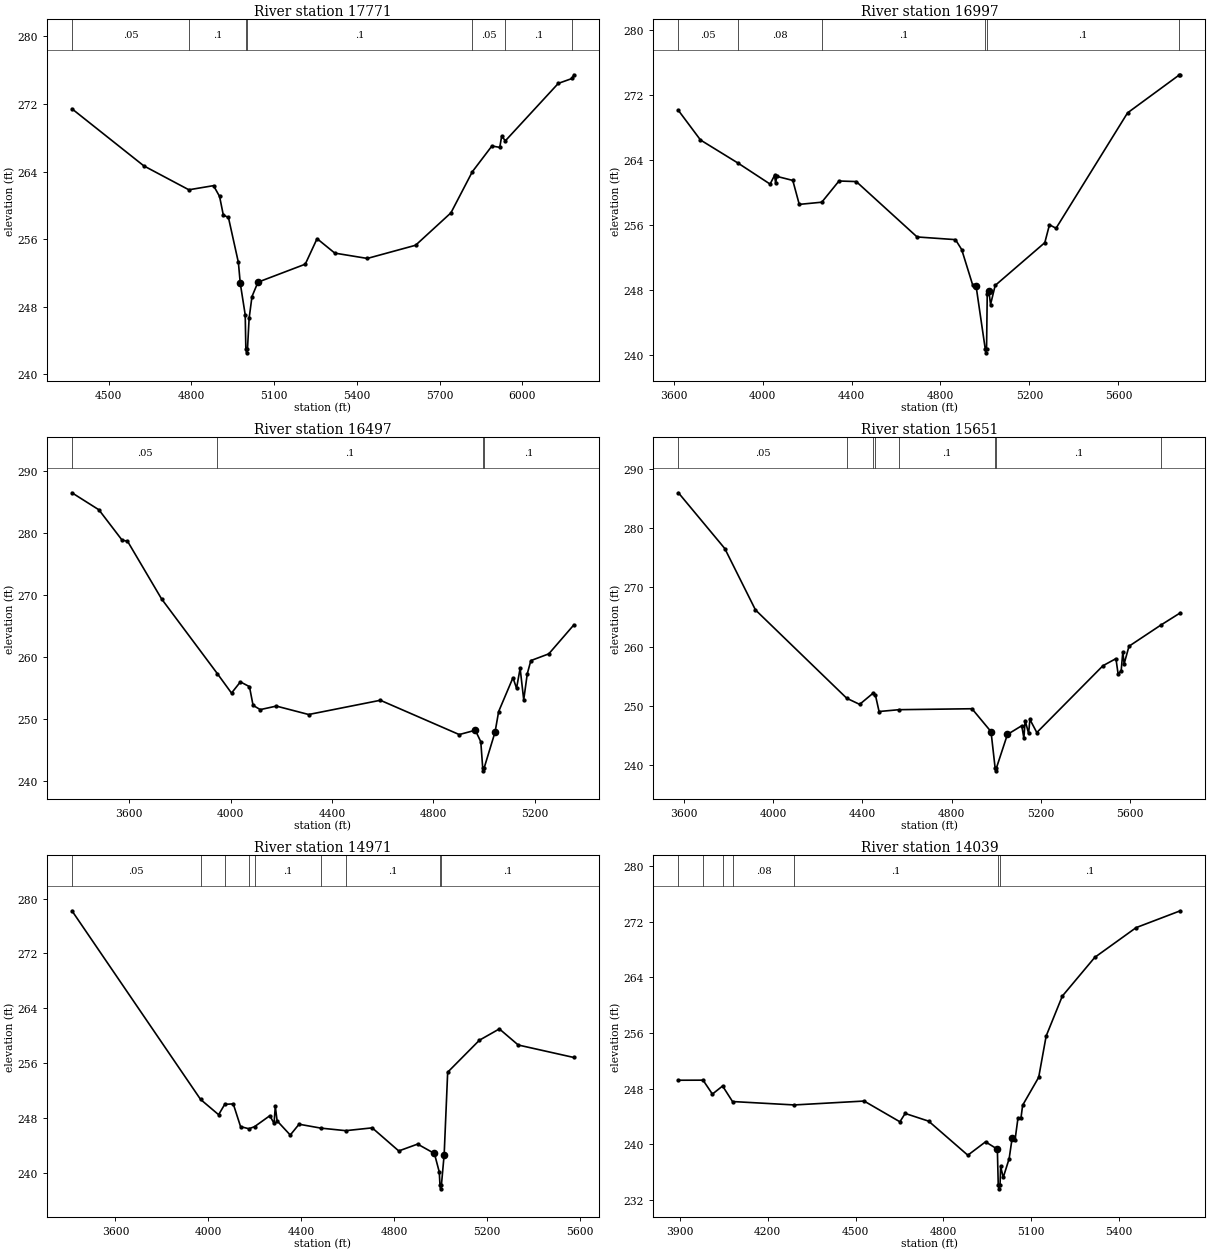
Type RM Length L Ch R = 1 ,17771   ,774,774,774
BEGIN DESCRIPTION:
LEOPARD CREEK 24.0
END DESCRIPTION:
XS GIS Cut Line= 4
      2219356.16     13265662.55      2219642.32     13265794.62
      2220588.97     13265431.37      2220951.83      13265101.5
#Sta/Elev= 30
  4366.9  271.43  4627.6  264.67  4790.7  261.84  4880.2  262.33  4902.1  261.05
  4915.6  258.85  4934.2  258.56  4970.3  253.23    4977  250.79    4995  247.03
  4997.3  243.03  5000.1  242.53  5003.3  243.03  5009.2  246.62  5019.6   249.2
  5041.3   250.9  5212.7  253.03  5255.5  256.05  5319.8  254.34  5437.6  253.71
  5612.6  255.27  5740.8  259.11  5818.4  263.98  5889.4  267.03  5917.8  266.86
  5924.6  268.17  5938.4  267.65    6130  274.44  6179.7  275.02  6186.4  275.46
#Mann= 7 ,-1 , 0
  4366.9     .05       0  4790.7      .1       0  4997.3     .07       0
  5003.3      .1       0  5818.4     .05       0  5938.4      .1       0
  6179.7     .05       0
Bank Sta=4977,5041.3
XS Rating Curve= 0 ,0
Exp/Cntr=0.3,0.1

Type RM Length L Ch R = 1 ,16997   ,500,500,500
BEGIN DESCRIPTION:
LEOPARD CREEK 22.0
END DESCRIPTION:
XS GIS Cut Line= 3
      2219359.47     13266462.45      2219912.88     13266538.41
      2221301.73     13265561.87
#Sta/Elev= 30
  3621.8   270.1    3721  266.46  3889.5  263.62  4033.9  261.03  4053.8  262.09
  4058.9  261.16  4064.2  261.98    4136  261.48  4165.1  258.53  4266.3   258.8
  4343.7  261.41  4421.3  261.34  4694.8  254.52  4867.3  254.19  4895.3  252.97
  4944.9  248.59  4959.7  248.53  5001.1  240.75  5003.8  240.25  5007.1  240.75
  5010.2  247.55  5017.6  247.88    5025   246.2  5045.9  248.55    5269  253.82
  5289.9  256.02  5319.5  255.59    5641   269.8    5871  274.42  5878.2  274.49
#Mann= 6 ,-1 , 0
  3621.8     .05       0  3889.5     .08       0  4266.3      .1       0
  5001.1     .07       0  5007.1      .1       0    5871     .05       0
Bank Sta=4959.7,5017.6
XS Rating Curve= 0 ,0
Exp/Cntr=0.3,0.1

Type RM Length L Ch R = 1 ,16497   ,846,846,846
BEGIN DESCRIPTION:
LEOPARD CREEK 21.0
END DESCRIPTION:
XS GIS Cut Line= 3
      2219787.71     13267446.86      2220987.72     13266346.85
      2221237.69     13266096.89
#Sta/Elev= 30
  3373.5  286.52  3479.9  283.77  3571.8  278.85  3592.7  278.71  3727.1  269.39
  3947.2  257.32  4003.4  254.16  4038.5  255.97  4074.3   255.2  4088.5  252.18
  4116.9  251.49  4180.4  252.06    4308   250.7    4591     253  4902.4  247.46
  4965.9  248.16  4987.5   246.3    4995   242.1  4997.8   241.6    5001   242.1
  5043.8  247.86    5058  251.18  5114.5  256.64  5128.7  254.94  5142.8  258.16
    5157  253.08  5171.1   257.3  5185.2  259.41    5256   260.5  5354.9  265.18
#Mann= 4 ,-1 , 0
  3373.5     .05       0  3947.2      .1       0    4995     .07       0
    5001      .1       0
Bank Sta=4965.9,5043.8
XS Rating Curve= 0 ,0
Exp/Cntr=0.3,0.1

Type RM Length L Ch R = 1 ,15651   ,680,680,680
BEGIN DESCRIPTION:
LEOPARD CREEK 19.0
END DESCRIPTION:
XS GIS Cut Line= 2
      2219934.62     13267829.62      2221853.95      13266658.5
#Sta/Elev= 30
  3576.6  286.02  3784.4  276.58  3921.8  266.19  4330.8  251.24  4388.5  250.21
  4447.9  252.08  4459.2  251.76  4475.5     249  4565.1  249.31  4891.7  249.47
    4977  245.59  4995.3  239.46    4998  238.96  5001.3  239.46  5050.5  245.12
  5114.8   246.6  5124.1  244.48  5129.9  247.47  5145.4  245.29  5151.2  247.66
  5182.1  245.44  5478.4  256.75  5536.6  257.95  5546.1  255.41    5560  255.86
  5567.4  259.11  5573.3  257.08  5595.1  260.05  5736.6   263.6    5825   265.7
#Mann= 8 ,-1 , 0
  3576.6     .05       0  4330.8     .08       0  4447.9      .1       0
  4459.2     .08       0  4565.1      .1       0  4995.3     .07       0
  5001.3      .1       0  5736.6     .05       0
Bank Sta=4977,5050.5
XS Rating Curve= 0 ,0
Exp/Cntr=0.3,0.1

Type RM Length L Ch R = 1 ,14971   ,932,932,932
BEGIN DESCRIPTION:
LEOPARD CREEK 18.0
END DESCRIPTION:
XS GIS Cut Line= 3
      2220336.01     13267916.46      2221290.92     13267612.63
      2222256.62     13266972.45
#Sta/Elev= 30
  3412.9  278.23  3966.6   250.7  4044.3  248.47  4070.6  249.98  4107.3  250.05
  4138.8  246.73  4174.6  246.42  4198.8  246.72  4264.7  248.32    4283   247.2
  4288.3  249.67  4296.2  247.57  4352.7   245.5  4390.6  247.08  4484.6  246.51
  4591.5  246.14  4705.5  246.55  4819.8  243.18    4901  244.18  4973.2  242.81
  4994.3   240.1  4997.3  238.15    5000  237.65  5003.3  238.15  5015.3  242.65
  5030.4  254.67    5167  259.34  5252.9  260.99  5334.2  258.64  5573.6  256.82
#Mann= 9 ,-1 , 0
  3412.9     .05       0  3966.6     .08       0  4070.6      .1       0
  4174.6     .08       0  4198.8      .1       0  4484.6     .08       0
  4591.5      .1       0  4997.3     .07       0  5003.3      .1       0
Bank Sta=4973.2,5015.3
XS Rating Curve= 0 ,0
Exp/Cntr=0.3,0.1

Type RM Length L Ch R = 1 ,14039   ,649,649,649
BEGIN DESCRIPTION:
LEOPARD CREEK 17.0
END DESCRIPTION:
XS GIS Cut Line= 3
      2221073.34     13267842.03      2221711.73     13268007.13
      2222757.43     13268139.22
#Sta/Elev= 30
  3895.1   249.2  3979.2  249.21  4011.1  247.21  4045.9  248.37  4079.8  246.14
  4290.5  245.65    4529  246.21  4651.2  243.23  4669.2  244.43  4749.4  243.32
  4883.1  238.43  4943.5  240.35  4983.9   239.3    4987   234.1  4989.8   233.6
    4993   234.1  4995.1  236.81    5004  235.24  5024.2  237.94  5034.3  240.87
  5044.3  240.63  5054.4  243.81  5064.5  243.77  5070.2  245.61    5125  249.62
  5150.5  255.55  5205.6  261.28  5316.5  266.85  5457.6  271.12  5608.5  273.54
#Mann= 7 ,-1 , 0
  3895.1      .1       0  3979.2     .08       0  4045.9      .1       0
  4079.8     .08       0  4290.5      .1       0    4987     .07       0
    4993      .1       0
Bank Sta=4983.9,5034.3
XS Rating Curve= 0 ,0
Exp/Cntr=0.3,0.1

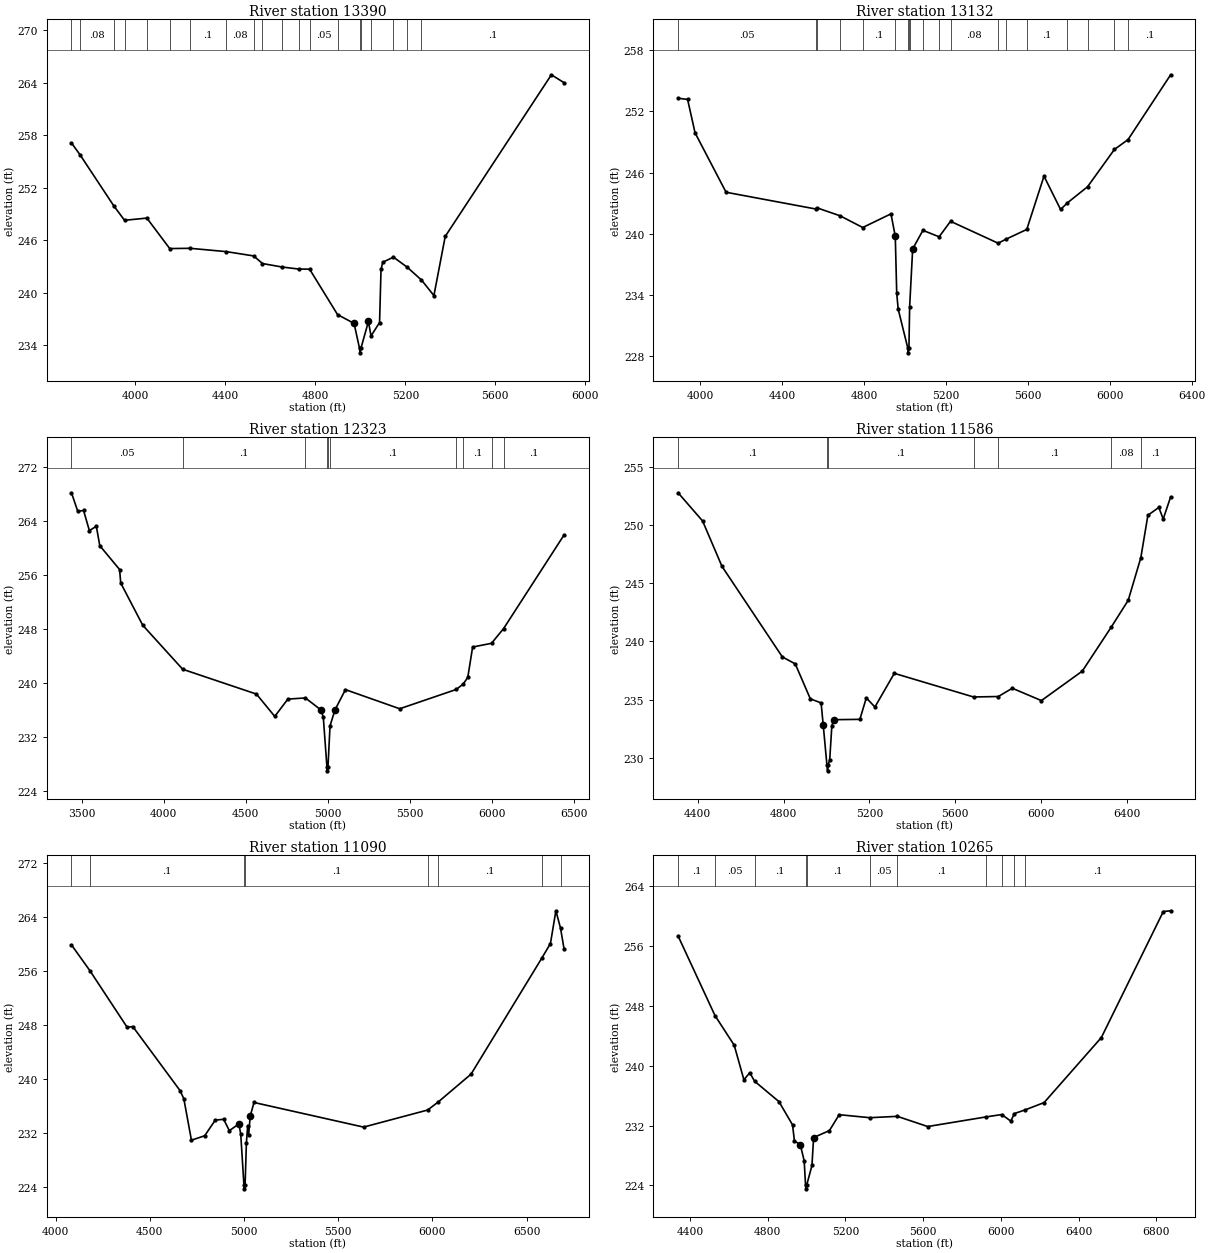
Type RM Length L Ch R = 1 ,13390   ,258,258,258
BEGIN DESCRIPTION:
Mapping XS 47f80d4f
END DESCRIPTION:
XS GIS Cut Line= 4
      2220919.22     13267941.09      2221337.48     13268018.14
      2222229.09     13268755.64       2222833.6      13268810.6
#Sta/Elev= 30
  3715.7  257.12    3753   255.8  3903.2  249.96  3951.5  248.29  4050.8  248.54
  4152.4  245.06  4243.2  245.09    4404  244.71  4525.4  244.22  4564.8  243.35
  4649.8  242.96  4725.6  242.72  4774.1  242.71  4898.4  237.52  4971.9  236.51
  4996.2  233.65  4998.9  233.15  5002.2  233.65  5035.7  236.73  5047.3  235.08
  5085.2  236.61  5091.7  242.67  5099.5   243.5  5147.1  244.08  5208.1  242.93
  5271.5  241.47  5326.8  239.69  5377.1  246.45    5849  264.91  5905.1  264.01
#Mann= 20 ,-1 , 0
  3715.7      .1       0    3753     .08       0  3903.2     .05       0
  3951.5     .08       0  4050.8      .1       0  4152.4     .08       0
  4243.2      .1       0    4404     .08       0  4525.4     .05       0
  4564.8     .08       0  4649.8     .05       0  4725.6     .08       0
  4774.1     .05       0  4898.4     .05       0  4996.2     .04       0
  5002.2     .05       0  5047.3     .05       0  5147.1      .1       0
  5208.1     .05       0  5271.5      .1       0
Bank Sta=4971.9,5035.7
XS Rating Curve= 0 ,0
Exp/Cntr=0.3,0.1

Type RM Length L Ch R = 1 ,13132   ,809,809,809
BEGIN DESCRIPTION:
Mapping XS 13a5c772
END DESCRIPTION:
XS GIS Cut Line= 4
      2220963.18     13268117.18      2221601.66     13268524.48
      2222207.07      13269129.9      2222988.63     13269250.99
#Sta/Elev= 30
  3892.6   253.3    3939  253.18  3975.4   249.9  4126.8  244.07  4563.9  242.43
  4570.8  242.54  4683.2  241.76    4794  240.61  4931.7  241.95  4952.8  239.75
  4959.9  234.15    4967   232.6  5013.5  228.81  5016.3  228.31  5019.5  228.81
  5022.9  232.83  5037.7  238.51  5087.7  240.33  5166.9   239.7  5222.5  241.22
  5454.9  239.07  5492.1  239.45  5594.7  240.42  5678.8  245.65  5759.8  242.38
  5792.5  243.02  5891.4  244.61  6022.5  248.27  6089.2  249.24    6297   255.6
#Mann= 19 ,-1 , 0
  3892.6     .05       0  4563.9     .08       0  4570.8     .05       0
  4683.2     .08       0    4794      .1       0  4952.8     .08       0
  5013.5     .07       0  5019.5     .08       0  5022.9      .1       0
  5087.7     .08       0  5166.9      .1       0  5222.5     .08       0
  5454.9      .1       0  5492.1     .08       0  5594.7      .1       0
  5792.5     .08       0  5891.4      .1       0  6022.5     .08       0
  6089.2      .1       0
Bank Sta=4952.8,5037.7
XS Rating Curve= 0 ,0
Exp/Cntr=0.3,0.1

Type RM Length L Ch R = 1 ,12323   ,737,737,737
BEGIN DESCRIPTION:
LEOPARD CREEK 13.0
END DESCRIPTION:
XS GIS Cut Line= 4
      2220588.94     13268711.58      2221139.34     13269306.02
      2222174.05     13269680.27      2223186.78     13269272.98
#Sta/Elev= 30
  3437.8  268.17  3475.9  265.44  3511.6  265.55  3546.8  262.58  3589.3  263.21
  3610.3  260.35  3731.1  256.82  3737.9  254.83  3872.2  248.58  4115.7  242.07
  4565.2   238.4  4676.8   235.1  4756.6  237.66  4863.4  237.83  4958.7  236.05
  4972.7  234.99    4995  227.55  4997.7  227.05    5001  227.55  5013.7   233.7
  5043.8  236.06  5107.6  239.06  5438.4  236.23  5783.6  239.09  5825.4  239.89
  5853.3  240.87  5882.9  245.36  5997.9  245.91  6071.7  248.09  6439.8  261.92
#Mann= 10 ,-1 , 0
  3437.8     .05       0  4115.7      .1       0  4863.4     .05       0
    4995    .033       0    5001     .05       0  5013.7      .1       0
  5783.6     .08       0  5825.4      .1       0  5997.9     .08       0
  6071.7      .1       0
Bank Sta=4958.7,5043.8
XS Rating Curve= 0 ,0
Exp/Cntr=0.3,0.1

Type RM Length L Ch R = 1 ,11586   ,496,496,496
BEGIN DESCRIPTION:
LEOPARD CREEK 12.0
END DESCRIPTION:
XS GIS Cut Line= 4
      2220864.16     13270186.62      2221326.47     13270142.59
      2221887.85     13270098.56      2223131.69      13269856.4
#Sta/Elev= 30
  4308.7  252.76  4422.8  250.34  4513.2  246.44  4794.4  238.67  4854.6  238.07
  4924.8  235.07    4975  234.72    4985  232.79  5002.1  229.39  5004.8  228.89
  5008.1  229.39  5015.1  229.85  5025.1  232.78  5034.2  233.28  5155.5  233.31
  5185.6  235.15  5225.7  234.37    5316  237.26  5685.2  235.23  5800.6  235.27
  5865.8  235.98  6001.3  234.92  6191.8  237.45  6327.5  241.25  6405.8  243.53
  6464.5  247.18  6497.5  250.83  6548.4   251.5  6568.8  250.51  6603.4   252.4
#Mann= 7 ,-1 , 0
  4308.7      .1       0  5002.1     .07       0  5008.1      .1       0
  5685.2     .05       0  5800.6      .1       0  6327.5     .08       0
  6464.5      .1       0
Bank Sta=4985,5034.2
XS Rating Curve= 0 ,0
Exp/Cntr=0.3,0.1

Type RM Length L Ch R = 1 ,11090   ,825,825,825
BEGIN DESCRIPTION:
LEOPARD CREEK 11.0
END DESCRIPTION:
XS GIS Cut Line= 4
      2220842.15     13270527.85      2221293.45     13270527.85
      2222052.97     13270439.79      2223450.88     13270494.83
#Sta/Elev= 30
  4084.1  259.89  4181.5  256.09  4379.7  247.68  4409.7  247.79  4660.5   238.3
  4680.6  237.09  4720.9  230.95  4791.4  231.61  4847.3  233.92    4892  234.05
  4922.2  232.36  4972.6  233.36  4982.6   231.9  4999.8  224.24  5002.5  223.74
  5005.8  224.24  5012.8  230.55  5019.7  233.12  5024.8  231.77    5033  234.52
  5053.1  236.54    5635  232.89  5975.1  235.42  6031.5  236.62  6205.5  240.74
  6582.4  257.99  6627.1   260.1  6655.8  264.95  6680.6  262.37    6699  259.34
#Mann= 8 ,-1 , 0
  4084.1     .05       0  4181.5      .1       0  4999.8     .07       0
  5005.8      .1       0  5975.1     .05       0  6031.5      .1       0
  6582.4     .08       0  6680.6      .1       0
Bank Sta=4972.6,5033
XS Rating Curve= 0 ,0
Exp/Cntr=0.3,0.1

Type RM Length L Ch R = 1 ,10265   ,533,533,533
BEGIN DESCRIPTION:
LEOPARD CREEK 10.0
END DESCRIPTION:
XS GIS Cut Line= 3
      2220919.15     13271045.21      2221843.82     13271001.17
      2223428.88     13270714.98
#Sta/Elev= 30
    4338  257.31  4527.9  246.69  4626.9  242.73  4676.9  238.11    4707  239.06
  4731.8  237.92  4857.2   235.2  4927.2   232.1  4937.2  229.94  4967.3  229.45
  4987.3  227.29  4994.3  224.05  4997.1  223.55  5000.3  224.05  5027.3  226.67
  5035.8   230.4  5117.4  231.33  5167.5  233.45    5325  233.05    5467  233.23
  5623.3  231.87    5925  233.16  6004.8  233.47  6051.5  232.59  6069.6   233.6
    6125  234.09  6222.9  235.07  6517.6  243.75  6836.7  260.58  6874.4  260.68
#Mann= 11 ,-1 , 0
    4338      .1       0  4527.9     .05       0  4731.8      .1       0
  4994.3     .07       0  5000.3      .1       0    5325     .05       0
    5467      .1       0    5925     .05       0  6004.8      .1       0
  6069.6     .05       0    6125      .1       0
Bank Sta=4967.3,5035.8
XS Rating Curve= 0 ,0
Exp/Cntr=0.3,0.1

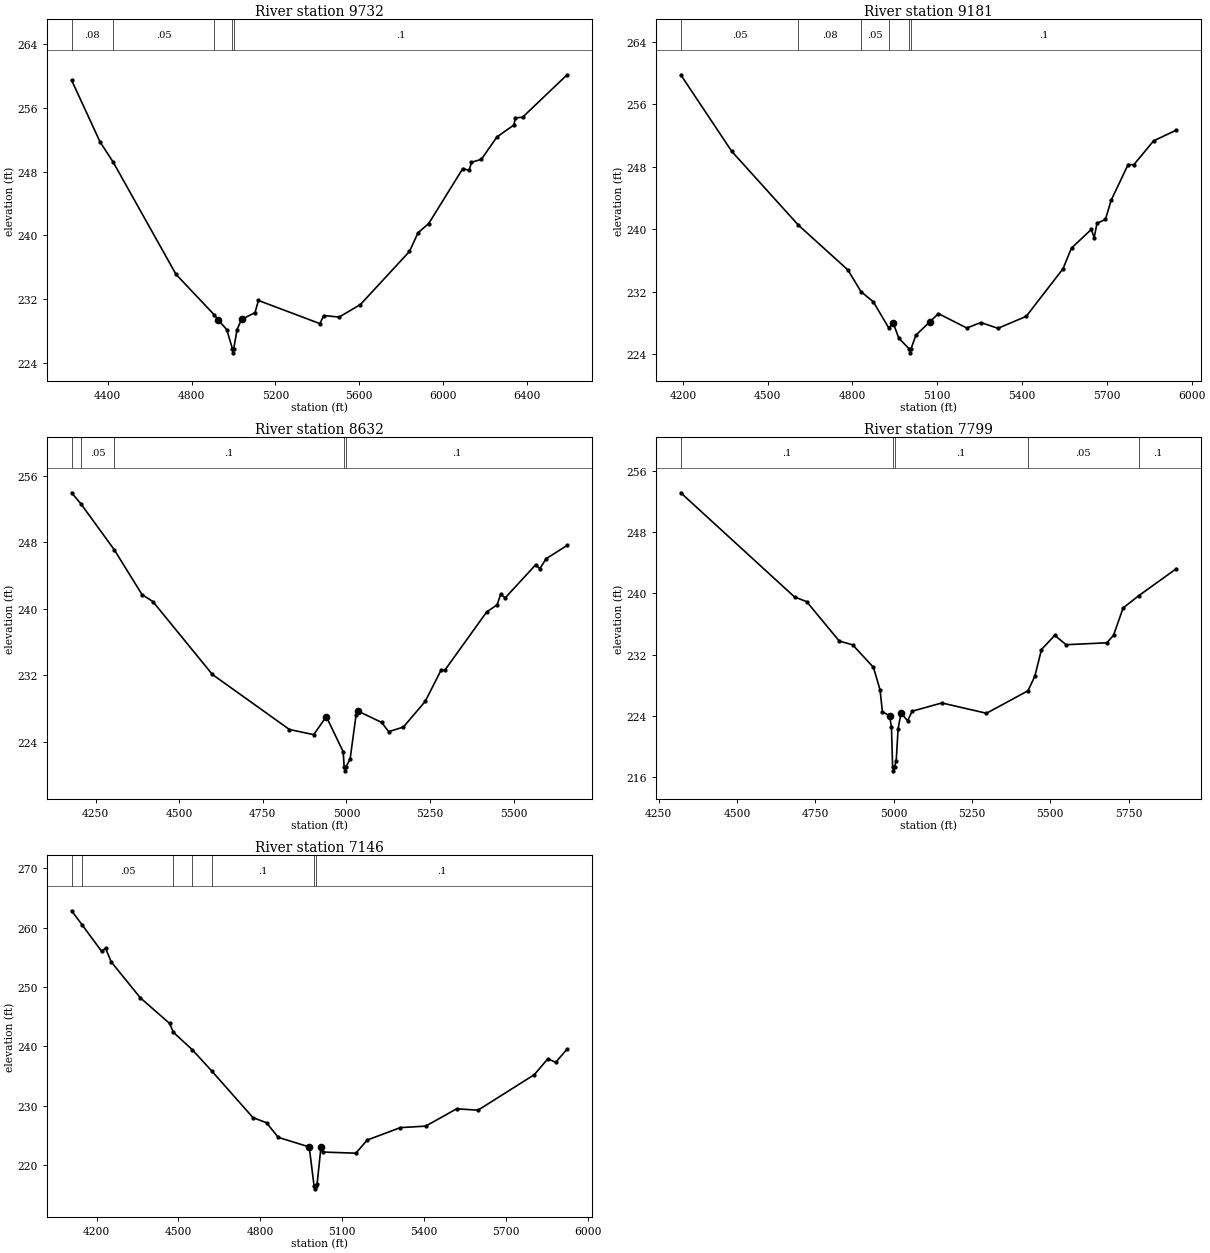
Type RM Length L Ch R = 1 ,9732    ,551,551,551
BEGIN DESCRIPTION:
LEOPARD CREEK 9.0
END DESCRIPTION:
XS GIS Cut Line= 3
      2220853.17     13271353.42      2221909.87     13271485.51
      2223186.79     13271727.68
#Sta/Elev= 30
  4227.4  259.49    4363  251.75  4425.4  249.22  4725.8   235.1  4908.1  230.03
  4927.4  229.36  4967.7  228.17  4994.9  225.75  4997.6  225.25  5000.9  225.75
    5017  228.18  5038.2  229.44  5102.7  230.31  5118.8  231.83  5412.3  228.92
  5430.6  229.94  5503.9  229.74  5605.7  231.32  5839.8  237.99  5880.5  240.33
  5931.4  241.49  6094.2   248.4  6124.7  248.17  6135.7  249.19  6182.9  249.56
  6257.1  252.37  6338.5  253.88  6344.8  254.77  6379.2  254.84    6592  260.18
#Mann= 5 ,-1 , 0
  4227.4     .08       0  4425.4     .05       0  4908.1      .1       0
  4994.9     .07       0  5000.9      .1       0
Bank Sta=4927.4,5038.2
XS Rating Curve= 0 ,0
Exp/Cntr=0.3,0.1

Type RM Length L Ch R = 1 ,9181    ,549,549,549
BEGIN DESCRIPTION:
LEOPARD CREEK 8.0
END DESCRIPTION:
XS GIS Cut Line= 3
      2220787.76     13271946.86      2221587.72     13271996.85
      2222537.69     13272046.85
#Sta/Elev= 30
  4192.7  259.77    4373  249.97  4609.1  240.51  4783.8  234.79  4830.4     232
    4874   230.7  4928.6  227.35  4944.1     228  4964.2  226.03  5001.2  224.67
    5004  224.17  5007.2  224.67  5024.3  226.42  5074.3  228.16  5104.4  229.19
  5204.5  227.35  5254.6  228.05  5314.7  227.31  5414.8  228.84    5545  234.94
    5575  237.59  5645.1  239.97  5655.1  238.92  5665.1  240.74  5695.2  241.26
  5715.2   243.7  5775.3  248.28  5795.3  248.25  5865.4  251.31  5945.5  252.68
#Mann= 6 ,-1 , 0
  4192.7     .05       0  4609.1     .08       0  4830.4     .05       0
  4928.6      .1       0  5001.2     .07       0  5007.2      .1       0
Bank Sta=4944.1,5074.3
XS Rating Curve= 0 ,0
Exp/Cntr=0.3,0.1

Type RM Length L Ch R = 1 ,8632    ,833,833,833
BEGIN DESCRIPTION:
LEOPARD CREEK 7.0
END DESCRIPTION:
XS GIS Cut Line= 3
      2220887.73     13272546.85      2221687.72     13272496.85
       2222337.7     13272296.86
#Sta/Elev= 30
  4178.4  253.95  4207.3  252.56  4305.9   247.1  4388.8  241.72  4421.4  240.87
  4599.2  232.11  4829.7  225.49  4902.3  224.87  4939.9  227.04  4990.4  222.82
  4993.3  221.02    4996  220.52  4999.3  221.02  5011.3  221.99    5029  227.25
  5034.2  227.71  5105.5  226.34  5126.4  225.23  5170.2  225.78  5235.6  228.86
  5283.4  232.65  5293.8  232.59  5419.4  239.62  5450.8  240.48  5461.2  241.74
    5475  241.32  5565.9  245.29  5578.3  244.82  5597.2  246.02    5660  247.62
#Mann= 5 ,-1 , 0
  4178.4     .08       0  4207.3     .05       0  4305.9      .1       0
  4993.3     .07       0  4999.3      .1       0
Bank Sta=4939.9,5034.2
XS Rating Curve= 0 ,0
Exp/Cntr=0.3,0.1

Type RM Length L Ch R = 1 ,7799    ,653,653,653
BEGIN DESCRIPTION:
LEOPARD CREEK 6.0
END DESCRIPTION:
XS GIS Cut Line= 3
       2220963.2     13273334.78      2221414.53     13273125.62
      2222328.12     13272542.25
#Sta/Elev= 30
  4320.8  253.15  4684.2  239.53  4722.6  238.93  4826.6  233.78  4869.5  233.28
  4935.7  230.35  4956.9  227.39  4964.4  224.55  4987.3     224  4993.3  222.54
    4997  217.32  4999.7  216.82    5003  217.32  5008.5  218.15  5014.4   222.3
  5023.7  224.37  5044.9  223.36  5059.3  224.61    5154  225.69  5296.6  224.34
    5429  227.28  5450.9  229.18  5472.1  232.67  5514.4  234.52  5550.8   233.3
  5681.1  233.55  5702.2  234.55  5732.7   238.1  5782.4   239.7  5902.2  243.22
#Mann= 5 ,-1 , 0
  4320.8      .1       0    4997     .07       0    5003      .1       0
    5429     .05       0  5782.4      .1       0
Bank Sta=4987.3,5023.7
XS Rating Curve= 0 ,0
Exp/Cntr=0.3,0.1

Type RM Length L Ch R = 1 ,7146    ,519,519,519
BEGIN DESCRIPTION:
LEOPARD CREEK 5.0
END DESCRIPTION:
XS GIS Cut Line= 3
      2221227.41     13273951.18      2222052.97     13273279.73
      2222636.36     13272806.41
#Sta/Elev= 30
  4108.6  262.84  4147.3  260.45  4218.5  256.01  4232.9  256.52  4253.7  254.22
  4360.7  248.15  4467.8  243.84  4481.4  242.35  4550.5  239.43  4621.8  235.84
    4773  227.98  4822.6  227.11  4865.7  224.65  4979.1  223.03  4996.9  216.47
  4999.7  215.97  5002.9  216.47  5007.9  216.73  5022.2  223.01  5028.7  222.17
  5150.1  221.98  5191.7   224.2  5313.1  226.29  5405.8  226.54  5519.3  229.46
  5597.6  229.23  5803.8  235.21  5853.4  237.89  5882.1  237.29    5924  239.53
#Mann= 7 ,-1 , 0
  4108.6      .1       0  4147.3     .05       0  4481.4      .1       0
  4550.5     .05       0  4621.8      .1       0  4996.9     .07       0
  5002.9      .1       0
Bank Sta=4979.1,5022.2
XS Rating Curve= 0 ,0
Exp/Cntr=0.3,0.1