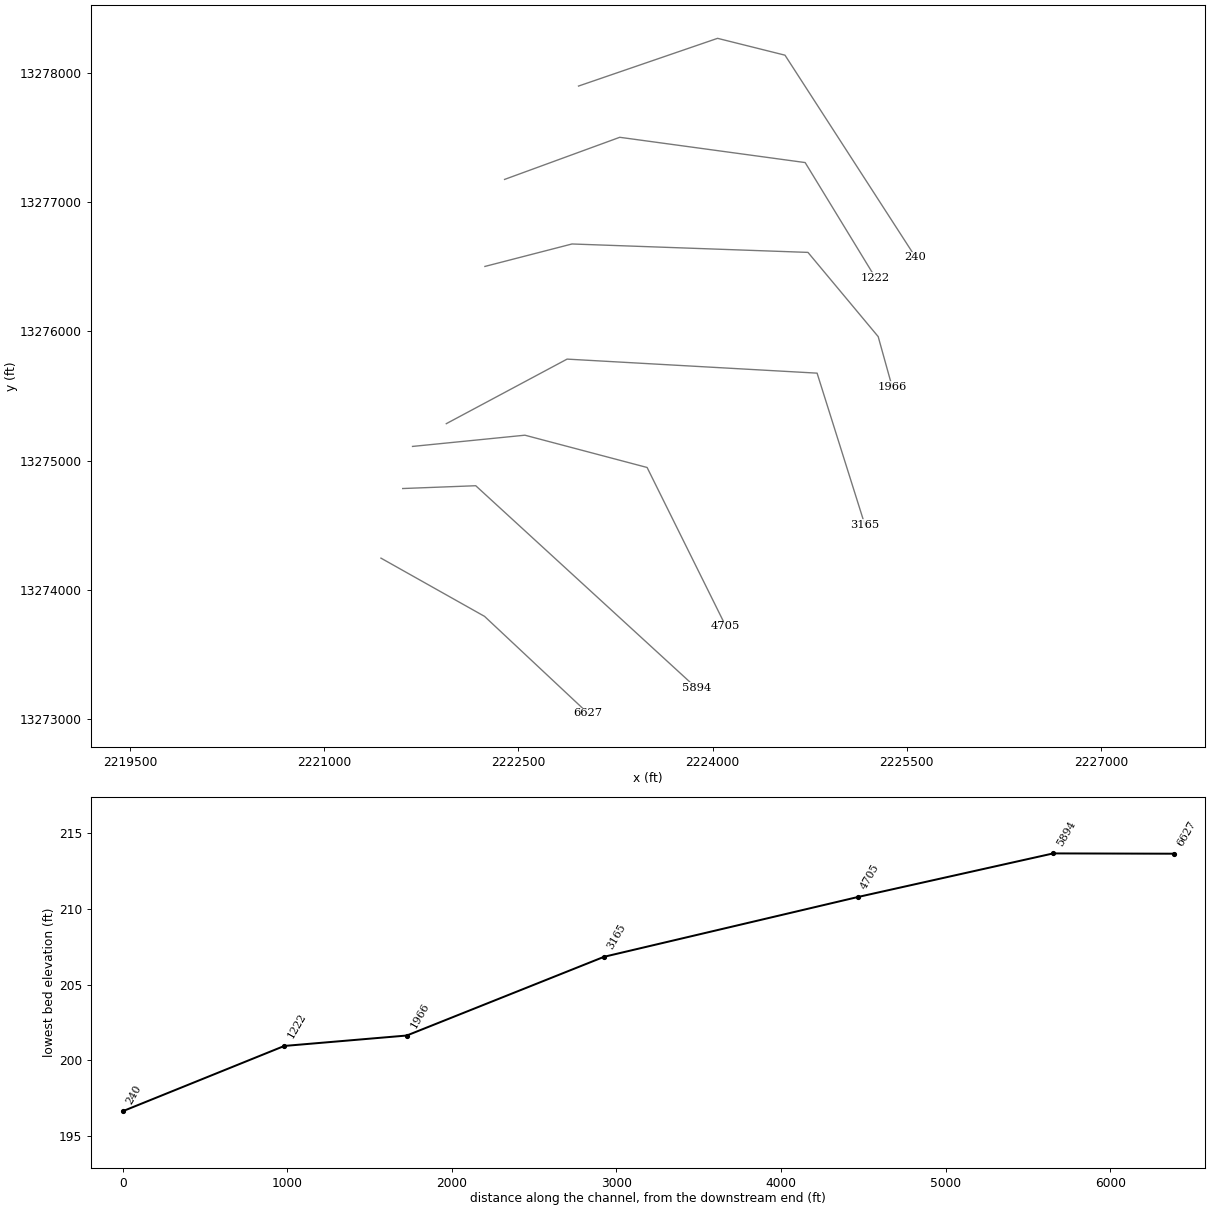
HEC-RAS study LEOPARD CREEK.prj: LEOPARD CREEK Base Level Engineering

--- LEOPARD CREEK.g01 (geometry) --- (continued)

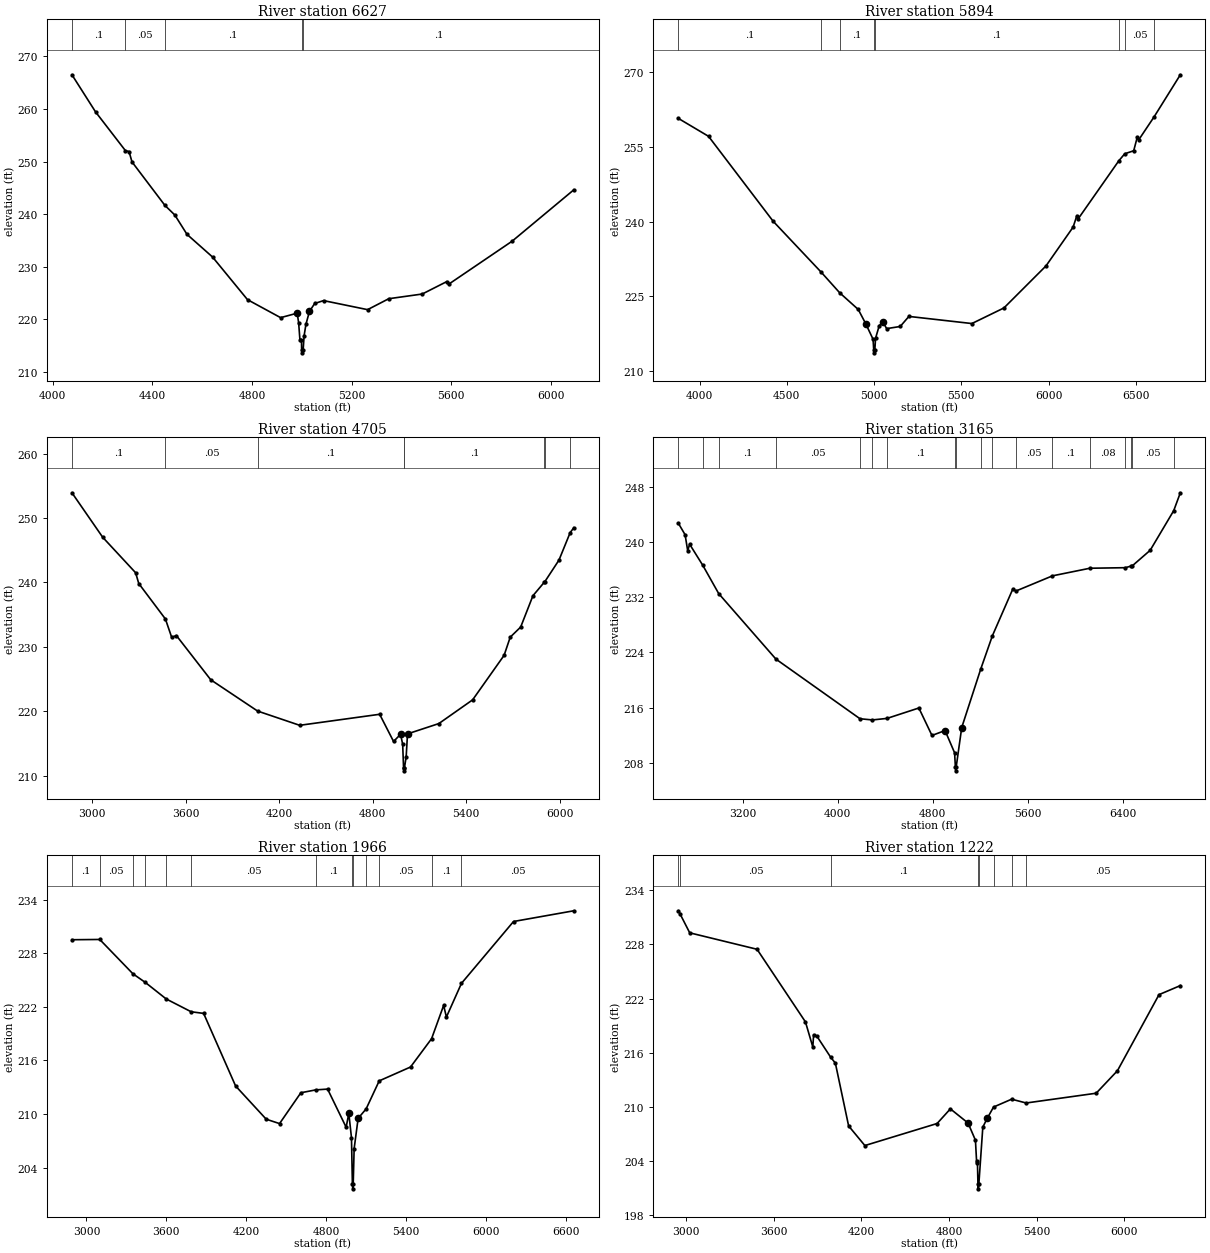
Type RM Length L Ch R = 1 ,6627    ,733,733,733
BEGIN DESCRIPTION:
LEOPARD CREEK 4.0
END DESCRIPTION:
XS GIS Cut Line= 3
      2221437.68     13274246.88      2222237.72     13273796.85
      2223037.71     13273046.86
#Sta/Elev= 30
  4077.3  266.52    4172  259.47  4292.1  252.09  4306.5  251.93  4318.3  249.96
  4450.5  241.69  4490.1  239.87  4539.2  236.18  4641.8  231.87    4782  223.77
  4914.9  220.35  4981.5   221.2  4987.3  219.37  4992.4  216.15  4998.7  216.15
  4999.3  214.16  5002.1  213.66  5005.3  214.16  5009.2  216.89  5016.5  219.06
  5030.6  221.53  5051.7  223.04  5087.3  223.59  5264.1  221.87  5349.1  223.95
  5483.4  224.84  5582.6  227.22  5589.4   226.7  5844.4  234.89  6091.8  244.65
#Mann= 5 ,-1 , 0
  4077.3      .1       0  4292.1     .05       0  4450.5      .1       0
  4999.3     .07       0  5005.3      .1       0
Bank Sta=4981.5,5030.6
XS Rating Curve= 0 ,0
Exp/Cntr=0.3,0.1

Type RM Length L Ch R = 1 ,5894    ,1189,1189,1189
BEGIN DESCRIPTION:
LEOPARD CREEK 3.0
END DESCRIPTION:
XS GIS Cut Line= 3
      2221605.61     13274784.94      2222169.83     13274806.64
      2223873.06     13273244.44
#Sta/Elev= 30
  3879.5  260.72  4051.7  257.14    4422  240.09  4696.8  229.89  4803.7  225.72
  4909.6  222.39  4952.2  219.55  4994.7   216.4  4998.5  214.18  5001.3  213.68
  5004.5  214.18  5008.9   216.6  5029.9  219.14  5051.4  219.85  5072.4  218.54
  5150.1  218.97    5200  220.99  5560.8  219.56  5744.5  222.69  5985.6  231.13
    6141  238.92  6162.6  241.23  6169.4  240.55  6402.5  252.21  6436.9  253.64
  6488.1  254.24  6509.1  257.03  6516.5  256.41  6604.7  261.03  6755.3  269.49
#Mann= 8 ,-1 , 0
  3879.5      .1       0  4696.8     .05       0  4803.7      .1       0
  4998.5     .07       0  5004.5      .1       0  6402.5     .08       0
  6436.9     .05       0  6604.7      .1       0
Bank Sta=4952.2,5051.4
XS Rating Curve= 0 ,0
Exp/Cntr=0.3,0.1

Type RM Length L Ch R = 1 ,4705    ,1540,1540,1540
BEGIN DESCRIPTION:
Mapping XS 185df61c
END DESCRIPTION:
XS GIS Cut Line= 4
      2221681.54     13275110.46       2222549.6     13275197.26
      2223493.61      13274947.7      2224101.17     13273721.72
#Sta/Elev= 30
    2872  253.91  3069.2  247.01  3280.2  241.51  3300.3  239.84  3471.1  234.34
  3511.4  231.49  3541.5  231.77  3761.8  224.91  4062.2  220.06    4332  217.85
  4844.5  219.56  4933.8  215.34  4978.5  216.46  4992.1  214.92  4997.8  211.29
  5000.5  210.79  5003.8  211.29  5014.6     213  5023.1  216.52    5224  218.12
  5440.6   221.8  5642.3   228.7  5681.6  231.52  5748.6  233.09  5827.3  237.95
  5901.1  240.07  5902.5  240.09  5994.1  243.47  6065.8  247.73  6089.1  248.49
#Mann= 8 ,-1 , 0
    2872      .1       0  3471.1     .05       0  4062.2      .1       0
  4997.8     .07       0  5003.8      .1       0  5901.1     .08       0
  5902.5     .05       0  6065.8      .1       0
Bank Sta=4978.5,5023.1
XS Rating Curve= 0 ,0
Exp/Cntr=0.3,0.1

Type RM Length L Ch R = 1 ,3165    ,1199,1199,1199
BEGIN DESCRIPTION:
LEOPARD CREEK 2.0
END DESCRIPTION:
XS GIS Cut Line= 4
      2221942.33      13275286.3      2222875.45     13275785.41
      2224806.88      13275676.9      2225175.81       13274505.
#Sta/Elev= 30
  2660.6   242.7  2716.3  241.07  2738.2  238.75  2754.5  239.69  2864.6  236.65
  2999.2  232.53  3480.2  223.04  4187.6  214.39    4292  214.22  4414.6  214.44
  4682.6  215.95  4792.8  211.97    4903  212.68  4983.1  209.46  4990.1  207.34
  4992.8  206.84  4996.1  207.34  5043.2  213.12  5202.6  221.57  5301.1  226.42
  5473.9  233.24  5498.1   232.9  5806.7  235.11  6120.8  236.21  6419.6  236.29
  6464.1  236.51  6477.9  236.56  6628.3  238.81  6826.4  244.56  6881.9  247.15
#Mann= 18 ,-1 , 0
  2660.6      .1       0  2864.6     .05       0  2999.2      .1       0
  3480.2     .05       0  4187.6      .1       0    4292     .05       0
  4414.6      .1       0  4990.1     .07       0  4996.1      .1       0
  5202.6     .08       0  5301.1      .1       0  5498.1     .05       0
  5806.7      .1       0  6120.8     .08       0  6419.6      .1       0
  6464.1     .08       0  6477.9     .05       0  6826.4      .1       0
Bank Sta=4903,5043.2
XS Rating Curve= 0 ,0
Exp/Cntr=0.3,0.1

Type RM Length L Ch R = 1 ,1966    ,744,744,744
BEGIN DESCRIPTION:
Mapping XS 1baf1021
END DESCRIPTION:
XS GIS Cut Line= 5
      2222240.73     13276501.84      2222913.46     13276675.45
      2224736.38     13276610.34      2225278.91      13275959.3
      2225386.98     13275570.25
#Sta/Elev= 30
  2891.1   229.5    3100  229.53  3349.2  225.69  3442.6  224.72  3599.6  222.87
  3786.9  221.44  3880.3  221.26  4120.5  213.14  4350.6  209.42  4450.7  208.93
  4610.8  212.38  4722.6   212.7  4811.6  212.79    4951  208.52    4971  210.07
    4991  207.36    4998  202.13  5000.8  201.63    5004  202.13    5011  206.12
  5041.1  209.52    5101  210.57  5199.4  213.71  5434.7  215.26  5592.9  218.43
  5683.4  222.15  5704.2  220.85  5817.3  224.62  6208.5  231.54  6661.2  232.74
#Mann= 13 ,-1 , 0
  2891.1      .1       0    3100     .05       0  3349.2      .1       0
  3442.6     .05       0  3599.6      .1       0  3786.9     .05       0
  4722.6      .1       0    4998     .07       0    5004      .1       0
    5101     .08       0  5199.4     .05       0  5592.9      .1       0
  5817.3     .05       0
Bank Sta=4971,5041.1
XS Rating Curve= 0 ,0
Exp/Cntr=0.3,0.1

Type RM Length L Ch R = 1 ,1222    ,982,982,982
BEGIN DESCRIPTION:
Mapping XS b021463f
END DESCRIPTION:
XS GIS Cut Line= 4
      2222392.64     13277174.58      2223282.39      13277500.1
      2224714.68     13277304.79      2225257.22     13276415.02
#Sta/Elev= 30
  2947.4  231.71  2960.2   231.3  3024.4  229.27  3485.2  227.45  3816.6  219.41
    3867  216.63  3872.4     218  3894.8  217.83  3988.9  215.51  4021.3  214.85
  4112.1   207.9  4223.2  205.73  4717.7  208.17  4808.5  209.79  4929.6  208.22
  4980.1  206.32  4988.6  203.77  4993.6  204.01  4997.3  201.44    5000  200.94
  5003.3  201.44  5030.6  207.77  5060.8  208.74  5103.9  209.99  5227.8  210.86
  5327.3  210.44  5806.4  211.52  5952.1  214.01  6236.7  222.43  6382.5  223.43
#Mann= 8 ,-1 , 0
  2947.4     .08       0  2960.2     .05       0  3988.9      .1       0
  4997.3     .07       0  5003.3      .1       0  5103.9     .05       0
  5227.8     .08       0  5327.3     .05       0
Bank Sta=4929.6,5060.8
XS Rating Curve= 0 ,0
Exp/Cntr=0.3,0.1

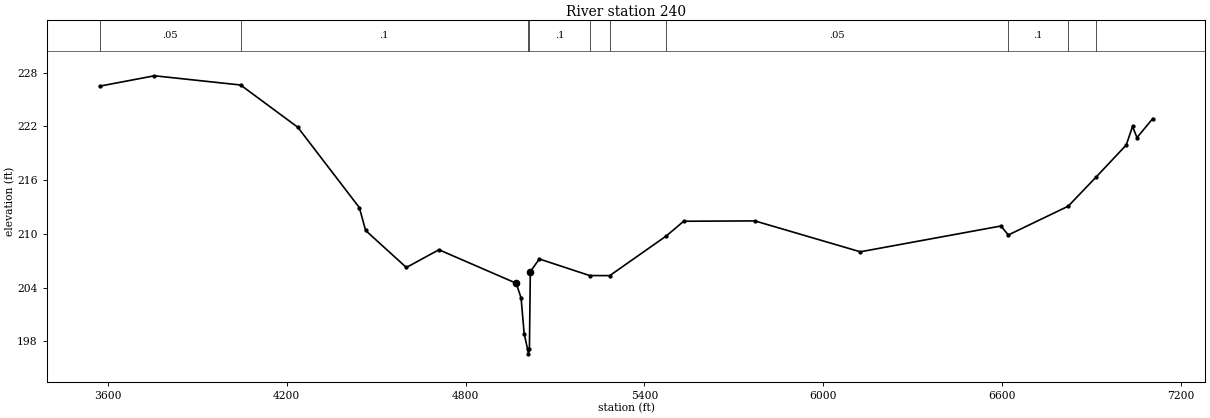
Type RM Length L Ch R = 1 ,240     ,0,0,0
BEGIN DESCRIPTION:
LEOPARD CREEK 1.0
END DESCRIPTION:
XS GIS Cut Line= 4
      2222963.82     13277896.19      2224038.01     13278265.11
      2224558.85      13278134.9      2225567.98     13276572.38
#Sta/Elev= 30
  3572.5   226.5  3756.4  227.66  4045.4  226.63    4237  221.92  4443.6  212.95
  4464.8  210.39  4601.4  206.26  4710.7  208.24  4969.9   204.5  4986.3  202.85
  4996.6  198.87  5008.2  197.12  5010.9  196.62  5014.2  197.12  5017.2  205.79
  5047.3  207.21  5216.2  205.36  5283.7  205.35  5473.4  209.78  5531.6  211.42
  5770.5  211.46  6124.1  208.01  6595.9  210.89  6620.7  209.89  6821.5   213.1
  6915.3  216.36  7016.2  219.93  7037.3     222  7052.3  220.76  7105.2  222.88
#Mann= 10 ,-1 , 0
  3572.5     .05       0  4045.4      .1       0  5008.2     .07       0
  5014.2      .1       0  5216.2     .05       0  5283.7     .08       0
  5473.4     .05       0  6620.7      .1       0  6821.5     .05       0
  6915.3      .1       0
Bank Sta=4969.9,5017.2
XS Rating Curve= 0 ,0
Exp/Cntr=0.3,0.1

Chan Stop Cuts=-1
Use User Specified Reach Order=0
Composite Channel Slope=5