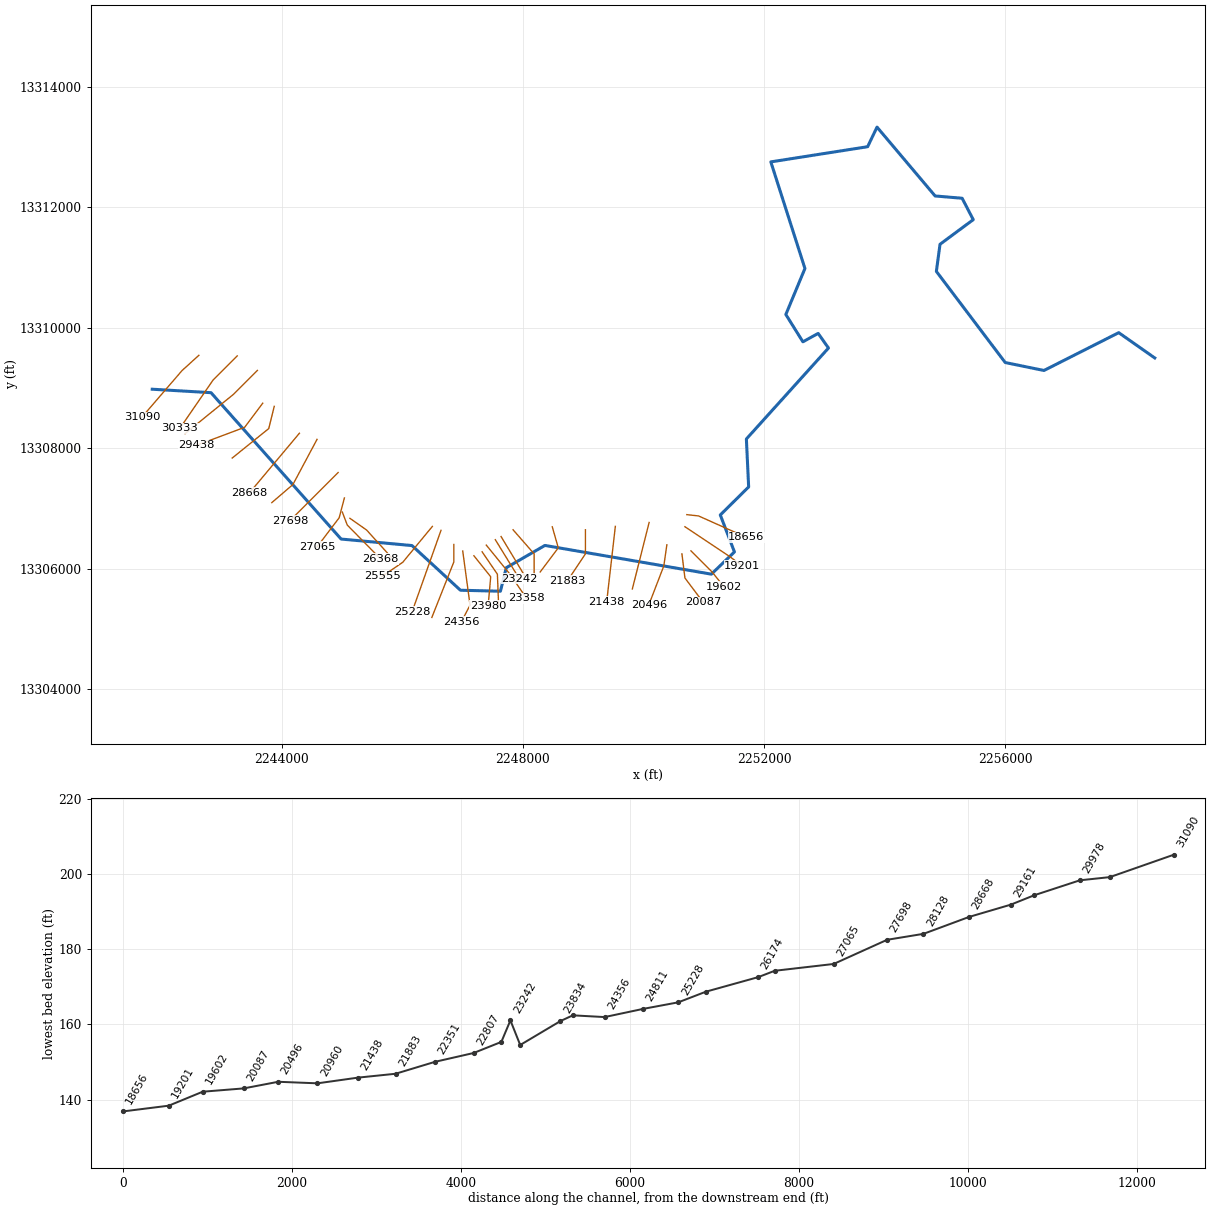
--- MCKIMZEY CREEK.prj (project) ---

Proj Title=MCKIMZEY CREEK Base Level Engineering
Current Plan=p01
Default Exp/Contr=0.3,0.1
English Units
Geom File=g01
Flow File=f01
Plan File=p01
Y Axis Title=Elevation
X Axis Title(PF)=Main Channel Distance
X Axis Title(XS)=Station
BEGIN DESCRIPTION:
MCKIMZEY CREEK
END DESCRIPTION:
DSS Export Rating Curves= 0
DSS Export Rating Curve Sorted= 0
DSS Export Volume Flow Curves= 0
DXF OffsetX= 0
DXF OffsetY= 0
DXF ScaleX= 1
DXF ScaleY= 10

--- MCKIMZEY CREEK.p01 (plan) ---

Plan Title=Multiple Run
Short Identifier=Multiple
Geom File=g01
Flow File=f01
Subcritical Flow
K Sum by GR= 0
Std Step Tol= 0.01
Critical Tol= 0.01
Num of Std Step Trials= 20
Max Error Tol= 0.3
Flow Tol Ratio= 0.001
Split Flow NTrial= 30
Split Flow Tol= 0.02
Split Flow Ratio= 0.02
Log Output Level= 0
Friction Slope Method= 1
Unsteady Friction Slope Method= 2
Unsteady Bridges Friction Slope Method= 1
Parabolic Critical Depth
Global Vel Dist=  1 , 1 , 1
Global Log Level= 0
CheckData=True
Encroach Param= -1, 0, 0, 0
BEGIN DESCRIPTION:
Multiple Run
END DESCRIPTION:

--- MCKIMZEY CREEK.f01 (steady flow) ---

Flow Title=Multiple
Program Version=4.10
Number of Profiles= 7
Profile Names=10-year,25-year,50-year,1pct_min,100-year,1pct_plu,500-year
River Rch & RM=MCKIMZEY CREEK,Reach-1         ,31090
     219     303     374     339     459     620     701
River Rch & RM=MCKIMZEY CREEK,Reach-1         ,30333
     288     404     502     459     621     839     962
River Rch & RM=MCKIMZEY CREEK,Reach-1         ,25228
     492     708     893     827    1118    1512    1782
River Rch & RM=MCKIMZEY CREEK,Reach-1         ,24811
     492     708     893     827    1118    1512    1782
River Rch & RM=MCKIMZEY CREEK,Reach-1         ,17933
     573     827    1045     970    1311    1773    2096
River Rch & RM=MCKIMZEY CREEK,Reach-1         ,8047
     905    1326    1694    1585    2144    2899    3488
Boundary for River Rch & Prof#=MCKIMZEY CREEK,Reach-1         , 1
Up Type= 0
Dn Type= 3
Dn Slope=0.005
Boundary for River Rch & Prof#=MCKIMZEY CREEK,Reach-1         , 2
Up Type= 0
Dn Type= 3
Dn Slope=0.005
Boundary for River Rch & Prof#=MCKIMZEY CREEK,Reach-1         , 3
Up Type= 0
Dn Type= 3
Dn Slope=0.005
Boundary for River Rch & Prof#=MCKIMZEY CREEK,Reach-1         , 4
Up Type= 0
Dn Type= 3
Dn Slope=0.005
Boundary for River Rch & Prof#=MCKIMZEY CREEK,Reach-1         , 5
Up Type= 0
Dn Type= 3
Dn Slope=0.005
Boundary for River Rch & Prof#=MCKIMZEY CREEK,Reach-1         , 6
Up Type= 0
Dn Type= 3
Dn Slope=0.005
Boundary for River Rch & Prof#=MCKIMZEY CREEK,Reach-1         , 7
Up Type= 0
Dn Type= 3
Dn Slope=0.005
DSS Import GetInterval= 0
DSS Import GetPeak= 0
DSS Import FillOption= 0

--- MCKIMZEY CREEK.g01 (geometry) ---

Geom Title=Existing Conditions
Program Version=4.10

River Reach=MCKIMZEY CREEK  ,Reach-1
Reach XY= 30
      2241855.36     13308978.65      2242830.28     13308920.96
      2244986.39     13306492.91      2246161.87     13306384.79
      2246965.63     13305643.57       2247628.6      13305627.3
      2247724.84     13306016.64      2248366.07     13306386.71
      2251126.36     13305910.14      2251508.38      13306279.1
        2251274.     13306892.38      2251744.05     13307357.22
      2251706.44     13308153.07       2253067.6     13309662.14
      2252896.51     13309904.18      2252643.46     13309765.07
       2252360.7     13310218.09      2252677.38     13310981.49
      2252111.99     13312750.02      2253716.88     13313001.86
      2253872.54     13313326.96      2254835.79     13312184.71
       2255283.7     13312146.51      2255468.22     13311791.59
      2254916.98     13311383.07      2254856.55     13310933.07
      2255997.99      13309421.3      2256640.79     13309289.37
      2257880.41      13309916.8      2258477.72     13309496.85

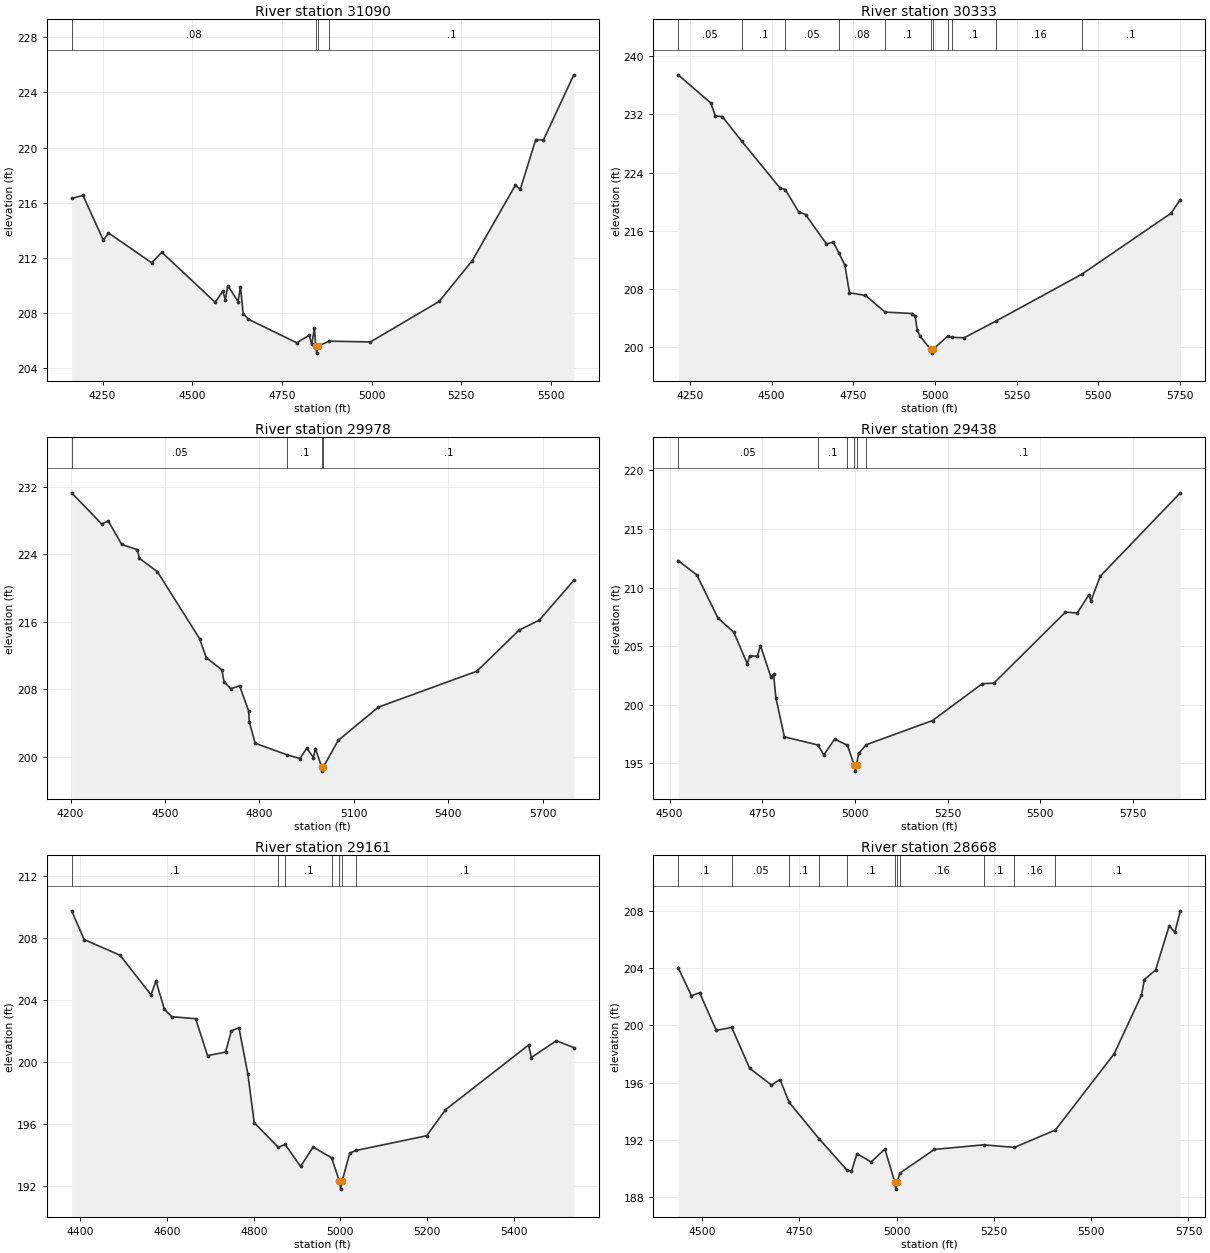
Type RM Length L Ch R = 1 ,31090   ,757,757,757
BEGIN DESCRIPTION:
MCKIMZEY CREEK 45.0
END DESCRIPTION:
XS GIS Cut Line= 3
      2242628.38     13309541.04      2242350.62     13309289.32
      2241682.49     13308512.73
#Sta/Elev= 30
    4164  216.32  4195.6  216.54  4252.4  213.29  4266.6  213.82  4386.9  211.66
  4415.3  212.42  4564.1  208.79    4585   209.6  4592.6  208.99  4599.2  210.01
  4627.7  208.85  4634.4  209.91    4642  207.98  4656.3  207.57  4791.2  205.86
  4826.3  206.41  4832.9  205.74  4840.6  206.92  4844.2  205.61    4847  205.11
  4850.2  205.61  4881.5  205.98  4996.4  205.92  5188.4  208.86  5280.6  211.82
  5400.2  217.27  5414.5     217  5457.3  220.59  5478.7  220.55  5563.3  225.28
#Mann= 4 ,-1 , 0
    4164     .08       0  4844.2     .07       0  4850.2     .08       0
  4881.5      .1       0
Bank Sta=4844.2,4850.2
XS Rating Curve= 0 ,0
Exp/Cntr=0.3,0.1

Type RM Length L Ch R = 1 ,30333   ,355,355,355
BEGIN DESCRIPTION:
MCKIMZEY CREEK 44.0
END DESCRIPTION:
XS GIS Cut Line= 3
      2243264.38      13309531.3      2242864.41     13309131.34
      2242314.57     13308331.55
#Sta/Elev= 30
  4214.3  237.46  4314.1  233.58  4328.2   231.8  4349.4  231.71  4408.1  228.36
  4526.2  221.87  4541.9  221.67  4582.8  218.61    4604  218.23  4667.6   214.2
  4688.8  214.42  4706.1  212.94  4724.2  211.27  4738.3  207.46  4787.2  207.09
  4847.4   204.8    4931   204.6  4939.4  204.22  4945.5  202.35  4954.3  201.48
  4987.2  199.65  4989.9  199.15  4993.2  199.65  5040.5  201.54    5051  201.33
  5088.9  201.26  5187.8  203.59  5450.2  210.04  5722.2  218.41  5750.5  220.29
#Mann= 11 ,-1 , 0
  4214.3     .05       0  4408.1      .1       0  4541.9     .05       0
  4706.1     .08       0  4847.4      .1       0  4987.2     .07       0
  4993.2      .1       0  5040.5     .16       0    5051      .1       0
  5187.8     .16       0  5450.2      .1       0
Bank Sta=4987.2,4993.2
XS Rating Curve= 0 ,0
Exp/Cntr=0.3,0.1

Type RM Length L Ch R = 1 ,29978   ,540,540,540
BEGIN DESCRIPTION:
MCKIMZEY CREEK 43.0
END DESCRIPTION:
XS GIS Cut Line= 3
       2243598.7     13309290.79      2243198.69     13308890.78
      2242399.37     13308241.34
#Sta/Elev= 30
  4203.3  231.27  4298.7  227.58  4319.9  227.93  4362.3  225.15  4411.8  224.54
  4418.9  223.49  4475.5  221.94  4609.8     214    4631  211.74  4680.5  210.31
  4687.6  208.88  4708.8  208.07  4737.1   208.4  4765.4  205.46  4768.2   204.1
  4786.4   201.6  4887.9  200.23  4928.6  199.79  4950.6  201.02  4971.7  199.91
  4978.1  200.97  4997.4   198.8  5000.2   198.3  5003.4   198.8    5050  201.93
  5177.9  205.88  5491.1  210.14  5625.4  215.01  5689.3  216.18  5798.9   220.9
#Mann= 4 ,-1 , 0
  4203.3     .05       0  4887.9      .1       0  4997.4     .07       0
  5003.4      .1       0
Bank Sta=4997.4,5003.4
XS Rating Curve= 0 ,0
Exp/Cntr=0.3,0.1

Type RM Length L Ch R = 1 ,29438   ,277,277,277
BEGIN DESCRIPTION:
MCKIMZEY CREEK 42.0
END DESCRIPTION:
XS GIS Cut Line= 3
      2243687.72     13308746.85      2243387.72     13308346.85
      2242587.72     13308046.85
#Sta/Elev= 30
  4523.3   212.3  4573.3  211.09  4630.6   207.4  4673.3  206.19  4709.8  203.49
    4716  204.18  4736.8  204.13  4745.2  205.05  4773.3  202.38  4780.6  202.58
  4786.8   200.6  4809.8  197.26  4900.3  196.56    4916  195.71  4945.2  197.06
  4979.6  196.55  4998.4  194.83  5001.2  194.33  5004.4  194.83  5009.8  195.85
  5031.1  196.59  5209.3  198.65  5343.7   201.8  5374.8  201.84    5568  207.91
    5600  207.83  5631.2   209.4  5636.5  208.84  5661.4  210.96  5877.7  218.09
#Mann= 6 ,-1 , 0
  4523.3     .05       0  4900.3      .1       0  4979.6     .07       0
  4998.4     .07       0  5004.4     .07       0  5031.1      .1       0
Bank Sta=4998.4,5004.4
XS Rating Curve= 0 ,0
Exp/Cntr=0.3,0.1

Type RM Length L Ch R = 1 ,29161   ,493,493,493
BEGIN DESCRIPTION:
MCKIMZEY CREEK 41.0
END DESCRIPTION:
XS GIS Cut Line= 3
       2243878.4     13308694.71      2243787.25     13308325.78
      2243181.17     13307836.58
#Sta/Elev= 30
  4379.8  209.76  4408.6  207.91  4491.5   206.9    4563  204.35  4574.4  205.24
  4593.9  203.42  4610.6  202.94    4666  202.81  4693.5  200.43    4735  200.66
  4748.4  202.03  4765.9  202.23  4786.7  199.22  4801.1  196.11  4856.5  194.53
  4872.6  194.71  4908.2  193.29    4937  194.54  4979.7  193.85  4997.9  192.33
  5000.7  191.83  5003.9  192.33  5021.7  194.15  5035.9  194.32  5199.3  195.27
  5242.4  196.94  5434.3  201.11  5440.8  200.31  5498.3  201.39  5538.7  200.95
#Mann= 7 ,-1 , 0
  4379.8      .1       0  4856.5     .05       0  4872.6      .1       0
  4979.7     .07       0  4997.9     .07       0  5003.9     .07       0
  5035.9      .1       0
Bank Sta=4997.9,5003.9
XS Rating Curve= 0 ,0
Exp/Cntr=0.3,0.1

Type RM Length L Ch R = 1 ,28668   ,540,540,540
BEGIN DESCRIPTION:
MCKIMZEY CREEK 40.0
END DESCRIPTION:
XS GIS Cut Line= 2
      2244295.08     13308247.67       2243466.1     13307258.11
#Sta/Elev= 30
  4438.2  204.02  4472.4  202.05  4493.3  202.27  4536.2  199.64  4575.8  199.85
  4621.9     197    4678  195.83  4700.1  196.21  4723.5  194.62  4800.9  192.07
  4871.1  189.93  4883.6  189.81  4897.9  191.05  4934.3  190.46  4969.5  191.37
  4995.1  189.07  4997.8  188.57  5001.1  189.07  5008.2  189.69    5097  191.34
  5223.5  191.66  5302.5  191.48  5407.8  192.69  5558.9     198  5629.1  202.09
  5636.9  203.19  5665.5  203.85  5700.7  206.95    5715  206.48  5729.1  207.98
#Mann= 11 ,-1 , 0
  4438.2      .1       0  4575.8     .05       0  4723.5      .1       0
  4800.9     .05       0  4871.1      .1       0  4995.1     .07       0
  5001.1      .1       0  5008.2     .16       0  5223.5      .1       0
  5302.5     .16       0  5407.8      .1       0
Bank Sta=4995.1,5001.1
XS Rating Curve= 0 ,0
Exp/Cntr=0.3,0.1

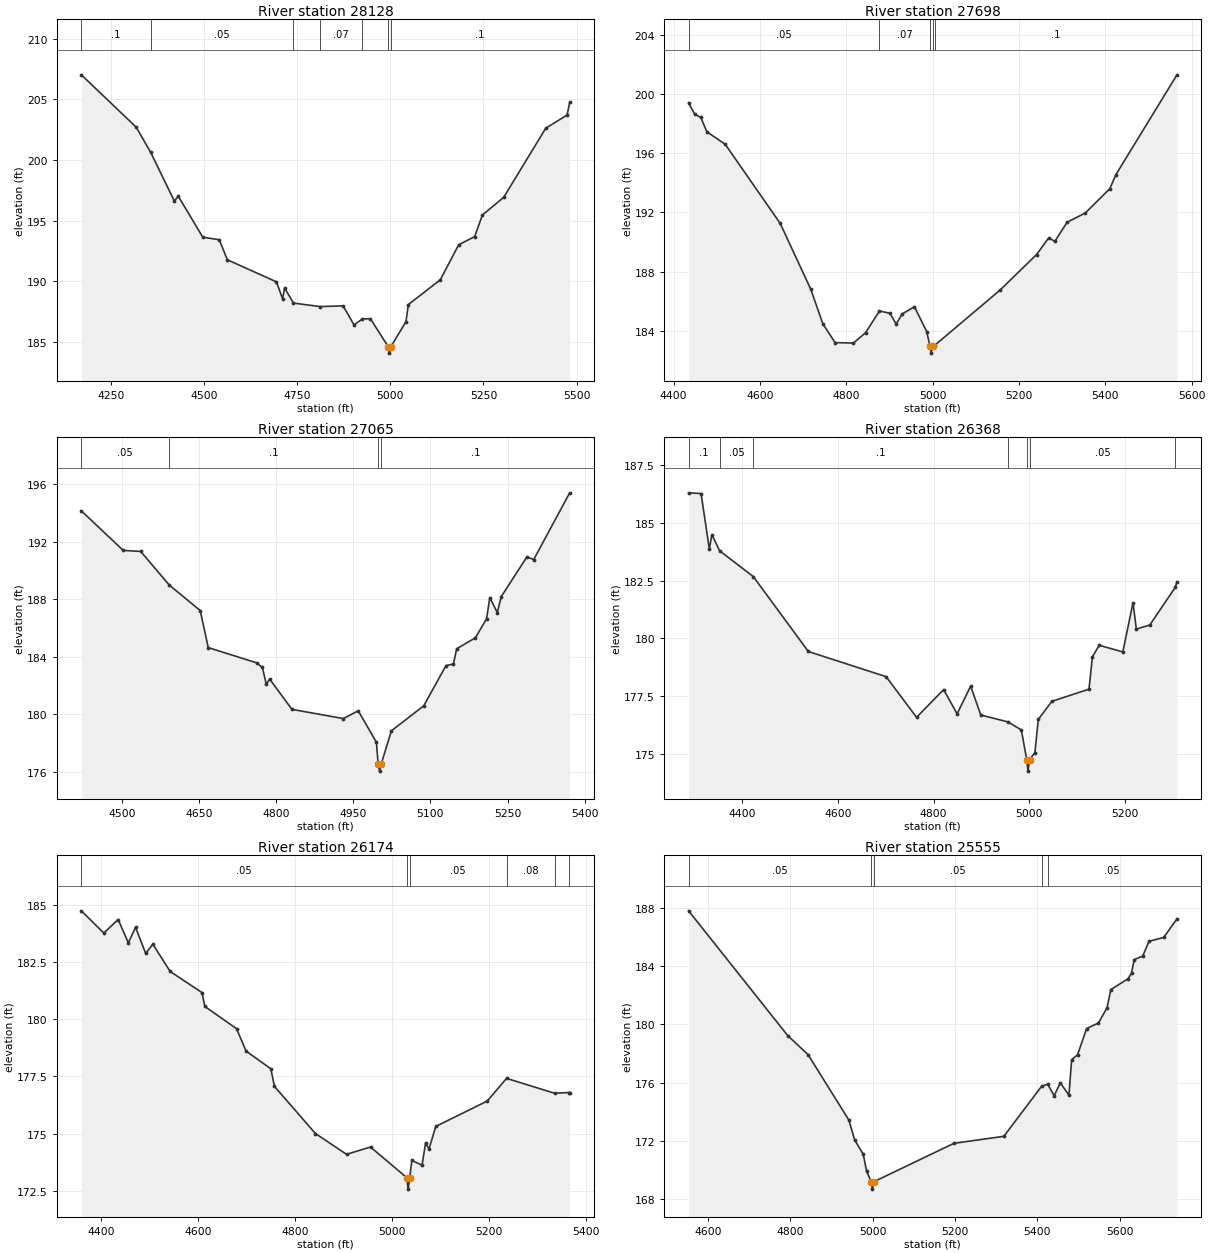
Type RM Length L Ch R = 1 ,28128   ,430,430,430
BEGIN DESCRIPTION:
MCKIMZEY CREEK 39.0
END DESCRIPTION:
XS GIS Cut Line= 3
       2244587.7     13308146.82      2244187.72     13307396.85
      2243837.75     13307096.88
#Sta/Elev= 30
  4170.6  207.03  4317.9  202.71  4356.5  200.65  4420.2  196.62  4430.9  197.01
  4496.7  193.63  4540.7  193.43  4562.6  191.77  4694.4  189.95  4710.7  188.55
  4716.3  189.44    4740   188.2  4811.4  187.91  4873.2  187.97  4902.6   186.4
  4925.1  186.89  4946.5  186.91  4994.9  184.57  4997.6  184.07  5000.9  184.57
    5042  186.67  5048.5  188.08  5134.2  190.12  5183.5  193.01  5226.3  193.68
  5247.2  195.47  5304.3  196.92  5417.3  202.63  5474.4  203.71  5481.5  204.75
#Mann= 7 ,-1 , 0
  4170.6      .1       0  4356.5     .05       0    4740      .1       0
  4811.4     .07       0  4925.1      .1       0  4994.9     .07       0
  5000.9      .1       0
Bank Sta=4994.9,5000.9
XS Rating Curve= 0 ,0
Exp/Cntr=0.3,0.1

Type RM Length L Ch R = 1 ,27698   ,633,633,633
BEGIN DESCRIPTION:
MCKIMZEY CREEK 38.0
END DESCRIPTION:
XS GIS Cut Line= 3
      2244937.69     13307596.83      2244537.72     13307196.85
      2244137.74     13306796.88
#Sta/Elev= 30
  4434.7   199.4  4448.8  198.63  4462.9  198.42  4477.1  197.44  4519.5   196.6
  4646.8  191.26  4717.5  186.82  4745.8  184.47  4774.1   183.2  4816.5  183.17
  4844.8  183.87  4876.8  185.34  4901.4  185.18  4915.5  184.45  4929.6  185.14
  4957.9  185.62  4986.2  183.95  4993.8  182.99  4996.6  182.49  4999.8  182.99
  5004.5  183.01  5155.9  186.74  5240.8  189.15    5269  190.28  5283.2  190.04
  5311.5  191.33  5353.9  191.96  5410.5   193.6  5424.6  194.55    5566  201.29
#Mann= 5 ,-1 , 0
  4434.7     .05       0  4876.8     .07       0  4993.8     .07       0
  4999.8     .07       0  5004.5      .1       0
Bank Sta=4993.8,4999.8
XS Rating Curve= 0 ,0
Exp/Cntr=0.3,0.1

Type RM Length L Ch R = 1 ,27065   ,697,697,697
BEGIN DESCRIPTION:
MCKIMZEY CREEK 37.0
END DESCRIPTION:
XS GIS Cut Line= 3
      2245041.59      13307175.6      2244954.79     13306845.75
      2244586.73     13306360.78
#Sta/Elev= 30
    4421  194.14  4502.4  191.39  4536.5  191.32  4591.9  188.99  4652.3  187.21
  4667.9  184.64  4762.1  183.58  4773.2  183.26  4780.8  182.08  4787.1  182.46
  4830.7  180.35  4930.5  179.71  4959.6  180.25    4995  178.06  4998.3  176.56
    5001  176.06  5004.3  176.56  5024.1  178.86  5087.1   180.6  5130.2  183.39
  5144.8   183.5    5151  184.56  5187.5  185.32  5209.2  186.64  5215.5  188.11
  5230.1  187.07  5237.7  188.18  5287.9  190.95  5300.8  190.75  5370.9  195.39
#Mann= 4 ,-1 , 0
    4421     .05       0  4591.9      .1       0  4998.3     .07       0
  5004.3      .1       0
Bank Sta=4998.3,5004.3
XS Rating Curve= 0 ,0
Exp/Cntr=0.3,0.1

Type RM Length L Ch R = 1 ,26368   ,194,194,194
BEGIN DESCRIPTION:
Mapping XS edc2afbe
END DESCRIPTION:
XS GIS Cut Line= 3
      2245006.86     13306941.26      2245089.34     13306724.22
      2245642.92     13306161.99
#Sta/Elev= 30
  4287.6   186.3  4313.7  186.27    4331  183.87  4336.3  184.49  4352.5  183.79
  4423.1  182.67    4538  179.43  4700.6  178.34  4764.3  176.58  4820.9  177.78
  4849.1  176.73  4877.4  177.93  4898.6  176.68  4955.5  176.38  4983.5  176.03
  4994.6  174.75  4997.3  174.25  5000.6  174.75  5011.7  175.05  5018.9  176.49
  5047.2  177.27  5124.9   177.8    5132   179.2  5146.2   179.7  5195.6  179.41
  5216.9  181.54  5223.9   180.4  5252.2  180.58  5305.3  182.21  5308.8  182.45
#Mann= 7 ,-1 , 0
  4287.6      .1       0  4352.5     .05       0  4423.1      .1       0
  4955.5     .05       0  4994.6    .035       0  5000.6     .05       0
  5305.3     .08       0
Bank Sta=4994.6,5000.6
XS Rating Curve= 0 ,0
Exp/Cntr=0.3,0.1

Type RM Length L Ch R = 1 ,26174   ,619,619,619
BEGIN DESCRIPTION:
Mapping XS 880a4db3
END DESCRIPTION:
XS GIS Cut Line= 3
      2245132.75     13306837.05      2245410.52     13306641.75
      2245857.57     13306146.95
#Sta/Elev= 30
  4360.1  184.73  4406.4  183.76    4436  184.35    4457  183.33  4471.8  184.01
  4492.7  182.87  4507.5  183.27  4543.2  182.08  4608.5  181.16  4614.7  180.55
    4680  179.58  4699.6   178.6  4750.6  177.83    4758  177.06  4842.5     175
  4906.7  174.09    4956  174.41  5030.8  173.07  5033.5  172.57  5036.8  173.07
  5041.2  173.83  5062.2  173.61  5069.6   174.6  5076.4  174.32  5090.6  175.31
  5196.7  176.42  5236.3  177.41  5335.3  176.76  5365.8  176.79  5366.5  176.79
#Mann= 6 ,-1 , 0
  4360.1     .05       0  5030.8     .04       0  5036.8     .05       0
  5236.3     .08       0  5335.3     .05       0  5365.8     .08       0
Bank Sta=5030.8,5036.8
XS Rating Curve= 0 ,0
Exp/Cntr=0.3,0.1

Type RM Length L Ch R = 1 ,25555   ,327,327,327
BEGIN DESCRIPTION:
Mapping XS 9766c913
END DESCRIPTION:
XS GIS Cut Line= 3
      2246499.96     13306702.55      2246009.48      13306107.9
      2245666.56      13305873.5
#Sta/Elev= 30
  4552.7  187.78  4793.4  179.23  4842.9  177.92  4941.9  173.44  4956.2  172.06
    4977  171.09  4984.9  169.95  4996.2   169.2    4999   168.7  5002.2   169.2
  5197.2  171.84  5318.4  172.32  5409.9  175.74  5424.8   175.9  5440.6   175.1
  5455.6  175.99  5476.5  175.14  5483.1  177.57  5497.5  177.91  5519.5  179.71
  5548.3  180.09  5569.3  181.15  5578.2  182.38  5620.1  183.12  5628.5   183.5
    5635  184.43    5656  184.69  5670.9  185.69  5706.8  185.96  5738.9  187.23
#Mann= 5 ,-1 , 0
  4552.7     .05       0  4996.2     .03       0  5002.2     .05       0
  5409.9     .08       0  5424.8     .05       0
Bank Sta=4996.2,5002.2
XS Rating Curve= 0 ,0
Exp/Cntr=0.3,0.1

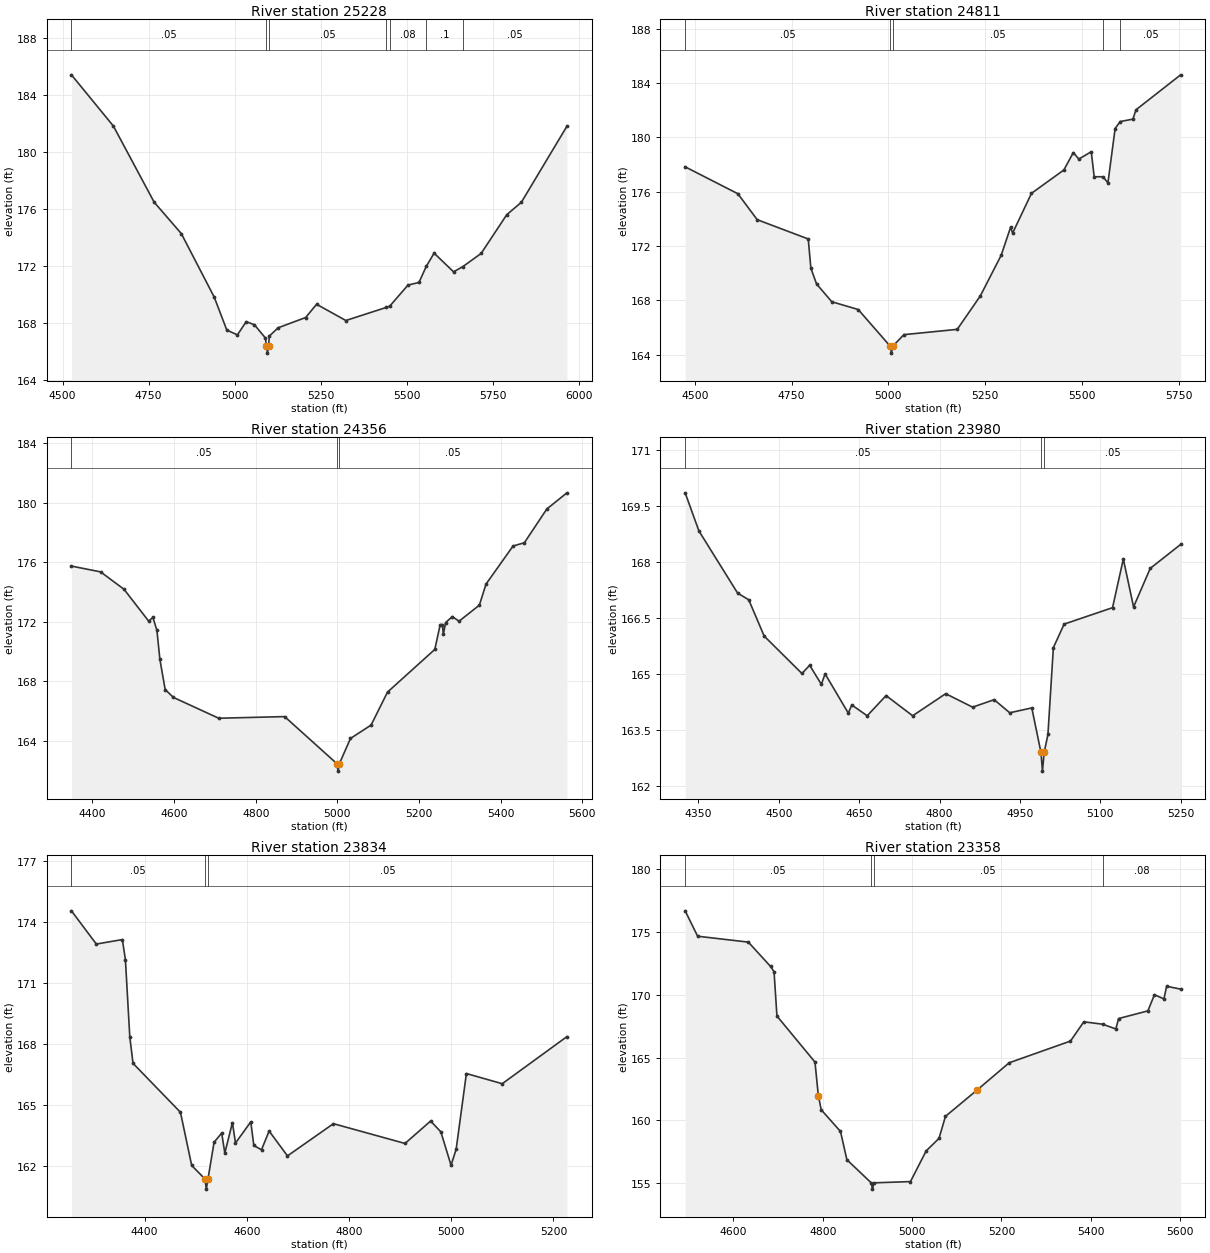
Type RM Length L Ch R = 1 ,25228   ,417,417,417
BEGIN DESCRIPTION:
MCKIMZEY CREEK 33.0
END DESCRIPTION:
XS GIS Cut Line= 2
      2246643.14     13306637.38      2246162.58     13305282.27
#Sta/Elev= 30
  4525.9  185.41  4647.7  181.81  4765.9  176.47  4844.8  174.26  4940.3   169.8
  4976.7  167.49  5007.5  167.15  5033.1  168.08    5057  167.86  5088.8  166.93
  5091.9  166.37  5094.6  165.87  5097.9  166.37  5100.2  167.07  5125.7  167.65
  5205.5  168.37  5237.3   169.3  5322.2  168.16  5439.7  169.08  5449.6  169.17
  5502.6  170.65  5534.4  170.83  5555.5  171.96  5578.3  172.89  5634.7  171.58
  5661.4  171.94  5714.8  172.87  5789.1  175.59  5831.5  176.46  5963.7   181.8
#Mann= 7 ,-1 , 0
  4525.9     .05       0  5091.9     .03       0  5097.9     .05       0
  5439.7      .1       0  5449.6     .08       0  5555.5      .1       0
  5661.4     .05       0
Bank Sta=5091.9,5097.9
XS Rating Curve= 0 ,0
Exp/Cntr=0.3,0.1

Type RM Length L Ch R = 1 ,24811   ,455,455,455
BEGIN DESCRIPTION:
MCKIMZEY CREEK 32.0
END DESCRIPTION:
XS GIS Cut Line= 3
      2246855.83     13306403.05      2246855.83     13306112.24
      2246491.26     13305192.14
#Sta/Elev= 30
  4474.7  177.83  4610.9  175.85  4660.9  173.94  4792.8  172.52  4799.6  170.37
  4814.3  169.21  4853.7   167.9  4921.9  167.33  5004.9  164.62  5007.7  164.12
  5010.9  164.62  5040.1  165.48  5177.9  165.87  5237.3  168.32  5291.4  171.32
  5315.7  173.38  5321.1  172.96  5369.7  175.88  5453.5   177.6  5477.8  178.88
    5492   178.4  5524.2  178.94  5531.8   177.1  5554.5   177.1  5567.3  176.65
  5585.9  180.65  5598.9  181.16  5631.8  181.34  5639.9  182.03  5755.2   184.6
#Mann= 5 ,-1 , 0
  4474.7     .05       0  5004.9     .03       0  5010.9     .05       0
  5554.5      .1       0  5598.9     .05       0
Bank Sta=5004.9,5010.9
XS Rating Curve= 0 ,0
Exp/Cntr=0.3,0.1

Type RM Length L Ch R = 1 ,24356   ,376,376,376
BEGIN DESCRIPTION:
MCKIMZEY CREEK 31.0
END DESCRIPTION:
XS GIS Cut Line= 3
       2247003.4     13306294.51      2247124.93     13305396.09
       2246982.2     13305123.61
#Sta/Elev= 30
  4348.4  175.75  4419.8  175.36  4477.2  174.19  4537.8  172.04  4547.9   172.3
  4557.9  171.42  4565.1  169.48  4578.1  167.44  4598.3  166.91  4709.3  165.51
  4870.8  165.62    4999  162.45  5001.7  161.95    5005  162.45  5032.2  164.15
  5082.7  165.05    5123  167.27  5238.8  170.14  5252.1  171.81  5257.4  171.81
  5259.8  171.16  5265.4  171.95  5281.8  172.35  5298.3  172.04    5348  173.12
  5364.4  174.54  5430.6   177.1  5458.3  177.32  5513.3  179.59  5562.6  180.68
#Mann= 3 ,-1 , 0
  4348.4     .05       0    4999     .03       0    5005     .05       0
Bank Sta=4999,5005
XS Rating Curve= 0 ,0
Exp/Cntr=0.3,0.1

Type RM Length L Ch R = 1 ,23980   ,146,146,146
BEGIN DESCRIPTION:
MCKIMZEY CREEK 30.0
END DESCRIPTION:
XS GIS Cut Line= 3
      2247189.24      13306215.2        2247467.       13305868.
      2247425.47     13305390.33
#Sta/Elev= 30
  4325.5  169.85  4351.2  168.83  4423.3  167.17  4444.1  166.99  4472.9  166.02
  4543.3  165.02  4557.7  165.24  4579.5  164.73  4586.5  165.01  4629.8  163.96
  4636.2  164.18    4665  163.89  4700.2  164.43  4749.8  163.89  4811.4  164.48
  4861.6  164.12  4901.8  164.32  4930.9  163.97    4972   164.1  4989.1  162.91
  4991.9  162.41  4995.1  162.91  5002.1  163.39  5012.2  165.71  5032.3  166.34
  5122.6  166.78  5142.7  168.08  5161.8   166.8  5192.9  167.83  5249.6  168.47
#Mann= 3 ,-1 , 0
  4325.5     .05       0  4989.1     .03       0  4995.1     .05       0
Bank Sta=4989.1,4995.1
XS Rating Curve= 0 ,0
Exp/Cntr=0.3,0.1

Type RM Length L Ch R = 1 ,23834   ,476,476,476
BEGIN DESCRIPTION:
Mapping XS 2978682a
END DESCRIPTION:
XS GIS Cut Line= 3
      2247324.63     13306281.21      2247578.11     13305909.66
      2247598.89     13305390.36
#Sta/Elev= 30
  4256.9  174.54  4305.6  172.91  4356.5  173.13  4362.5  172.15  4371.1  168.35
  4377.4  167.06  4470.2  164.66  4492.2  162.05  4518.1  161.39  4520.8  160.89
  4524.1  161.39    4536  163.19  4550.9  163.64    4557  162.66  4571.9  164.15
  4577.9  163.15  4607.8  164.19  4613.8  163.03  4628.8  162.82  4643.7  163.74
  4679.6  162.52  4769.5   164.1  4909.6  163.13  4959.7  164.23  4979.7   163.7
  4999.7  162.06  5009.7  162.85  5029.7  166.56  5099.8  166.06  5226.4  168.37
#Mann= 3 ,-1 , 0
  4256.9     .05       0  4518.1     .03       0  4524.1     .05       0
Bank Sta=4518.1,4524.1
XS Rating Curve= 0 ,0
Exp/Cntr=0.3,0.1

Type RM Length L Ch R = 1 ,23358   ,116,116,116
BEGIN DESCRIPTION:
Mapping XS 10f7b0dd
END DESCRIPTION:
XS GIS Cut Line= 3
      2247394.08      13306392.3      2247786.45     13305909.66
      2248062.23     13305508.53
#Sta/Elev= 30
  4492.1  176.67    4520  174.65  4633.5  174.18  4683.1  172.25    4691  171.83
  4697.5   168.3  4782.6  164.64  4790.1  161.97  4796.6  160.84  4839.7  159.12
    4854  156.87  4908.5  155.03  4911.3  154.53  4914.5  155.03  4996.3  155.13
  5031.4  157.57  5060.2  158.57  5074.6  160.32  5145.3  162.41  5217.1  164.58
  5354.4  166.31  5384.2  167.84  5426.5  167.65  5455.9  167.27    5462   168.1
  5527.6  168.71  5542.3     170  5563.5  169.66  5569.5  170.67  5600.9  170.44
#Mann= 4 ,-1 , 0
  4492.1     .05       0  4908.5     .03       0  4914.5     .05       0
  5426.5     .08       0
Bank Sta=4790.1,5145.3
XS Rating Curve= 0 ,0
Exp/Cntr=0.3,0.1

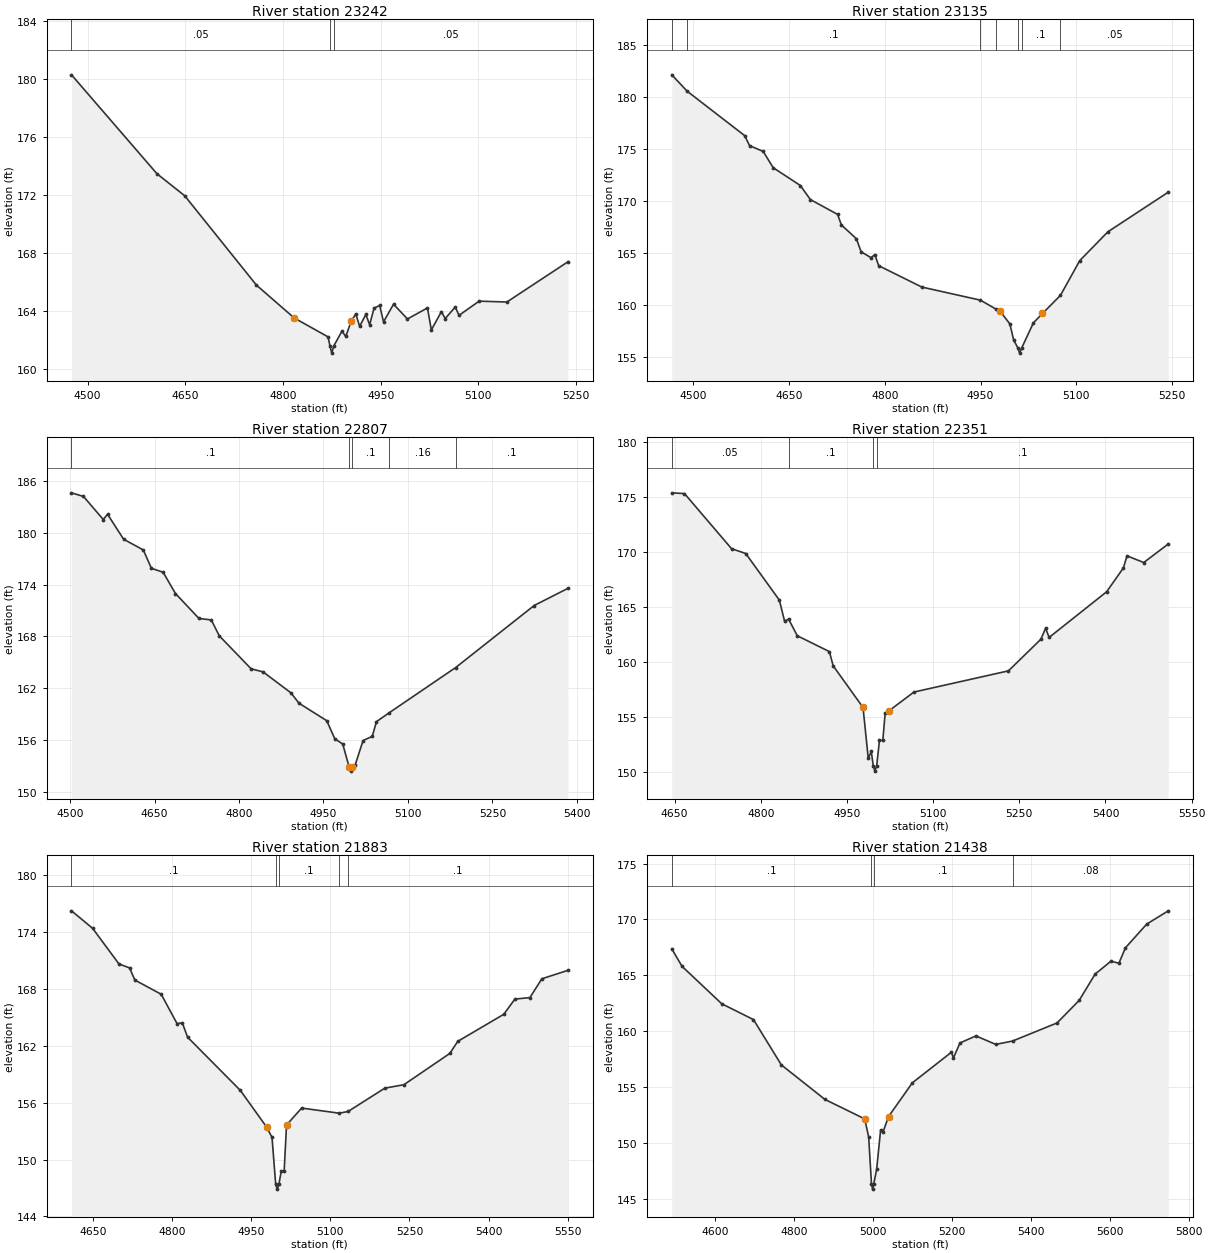
Type RM Length L Ch R = 1 ,23242   ,107,107,107
BEGIN DESCRIPTION:
Mapping XS c2250407
END DESCRIPTION:
XS GIS Cut Line= 2
      2247543.37     13306482.61       2247942.7     13305833.27
#Sta/Elev= 30
  4475.3  180.29  4606.5  173.46  4649.1  171.94  4759.2  165.77  4817.2   163.5
  4869.3  162.19  4872.1  161.57  4874.9  161.07  4878.1  161.57  4890.6  162.59
  4896.4  162.22  4904.7  163.26  4911.8  163.78  4917.7  162.92  4927.3  163.74
  4933.1  163.03  4939.9  164.18  4948.5  164.36  4954.4  163.23  4969.8  164.45
  4991.1  163.43  5021.9  164.19  5027.8  162.67  5043.2  163.93  5049.1  163.46
  5064.5  164.25  5070.4  163.68  5101.2  164.66  5143.8   164.6  5237.6  167.38
#Mann= 3 ,-1 , 0
  4475.3     .05       0  4872.1     .03       0  4878.1     .05       0
Bank Sta=4817.2,4904.7
XS Rating Curve= 0 ,0
Exp/Cntr=0.3,0.1

Type RM Length L Ch R = 1 ,23135   ,328,328,328
BEGIN DESCRIPTION:
Mapping XS f16ea3a4
END DESCRIPTION:
XS GIS Cut Line= 2
      2247638.89     13306534.64      2248039.94     13305867.97
#Sta/Elev= 30
  4466.2  182.15  4490.3  180.57  4580.3   176.3  4588.1  175.33  4609.5  174.77
    4625  173.21  4667.7  171.49  4683.3  170.14    4726  168.71    4732  167.69
  4755.4  166.37  4762.9  165.11  4778.4  164.54  4784.3  164.84  4790.4  163.77
  4858.1  161.71  4949.9  160.45  4974.7  159.57  4980.5   159.4    4996  158.16
  5001.8  156.64  5008.5  155.85  5011.3  155.35  5014.5  155.85  5032.9  158.27
  5047.1  159.17  5075.2  160.91  5105.5  164.26  5149.5  167.03  5244.2  170.85
#Mann= 7 ,-1 , 0
  4466.2     .05       0  4490.3      .1       0  4949.9     .05       0
  4974.7      .1       0  5008.5     .07       0  5014.5      .1       0
  5075.2     .05       0
Bank Sta=4980.5,5047.1
XS Rating Curve= 0 ,0
Exp/Cntr=0.3,0.1

Type RM Length L Ch R = 1 ,22807   ,456,456,456
BEGIN DESCRIPTION:
MCKIMZEY CREEK 27.0
END DESCRIPTION:
XS GIS Cut Line= 3
      2247837.75     13306646.83      2248187.72     13306246.85
      2248187.72     13305896.82
#Sta/Elev= 30
  4502.6  184.63  4523.9  184.21    4559  181.54  4566.6  182.15  4595.1  179.26
  4630.2  178.01  4644.5  175.89  4665.3  175.43  4687.2  172.97  4728.9  170.08
  4750.8  169.91    4765  168.07  4821.5  164.25  4842.8  163.89  4892.2  161.47
  4906.4  160.27  4955.8  158.24    4970  156.16  4984.2  155.53  4995.5   152.9
  4998.2   152.4  5001.5   152.9  5006.1  153.08  5020.3  155.94  5036.6  156.43
  5044.1  158.13  5066.5  159.15  5184.8   164.4  5324.1  171.58  5384.1  173.57
#Mann= 5 ,-1 , 0
  4502.6      .1       0  4995.5     .07       0  5001.5      .1       0
  5066.5     .16       0  5184.8      .1       0
Bank Sta=4995.5,5001.5
XS Rating Curve= 0 ,0
Exp/Cntr=0.3,0.1

Type RM Length L Ch R = 1 ,22351   ,468,468,468
BEGIN DESCRIPTION:
MCKIMZEY CREEK 26.0
END DESCRIPTION:
XS GIS Cut Line= 3
      2248487.71     13306696.88      2248587.72     13306346.85
      2248287.74     13305946.88
#Sta/Elev= 30
  4645.3  175.37  4667.4   175.3  4749.3  170.29    4774  169.85  4832.5  165.61
  4841.6  163.69  4848.5  163.89  4863.7  162.37  4919.6  160.93  4926.1  159.64
  4978.1  155.85  4987.2  151.21  4992.4  151.85  4995.9  150.56  4998.7  150.06
  5001.9  150.56  5006.7  152.86  5012.5  152.86  5016.6  155.31  5022.9  155.53
  5066.6  157.25  5231.2  159.18  5287.5  162.05  5295.8  163.05    5302  162.22
    5402  166.37  5431.2  168.54  5437.5  169.64  5466.6  169.03  5509.3  170.72
#Mann= 4 ,-1 , 0
  4645.3     .05       0  4848.5      .1       0  4995.9     .07       0
  5001.9      .1       0
Bank Sta=4978.1,5022.9
XS Rating Curve= 0 ,0
Exp/Cntr=0.3,0.1

Type RM Length L Ch R = 1 ,21883   ,445,445,445
BEGIN DESCRIPTION:
MCKIMZEY CREEK 25.0
END DESCRIPTION:
XS GIS Cut Line= 3
      2249037.72     13306646.87      2249037.72     13306246.85
      2248737.74     13305796.89
#Sta/Elev= 30
  4609.5   176.2  4649.5  174.36  4699.5   170.6  4719.5  170.19  4729.5  168.91
  4779.5  167.41  4809.5  164.32  4819.5   164.4  4829.5  162.89  4929.5  157.28
  4979.5   153.4  4989.5  152.32  4996.5  147.38  4999.3  146.88  5002.5  147.38
    5007  148.78  5012.5  148.78    5017  153.63  5045.6  155.42  5116.9  154.88
  5133.6  155.06  5203.3  157.52  5239.4  157.88  5326.5  161.18  5341.5  162.45
  5428.7   165.3  5449.7   166.9  5478.2  167.06  5500.8  169.04  5550.3  169.93
#Mann= 5 ,-1 , 0
  4609.5      .1       0  4996.5     .07       0  5002.5      .1       0
  5116.9     .16       0  5133.6      .1       0
Bank Sta=4979.5,5017
XS Rating Curve= 0 ,0
Exp/Cntr=0.3,0.1

Type RM Length L Ch R = 1 ,21438   ,478,478,478
BEGIN DESCRIPTION:
MCKIMZEY CREEK 24.0
END DESCRIPTION:
XS GIS Cut Line= 2
      2249533.78     13306702.55      2249390.55     13305452.53
#Sta/Elev= 30
  4490.5  167.36  4516.4   165.8    4617  162.45  4697.5  161.03  4768.2  156.97
  4878.7  153.88  4979.4  152.14  4989.4  150.52  4996.5  146.35  4999.3  145.85
  5002.5  146.35  5009.6  147.62  5019.6  151.11  5025.8  150.96  5039.8  152.35
  5100.2  155.37  5199.2  158.11  5204.2   157.6  5220.9  158.94  5261.2  159.57
  5311.5  158.81  5354.1  159.11  5466.8  160.73  5522.9  162.75  5563.2   165.1
  5603.4  166.26  5623.6  166.08  5640.2  167.46    5694  169.58  5748.7  170.77
#Mann= 4 ,-1 , 0
  4490.5      .1       0  4996.5     .07       0  5002.5      .1       0
  5354.1     .08       0
Bank Sta=4979.4,5039.8
XS Rating Curve= 0 ,0
Exp/Cntr=0.3,0.1

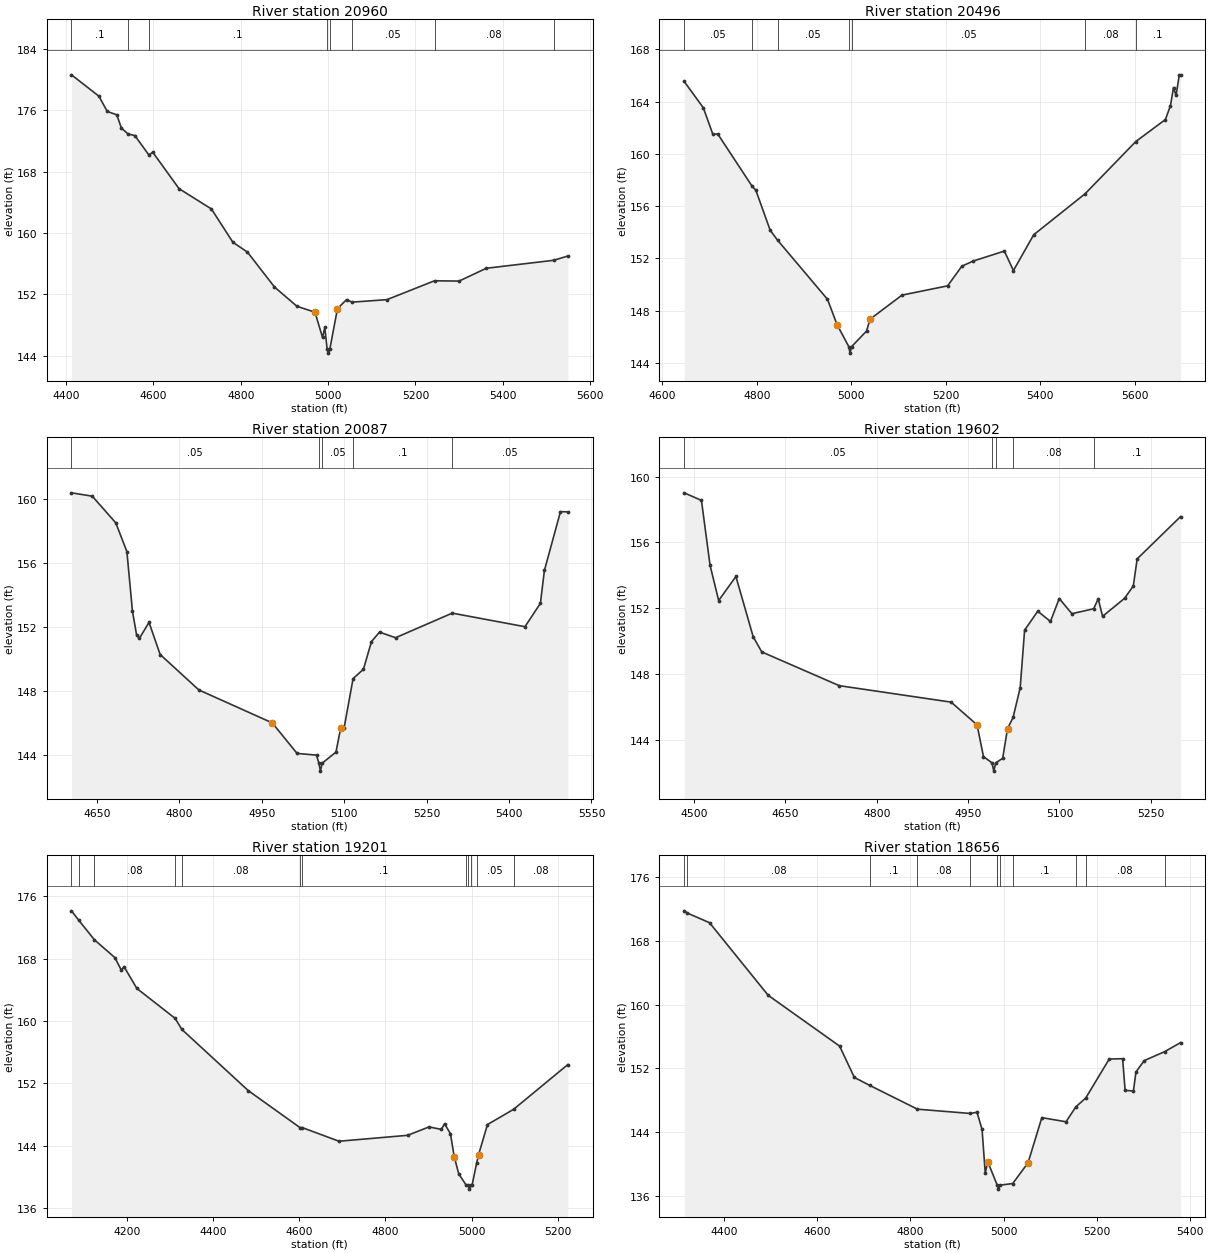
Type RM Length L Ch R = 1 ,20960   ,464,464,464
BEGIN DESCRIPTION:
MCKIMZEY CREEK 23.0
END DESCRIPTION:
XS GIS Cut Line= 2
      2250093.68     13306767.63       2249815.9     13305665.19
#Sta/Elev= 30
  4412.3  180.65    4475  177.87  4494.3  175.87  4516.2  175.43  4526.5  173.71
  4541.9  172.94  4557.5  172.72  4589.2  170.22  4598.7  170.53  4658.6   165.8
  4732.8  163.15  4781.9  158.81  4815.3  157.52  4877.2  152.97  4928.7  150.45
    4970  149.68  4987.3  146.38  4992.5  147.69  4997.9  144.84  5000.7  144.34
  5003.9  144.84  5021.5  150.14  5042.2  151.32  5054.8  150.99    5135  151.32
  5243.8  153.78    5300  153.74  5362.3  155.41  5516.5  156.45  5549.2  157.01
#Mann= 8 ,-1 , 0
  4412.3      .1       0  4541.9     .05       0  4589.2      .1       0
  4997.9     .07       0  5003.9      .1       0  5054.8     .05       0
  5243.8     .08       0  5516.5     .05       0
Bank Sta=4970,5021.5
XS Rating Curve= 0 ,0
Exp/Cntr=0.3,0.1

Type RM Length L Ch R = 1 ,20496   ,409,409,409
BEGIN DESCRIPTION:
MCKIMZEY CREEK 22.0
END DESCRIPTION:
XS GIS Cut Line= 3
      2250387.73      13306396.9      2250337.72     13306046.85
      2250087.73     13305396.87
#Sta/Elev= 30
  4646.6  165.54    4687  163.53  4707.3  161.49  4717.4  161.53  4789.4  157.57
  4798.2  157.21  4828.5  154.15  4844.2  153.39  4949.7  148.87  4969.9  146.93
  4994.7  145.25  4997.4  144.75  5000.7  145.25  5032.3  146.44  5039.8  147.35
  5107.3  149.19  5203.8   149.9  5233.8   151.4  5257.3  151.79  5323.8  152.56
    5343  151.07  5385.9  153.81  5494.7  156.95  5601.7  160.94  5664.5  162.63
  5675.2   163.7  5681.6  165.08    5687  164.47  5693.9  166.05  5696.6  166.05
#Mann= 7 ,-1 , 0
  4646.6     .05       0  4789.4      .1       0  4844.2     .05       0
  4994.7     .04       0  5000.7     .05       0  5494.7     .08       0
  5601.7      .1       0
Bank Sta=4969.9,5039.8
XS Rating Curve= 0 ,0
Exp/Cntr=0.3,0.1

Type RM Length L Ch R = 1 ,20087   ,485,485,485
BEGIN DESCRIPTION:
MCKIMZEY CREEK 21.0
END DESCRIPTION:
XS GIS Cut Line= 3
      2250637.72     13306246.86      2250687.72     13305846.85
      2250987.71     13305446.87
#Sta/Elev= 30
    4604  160.41  4641.8   160.2  4684.6  158.53  4704.8  156.73  4714.9  153.01
  4722.4  151.52  4727.5   151.3  4745.1   152.3  4765.3  150.29  4835.8  148.07
  4969.3  146.01  5014.4   144.1  5049.8  143.99  5054.1  143.49  5056.9  142.99
  5060.1  143.49  5085.2  144.18  5093.6  145.66  5099.8  145.66  5116.3  148.78
  5135.2  149.37  5149.8   151.1  5164.4  151.69  5193.6  151.34  5296.7  152.88
    5429  152.03  5457.1  153.49  5464.4  155.55  5493.6  159.23  5507.1  159.22
#Mann= 5 ,-1 , 0
    4604     .05       0  5054.1     .04       0  5060.1     .05       0
  5116.3      .1       0  5296.7     .05       0
Bank Sta=4969.3,5093.6
XS Rating Curve= 0 ,0
Exp/Cntr=0.3,0.1

Type RM Length L Ch R = 1 ,19602   ,401,401,401
BEGIN DESCRIPTION:
MCKIMZEY CREEK 20.0
END DESCRIPTION:
XS GIS Cut Line= 3
       2250787.7     13306296.87      2251137.72     13305946.85
      2251337.75     13305696.82
#Sta/Elev= 30
  4483.7  159.01    4512  158.55  4526.2   154.6  4540.3  152.47  4568.6  153.93
  4596.9  150.28    4611  149.35  4738.3   147.3  4922.1   146.3  4964.6  144.92
  4975.2  142.99  4989.3  142.61  4992.1  142.11  4995.3  142.61  5006.7  142.89
  5014.7  144.69  5023.8  145.37  5035.5  147.18  5042.7  150.67  5064.3  151.82
  5085.2   151.2  5099.6  152.59  5120.4  151.67  5156.1  151.97  5163.6  152.57
  5170.8  151.51  5206.8   152.6  5221.2  153.35  5227.6     155  5298.9  157.57
#Mann= 5 ,-1 , 0
  4483.7     .05       0  4989.3     .04       0  4995.3     .05       0
  5023.8     .08       0  5156.1      .1       0
Bank Sta=4964.6,5014.7
XS Rating Curve= 0 ,0
Exp/Cntr=0.3,0.1

Type RM Length L Ch R = 1 ,19201   ,545,545,545
BEGIN DESCRIPTION:
MCKIMZEY CREEK 19.0
END DESCRIPTION:
XS GIS Cut Line= 3
      2250687.72     13306696.85      2251437.72     13306196.85
      2251637.73     13306046.85
#Sta/Elev= 30
  4071.7  174.14  4088.3  172.95  4124.9  170.42  4172.4  168.13  4187.4  166.51
  4193.4  166.98  4223.4  164.17  4312.1  160.33  4327.7  158.91  4481.8  151.05
  4602.3  146.28  4606.6  146.31  4692.2  144.55  4851.4  145.31    4901  146.39
  4929.5  146.07    4937  146.79  4950.6  145.54  4959.6  142.54  4970.1  140.34
  4986.6  138.97    4992   138.9  4994.7   138.4    4998   138.9  5001.2  138.99
  5011.5  141.75  5015.8  142.79  5036.6  146.69  5097.2  148.65  5223.1   154.4
#Mann= 12 ,-1 , 0
  4071.7     .08       0  4088.3     .05       0  4124.9     .08       0
  4312.1     .05       0  4327.7     .08       0  4602.3     .05       0
  4606.6      .1       0  4986.6     .08       0    4992     .07       0
    4998     .08       0  5011.5     .05       0  5097.2     .08       0
#XS Ineff= 2 , 0
         4936.25  146.59
Permanent Ineff=
       F       F
Bank Sta=4959.6,5015.8
XS Rating Curve= 0 ,0
Exp/Cntr=0.3,0.1

Type RM Length L Ch R = 1 ,18656   ,496,496,496
BEGIN DESCRIPTION:
Mapping XS 20a1b81c
END DESCRIPTION:
XS GIS Cut Line= 3
      2250718.65     13306897.83      2250913.99     13306876.13
      2251706.43     13306521.04
#Sta/Elev= 30
  4314.6  171.77  4321.2  171.49  4368.9  170.28  4494.8  161.17    4648   154.8
  4679.6  150.87  4712.3  149.88    4815  146.89  4928.6  146.35  4942.7  146.51
  4953.6  144.34  4960.4  138.89  4965.9  140.29  4986.1  137.36  4988.8  136.86
  4992.1  137.36  5019.3  137.56  5052.2  140.16  5081.8  145.83  5133.7  145.31
  5154.9  147.19  5175.9  148.28  5226.4  153.18  5255.1  153.22  5260.5  149.25
  5278.3  149.17  5283.7  151.55  5301.4  152.98  5345.4  154.11  5379.5  155.24
#Mann= 12 ,-1 , 0
  4314.6      .1       0  4321.2     .08       0  4712.3      .1       0
    4815     .08       0  4928.6      .1       0  4986.1     .08       0
  4986.1     .07       0  4992.1     .08       0  5019.3      .1       0
  5154.9     .05       0  5175.9     .08       0  5345.4      .1       0
Bank Sta=4965.9,5052.2
XS Rating Curve= 0 ,0
Exp/Cntr=0.3,0.1