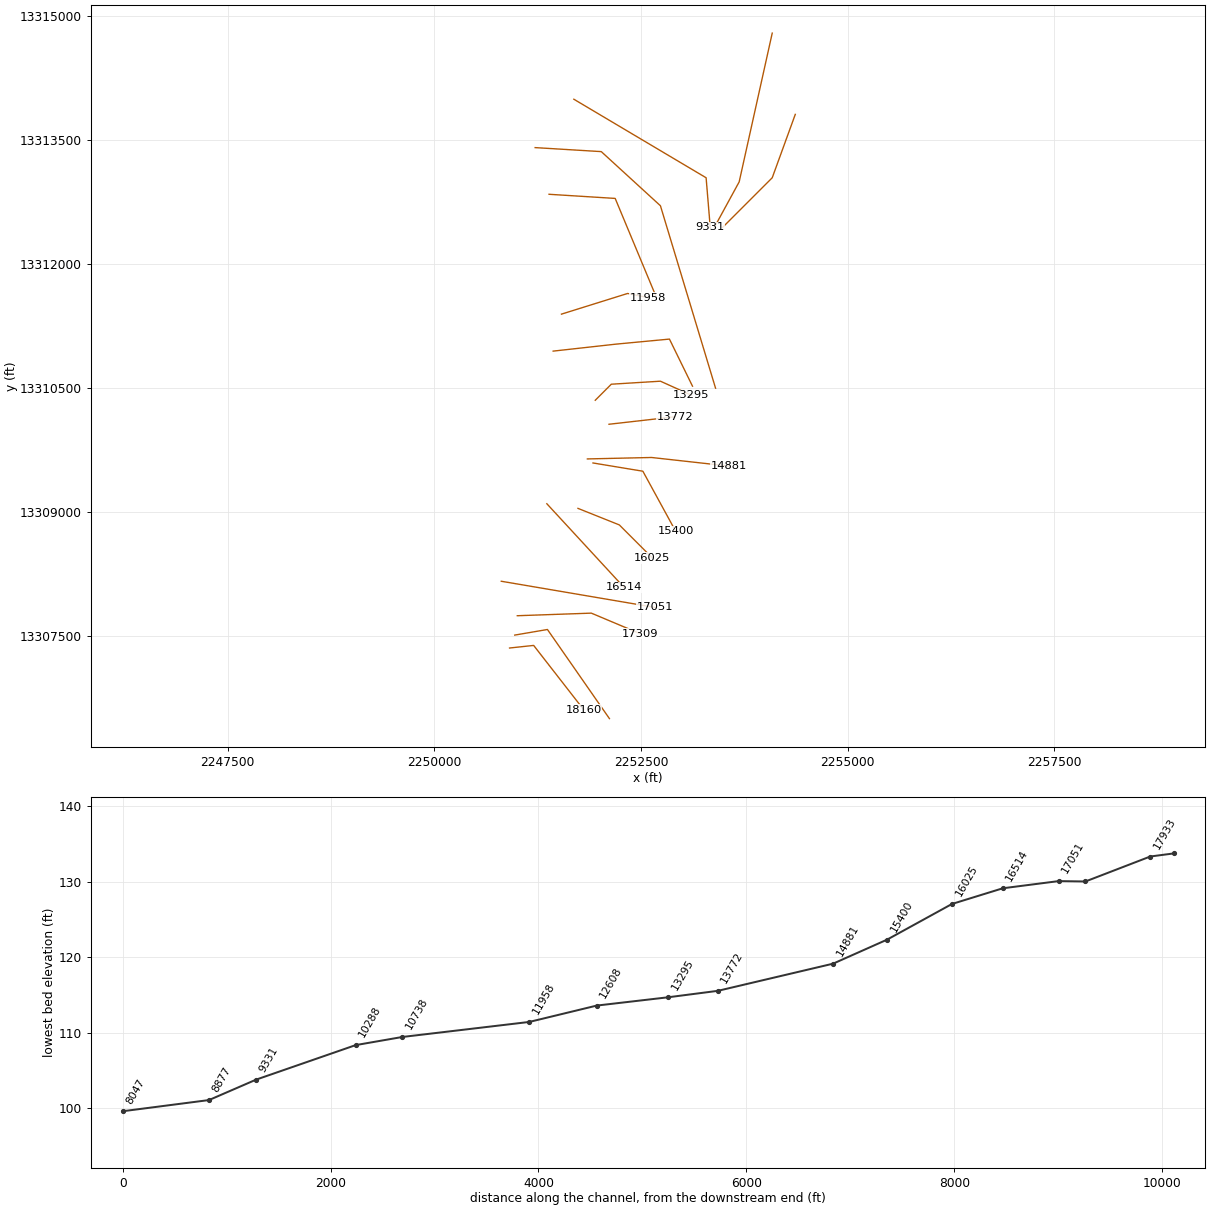
HEC-RAS study MCKIMZEY CREEK.prj: MCKIMZEY CREEK Base Level Engineering

--- MCKIMZEY CREEK.g01 (geometry) --- (continued)

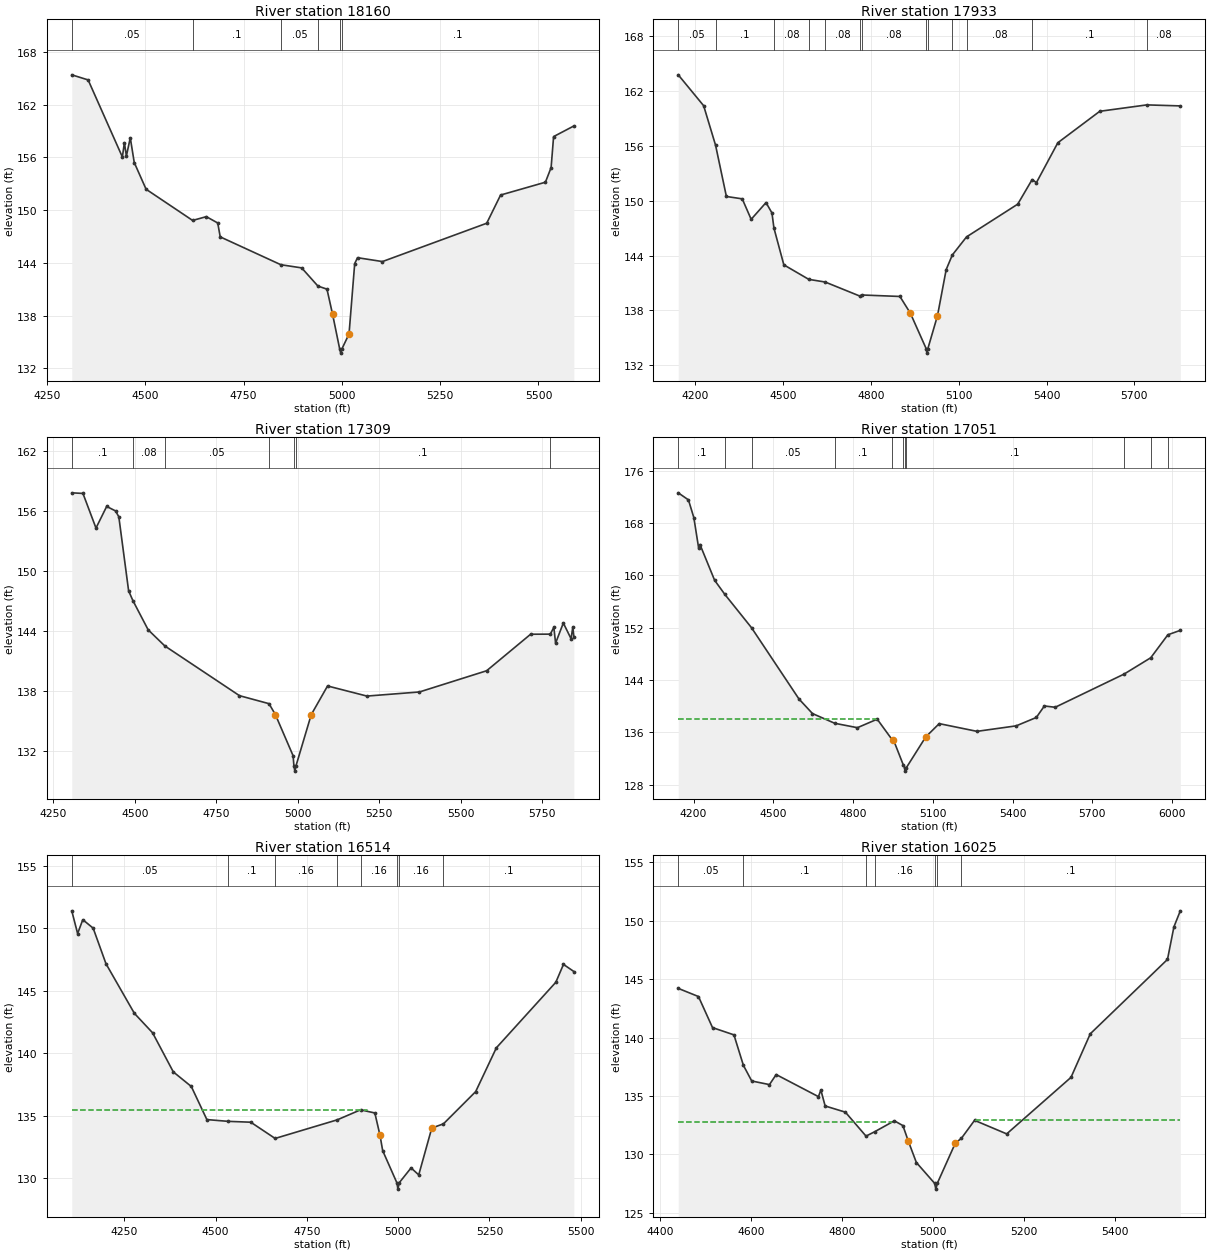
Type RM Length L Ch R = 1 ,18160   ,227,227,227
BEGIN DESCRIPTION:
MCKIMZEY CREEK 17.0
END DESCRIPTION:
XS GIS Cut Line= 3
      2250909.76     13307357.58      2251201.38     13307388.83
      2251805.56     13306612.77
#Sta/Elev= 30
  4313.1   165.4  4354.7  164.82  4441.8  156.05  4446.9  157.68    4452  156.16
  4461.9  158.24    4472  155.42  4502.1  152.38  4620.4  148.83  4655.3  149.26
  4684.3  148.54  4690.6  146.96  4844.8  143.79  4897.8  143.43  4939.1  141.36
  4962.1  141.01  4976.4  138.14  4994.3  134.23  4997.1  133.73  5000.3  134.23
  5018.2  135.91  5032.6  143.92  5039.8  144.59  5103.2  144.15  5368.3  148.51
  5403.6  151.72  5517.6  153.18  5532.1  154.85  5538.4  158.37  5589.9  159.58
#Mann= 6 ,-1 , 0
  4313.1     .05       0  4620.4      .1       0  4844.8     .05       0
  4939.1      .1       0  4994.3     .07       0  5000.3      .1       0
Bank Sta=4976.4,5018.2
XS Rating Curve= 0 ,0
Exp/Cntr=0.3,0.1

Type RM Length L Ch R = 1 ,17933   ,624,624,624
BEGIN DESCRIPTION:
Mapping XS 19a05e5b
END DESCRIPTION:
XS GIS Cut Line= 3
       2250972.2     13307513.83      2251368.05     13307581.54
      2252118.03     13306503.44
#Sta/Elev= 30
  4141.8  163.77  4228.6  160.39  4269.3  156.07  4306.3  150.46  4360.4   150.2
  4390.9  147.96  4441.6  149.79  4461.9  148.66  4468.7     147  4502.5  142.98
  4587.7  141.39  4643.6   141.1  4761.5  139.57  4769.9  139.68    4899  139.52
  4934.8  137.68  4988.5  133.82  4991.3  133.32  4994.5  133.82  5027.3  137.41
    5057  142.46    5078  144.06  5126.6  146.04  5301.4  149.62  5350.6  152.31
  5365.3  151.98  5438.4  156.34  5581.6  159.78  5742.3  160.48  5856.7  160.37
#Mann= 13 ,-1 , 0
  4141.8     .05       0  4269.3      .1       0  4468.7     .08       0
  4587.7      .1       0  4643.6     .08       0  4761.5      .1       0
  4769.9     .08       0  4988.5     .07       0  4994.5     .08       0
    5078      .1       0  5126.6     .08       0  5350.6      .1       0
  5742.3     .08       0
Bank Sta=4934.8,5027.3
XS Rating Curve= 0 ,0
Exp/Cntr=0.3,0.1

Type RM Length L Ch R = 1 ,17309   ,258,258,258
BEGIN DESCRIPTION:
MCKIMZEY CREEK 15.0
END DESCRIPTION:
XS GIS Cut Line= 3
      2251003.43      13307748.2       2251899.3     13307779.45
      2252492.91     13307529.51
#Sta/Elev= 30
  4306.5  157.82  4340.8  157.76  4380.8   154.3  4413.6  156.46  4440.9  156.01
  4450.9  155.42  4480.9  148.03  4493.9  147.06  4540.9  144.13    4592  142.52
  4821.1  137.55  4911.7  136.75  4931.2  135.66  4985.6  131.55  4988.2  130.51
    4991  130.01  4994.2  130.51  5041.2  135.65  5091.3  138.52  5212.1  137.51
  5373.2  137.92  5579.4  140.04  5714.4  143.69  5774.9   143.7  5785.6  144.38
    5791   142.8  5814.7  144.81  5838.5  143.24  5843.9  144.43    5847  143.45
#Mann= 7 ,-1 , 0
  4306.5      .1       0  4493.9     .08       0    4592     .05       0
  4911.7      .1       0  4988.2     .07       0  4994.2      .1       0
  5774.9     .08       0
Bank Sta=4931.2,5041.2
XS Rating Curve= 0 ,0
Exp/Cntr=0.3,0.1

Type RM Length L Ch R = 1 ,17051   ,537,537,537
BEGIN DESCRIPTION:
MCKIMZEY CREEK 14.0
END DESCRIPTION:
XS GIS Cut Line= 2
      2250809.86     13308165.18      2252671.79     13307848.35
#Sta/Elev= 30
  4142.2   172.6  4180.6  171.52  4200.9  168.81  4218.9  164.18    4224   164.7
  4279.1  159.23  4317.8  157.06  4417.9  151.98  4596.5  141.08  4647.2  138.86
  4731.1  137.37  4816.2   136.7  4890.7     138  4944.8  134.98  4951.5  134.87
  4988.9     131  4993.9  130.56  4996.6  130.06  4999.9  130.56  5073.3  135.29
    5124  137.32    5266  136.14  5413.5  136.98  5489.2  138.26  5519.6  140.02
  5560.2  139.82  5819.6   144.9  5919.7  147.39  5984.1   150.9  6030.9  151.58
#Mann= 11 ,-1 , 0
  4142.2      .1       0  4317.8     .08       0  4417.9     .05       0
  4731.1      .1       0  4944.8     .05       0  4988.9      .1       0
  4993.9     .07       0  4999.9      .1       0  5819.6     .05       0
  5919.7      .1       0  5984.1     .05       0
#XS Ineff= 2 , 0
         4887.78  138.01
Permanent Ineff=
       F       F
Bank Sta=4951.5,5073.3
XS Rating Curve= 0 ,0
Exp/Cntr=0.3,0.1

Type RM Length L Ch R = 1 ,16514   ,489,489,489
BEGIN DESCRIPTION:
MCKIMZEY CREEK 13.0
END DESCRIPTION:
XS GIS Cut Line= 2
      2251361.01     13309102.72      2252293.26     13308092.42
#Sta/Elev= 30
  4106.4   151.4  4122.4  149.58  4136.6  150.69    4165  150.01  4200.1  147.16
  4277.8  143.19  4327.7  141.63  4384.4   138.5  4433.7  137.33  4476.3  134.68
    4534  134.54  4596.5  134.47  4663.2  133.17  4833.3  134.66    4897  135.46
  4936.2  135.21  4950.3  133.43  4957.7  132.19  4996.7  129.61  4999.4  129.11
  5002.7  129.61  5035.4  130.81  5056.4  130.25  5092.1     134  5124.1  134.34
  5212.3  136.92    5269  140.43  5431.8  145.68  5452.7  147.11  5481.1  146.54
#Mann= 8 ,-1 , 0
  4106.4     .05       0    4534      .1       0  4663.2     .16       0
  4833.3     .12       0    4897     .16       0  4996.7     .07       0
  5002.7     .16       0  5124.1      .1       0
#XS Ineff= 2 , 0
         4914.55  135.44
Permanent Ineff=
       F       F
Bank Sta=4950.3,5092.1
XS Rating Curve= 0 ,0
Exp/Cntr=0.3,0.1

Type RM Length L Ch R = 1 ,16025   ,625,625,625
BEGIN DESCRIPTION:
MCKIMZEY CREEK 12.0
END DESCRIPTION:
XS GIS Cut Line= 3
      2251737.69     13309046.87      2252237.72     13308846.85
      2252637.69     13308446.88
#Sta/Elev= 30
  4439.6  144.22  4484.1  143.52    4515  140.86  4562.1  140.24  4582.9  137.63
  4601.2  136.29  4640.2  135.98    4655  136.84  4747.9  134.95  4753.3  135.51
  4762.7  134.15  4807.2  133.62  4852.6  131.57  4871.9  131.95  4914.9  132.88
  4933.7  132.47  4945.8  131.12  4963.3  129.31  5003.4  127.53  5006.2  127.03
  5009.4  127.53  5048.9  130.96  5062.5  131.39  5091.3  132.92    5162  131.76
  5303.4   136.6  5345.8  140.33  5515.6   146.7  5529.7  149.48  5543.8  150.86
#Mann= 7 ,-1 , 0
  4439.6     .05       0  4582.9      .1       0  4852.6     .12       0
  4871.9     .16       0  5003.4     .07       0  5009.4     .16       0
  5062.5      .1       0
#XS Ineff= 2 , 0
         4909.32  132.77 5093.41          132.92
Permanent Ineff=
       F       F
Bank Sta=4945.8,5048.9
XS Rating Curve= 0 ,0
Exp/Cntr=0.3,0.1

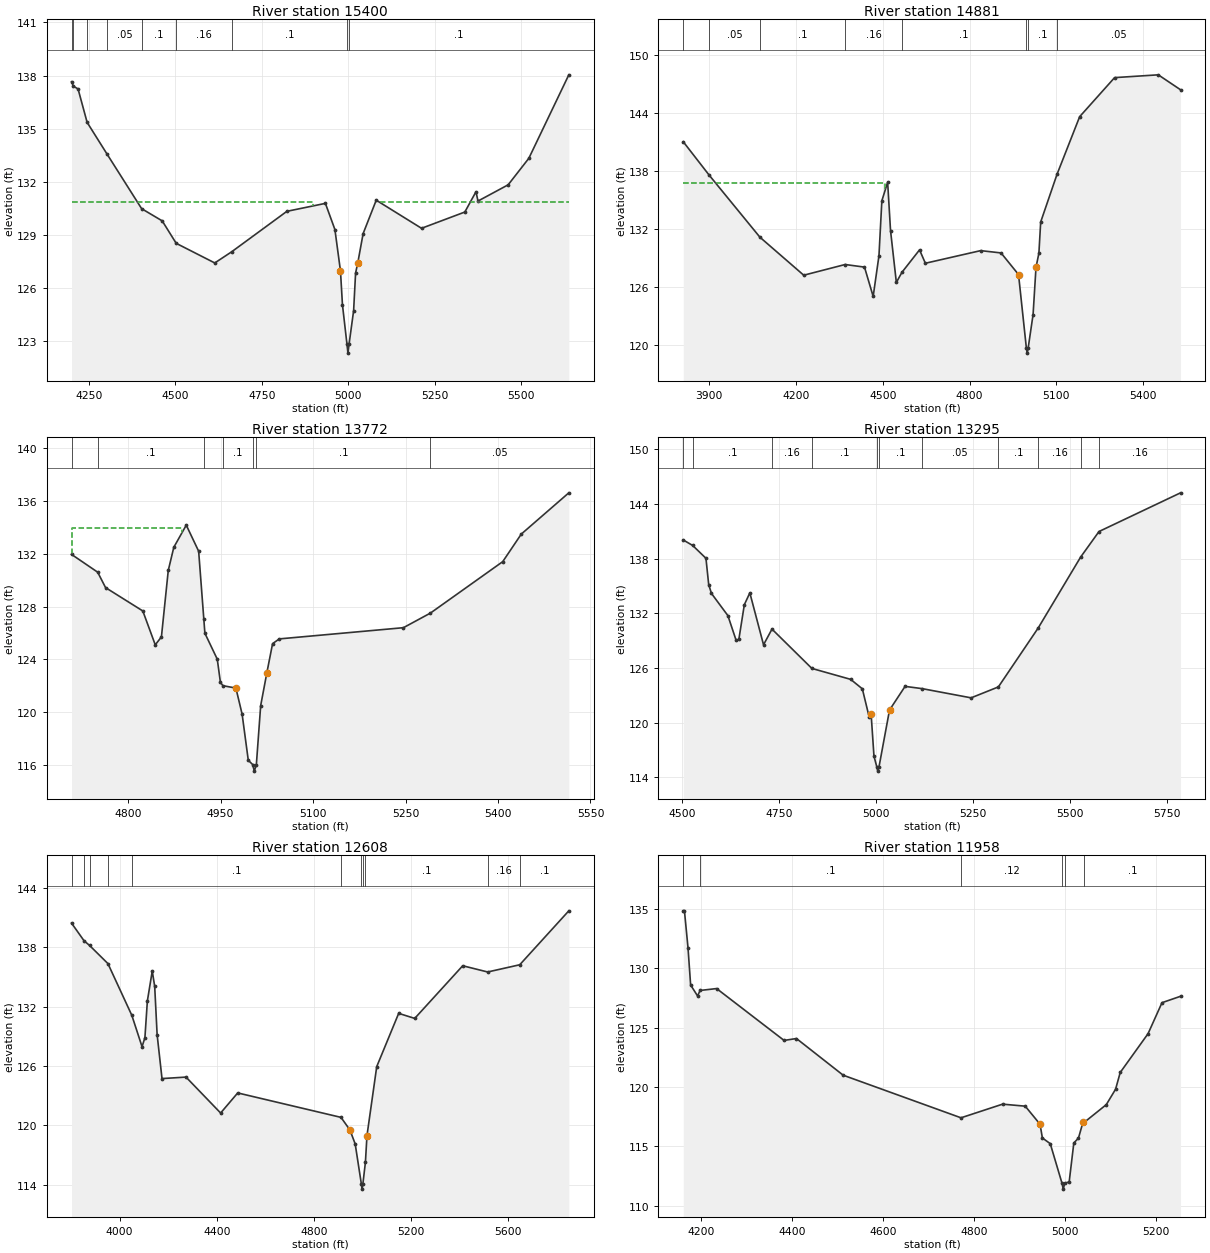
Type RM Length L Ch R = 1 ,15400   ,519,519,519
BEGIN DESCRIPTION:
Mapping XS 709ae712
END DESCRIPTION:
XS GIS Cut Line= 3
      2251919.04     13309596.21      2252522.56     13309496.47
      2252918.66     13308771.31
#Sta/Elev= 30
  4200.1  137.65  4205.4   137.4    4219  137.24  4245.2  135.35  4302.7  133.56
  4402.8  130.47  4462.3  129.78  4502.8  128.51  4614.3   127.4  4663.1  128.03
  4822.8  130.32  4934.2  130.77  4961.7  129.29  4977.8  126.95  4983.5  125.04
  4996.6   122.8  4999.4   122.3  5002.6   122.8  5015.8   124.7  5021.5  126.83
  5027.9  127.41  5043.3  129.06  5081.2  130.95  5212.2  129.36  5337.4  130.28
  5369.7  131.43  5375.4   130.9  5462.7  131.82  5522.5  133.32  5638.1  138.04
#Mann= 9 ,-1 , 0
  4200.1     .08       0  4205.4     .05       0  4245.2      .1       0
  4302.7     .05       0  4402.8      .1       0  4502.8     .16       0
  4663.1      .1       0  4996.6     .07       0  5002.6      .1       0
#XS Ineff= 2 , 0
         4899.09  130.85 5091.82          130.83
Permanent Ineff=
       F       F
Bank Sta=4977.8,5027.9
XS Rating Curve= 0 ,0
Exp/Cntr=0.3,0.1

Type RM Length L Ch R = 1 ,14881   ,1109,1109,1109
BEGIN DESCRIPTION:
MCKIMZEY CREEK 10.0
END DESCRIPTION:
XS GIS Cut Line= 3
      2251851.45     13309645.22       2252628.4     13309662.59
       2253564.3      13309558.6
#Sta/Elev= 30
  3810.4  141.04  3899.6  137.59  4075.4  131.14  4226.8   127.2  4369.9  128.31
  4436.8  128.04  4466.8     125  4486.8  129.22  4496.8  134.92  4516.8  136.84
  4526.8  131.83  4546.9  126.45  4566.2   127.5  4627.1  129.83  4647.2  128.44
  4838.4  129.75  4908.8  129.51  4969.2  127.27  4996.4  119.62  4999.1  119.12
  5002.4  119.62  5019.5  123.12  5029.6  128.02  5039.6  129.48  5045.8  132.72
  5102.2  137.66  5180.5  143.64  5301.2  147.69  5452.2  147.98  5529.2  146.43
#Mann= 8 ,-1 , 0
  3810.4     .08       0  3899.6     .05       0  4075.4      .1       0
  4369.9     .16       0  4566.2      .1       0  4996.4     .07       0
  5002.4      .1       0  5102.2     .05       0
#XS Ineff= 2 , 0
         4507.73  136.77
Permanent Ineff=
       F       F
Bank Sta=4969.2,5029.6
XS Rating Curve= 0 ,0
Exp/Cntr=0.3,0.1

Type RM Length L Ch R = 1 ,13772   ,477,477,477
BEGIN DESCRIPTION:
MCKIMZEY CREEK 9.0
END DESCRIPTION:
XS GIS Cut Line= 2
      2252112.83     13310064.61      2252914.28     13310155.58
#Sta/Elev= 30
  4708.3  131.96  4750.7  130.61  4763.5  129.44  4823.9  127.67  4844.1   125.1
  4854.1   125.7  4865.2  130.74  4874.2   132.5  4894.4  134.18  4914.5   132.2
  4922.9  127.03  4924.6  125.98  4944.7  124.01  4949.8  122.25  4953.9     122
  4974.9  121.82    4985  119.84    4995  116.34  5002.1  116.02  5004.8  115.52
  5008.1  116.02  5015.1  120.49  5025.2     123  5034.4  125.19  5045.3  125.55
  5246.6   126.4  5290.5  127.51  5407.7  131.41  5437.8   133.5  5514.9  136.63
#Mann= 7 ,-1 , 0
  4708.3     .05       0  4750.7      .1       0  4922.9     .16       0
  4953.9      .1       0  5002.1     .07       0  5008.1      .1       0
  5290.5     .05       0
#XS Ineff= 2 , 0
         4886.93  133.93
Permanent Ineff=
       F       F
Bank Sta=4974.9,5025.2
XS Rating Curve= 0 ,0
Exp/Cntr=0.3,0.1

Type RM Length L Ch R = 1 ,13295   ,687,687,687
BEGIN DESCRIPTION:
MCKIMZEY CREEK 8.0
END DESCRIPTION:
XS GIS Cut Line= 4
      2251946.67      13310355.1      2252140.73     13310549.16
      2252735.04     13310585.55      2253111.02     13310415.75
#Sta/Elev= 30
  4503.1  140.06  4527.3  139.46  4561.6  138.05  4568.7  135.16  4575.8  134.19
  4618.2  131.75  4639.4  129.04  4646.5  129.15  4660.6  132.95  4674.8  134.25
  4710.1  128.55  4731.9  130.27  4834.8  125.95  4934.8  124.75  4964.9  123.71
  4982.6   120.6  4987.6   120.9  4994.9  116.32    5002  115.17  5004.7  114.67
    5008  115.17    5035  121.38  5075.1  123.98  5119.3  123.73  5245.4  122.72
  5315.7  123.92  5418.5   130.4  5527.8  138.18  5575.2  140.99  5785.5  145.24
#Mann= 11 ,-1 , 0
  4503.1     .05       0  4527.3      .1       0  4731.9     .16       0
  4834.8      .1       0    5002     .07       0    5008      .1       0
  5119.3     .05       0  5315.7      .1       0  5418.5     .16       0
  5527.8      .1       0  5575.2     .16       0
Bank Sta=4987.6,5035
XS Rating Curve= 0 ,0
Exp/Cntr=0.3,0.1

Type RM Length L Ch R = 1 ,12608   ,650,650,650
BEGIN DESCRIPTION:
MCKIMZEY CREEK 6.0
END DESCRIPTION:
XS GIS Cut Line= 4
      2251437.26     13310949.41      2252201.38     13311034.31
       2252844.2     13311094.96      2253122.93     13310525.39
#Sta/Elev= 30
  3801.8  140.45  3853.2  138.67  3876.1  138.19  3951.7  136.36  4050.2  131.13
  4092.3  127.96  4104.1  128.87  4114.2  132.58  4134.3   135.6  4144.4  134.06
  4154.4  129.18  4174.5  124.74  4273.4  124.89    4416  121.26  4486.4  123.29
  4911.9  120.82  4948.6  119.55  4970.3  118.14  4995.9  114.07  4998.6  113.57
  5001.9  114.07  5012.5  116.29  5018.9  118.98  5059.1  125.95  5149.5  131.33
  5215.6  130.82  5413.3  136.14  5516.1  135.51  5648.2  136.24  5850.4  141.69
#Mann= 11 ,-1 , 0
  3801.8     .05       0  3853.2      .1       0  3876.1     .05       0
  3951.7     .16       0  4050.2      .1       0  4911.9     .12       0
  4995.9     .07       0  5001.9     .12       0  5012.5      .1       0
  5516.1     .16       0  5648.2      .1       0
Bank Sta=4948.6,5018.9
XS Rating Curve= 0 ,0
Exp/Cntr=0.3,0.1

Type RM Length L Ch R = 1 ,11958   ,1220,1220,1220
BEGIN DESCRIPTION:
MCKIMZEY CREEK 5.0
END DESCRIPTION:
XS GIS Cut Line= 3
      2251537.75     13311396.86      2252337.72     13311646.85
      2252587.75     13311596.85
#Sta/Elev= 30
  4161.4  134.85    4164  134.85  4171.8  131.75  4177.6   128.6  4192.8  127.68
  4198.5  128.14  4234.7   128.3    4383  123.93  4410.2  124.09  4512.9     121
  4771.9  117.41  4863.3  118.56  4913.1  118.39  4945.6  116.87  4950.8  115.71
  4968.1  115.23  4993.9   111.9  4996.7   111.4  4999.9   111.9  5009.7  112.01
  5019.9  115.29  5030.1   115.7  5040.3  117.07  5043.2  117.04  5091.3  118.52
  5111.7  119.82  5121.9  121.23  5183.1   124.5  5213.7  127.11  5254.5  127.65
#Mann= 6 ,-1 , 0
  4161.4     .16       0  4198.5      .1       0  4771.9     .12       0
  4993.9     .07       0  4999.9     .12       0  5043.2      .1       0
Bank Sta=4945.6,5040.3
XS Rating Curve= 0 ,0
Exp/Cntr=0.3,0.1

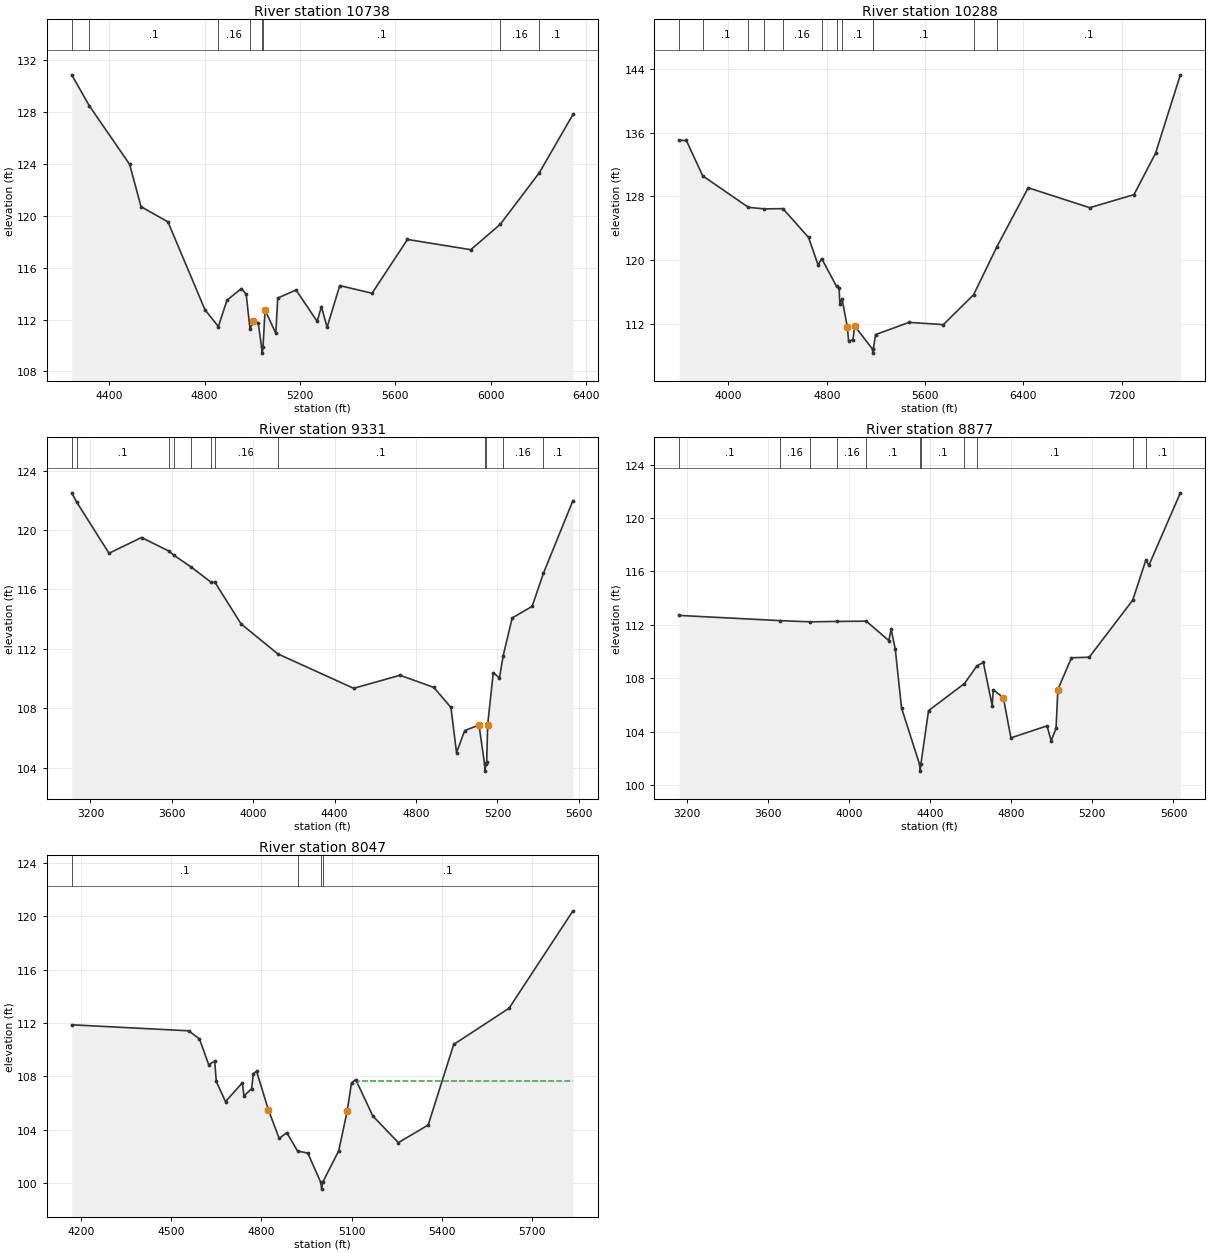
Type RM Length L Ch R = 1 ,10738   ,450,450,450
BEGIN DESCRIPTION:
MCKIMZEY CREEK 4.0
END DESCRIPTION:
XS GIS Cut Line= 3
      2251387.75     13312846.85      2252187.72     13312796.85
      2252687.71     13311596.88
#Sta/Elev= 30
  4243.3  130.88  4316.7   128.5  4486.2  123.97  4533.8  120.71  4646.6  119.54
  4801.9  112.76    4858  111.46  4894.5   113.5  4954.7  114.39  4974.7  113.96
  4990.7  111.28  5004.8  111.85  5024.8  111.76  5039.3  109.91  5042.1  109.41
  5045.3  109.91    5054  112.73    5099  110.94  5107.1  113.66    5184  114.28
  5272.3  111.86  5290.2     113    5314  111.41  5367.1  114.62  5502.5  114.03
    5651  118.18  5916.4  117.39  6040.3  119.35  6204.2  123.34  6344.8  127.82
#Mann= 8 ,-1 , 0
  4243.3     .05       0  4316.7      .1       0    4858     .16       0
  4990.7      .1       0  5039.3     .07       0  5045.3      .1       0
  6040.3     .16       0  6204.2      .1       0
Bank Sta=5004.8,5054
XS Rating Curve= 0 ,0
Exp/Cntr=0.3,0.1

Type RM Length L Ch R = 1 ,10288   ,957,957,957
BEGIN DESCRIPTION:
MCKIMZEY CREEK 3.0
END DESCRIPTION:
XS GIS Cut Line= 4
      2251218.92     13313411.56      2252019.45     13313363.04
      2252735.04     13312708.09      2253401.95     13310501.22
#Sta/Elev= 30
  3599.4  135.04  3658.3  135.03  3790.9  130.59  4162.7  126.64  4289.4  126.44
    4444  126.47  4652.4  122.85  4730.1  119.39  4758.7  120.21  4880.2   116.7
  4900.3  116.55  4907.1  114.44  4924.1  115.16 4967.87  111.64    4978  109.86
  5013.1     110  5027.3  111.74  5172.9  108.83  5175.7  108.33  5178.9  108.83
  5197.5  110.66  5469.6  112.19  5748.9  111.91  5995.3  115.67  6185.3  121.71
  6439.3  129.09  6939.7  126.59  7299.7  128.23  7474.9  133.42  7676.9  143.27
#Mann= 12 ,-1 , 0
  3599.4     .05       0  3790.9      .1       0  4162.7     .16       0
  4289.4      .1       0    4444     .16       0  4758.7      .1       0
  4880.2     .16       0  4924.1      .1       0  5172.9     .07       0
  5178.9      .1       0  5995.3     .16       0  6185.3      .1       0
Bank Sta=4967.87,5027.3
XS Rating Curve= 0 ,0
Exp/Cntr=0.3,0.1

Type RM Length L Ch R = 1 ,9331    ,454,454,454
BEGIN DESCRIPTION:
MCKIMZEY CREEK 2.0
END DESCRIPTION:
XS GIS Cut Line= 3
      2251687.72     13313996.86      2253287.72     13313046.85
      2253337.72     13312446.82
#Sta/Elev= 30
  3108.1  122.51  3132.3  121.89  3291.3  118.44    3451   119.5  3585.2  118.59
  3610.4   118.3  3695.2  117.51  3794.5  116.47  3811.5  116.49  3940.1  113.68
  4120.8  111.66  4493.4  109.34  4721.4  110.22  4887.5   109.4  4971.4  108.05
    4999  105.01  5039.1  106.49  5109.4  106.87  5136.5  104.26  5139.2  103.76
  5142.5  104.26    5147  104.35    5152   106.9  5179.6   110.4  5209.7  110.03
  5227.9  111.52  5272.4  114.08  5370.3  114.86  5425.6  117.08    5571  121.99
#Mann= 12 ,-1 , 0
  3108.1     .16       0  3132.3      .1       0  3585.2     .16       0
  3610.4      .1       0  3695.2     .16       0  3794.5      .1       0
  3811.5     .16       0  4120.8      .1       0  5136.5     .07       0
  5142.5      .1       0  5227.9     .16       0  5425.6      .1       0
Bank Sta=5109.4,5152
XS Rating Curve= 0 ,0
Exp/Cntr=0.3,0.1

Type RM Length L Ch R = 1 ,8877    ,830,830,830
BEGIN DESCRIPTION:
MCKIMZEY CREEK 1.01
END DESCRIPTION:
XS GIS Cut Line= 3
      2254087.73     13314796.88      2253687.72     13312996.85
      2253387.74     13312446.88
#Sta/Elev= 30
  3163.5  112.71  3661.1  112.32  3807.8  112.23  3941.1  112.26  4085.7  112.28
  4196.9  110.83  4208.4  111.66  4228.9  110.18  4259.6  105.78  4348.8  101.55
  4351.6  101.05  4354.8  101.55  4392.8  105.58  4569.9  107.61    4631  108.93
    4663  109.19  4706.5  105.95  4711.6  107.14  4761.6  106.55  4798.7  103.54
  4976.7  104.44  4997.2  103.33  5021.2  104.25  5030.2  107.16  5097.1  109.54
  5184.5  109.58    5399  113.85    5464  116.86  5478.7  116.46  5633.9  121.89
#Mann= 11 ,-1 , 0
  3163.5      .1       0  3661.1     .16       0  3807.8      .1       0
  3941.1     .16       0  4085.7      .1       0  4348.8     .07       0
  4354.8      .1       0  4569.9     .05       0    4631      .1       0
    5399     .16       0    5464      .1       0
#XS Ineff= 2 , 0
         4661.93  109.12
Permanent Ineff=
       F       F
Bank Sta=4761.6,5030.2
XS Rating Curve= 0 ,0
Exp/Cntr=0.3,0.1

Type RM Length L Ch R = 1 ,8047    ,442,442,442
BEGIN DESCRIPTION:
MCKIMZEY CREEK 1.91
END DESCRIPTION:
XS GIS Cut Line= 3
      2254366.58     13313813.72      2254087.72     13313046.85
      2253487.74     13312446.87
#Sta/Elev= 30
  4170.2  111.87  4558.6  111.42  4594.5  110.81  4625.1  108.88    4645  109.16
  4650.3  107.63  4680.9  106.12  4736.8  107.53  4742.1  106.55  4767.4  107.08
  4773.4  108.22    4784  108.39  4823.3  105.51  4859.2  103.36  4884.4   103.8
  4920.2  102.42  4954.3  102.27  4997.3  100.07  5000.1   99.57  5003.3  100.07
  5056.9  102.44  5085.2  105.44  5099.3  107.52  5113.5  107.77    5170  105.05
  5254.9  103.05  5353.9  104.37  5438.7   110.4  5622.6  113.11  5834.7   120.4
#Mann= 4 ,-1 , 0
  4170.2      .1       0  4920.2     .16       0  4997.3     .07       0
  5003.3      .1       0
#XS Ineff= 2 , 0
                         5121.59          107.66
Permanent Ineff=
       F       F
Bank Sta=4823.3,5085.2
XS Rating Curve= 0 ,0
Exp/Cntr=0.3,0.1