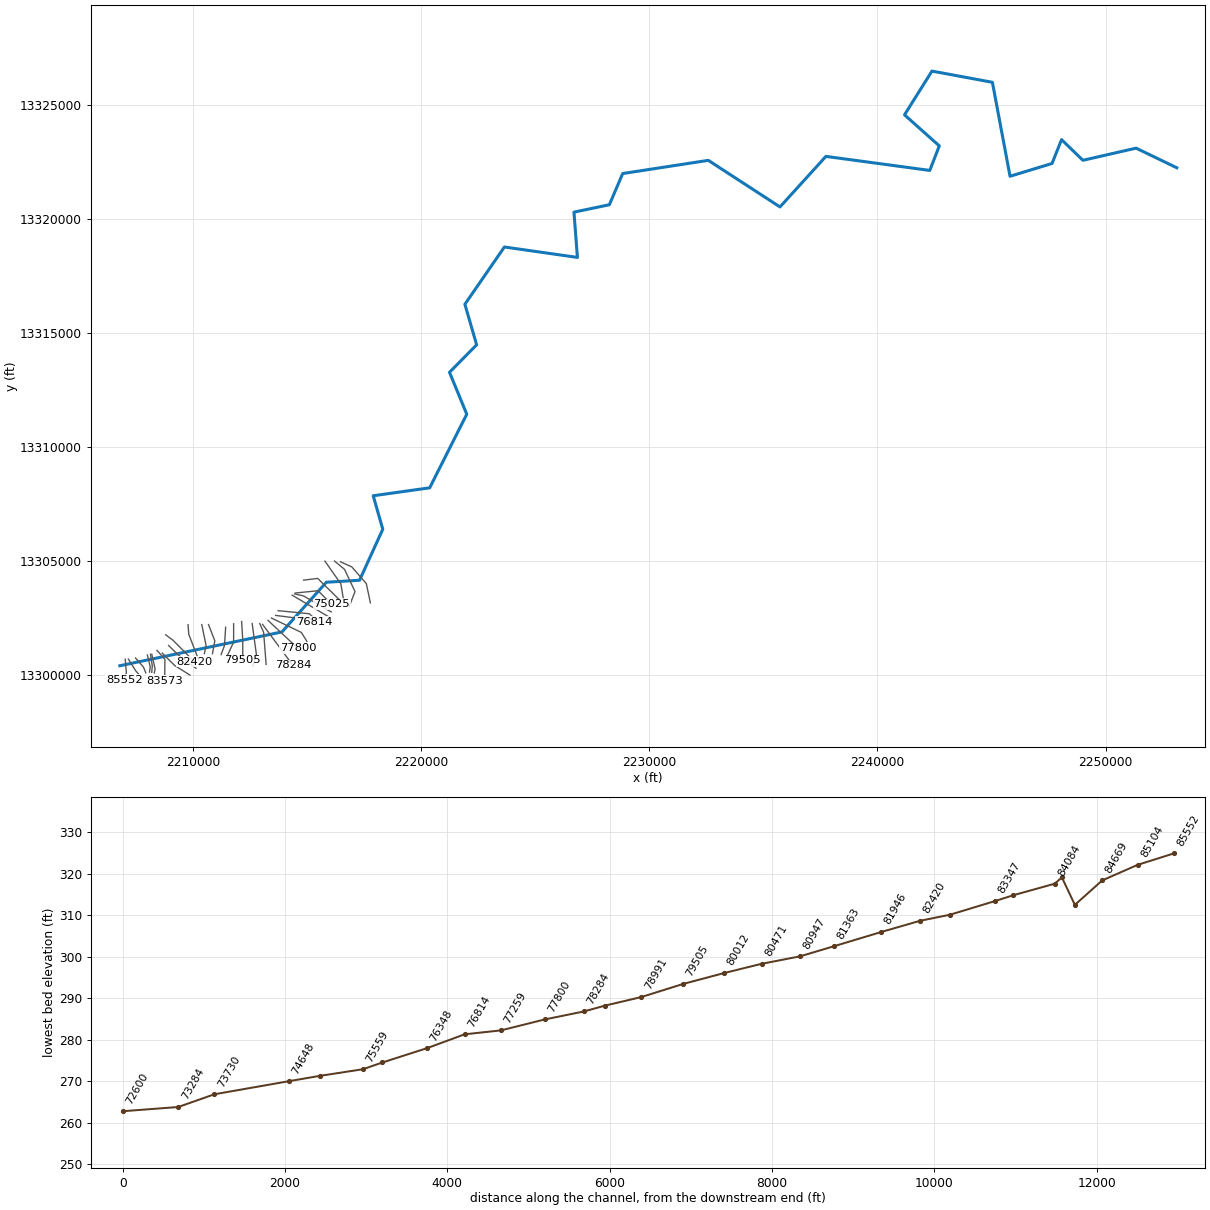
--- SALT BRANCH.prj (project) ---

Proj Title=SALT BRANCH Base Level Engineering
Current Plan=p01
Default Exp/Contr=0.3,0.1
English Units
Geom File=g01
Flow File=f01
Plan File=p01
Y Axis Title=Elevation
X Axis Title(PF)=Main Channel Distance
X Axis Title(XS)=Station
BEGIN DESCRIPTION:
SALT BRANCH
END DESCRIPTION:
DSS Export Rating Curves= 0
DSS Export Rating Curve Sorted= 0
DSS Export Volume Flow Curves= 0
DXF OffsetX= 0
DXF OffsetY= 0
DXF ScaleX= 1
DXF ScaleY= 10

--- SALT BRANCH.p01 (plan) ---

Plan Title=Multiple Run
Short Identifier=Multiple
Geom File=g01
Flow File=f01
Subcritical Flow
K Sum by GR= 0
Std Step Tol= 0.01
Critical Tol= 0.01
Num of Std Step Trials= 20
Max Error Tol= 0.3
Flow Tol Ratio= 0.001
Split Flow NTrial= 30
Split Flow Tol= 0.02
Split Flow Ratio= 0.02
Log Output Level= 0
Friction Slope Method= 1
Unsteady Friction Slope Method= 2
Unsteady Bridges Friction Slope Method= 1
Parabolic Critical Depth
Global Vel Dist=  1 , 1 , 1
Global Log Level= 0
CheckData=True
Encroach Param= -1, 0, 0, 0
BEGIN DESCRIPTION:
Multiple Run
END DESCRIPTION:

--- SALT BRANCH.f01 (steady flow) ---

Flow Title=Multiple
Program Version=4.10
Number of Profiles= 7
Profile Names=10-year,25-year,50-year,1pct_min,100-year,1pct_plu,500-year
River Rch & RM=SALT BRANCH,Reach-1         ,85552
     181     248     302     271     367     496     549
River Rch & RM=SALT BRANCH,Reach-1         ,83347
     419     599     753     695     940    1272    1490
River Rch & RM=SALT BRANCH,Reach-1         ,82796
     419     599     753     695     940    1272    1490
River Rch & RM=SALT BRANCH,Reach-1         ,78284
     681     992    1263    1179    1594    2156    2582
River Rch & RM=SALT BRANCH,Reach-1         ,77259
     681     992    1263    1179    1594    2156    2582
River Rch & RM=SALT BRANCH,Reach-1         ,72041
     850    1247    1593    1492    2018    2729    3289
River Rch & RM=SALT BRANCH,Reach-1         ,71440
     850    1247    1593    1492    2018    2729    3289
River Rch & RM=SALT BRANCH,Reach-1         ,65107
     858    1255    1601    1497    2024    2737    3286
River Rch & RM=SALT BRANCH,Reach-1         ,60530
     993    1457    1862    1743    2357    3188    3837
River Rch & RM=SALT BRANCH,Reach-1         ,58508
     993    1457    1862    1743    2357    3188    3837
River Rch & RM=SALT BRANCH,Reach-1         ,53018
    1043    1532    1959    1835    2481    3356    4043
River Rch & RM=SALT BRANCH,Reach-1         ,49614
    1090    1602    2051    1922    2600    3516    4242
River Rch & RM=SALT BRANCH,Reach-1         ,43305
    1132    1665    2131    1998    2702    3654    4409
River Rch & RM=SALT BRANCH,Reach-1         ,42264
    1187    1749    2241    2101    2842    3843    4644
River Rch & RM=SALT BRANCH,Reach-1         ,41610
    1247    1839    2359    2215    2996    4051    4906
River Rch & RM=SALT BRANCH,Reach-1         ,37759
    1260    1856    2379    2232    3018    4081    4933
River Rch & RM=SALT BRANCH,Reach-1         ,33473
    1620    2404    3096    2917    3945    5335    6503
River Rch & RM=SALT BRANCH,Reach-1         ,27146
    1659    2464    3175    2993    4048    5474    6680
River Rch & RM=SALT BRANCH,Reach-1         ,26840
    1688    2506    3230    3045    4117    5568    6794
River Rch & RM=SALT BRANCH,Reach-1         ,20275
    1752    2602    3353    3161    4275    5781    7053
River Rch & RM=SALT BRANCH,Reach-1         ,16575
    1765    2617    3370    3173    4291    5803    7064
Boundary for River Rch & Prof#=SALT BRANCH,Reach-1         , 1
Up Type= 0
Dn Type= 3
Dn Slope=0.005
Boundary for River Rch & Prof#=SALT BRANCH,Reach-1         , 2
Up Type= 0
Dn Type= 3
Dn Slope=0.005
Boundary for River Rch & Prof#=SALT BRANCH,Reach-1         , 3
Up Type= 0
Dn Type= 3
Dn Slope=0.005
Boundary for River Rch & Prof#=SALT BRANCH,Reach-1         , 4
Up Type= 0
Dn Type= 3
Dn Slope=0.005
Boundary for River Rch & Prof#=SALT BRANCH,Reach-1         , 5
Up Type= 0
Dn Type= 3
Dn Slope=0.005
Boundary for River Rch & Prof#=SALT BRANCH,Reach-1         , 6
Up Type= 0
Dn Type= 3
Dn Slope=0.005
Boundary for River Rch & Prof#=SALT BRANCH,Reach-1         , 7
Up Type= 0
Dn Type= 3
Dn Slope=0.005
DSS Import GetInterval= 0
DSS Import GetPeak= 0
DSS Import FillOption= 0

--- SALT BRANCH.g01 (geometry) ---

Geom Title=Existing Conditions
Program Version=4.10

River Reach=SALT BRANCH     ,Reach-1
Reach XY= 30
      2206799.01     13300406.77      2213906.33     13301890.83
      2215851.24      13304069.6      2217306.82     13304157.58
      2218324.11     13306393.33      2217905.58     13307863.17
      2220380.16      13308210.4      2222004.48      13311438.2
      2221248.09     13313276.05      2222437.18     13314481.55
      2221922.68     13316259.73      2223655.09     13318771.83
      2226854.28     13318314.26      2226702.21     13320299.77
       2228254.3     13320624.76      2228838.64     13321993.23
      2232589.52      13322571.6      2235731.94     13320528.32
      2237743.54     13322744.89      2242296.46     13322129.89
      2242713.96      13323205.3      2241188.88     13324566.76
      2242391.46       13326486.      2245040.22     13325994.62
      2245813.77     13321874.89      2247654.48     13322434.78
      2248070.97     13323480.83      2249007.03     13322573.75
      2251338.63     13323106.48      2253121.28     13322246.29

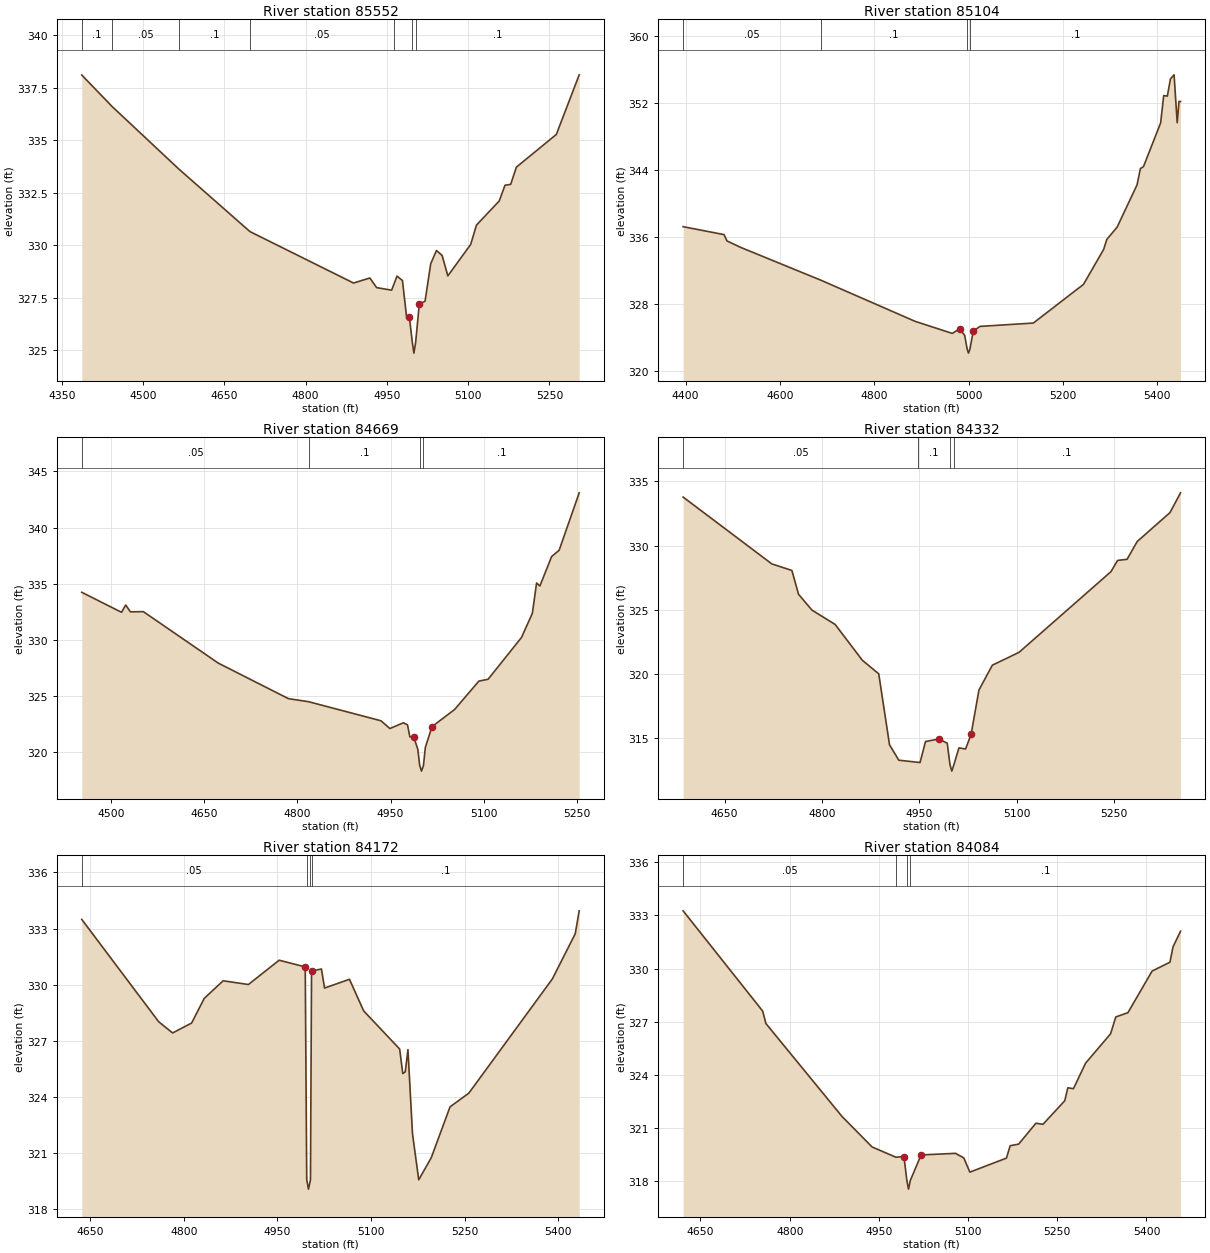
Type RM Length L Ch R = 1 ,85552   ,448,448,448
BEGIN DESCRIPTION:
SALT BRANCH 137.0
END DESCRIPTION:
XS GIS Cut Line= 3
      2207037.72     13300696.84      2207087.72     13300096.85
      2206987.72     13299796.84
#Sta/Elev= 30
  4386.7   338.1  4442.7   336.6  4565.5  333.63  4697.2  330.64  4888.4  328.19
  4918.5  328.43  4931.1  327.97  4958.7  327.85  4962.9  328.13  4968.7  328.52
  4978.7  328.31  4986.3  326.58  4991.4  326.58    4997  325.35  4999.8  324.85
    5003  325.35  5009.8  327.19  5020.4  327.32  5030.9  329.11  5041.5  329.74
    5052   329.5  5062.5  328.53  5104.7  330.03  5115.3  330.95  5157.4   332.1
    5168  332.85  5178.5  332.89    5189  333.71  5262.8  335.27    5305  338.11
#Mann= 7 ,-1 , 0
  4386.7      .1       0  4442.7     .05       0  4565.5      .1       0
  4697.2     .05       0  4962.9      .1       0    4997     .07       0
    5003      .1       0
Bank Sta=4991.4,5009.8
XS Rating Curve= 0 ,0
Exp/Cntr=0.3,0.1

Type RM Length L Ch R = 1 ,85104   ,435,435,435
BEGIN DESCRIPTION:
SALT BRANCH 136.0
END DESCRIPTION:
XS GIS Cut Line= 3
      2207173.04     13300700.34      2207487.72     13300196.85
      2207787.71     13299846.86
#Sta/Elev= 30
  4394.8  337.22  4481.5  336.27  4487.9  335.51  4516.8  334.74  4687.8  330.79
  4886.5  325.89  4965.5  324.44  4980.9  324.99  4991.8  324.21    4997  322.58
  4999.8  322.08    5003  322.58  5009.9   324.7  5024.2  325.28  5137.3  325.68
  5243.7  330.31  5286.5   334.5  5293.1  335.69  5315.1  337.17  5357.3  342.23
  5364.4  344.17    5371  344.42  5407.3  349.65  5413.8  352.92  5421.5  352.85
  5428.1  354.92  5435.8   355.4  5442.4  349.67  5446.2  352.21  5449.5  352.21
#Mann= 4 ,-1 , 0
  4394.8     .05       0  4687.8      .1       0    4997     .07       0
    5003      .1       0
Bank Sta=4980.9,5009.9
XS Rating Curve= 0 ,0
Exp/Cntr=0.3,0.1

Type RM Length L Ch R = 1 ,84669   ,337,337,337
BEGIN DESCRIPTION:
SALT BRANCH 135.0
END DESCRIPTION:
XS GIS Cut Line= 3
      2207487.75     13300746.82      2207837.72     13300346.85
      2207937.71     13300096.88
#Sta/Elev= 30
    4453  334.25    4517  332.47  4523.7  333.12  4531.3  332.51  4552.1  332.53
  4672.7  327.95  4785.6  324.79  4818.5  324.51  4934.6  322.82  4948.9  322.13
  4970.7  322.64  4977.3  322.46  4981.1  321.39  4987.2  321.39  4993.9  320.29
    4997  318.84  4999.8  318.34    5003  318.84    5006  320.45  5016.8   322.3
  5053.1  323.82  5092.2  326.35    5107  326.51  5160.8  330.23  5178.3  332.38
  5185.1  335.08  5190.4  334.81  5209.3  337.43  5221.4  337.99  5253.7   343.1
#Mann= 4 ,-1 , 0
    4453     .05       0  4818.5      .1       0    4997     .07       0
    5003      .1       0
Bank Sta=4987.2,5016.8
XS Rating Curve= 0 ,0
Exp/Cntr=0.3,0.1

Type RM Length L Ch R = 1 ,84332   ,160,160,160
BEGIN DESCRIPTION:
Mapping XS 604bce04
END DESCRIPTION:
XS GIS Cut Line= 3
       2208007.8     13300879.63       2208132.8     13300362.24
       2208101.7      13300130.7
#Sta/Elev= 30
  4586.1  333.77  4722.7  328.57  4753.6  328.06  4763.8  326.21  4784.4  324.98
  4820.2  323.86  4862.1  321.07  4887.3  320.02  4903.9   314.5  4918.2   313.3
  4947.1  313.14  4950.9  313.12  4959.3  314.75  4979.9  314.95  4992.8  314.62
    4997  312.95  4999.8  312.45    5003  312.95  5010.8  314.26    5021  314.17
  5029.5  315.31  5041.6  318.76  5062.2  320.69  5103.3  321.69  5244.9  327.97
    5255  328.84  5269.7  328.93  5285.2  330.31  5335.7  332.56    5352   334.1
#Mann= 4 ,-1 , 0
  4586.1     .05       0  4947.1      .1       0    4997     .07       0
    5003      .1       0
Bank Sta=4979.9,5029.5
XS Rating Curve= 0 ,0
Exp/Cntr=0.3,0.1

Type RM Length L Ch R = 1 ,84172   ,88,88,88
BEGIN DESCRIPTION:
Mapping XS b834e9cf
END DESCRIPTION:
XS GIS Cut Line= 3
      2208143.22     13300910.85      2208223.08     13300400.44
      2208198.89      13300120.5
#Sta/Elev= 30
  4636.3  333.49  4759.6  328.02    4782  327.42  4812.4  327.95  4832.7  329.27
    4863  330.21  4903.5  330.01  4952.8  331.31  4994.6  330.95    4997  319.57
  4999.8  319.07    5003  319.57  5004.7  330.74    5006  330.74  5020.6  330.84
  5025.6  329.82  5065.5  330.29  5088.3   328.6    5146  326.56    5151  325.25
    5155  325.34  5159.3  326.53  5166.6  322.03  5176.6  319.57  5196.7  320.75
  5226.8  323.47  5256.9   324.2  5390.9  330.31  5427.5  332.72  5433.9  333.95
#Mann= 4 ,-1 , 0
  4636.3     .05       0    4997    .035       0    5003     .05       0
    5006      .1       0
Bank Sta=4994.6,5004.7
XS Rating Curve= 0 ,0
Exp/Cntr=0.3,0.1

Type RM Length L Ch R = 1 ,84084   ,511,511,511
BEGIN DESCRIPTION:
Mapping XS 9e4044eb
END DESCRIPTION:
XS GIS Cut Line= 3
      2208202.24     13300907.42      2208344.61     13300271.97
      2208310.25     13300089.89
#Sta/Elev= 30
  4620.8  333.26  4754.6   327.6    4760   326.9  4887.8  321.66  4938.6  319.93
  4978.7  319.35  4992.2  319.39    4997  318.05  4999.8  317.55    5003  318.05
    5021  319.48  5078.9  319.57  5092.8  319.31    5103  318.51  5164.5   319.3
  5170.8     320    5185  320.09  5214.1  321.27    5226  321.21  5262.6  322.54
  5267.7  323.27  5277.2  323.22  5297.6  324.66  5339.7  326.32  5348.4  327.27
  5368.8  327.51  5409.5  329.86  5439.5  330.36  5444.6  331.22  5457.3  332.11
#Mann= 4 ,-1 , 0
  4620.8     .05       0  4978.7      .1       0    4997     .07       0
    5003      .1       0
Bank Sta=4992.2,5021
XS Rating Curve= 0 ,0
Exp/Cntr=0.3,0.1

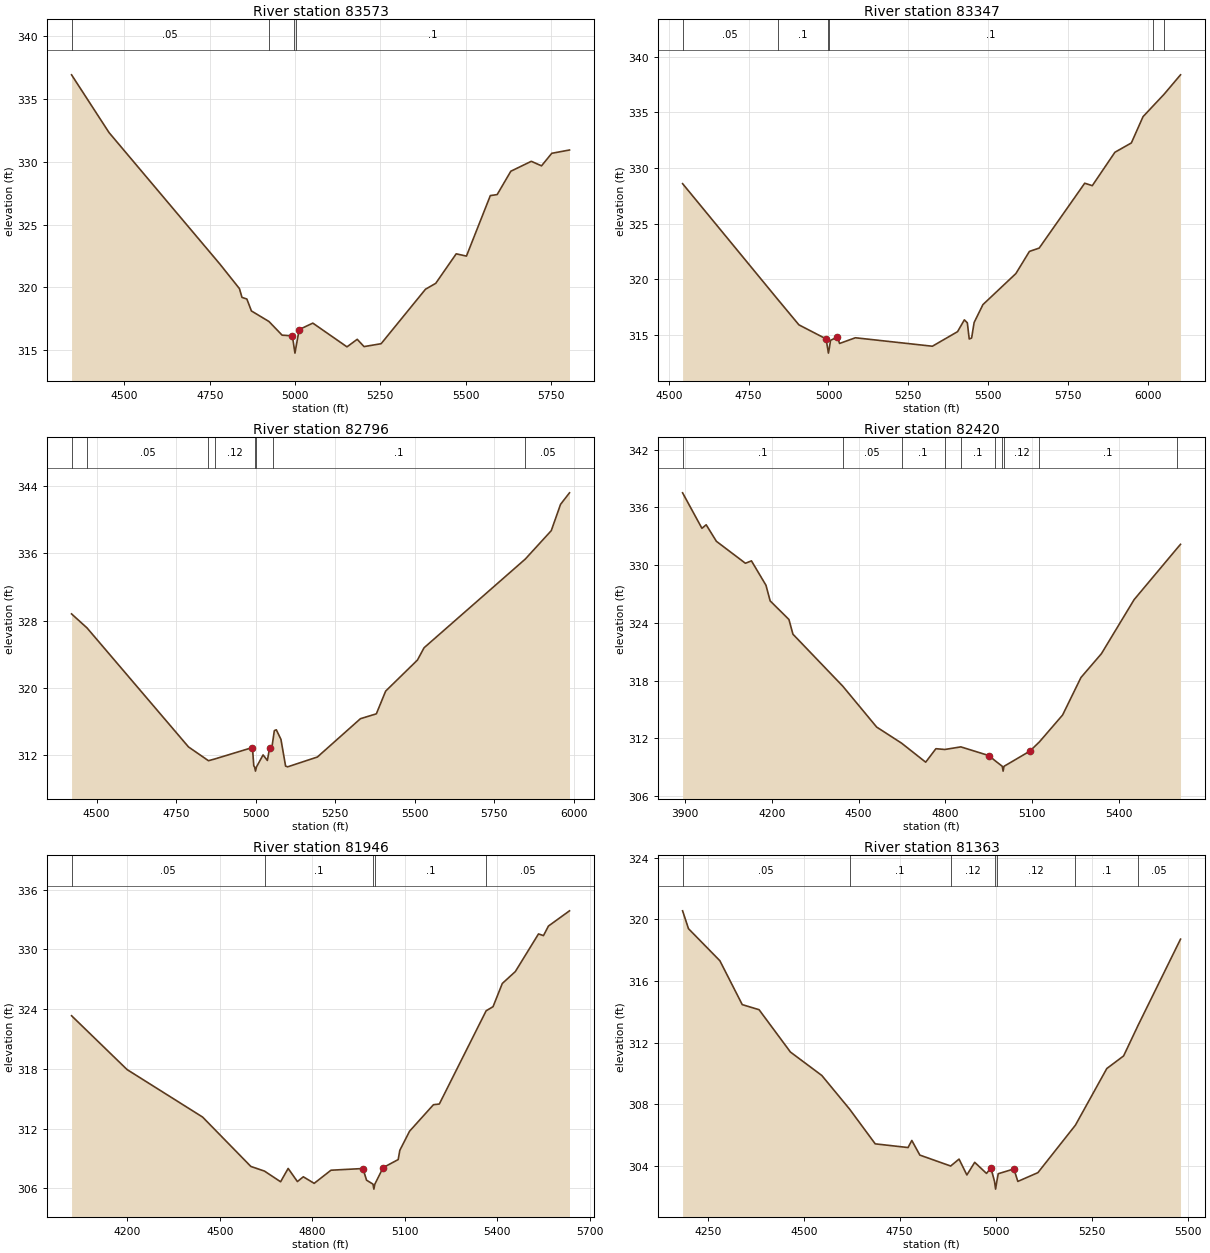
Type RM Length L Ch R = 1 ,83573   ,226,226,226
BEGIN DESCRIPTION:
SALT BRANCH 132.0
END DESCRIPTION:
XS GIS Cut Line= 3
      2208427.46     13301081.33      2208774.67     13300692.46
      2208767.73       13299755.
#Sta/Elev= 30
  4345.3  336.94  4455.1  332.34  4780.3  321.85  4837.1  319.91  4844.6  319.21
  4858.9  319.08  4872.2  318.13  4923.6  317.29  4962.2   316.2  4992.2  316.15
    4997  315.27  4999.8  314.77    5003  315.27  5012.2  316.65  5052.2  317.16
  5152.2  315.27  5182.2  315.87  5202.2  315.29  5252.2  315.52  5382.2  319.86
  5412.2  320.33  5472.2  322.68  5502.2   322.5  5572.2  327.32  5592.2   327.4
  5632.2  329.26  5692.2  330.05  5722.2  329.69  5752.2  330.69  5804.1  330.95
#Mann= 4 ,-1 , 0
  4345.3     .05       0  4923.6      .1       0    4997     .07       0
    5003      .1       0
Bank Sta=4992.2,5012.2
XS Rating Curve= 0 ,0
Exp/Cntr=0.3,0.1

Type RM Length L Ch R = 1 ,83347   ,551,551,551
BEGIN DESCRIPTION:
SALT BRANCH 133.0
END DESCRIPTION:
XS GIS Cut Line= 3
      2208658.19     13300962.73      2209199.86     13300421.06
      2209871.75     13299999.17
#Sta/Elev= 30
  4543.1  328.59  4841.7  318.17  4907.5   315.9  4992.4  314.64    4997  313.86
  4999.8  313.36    5003  313.86  5006.5  314.51  5027.8   314.8  5034.8  314.23
  5084.3  314.74  5325.4  313.98  5404.3  315.29  5425.5  316.35  5434.9  316.08
  5440.8  314.63  5448.3  314.72  5456.1  316.11  5483.7  317.72  5586.9  320.51
  5629.3   322.5  5659.9   322.8  5802.5  328.63  5826.2  328.41    5897  331.41
  5948.6  332.25  5985.1  334.61  6015.5  335.54  6050.9  336.62  6102.5  338.37
#Mann= 6 ,-1 , 0
  4543.1     .05       0  4841.7      .1       0    4997     .07       0
    5003      .1       0  6015.5     .05       0  6050.9      .1       0
#XS Ineff= 1 ,-1
 5425.53 5463.76  316.34
Permanent Ineff=
       F
Bank Sta=4992.4,5027.8
XS Rating Curve= 0 ,0
Exp/Cntr=0.3,0.1

Type RM Length L Ch R = 1 ,82796   ,376,376,376
BEGIN DESCRIPTION:
SALT BRANCH 131.0
END DESCRIPTION:
XS GIS Cut Line= 3
      2208937.69     13301296.88      2209337.72     13300896.85
       2210137.7     13300296.87
#Sta/Elev= 30
  4421.5   328.8  4470.2  327.13  4789.2  312.97    4852  311.33  4871.3  311.53
  4990.3   312.9  4994.5  310.72    4997  310.59  4999.8  310.09    5003  310.59
  5023.7  312.02  5037.2  311.36  5044.5   312.9  5050.8  312.74  5054.7  313.76
  5059.1  314.91  5065.3  315.01  5079.9  313.87  5094.5  310.69  5100.8   310.6
  5194.5  311.77  5329.9  316.33  5379.9  316.91  5409.1  319.61  5509.1  323.31
  5529.9  324.77  5848.3  335.33  5929.9  338.71  5959.1  341.84  5987.2  343.21
#Mann= 8 ,-1 , 0
  4421.5      .1       0  4470.2     .05       0    4852      .1       0
  4871.3     .12       0    4997     .07       0    5003     .12       0
  5054.7      .1       0  5848.3     .05       0
Bank Sta=4990.3,5044.5
XS Rating Curve= 0 ,0
Exp/Cntr=0.3,0.1

Type RM Length L Ch R = 1 ,82420   ,474,474,474
BEGIN DESCRIPTION:
SALT BRANCH 130.0
END DESCRIPTION:
XS GIS Cut Line= 3
      2208809.37     13301761.92      2209121.89     13301532.73
      2210066.34     13300588.29
#Sta/Elev= 30
  3890.6  337.51  3957.6  333.82  3972.2  334.19  4007.7  332.47  4108.1  330.19
  4128.9  330.44  4179.1  327.91  4193.7  326.28  4258.6  324.35  4272.5  322.82
  4444.9  317.42  4562.2  313.17  4648.3   311.5  4731.9  309.52  4767.3  310.92
  4798.3  310.84  4853.6  311.11  4951.1   310.2  4970.1  309.72    4997  309.09
  4999.8  308.59    5003  309.09  5092.5  310.67  5125.5  311.63  5205.7  314.42
  5269.3  318.32    5340  320.79  5453.2  326.41  5600.2  331.68  5613.8  332.16
#Mann= 10 ,-1 , 0
  3890.6      .1       0  4444.9     .05       0  4648.3      .1       0
  4798.3     .12       0  4853.6      .1       0  4970.1     .12       0
    4997     .07       0    5003     .12       0  5125.5      .1       0
  5600.2     .05       0
Bank Sta=4951.1,5092.5
XS Rating Curve= 0 ,0
Exp/Cntr=0.3,0.1

Type RM Length L Ch R = 1 ,81946   ,583,583,583
BEGIN DESCRIPTION:
SALT BRANCH 129.0
END DESCRIPTION:
XS GIS Cut Line= 3
      2209788.56     13302206.35      2209823.28     13301782.73
      2210253.24     13300673.16
#Sta/Elev= 30
  4019.3  323.33  4199.4  317.92  4444.3  313.15  4600.8  308.19  4645.1  307.72
  4697.3  306.65  4721.8  307.99  4751.8  306.67    4771  307.15  4806.2  306.49
  4860.7  307.81  4964.3  307.98  4976.1  306.81    4997  306.41  4999.8  305.91
    5003  306.41  5029.8  308.07  5078.7  308.88    5084  309.81  5115.6  311.73
    5193  314.39  5212.1  314.46    5364  323.83  5386.4  324.24  5416.3  326.57
  5458.7  327.77  5533.8  331.55  5549.9  331.38    5566  332.34  5634.3  333.87
#Mann= 5 ,-1 , 0
  4019.3     .05       0  4645.1      .1       0    4997     .07       0
    5003      .1       0    5364     .05       0
Bank Sta=4964.3,5029.8
XS Rating Curve= 0 ,0
Exp/Cntr=0.3,0.1

Type RM Length L Ch R = 1 ,81363   ,416,416,416
BEGIN DESCRIPTION:
SALT BRANCH 128.0
END DESCRIPTION:
XS GIS Cut Line= 3
      2210390.81      13302211.9       2210578.3     13301305.66
      2210505.47      13300941.5
#Sta/Elev= 30
  4184.6  320.55    4200  319.39  4281.7  317.31    4340  314.46  4383.8  314.13
  4465.5  311.38  4547.2  309.86  4619.7  307.67  4686.3  305.42  4771.8  305.18
  4781.6  305.64  4802.5  304.69  4882.8  303.98  4904.6  304.43    4925   303.4
  4945.4  304.22  4976.1   303.5  4987.6  303.86    4997  302.98  4999.8  302.48
    5003  302.98  5006.7  303.48  5047.5  303.79  5057.7  302.98    5110  303.55
  5207.6  306.63  5289.4  310.31  5333.2  311.13  5370.8  313.11  5481.4  318.71
#Mann= 7 ,-1 , 0
  4184.6     .05       0  4619.7      .1       0  4882.8     .12       0
    4997     .07       0    5003     .12       0  5207.6      .1       0
  5370.8     .05       0
Bank Sta=4987.6,5047.5
XS Rating Curve= 0 ,0
Exp/Cntr=0.3,0.1

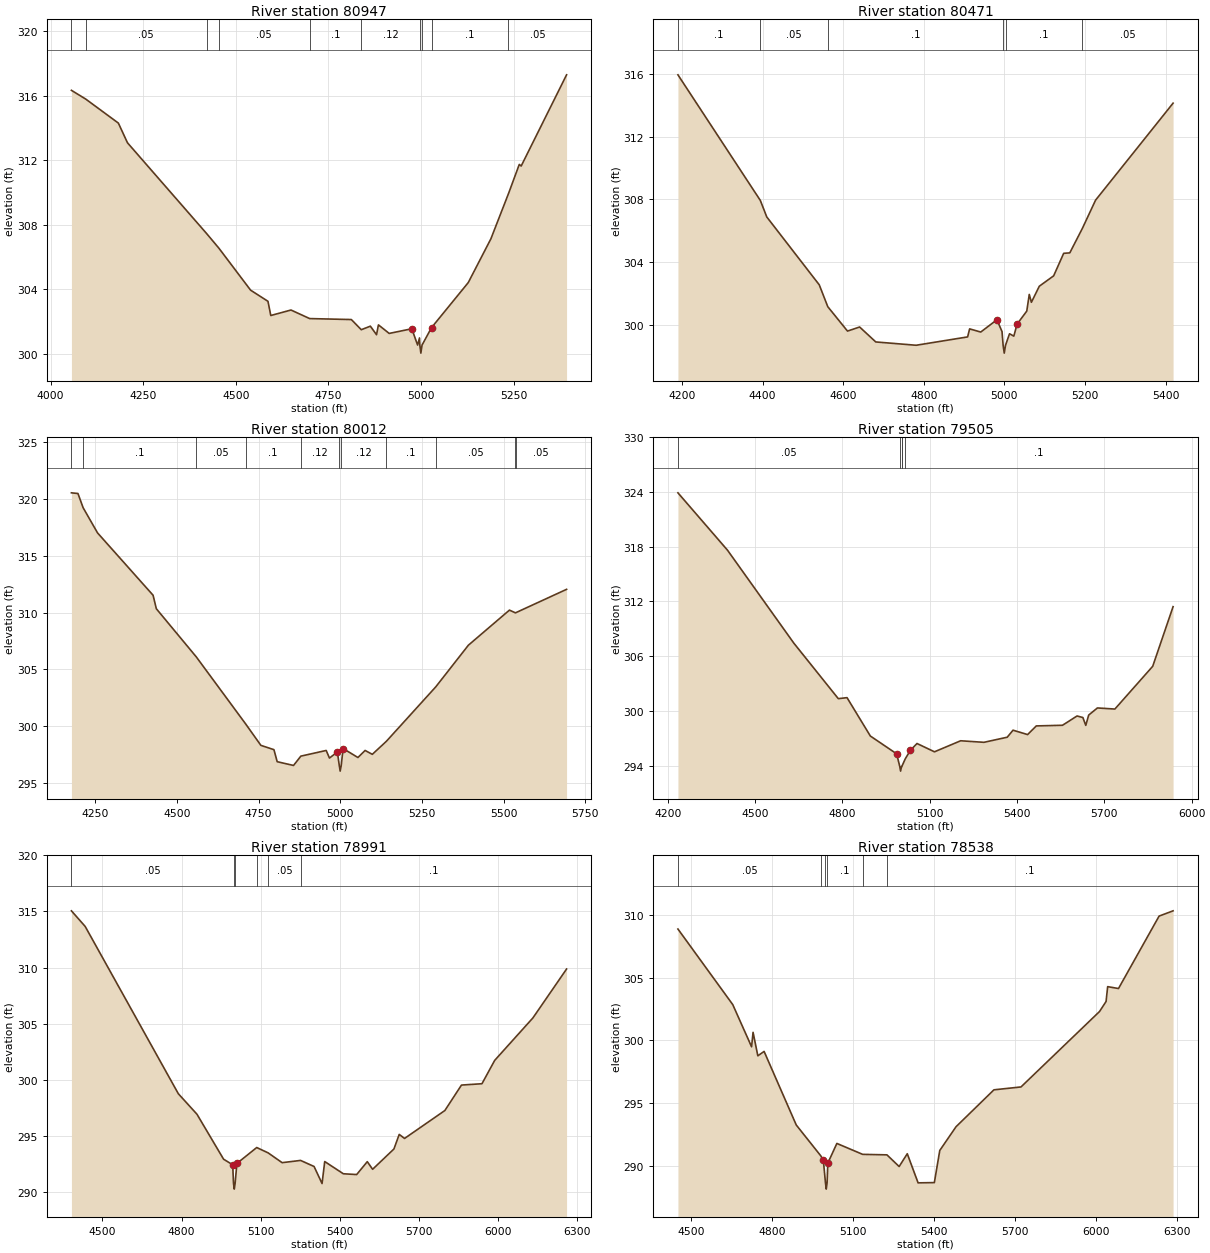
Type RM Length L Ch R = 1 ,80947   ,476,476,476
BEGIN DESCRIPTION:
SALT BRANCH 127.0
END DESCRIPTION:
XS GIS Cut Line= 3
      2210687.67     13302211.94      2210963.72     13301498.37
      2210859.55     13300935.84
#Sta/Elev= 30
  4056.1  316.33  4094.6  315.79  4182.9   314.3  4207.5  313.08  4421.1  307.46
  4454.4  306.55    4540  303.95  4586.9  303.26  4594.5  302.38    4649  302.72
  4699.6  302.19  4812.1  302.13  4838.9   301.5  4863.4  301.72  4880.1  301.19
  4885.2   301.8  4914.3  301.27  4975.3  301.56    4991  300.55  4996.1  300.99
    4997  300.55  4999.8  300.05    5003  300.55  5028.6  301.63  5127.8  304.42
  5188.9  307.13  5236.4  309.93  5265.6  311.74  5270.7  311.64  5393.3  317.29
#Mann= 10 ,-1 , 0
  4056.1      .1       0  4094.6     .05       0  4421.1      .1       0
  4454.4     .05       0  4699.6      .1       0  4838.9     .12       0
    4997     .07       0    5003     .12       0  5028.6      .1       0
  5236.4     .05       0
Bank Sta=4975.3,5028.6
XS Rating Curve= 0 ,0
Exp/Cntr=0.3,0.1

Type RM Length L Ch R = 1 ,80471   ,459,459,459
BEGIN DESCRIPTION:
SALT BRANCH 126.0
END DESCRIPTION:
XS GIS Cut Line= 3
      2211437.72     13302096.88      2211387.72     13301296.85
      2211237.72     13300896.84
#Sta/Elev= 30
    4190  315.92  4394.5  307.94  4410.5  306.89  4540.7  302.58  4561.9  301.19
  4610.8  299.64  4640.9   299.9    4681  298.95  4781.2  298.74  4908.9  299.27
  4913.9  299.78  4941.5  299.58  4981.6  300.36  4994.3  299.61    4997  298.74
  4999.8  298.24    5003  298.74  5012.9  299.47  5023.6  299.32  5031.6  300.08
  5055.7  300.91  5061.9  301.97  5067.2  301.47  5086.8  302.49  5122.4  303.15
  5147.3  304.58  5162.5  304.61  5193.6  306.16  5226.5  307.96  5418.8  314.12
#Mann= 6 ,-1 , 0
    4190      .1       0  4394.5     .05       0  4561.9      .1       0
    4997     .07       0    5003      .1       0  5193.6     .05       0
Bank Sta=4981.6,5031.6
XS Rating Curve= 0 ,0
Exp/Cntr=0.3,0.1

Type RM Length L Ch R = 1 ,80012   ,507,507,507
BEGIN DESCRIPTION:
SALT BRANCH 125.0
END DESCRIPTION:
XS GIS Cut Line= 3
      2211787.72     13302246.86      2211787.72     13301446.85
      2211487.72     13300796.85
#Sta/Elev= 30
    4177  320.54    4197  320.48  4212.8  319.23    4257  317.01    4427  311.52
    4437  310.33  4559.3  306.09  4710.3  300.19    4757   298.3    4797  297.92
    4807  296.86    4857  296.53  4879.4  297.35    4957  297.85    4967  297.18
  4991.2  297.72    4997  296.53  4999.8  296.03    5003  296.53  5008.7  298.02
  5054.1  297.23  5076.1  297.85  5098.2  297.51    5141  298.65  5292.4  303.45
  5392.3  307.12    5518  310.21  5536.3  309.97  5537.2  309.98  5692.9  312.04
#Mann= 11 ,-1 , 0
    4177     .05       0  4212.8      .1       0  4559.3     .05       0
  4710.3      .1       0  4879.4     .12       0    4997     .07       0
    5003     .12       0    5141      .1       0  5292.4     .05       0
  5536.3      .1       0  5537.2     .05       0
Bank Sta=4991.2,5008.7
XS Rating Curve= 0 ,0
Exp/Cntr=0.3,0.1

Type RM Length L Ch R = 1 ,79505   ,514,514,514
BEGIN DESCRIPTION:
SALT BRANCH 124.0
END DESCRIPTION:
XS GIS Cut Line= 3
      2212137.72     13302346.85      2212187.72     13301546.85
      2212187.72     13300646.81
#Sta/Elev= 30
  4234.6  323.92  4404.9  317.63  4632.9  307.43  4785.7  301.34  4815.7  301.45
  4895.9  297.24  4986.1  295.29    4997  293.89  4999.8  293.39    5003  293.89
  5003.9  293.89  5015.7  294.73  5033.6  295.68  5056.2  296.42  5116.2  295.51
  5206.2  296.72  5286.2  296.55  5366.2  297.11  5386.2  297.88  5436.2   297.4
  5466.2  298.35  5556.2  298.42  5606.2  299.44  5626.2  299.27  5636.2  298.41
  5646.2  299.54  5676.2  300.32  5736.2   300.2  5866.2  304.89  5936.2  311.43
#Mann= 5 ,-1 , 0
  4234.6     .05       0    4997     .03       0    5003     .05       0
  5003.9     .12       0  5015.7      .1       0
Bank Sta=4986.1,5033.6
XS Rating Curve= 0 ,0
Exp/Cntr=0.3,0.1

Type RM Length L Ch R = 1 ,78991   ,453,453,453
BEGIN DESCRIPTION:
SALT BRANCH 123.0
END DESCRIPTION:
XS GIS Cut Line= 3
       2212600.6     13302258.52      2212786.11      13300891.2
      2212634.97     13300417.16
#Sta/Elev= 30
  4382.4  315.06  4434.5  313.67  4787.7  298.75  4858.4  296.92  4959.3  292.91
  4993.9  292.41    4997  290.74  4999.8  290.24    5003  290.74  5009.8  292.53
    5085  293.95  5128.5  293.47  5181.3   292.6  5251.2   292.8  5302.4  292.26
  5332.7  290.74  5342.8   292.7  5413.4  291.61  5463.9  291.54  5504.2  292.69
  5524.4  292.01  5605.2  293.82  5625.3  295.12  5645.5  294.76  5798.3  297.25
  5861.3  299.52    5939  299.64  5987.2  301.72  6132.2  305.51  6259.8  309.87
#Mann= 6 ,-1 , 0
  4382.4     .05       0    4997     .03       0    5003     .05       0
    5085      .1       0  5128.5     .05       0  5251.2      .1       0
Bank Sta=4993.9,5009.8
XS Rating Curve= 0 ,0
Exp/Cntr=0.3,0.1

Type RM Length L Ch R = 1 ,78538   ,254,254,254
BEGIN DESCRIPTION:
SALT BRANCH 122.0
END DESCRIPTION:
XS GIS Cut Line= 3
      2212930.42     13302258.46      2213102.17     13301873.74
       2213212.1     13300465.25
#Sta/Elev= 30
  4450.5  308.87  4653.6  302.85  4723.3  299.49  4728.8  300.64  4746.5  298.77
  4769.7  299.12  4888.8  293.26  4979.7   290.8  4989.1  290.46    4997  288.65
  4999.8  288.15    5003  288.65  5005.7  290.22  5039.2  291.79  5134.7  290.92
  5224.7  290.88  5269.9  289.95    5300  290.97  5340.1  288.65  5400.3  288.67
  5420.4  291.23  5480.6  293.12    5621  296.06  5721.3  296.29  6012.2   302.3
  6036.4   303.1  6042.3  304.28  6082.4  304.13  6232.8   309.9  6284.6  310.32
#Mann= 6 ,-1 , 0
  4450.5     .05       0  4979.7      .1       0    4997     .07       0
    5003      .1       0  5134.7     .05       0  5224.7      .1       0
Bank Sta=4989.1,5005.7
XS Rating Curve= 0 ,0
Exp/Cntr=0.3,0.1

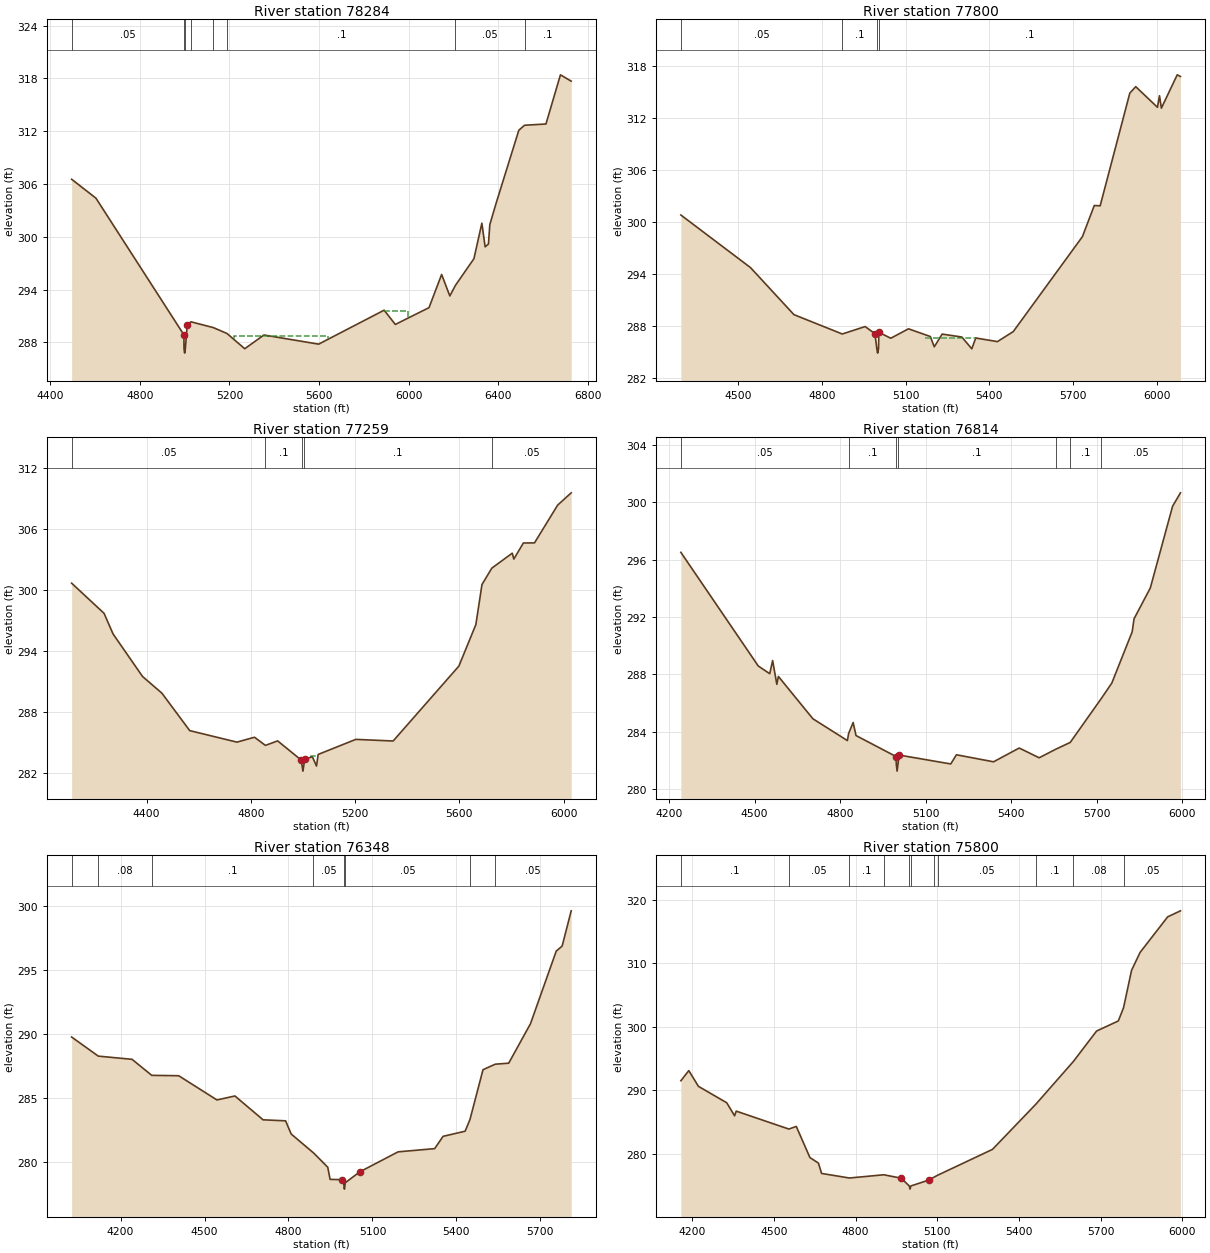
Type RM Length L Ch R = 1 ,78284   ,484,484,484
BEGIN DESCRIPTION:
SALT BRANCH 121.0
END DESCRIPTION:
XS GIS Cut Line= 2
       2213054.1     13302224.12       2214379.8     13300431.33
#Sta/Elev= 30
  4495.5  306.53    4604  304.38  4996.8  288.84    4997  287.27  4999.8  286.77
    5003  287.27  5011.4  289.97  5027.8  290.33  5128.2  289.67    5189     289
  5268.1  287.27  5353.7  288.83    5598  287.79  5890.2  291.65  5940.3  290.03
  6090.6  291.94  6146.9  295.71  6183.5  293.27  6208.7  294.48    6291   297.5
  6326.5  301.54  6341.1  298.85  6355.8  299.17    6362  301.38  6391.2   303.9
  6491.4   312.1    6517  312.67  6612.5  312.81  6677.2   318.4  6725.2  317.68
#Mann= 8 ,-1 , 0
  4495.5     .05       0    4997     .03       0    5003     .05       0
  5027.8      .1       0  5128.2     .05       0    5189      .1       0
  6208.7     .05       0    6517      .1       0
#XS Ineff= 2 ,-1
 5218.12 5638.21  288.67 5889.84 5998.29  291.53
Permanent Ineff=
       F       F
Bank Sta=4996.8,5011.4
XS Rating Curve= 0 ,0
Exp/Cntr=0.3,0.1

Type RM Length L Ch R = 1 ,77800   ,541,541,541
BEGIN DESCRIPTION:
SALT BRANCH 120.0
END DESCRIPTION:
XS GIS Cut Line= 2
      2213294.57     13302395.91      2214599.99     13301172.94
#Sta/Elev= 30
  4295.3   300.8  4544.7  294.72    4700  289.29  4873.2  287.05    4955  287.91
  4990.1  287.09    4997  285.34  4999.8  284.84    5003  285.34  5004.3  287.25
  5046.8  286.56  5110.3  287.65  5188.5  286.76  5202.6  285.57  5230.9  287.04
  5301.3   286.7    5337  285.34  5351.1  286.59  5428.8  286.17  5485.5  287.33
  5733.1   298.3  5775.6   301.9  5796.6  301.86  5902.9  314.89  5924.1  315.63
  6001.8  313.25  6009.1  314.58  6015.9  313.15  6072.6     317  6084.1  316.81
#Mann= 4 ,-1 , 0
  4295.3     .05       0  4873.2      .1       0    4997     .07       0
    5003      .1       0
#XS Ineff= 1 ,-1
 5167.78 5351.78  286.61
Permanent Ineff=
       F
Bank Sta=4990.1,5004.3
XS Rating Curve= 0 ,0
Exp/Cntr=0.3,0.1

Type RM Length L Ch R = 1 ,77259   ,445,445,445
BEGIN DESCRIPTION:
SALT BRANCH 119.0
END DESCRIPTION:
XS GIS Cut Line= 3
      2213445.71     13302498.99      2214758.05     13301866.86
      2214998.52     13301475.25
#Sta/Elev= 30
  4112.8  300.67  4237.1  297.71  4271.7  295.68  4384.8   291.5  4459.1  289.86
  4565.8  286.18  4746.8  285.05  4814.3  285.53    4856  284.73  4903.1  285.17
  4991.9  283.32    4997   282.7  4999.8   282.2    5003   282.7  5006.7  283.37
  5036.3  283.61    5052   282.7  5058.5  283.84  5202.8  285.32    5346  285.16
  5598.1  292.52  5663.3   296.6  5686.8  300.54  5724.6  302.15    5803  303.62
  5808.9  303.04  5845.6  304.62  5888.2  304.63    5977  308.34    6029  309.55
#Mann= 5 ,-1 , 0
  4112.8     .05       0    4856      .1       0    4997     .07       0
    5003      .1       0  5724.6     .05       0
#XS Ineff= 1 ,-1
  5029.5  5059.3  283.72
Permanent Ineff=
       F
Bank Sta=4991.9,5006.7
XS Rating Curve= 0 ,0
Exp/Cntr=0.3,0.1

Type RM Length L Ch R = 1 ,76814   ,466,466,466
BEGIN DESCRIPTION:
Mapping XS 1330979b
END DESCRIPTION:
XS GIS Cut Line= 4
      2213628.65     13302614.69      2214493.23     13302503.58
      2215121.71     13302486.22      2215312.67     13302323.03
#Sta/Elev= 30
  4241.7  296.51    4513  288.59  4553.3  288.05  4563.4  288.97  4578.1  287.31
  4583.6  287.86  4704.6  284.91  4825.5  283.39    4830  283.89  4845.7  284.65
  4855.8  283.74  4996.9  282.27    4997  281.76  4999.8  281.26    5003  281.76
    5007  282.38  5187.9  281.76  5207.9   282.4    5338  281.91    5428  282.87
    5498  282.19  5555.5  282.78  5606.8  283.26  5716.1  286.33  5752.7   287.4
  5824.1  290.97  5830.7  291.88  5887.7  294.03  5965.7  299.72  5993.3  300.66
#Mann= 7 ,-1 , 0
  4241.7     .05       0    4830      .1       0    4997     .07       0
    5003      .1       0  5555.5     .05       0  5606.8      .1       0
  5716.1     .05       0
Bank Sta=4996.9,5007
XS Rating Curve= 0 ,0
Exp/Cntr=0.3,0.1

Type RM Length L Ch R = 1 ,76348   ,548,548,548
BEGIN DESCRIPTION:
Mapping XS bd6b7ff5
END DESCRIPTION:
XS GIS Cut Line= 3
      2213737.11     13302823.03      2215106.95     13302687.61
      2215403.27     13302406.88
#Sta/Elev= 30
  4025.3  289.78  4120.5  288.29  4241.2  288.04  4311.4  286.79  4407.8  286.76
  4544.4  284.87  4608.7  285.18  4709.2  283.32  4789.6  283.24  4809.7  282.21
  4889.3  280.74  4940.3  279.62  4948.7  278.67  4990.6  278.65    4997  278.41
  4999.8  277.91    5003  278.41  5054.8  279.26  5191.6  280.82  5322.2  281.07
  5352.3  282.03    5431  282.43  5448.2  283.33  5494.9  287.23  5538.7  287.66
  5586.8  287.74  5664.6  290.82  5756.6  296.49  5777.7  296.88    5810  299.63
#Mann= 8 ,-1 , 0
  4025.3      .1       0  4120.5     .08       0  4311.4      .1       0
  4889.3     .05       0    4997     .04       0    5003     .05       0
  5448.2      .1       0  5538.7     .05       0
Bank Sta=4990.6,5054.8
XS Rating Curve= 0 ,0
Exp/Cntr=0.3,0.1

Type RM Length L Ch R = 1 ,75800   ,241,241,241
BEGIN DESCRIPTION:
SALT BRANCH 116.0
END DESCRIPTION:
XS GIS Cut Line= 2
      2214352.68     13303502.13       2215932.8     13302567.79
#Sta/Elev= 30
  4157.8  291.54  4186.9  293.13  4222.4  290.65  4326.3  288.07  4355.1  286.02
  4361.2  286.75  4554.5  283.93  4581.9  284.34    4632  279.44  4663.2  278.57
  4674.9  276.94  4776.9  276.22  4903.7  276.73  4967.5  276.19    4997  274.97
  4999.8  274.47    5003  274.97  5069.8  275.91  5089.1  276.38    5102  276.67
  5302.9  280.73  5462.4  287.85  5599.9  294.56  5685.3  299.36  5765.2  300.95
  5784.5  303.04  5813.9  308.92  5845.2  311.74  5946.6  317.34  5993.5  318.29
#Mann= 11 ,-1 , 0
  4157.8      .1       0  4554.5     .05       0  4776.9      .1       0
  4903.7     .05       0    4997     .03       0    5003     .05       0
  5089.1      .1       0    5102     .05       0  5462.4      .1       0
  5599.9     .08       0  5784.5     .05       0
Bank Sta=4967.5,5069.8
XS Rating Curve= 0 ,0
Exp/Cntr=0.3,0.1

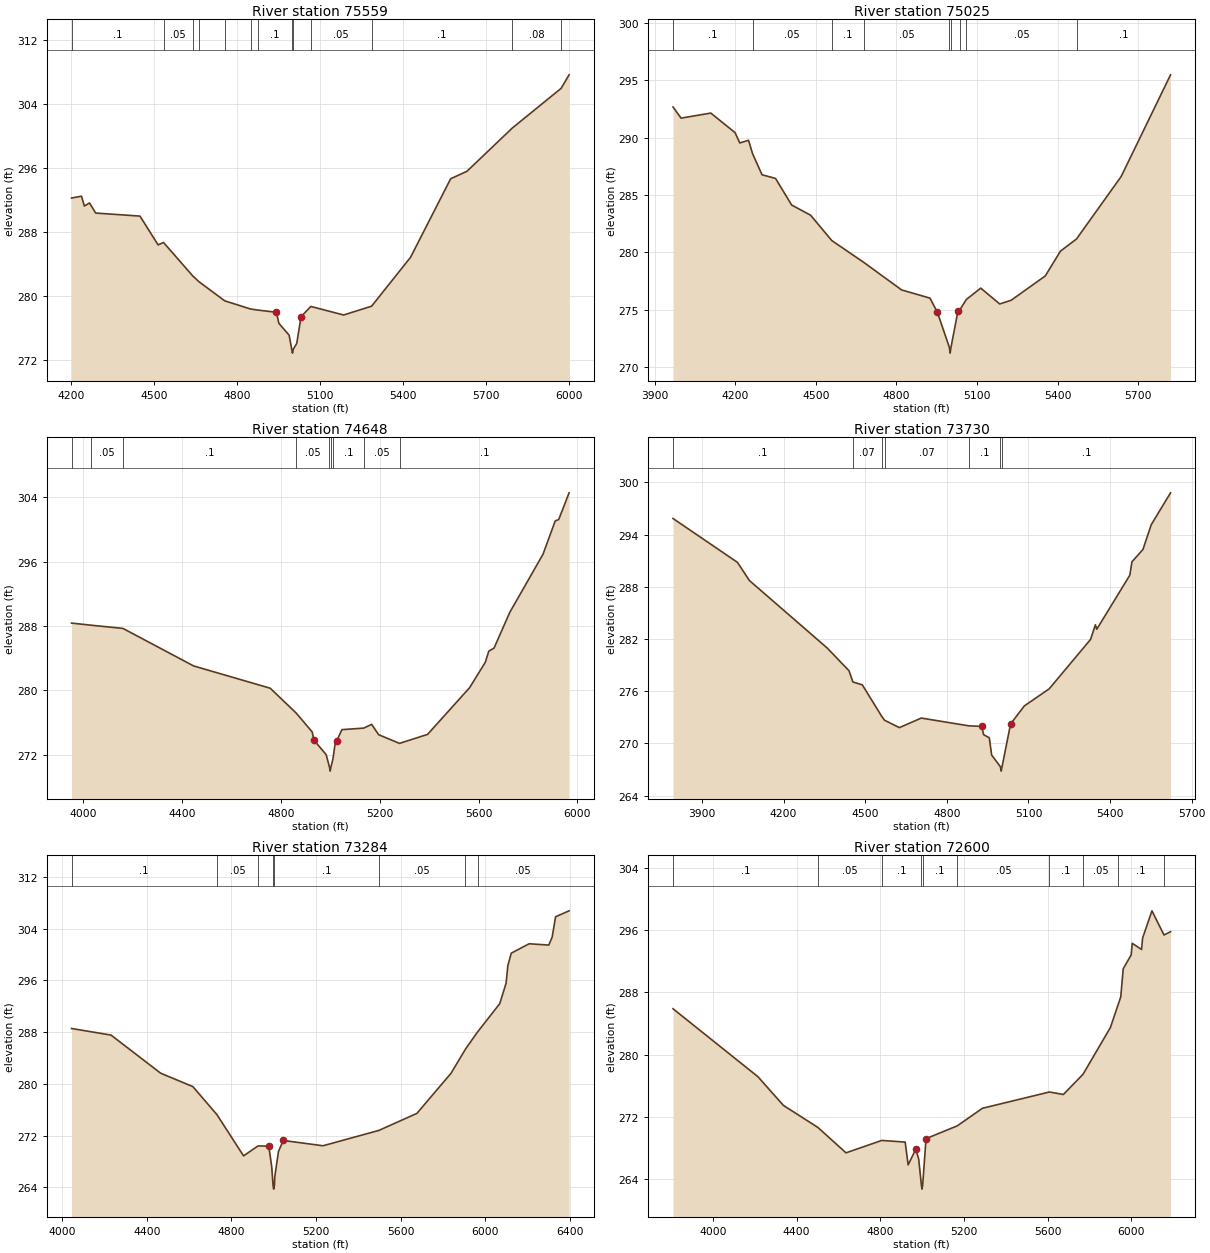
Type RM Length L Ch R = 1 ,75559   ,534,534,534
BEGIN DESCRIPTION:
SALT BRANCH 115.0
END DESCRIPTION:
XS GIS Cut Line= 3
      2214462.57     13303557.11      2214854.24     13303467.78
      2216063.16     13302767.15
#Sta/Elev= 30
    4201  292.24  4237.1  292.47  4247.3  291.24  4266.1  291.62  4288.3  290.36
  4448.4  289.98    4514  286.38  4533.6  286.68  4639.5  282.49  4661.1  281.79
    4755  279.38  4848.3  278.36  4873.5  278.23  4941.9  277.95  4950.6  276.57
  4987.9  275.08    4997  273.34  4999.8  272.84    5003  273.34  5015.2  274.05
    5031   277.4  5066.3  278.68  5184.7  277.61  5285.9  278.71  5426.9  284.83
  5571.8  294.65  5630.6  295.58  5794.6  300.99  5971.3  305.96    6000  307.65
#Mann= 13 ,-1 , 0
    4201      .1       0  4533.6     .05       0  4639.5      .1       0
  4661.1     .05       0    4755      .1       0  4848.3     .05       0
  4873.5      .1       0    4997     .07       0    5003      .1       0
  5066.3     .05       0  5285.9      .1       0  5794.6     .08       0
  5971.3     .05       0
Bank Sta=4941.9,5031
XS Rating Curve= 0 ,0
Exp/Cntr=0.3,0.1

Type RM Length L Ch R = 1 ,75025   ,377,377,377
BEGIN DESCRIPTION:
SALT BRANCH 114.0
END DESCRIPTION:
XS GIS Cut Line= 3
      2214487.75     13303596.86      2215487.72     13303696.85
      2216087.73     13303096.85
#Sta/Elev= 30
  3967.5  292.66  3997.6  291.69  4108.2  292.13  4198.6  290.43  4216.2  289.53
  4248.9  289.76  4263.8   288.6  4299.1  286.76  4349.4  286.44  4409.7  284.12
    4480  283.24    4559  281.03  4679.5  279.11  4819.2  276.73  4924.7  276.02
  4952.4  274.79    4997  271.73  4999.8  271.23    5003  271.73    5029  274.89
  5037.7  275.06  5060.1   275.9  5113.9  276.89  5184.6  275.51    5227  275.83
  5354.3  277.95  5410.9  280.11  5470.7  281.17  5637.1  286.61    5821  295.46
#Mann= 9 ,-1 , 0
  3967.5      .1       0  4263.8     .05       0    4559      .1       0
  4679.5     .05       0    4997     .03       0    5003     .05       0
  5037.7      .1       0  5060.1     .05       0  5470.7      .1       0
Bank Sta=4952.4,5029
XS Rating Curve= 0 ,0
Exp/Cntr=0.3,0.1

Type RM Length L Ch R = 1 ,74648   ,918,918,918
BEGIN DESCRIPTION:
SALT BRANCH 113.0
END DESCRIPTION:
XS GIS Cut Line= 3
      2214854.22     13304161.73      2215472.62     13304237.31
      2216461.92     13303261.75
#Sta/Elev= 30
  3953.8  288.37  4032.1  288.11  4161.5  287.71  4447.7  283.04  4757.5  280.27
  4863.1  277.16  4927.2  274.83  4934.3  273.81  4983.8  272.01    4997  270.46
  4999.8  269.96    5003  270.46  5011.1  271.47  5019.2  273.22  5026.2   273.7
  5047.4  275.12  5135.8  275.31  5167.6  275.78  5195.9  274.49  5280.3  273.41
  5393.9  274.53  5563.7  280.33  5627.3  283.49  5641.4  284.88  5662.7  285.26
  5726.3   289.7  5860.7  296.93  5910.1  301.07  5924.3  301.25  5966.2  304.57
#Mann= 9 ,-1 , 0
  3953.8      .1       0  4032.1     .05       0  4161.5      .1       0
  4863.1     .05       0    4997     .03       0    5003     .05       0
  5011.1      .1       0  5135.8     .05       0  5280.3      .1       0
Bank Sta=4934.3,5026.2
XS Rating Curve= 0 ,0
Exp/Cntr=0.3,0.1

Type RM Length L Ch R = 1 ,73730   ,446,446,446
BEGIN DESCRIPTION:
SALT BRANCH 112.0
END DESCRIPTION:
XS GIS Cut Line= 3
       2215787.7     13304996.88      2216487.72     13303996.85
      2216587.73     13303396.82
#Sta/Elev= 30
  3793.4  295.85  4030.2  290.81  4074.2  288.72  4360.6  280.95  4440.4  278.35
  4454.6  277.06  4489.2  276.73    4560  273.14    4571  272.66  4625.7  271.81
  4705.9  272.91  4880.1  272.02  4928.6  271.95  4935.2     271  4956.1  270.64
  4964.8  268.66    4997  267.31  4999.8  266.81    5003  267.31  5034.4  272.24
  5085.1  274.31  5176.3  276.27  5328.4  281.95  5346.1  283.63  5351.2  283.12
  5472.8  289.34  5480.4  290.87    5521  292.29  5551.4  295.14  5622.4   298.8
#Mann= 7 ,-1 , 0
  3793.4      .1       0  4454.6     .07       0    4560      .1       0
    4571     .07       0  4880.1      .1       0    4997     .07       0
    5003      .1       0
Bank Sta=4928.6,5034.4
XS Rating Curve= 0 ,0
Exp/Cntr=0.3,0.1

Type RM Length L Ch R = 1 ,73284   ,684,684,684
BEGIN DESCRIPTION:
SALT BRANCH 111.0
END DESCRIPTION:
XS GIS Cut Line= 4
      2216207.83     13304999.96      2216647.54     13304635.82
      2217107.89     13303660.16      2216853.67     13303007.45
#Sta/Elev= 30
  4044.9  288.56  4231.6  287.54    4466  281.65    4618  279.58  4731.7  275.25
  4857.4  268.88  4925.8  270.41  4976.8  270.39  4990.6  267.13    4997  264.24
  4999.8  263.74    5003  264.24  5005.1   265.7  5022.3  269.55  5045.1  271.26
  5232.8  270.44  5496.5  272.81  5676.2  275.44  5837.7  281.65  5905.3  285.35
  5962.7  288.02  6067.7   292.4  6097.6  295.57    6106   298.3  6122.1   300.2
  6206.4  301.65  6299.2  301.45  6315.2  302.68  6331.3  305.82  6395.1  306.74
#Mann= 8 ,-1 , 0
  4044.9      .1       0  4731.7     .05       0  4925.8      .1       0
    4997     .07       0    5003      .1       0  5496.5     .05       0
  5905.3      .1       0  5962.7     .05       0
Bank Sta=4976.8,5045.1
XS Rating Curve= 0 ,0
Exp/Cntr=0.3,0.1

Type RM Length L Ch R = 1 ,72600   ,559,559,559
BEGIN DESCRIPTION:
SALT BRANCH 110.0
END DESCRIPTION:
XS GIS Cut Line= 4
      2216468.88     13304965.63       2216963.6     13304745.76
      2217602.59     13304010.57      2217781.22      13303165.5
#Sta/Elev= 30
  3809.2  285.88  4215.4  277.15  4337.1  273.47    4502  270.64  4636.4  267.38
  4807.2  268.97  4919.4  268.76  4933.6  265.83  4969.7  267.82    4984   266.6
    4997  263.22  4999.8  262.72    5003  263.22  5019.1   269.2    5169  270.85
  5288.8   273.1  5609.2  275.19    5676  274.87  5769.9  277.47  5900.6  283.46
  5939.2  286.52  5950.3   287.4  5962.2  291.02  6000.1  292.79  6005.2  294.28
  6049.8  293.49  6054.9  294.97  6099.5  298.45    6157  295.35  6188.4  295.77
#Mann= 10 ,-1 , 0
  3809.2      .1       0    4502     .05       0  4807.2      .1       0
    4997     .07       0    5003      .1       0    5169     .05       0
  5609.2      .1       0  5769.9     .05       0  5939.2      .1       0
    6157     .05       0
Bank Sta=4969.7,5019.1
XS Rating Curve= 0 ,0
Exp/Cntr=0.3,0.1