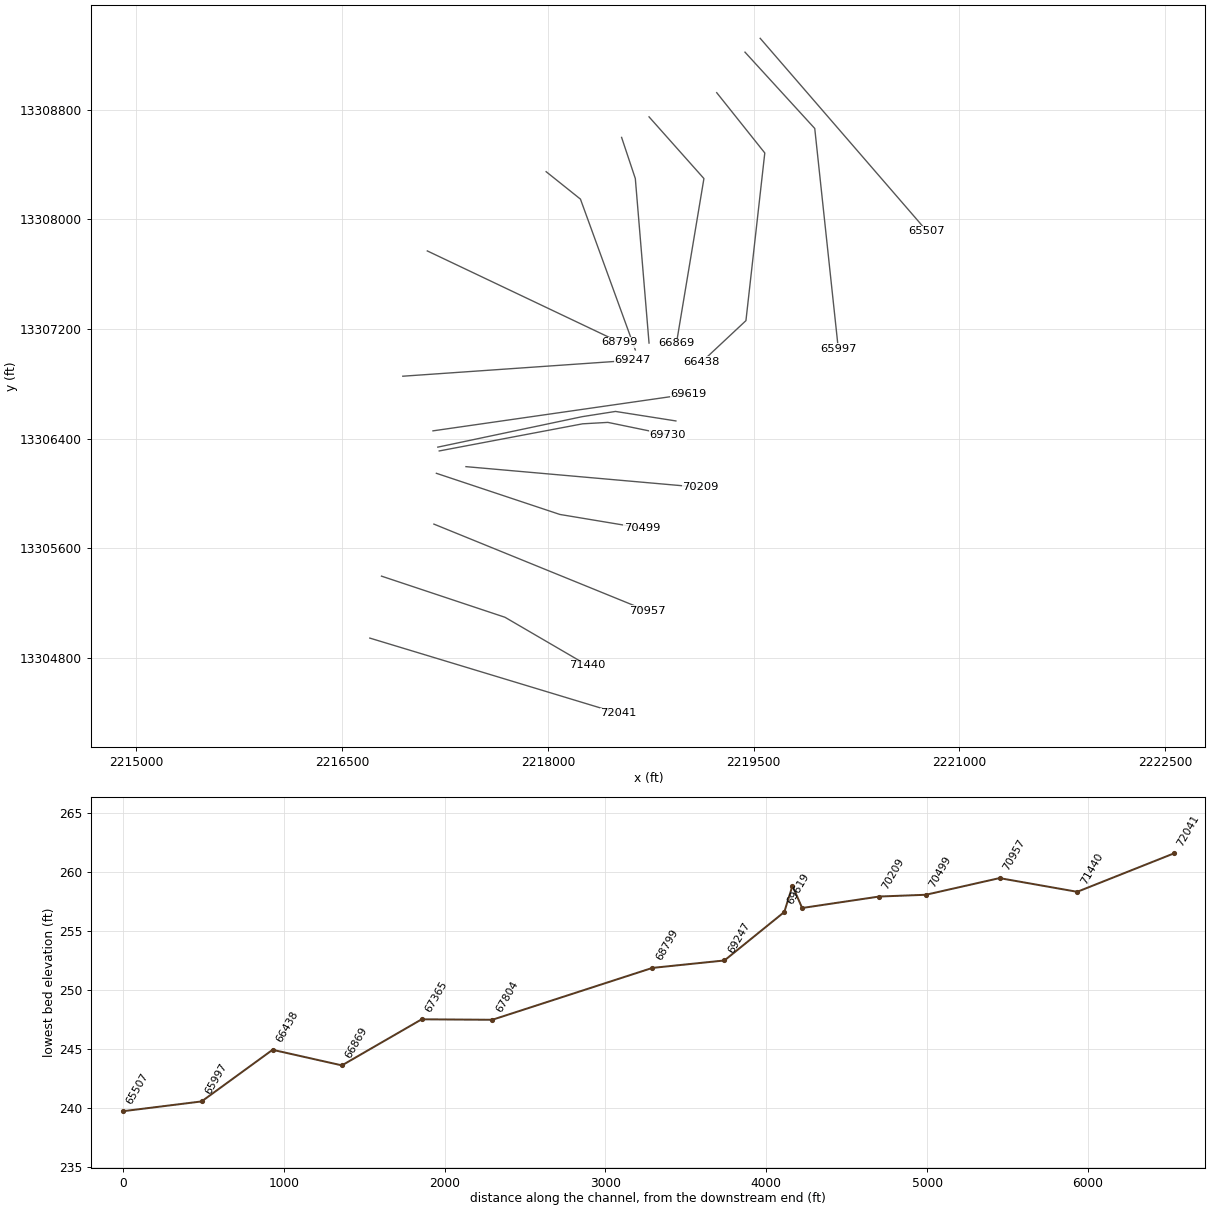
HEC-RAS study SALT BRANCH.prj: SALT BRANCH Base Level Engineering

--- SALT BRANCH.g01 (geometry) --- (continued)

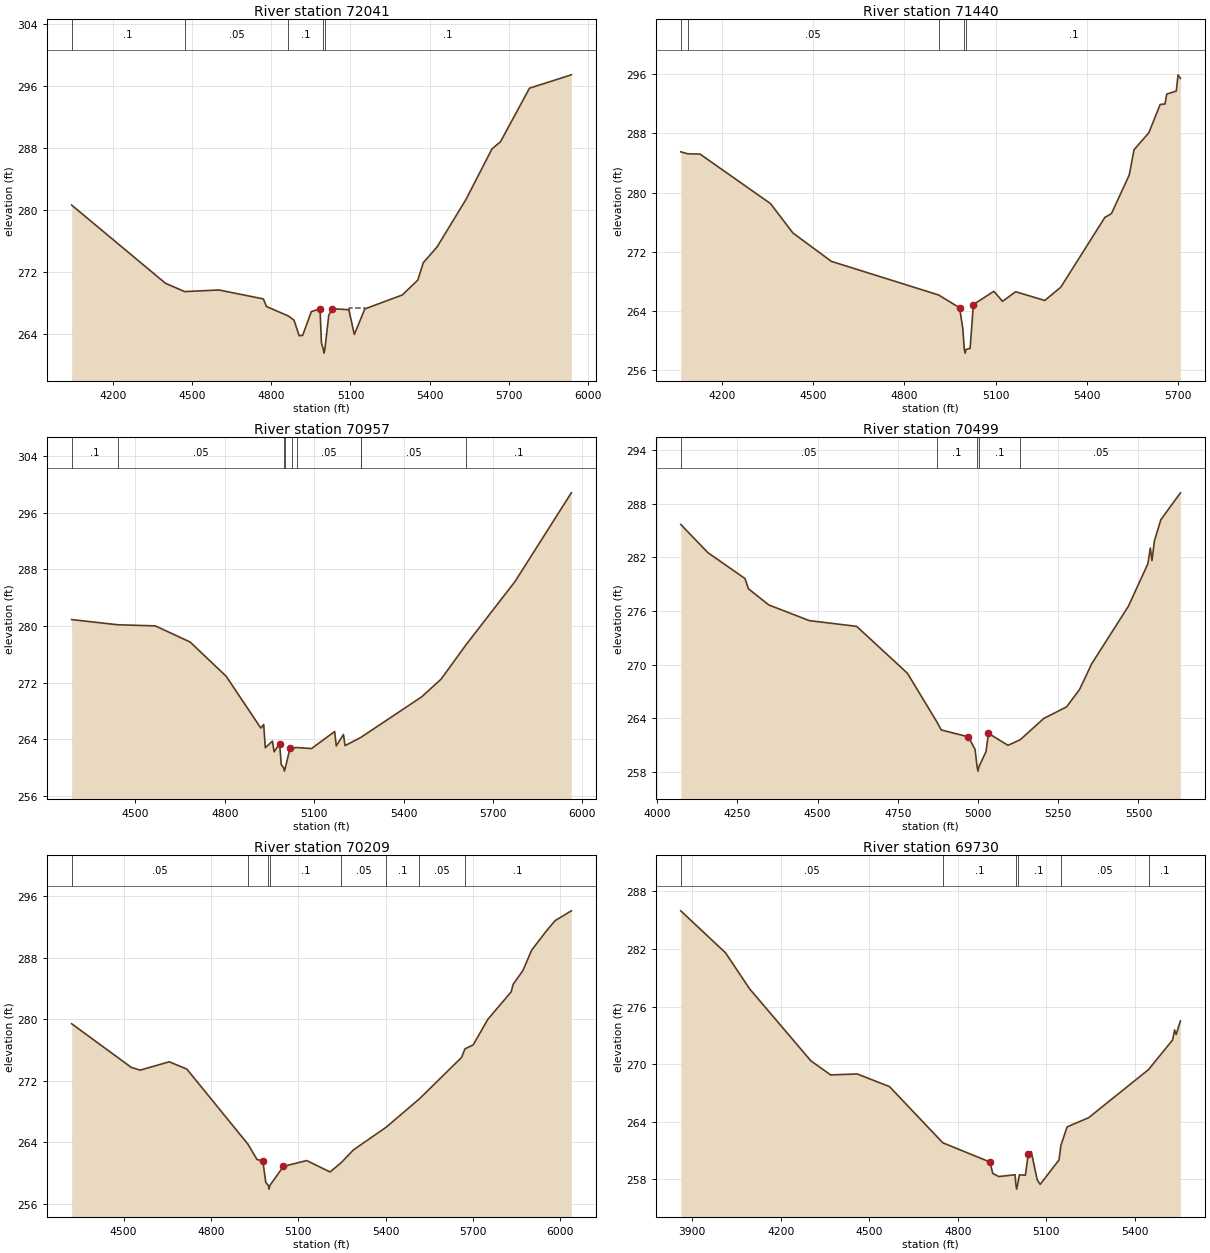
Type RM Length L Ch R = 1 ,72041   ,601,601,601
BEGIN DESCRIPTION:
SALT BRANCH 109.0
END DESCRIPTION:
XS GIS Cut Line= 2
      2216702.52     13304945.01      2218514.55     13304395.91
#Sta/Elev= 30
  4043.5  280.64  4399.1  270.57  4471.9   269.5  4601.8  269.71  4769.9  268.56
    4782  267.58  4865.2  266.35    4886  265.83  4905.8  263.82  4918.9  263.87
  4951.8  266.93  4984.8  267.27    4990  262.92    4997  262.08  4999.8  261.58
    5003  262.08  5017.7  266.44  5031.1   267.3  5093.9  267.17  5114.7  263.98
  5154.5  267.27  5296.7  269.07  5355.1  270.98    5376  273.22  5428.2  275.25
  5537.5  281.35  5636.2  287.87  5668.5  288.79  5778.4  295.69  5936.9  297.41
#Mann= 5 ,-1 , 0
  4043.5      .1       0  4471.9     .05       0  4865.2      .1       0
    4997     .07       0    5003      .1       0
#XS Ineff= 1 ,-1
 5093.75 5154.69  267.43
Permanent Ineff=
       F
Bank Sta=4984.8,5031.1
XS Rating Curve= 0 ,0
Exp/Cntr=0.3,0.1

Type RM Length L Ch R = 1 ,71440   ,483,483,483
BEGIN DESCRIPTION:
SALT BRANCH 108.0
END DESCRIPTION:
XS GIS Cut Line= 3
      2216787.71     13305396.86      2217687.72     13305096.85
      2218287.71     13304746.86
#Sta/Elev= 30
  4064.5  285.51  4087.3  285.25  4127.8  285.21  4359.7  278.52  4433.4  274.55
  4559.9  270.72  4912.7  266.18  4981.6  264.45  4992.1  261.65    4997  258.83
  4999.8  258.33    5003  258.83  5016.1  258.97  5026.8  264.89  5094.2  266.68
  5122.8  265.33  5165.8  266.62  5261.7  265.44  5314.2  267.23  5459.3  276.66
  5480.8  277.16  5539.5  282.39  5555.2   285.8    5604  288.09  5641.2  291.91
    5657  291.97  5662.7  293.31  5694.2  293.72    5700  295.91  5707.8  295.42
#Mann= 5 ,-1 , 0
  4064.5      .1       0  4087.3     .05       0  4912.7      .1       0
    4997     .07       0    5003      .1       0
Bank Sta=4981.6,5026.8
XS Rating Curve= 0 ,0
Exp/Cntr=0.3,0.1

Type RM Length L Ch R = 1 ,70957   ,458,458,458
BEGIN DESCRIPTION:
SALT BRANCH 107.0
END DESCRIPTION:
XS GIS Cut Line= 2
       2217169.7      13305776.4      2218722.57     13305144.26
#Sta/Elev= 30
  4285.9  280.89  4440.3  280.16  4566.5     280  4683.2  277.73  4804.6  272.88
  4920.8  265.56  4930.3  266.07  4935.7   262.8  4959.8  263.73  4965.2  262.22
  4983.8  263.37  4989.2   260.4    4997  259.99  4999.8  259.49    5003  259.99
  5018.7  262.72  5024.4  262.76  5041.2  262.82  5090.9  262.68  5168.4  265.08
  5173.8  263.05  5197.9  264.66  5203.3  263.09  5255.8  264.24  5256.6  264.26
  5460.1  269.97  5525.4  272.47  5609.2  277.33  5773.7  286.27  5962.5  298.79
#Mann= 9 ,-1 , 0
  4285.9      .1       0  4440.3     .05       0    4997     .03       0
    5003     .05       0  5024.4      .1       0  5041.2     .05       0
  5255.8      .1       0  5256.6     .05       0  5609.2      .1       0
Bank Sta=4983.8,5018.7
XS Rating Curve= 0 ,0
Exp/Cntr=0.3,0.1

Type RM Length L Ch R = 1 ,70499   ,290,290,290
BEGIN DESCRIPTION:
SALT BRANCH 106.0
END DESCRIPTION:
XS GIS Cut Line= 3
       2217187.7     13306146.86      2218087.72     13305846.85
      2218687.74     13305746.85
#Sta/Elev= 30
  4073.7   285.7    4158  282.55    4274  279.64  4284.5   278.5  4347.8  276.69
  4474.3  274.93  4621.8  274.29    4780  269.04  4872.8  263.53  4885.4  262.69
  4969.7  261.92  4990.8  260.51    4997  258.58  4999.8  258.08    5003  258.58
  5024.9  260.27  5032.5  262.31  5093.4  260.97  5131.6   261.6  5204.9  263.98
  5275.8  265.27  5316.4  267.22  5354.4  270.11  5468.5  276.54  5529.3   281.3
  5536.9  283.07    5542  281.65  5549.6  283.86  5569.8  286.24  5630.7  289.24
#Mann= 5 ,-1 , 0
  4073.7     .05       0  4872.8      .1       0    4997     .07       0
    5003      .1       0  5131.6     .05       0
Bank Sta=4969.7,5032.5
XS Rating Curve= 0 ,0
Exp/Cntr=0.3,0.1

Type RM Length L Ch R = 1 ,70209   ,479,479,479
BEGIN DESCRIPTION:
SALT BRANCH 105.0
END DESCRIPTION:
XS GIS Cut Line= 2
      2217403.34     13306195.51      2219113.48     13306044.41
#Sta/Elev= 30
  4321.6   279.4  4526.8  273.73  4556.9  273.38  4657.3  274.46  4717.5  273.51
  4927.3  263.77  4958.5  261.78  4978.5  261.58  4988.6  258.81    4997  258.43
  4999.8  257.93    5003  258.43  5049.3  260.88  5129.1  261.64  5209.4  260.16
  5246.5  261.32  5289.7  263.02  5402.3  265.97  5516.4  269.65  5661.2  275.02
    5673  276.14  5701.3  276.66  5751.5  279.97  5831.8  283.54  5838.5  284.52
    5872   286.3  5902.1  288.95  5950.6  291.34  5982.4  292.78  6038.4  294.06
#Mann= 8 ,-1 , 0
  4321.6     .05       0  4927.3      .1       0    4997     .07       0
    5003      .1       0  5246.5     .05       0  5402.3      .1       0
  5516.4     .05       0    5673      .1       0
Bank Sta=4978.5,5049.3
XS Rating Curve= 0 ,0
Exp/Cntr=0.3,0.1

Type RM Length L Ch R = 1 ,69730   ,60,60,60
BEGIN DESCRIPTION:
Mapping XS 65cd8999
END DESCRIPTION:
XS GIS Cut Line= 4
      2217208.56     13306310.01      2218253.65     13306507.92
      2218437.68     13306518.34       2218873.9     13306428.32
#Sta/Elev= 30
  3861.4  285.98  4013.2   281.6  4094.6  277.85  4302.3  270.34  4369.4  268.87
  4459.2  268.97  4568.9  267.65  4749.5  261.79  4908.9  259.79    4919  258.59
  4939.2  258.27  4994.5  258.46    4997  257.46  4999.8  256.96    5003  257.46
  5009.3  258.45  5029.3  258.41  5039.3  260.67  5049.3  260.87  5069.4  257.93
  5079.4  257.46  5143.3     260  5149.5   261.5  5170.7  263.45  5243.8  264.41
  5446.8  269.43  5528.1  272.51  5535.2  273.56  5540.3  273.08  5554.8   274.5
#Mann= 6 ,-1 , 0
  3861.4     .05       0  4749.5      .1       0    4997     .07       0
    5003      .1       0  5149.5     .05       0  5446.8      .1       0
Bank Sta=4908.9,5039.3
XS Rating Curve= 0 ,0
Exp/Cntr=0.3,0.1

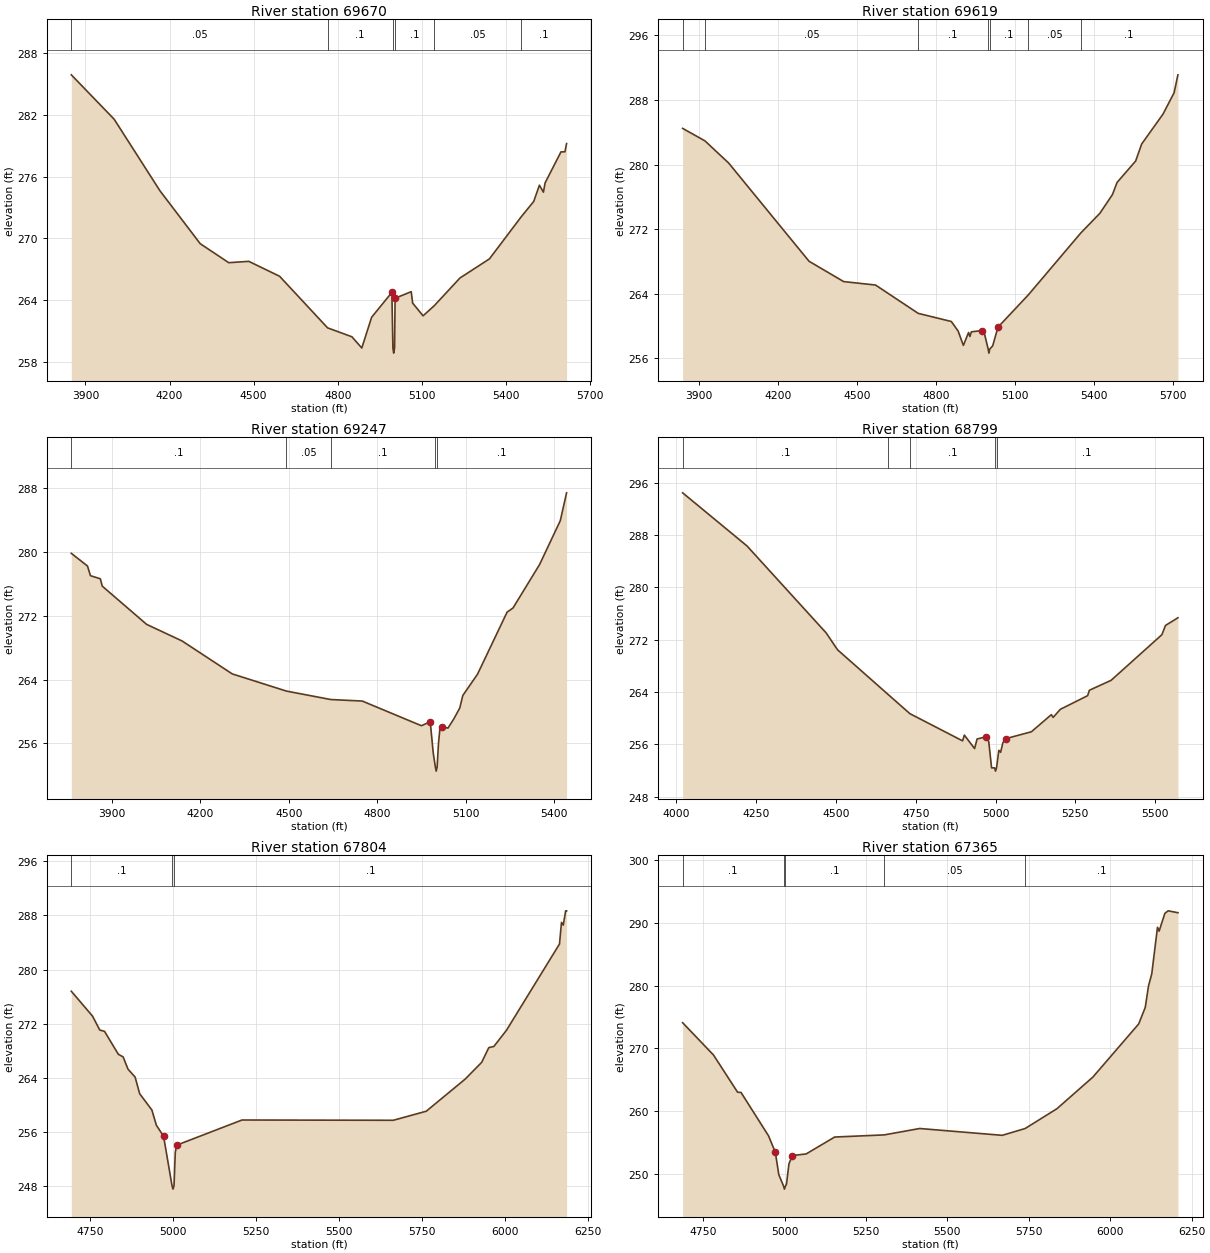
Type RM Length L Ch R = 1 ,69670   ,51,51,51
BEGIN DESCRIPTION:
Mapping XS 9d2ba926
END DESCRIPTION:
XS GIS Cut Line= 4
       2217198.1     13306337.78      2218250.18       13306560.
      2218493.23      13306598.2      2218933.48     13306528.87
#Sta/Elev= 30
  3849.6  285.92  4002.5   281.6  4166.1  274.63  4309.5  269.49  4411.3  267.64
  4482.9  267.77  4592.7  266.32  4763.9   261.3  4850.8  260.43    4886  259.34
  4921.1  262.33  4993.3  264.75    4997  259.34  4999.8  258.84    5003  259.34
  5004.8  264.18  5062.4  264.82  5067.4  263.71  5104.6  262.47  5145.1  263.47
  5236.2  266.15  5341.4  268.01  5454.4  272.09  5499.4   273.6  5519.7  275.18
    5534   274.5  5539.9   275.4  5596.5  278.42  5610.8  278.43  5616.6  279.23
#Mann= 6 ,-1 , 0
  3849.6     .05       0  4763.9      .1       0    4997     .07       0
    5003      .1       0  5145.1     .05       0  5454.4      .1       0
Bank Sta=4993.3,5004.8
XS Rating Curve= 0 ,0
Exp/Cntr=0.3,0.1

Type RM Length L Ch R = 1 ,69619   ,372,372,372
BEGIN DESCRIPTION:
SALT BRANCH 104.0
END DESCRIPTION:
XS GIS Cut Line= 2
      2217162.84      13306456.6      2219023.77     13306724.41
#Sta/Elev= 30
  3837.2  284.48    3922  282.93  4011.7  280.19    4317  268.01  4448.3  265.49
  4569.5  265.06  4731.4  261.55  4857.2  260.54  4882.7  259.37  4902.9  257.58
  4922.6  259.18  4927.7  258.68  4933.3  259.26  4973.7  259.42  4983.8  258.91
    4997  257.12  4999.8  256.62    5003  257.12  5014.1  257.52  5034.3  259.84
    5150  263.86  5347.7  271.48  5420.9  273.95  5468.7  276.27  5486.3  277.78
  5556.8  280.43  5579.8  282.55  5660.7  286.25  5702.8   288.9  5717.3  291.12
#Mann= 7 ,-1 , 0
  3837.2      .1       0    3922     .05       0  4731.4      .1       0
    4997     .07       0    5003      .1       0    5150     .05       0
  5347.7      .1       0
Bank Sta=4973.7,5034.3
XS Rating Curve= 0 ,0
Exp/Cntr=0.3,0.1

Type RM Length L Ch R = 1 ,69247   ,448,448,448
BEGIN DESCRIPTION:
SALT BRANCH 103.0
END DESCRIPTION:
XS GIS Cut Line= 2
      2216942.97     13306855.11      2218619.01     13306971.88
#Sta/Elev= 30
    3762  279.81  3816.9  278.22  3826.9  277.01  3860.5  276.62    3867   275.7
  4017.4  270.91  4137.7  268.83  4308.1   264.7  4491.7  262.55  4642.4  261.49
  4749.1   261.3  4949.6  258.21  4979.7   258.7  4989.7  254.82    4997  253.02
  4999.8  252.52    5003  253.02  5007.4   255.9  5012.4  257.85  5019.8  258.11
  5039.8  257.91  5059.9  259.08  5079.9  260.44    5090  261.99  5140.1  264.67
  5240.3  272.44  5260.4  272.96  5350.6  278.41  5420.8   283.9  5442.1  287.39
#Mann= 5 ,-1 , 0
    3762      .1       0  4491.7     .05       0  4642.4      .1       0
    4997     .07       0    5003      .1       0
Bank Sta=4979.7,5019.8
XS Rating Curve= 0 ,0
Exp/Cntr=0.3,0.1

Type RM Length L Ch R = 1 ,68799   ,995,995,995
BEGIN DESCRIPTION:
SALT BRANCH 102.0
END DESCRIPTION:
XS GIS Cut Line= 2
      2217121.63     13307768.93      2218522.98     13307102.61
#Sta/Elev= 30
  4019.6  294.46  4221.3  286.33  4469.3  273.03  4504.9  270.45  4664.2  263.58
  4731.6  260.68  4896.6  256.52  4902.2   257.4  4934.3  255.34  4942.1  256.81
  4970.3  257.14  4978.6  256.42  4987.5  252.39    4997  252.39  4999.8  251.89
    5003  252.39  5010.2  255.07  5015.8  254.77  5022.9  256.23  5032.9  256.87
  5112.2  257.91  5174.8  260.53  5180.3  260.11    5203  261.35  5288.4  263.43
  5293.9  264.26    5362  265.78  5521.1  272.76  5532.3  274.17  5571.3  275.35
#Mann= 5 ,-1 , 0
  4019.6      .1       0  4664.2     .05       0  4731.6      .1       0
    4997     .07       0    5003      .1       0
Bank Sta=4970.3,5032.9
XS Rating Curve= 0 ,0
Exp/Cntr=0.3,0.1

Type RM Length L Ch R = 1 ,67804   ,439,439,439
BEGIN DESCRIPTION:
SALT BRANCH 101.0
END DESCRIPTION:
XS GIS Cut Line= 3
      2217987.74     13308346.84      2218237.72     13308146.85
      2218637.72     13307046.85
#Sta/Elev= 30
  4693.8  276.79  4757.8   273.1  4779.4  271.05  4793.8  270.85  4835.4  267.46
  4849.8  267.07  4864.3  265.27  4885.9  264.08  4899.5  261.63  4936.3  259.21
  4949.9  256.95  4971.5  255.33    4997     248  4999.8   247.5    5003     248
  5006.7   252.9  5010.7     254  5207.5  257.73    5663  257.69  5762.1  259.03
  5879.1  263.78    5929  266.27  5950.3  268.44  5965.6  268.62  6003.5  271.01
  6163.1  283.78  6169.1  286.98  6174.4  286.58  6181.7  288.69  6184.4  288.69
#Mann= 3 ,-1 , 0
  4693.8      .1       0    4997     .07       0    5003      .1       0
Bank Sta=4971.5,5010.7
XS Rating Curve= 0 ,0
Exp/Cntr=0.3,0.1

Type RM Length L Ch R = 1 ,67365   ,496,496,496
BEGIN DESCRIPTION:
SALT BRANCH 100.0
END DESCRIPTION:
XS GIS Cut Line= 3
      2218537.71     13308596.89      2218637.72     13308296.85
      2218737.72     13307096.88
#Sta/Elev= 30
  4687.3  274.08  4782.2  268.92    4856     263  4866.5  262.96  4950.9  256.05
  4971.9   253.4  4982.5  249.84    4997  248.04  4999.8  247.54    5003  248.04
  5006.1  248.34  5013.6  251.56  5023.6  252.89  5066.3  253.15  5154.1  255.85
  5306.2  256.19    5415  257.21  5668.4  256.12  5738.8  257.21  5836.4  260.37
  5946.8  265.42  6087.3  273.89  6107.4  276.52  6117.4  279.95  6127.4  281.88
    6145  289.31    6150  288.69  6167.6  291.52  6177.6  291.93  6207.7  291.63
#Mann= 5 ,-1 , 0
  4687.3      .1       0    4997     .07       0    5003      .1       0
  5306.2     .05       0  5738.8      .1       0
Bank Sta=4971.9,5023.6
XS Rating Curve= 0 ,0
Exp/Cntr=0.3,0.1

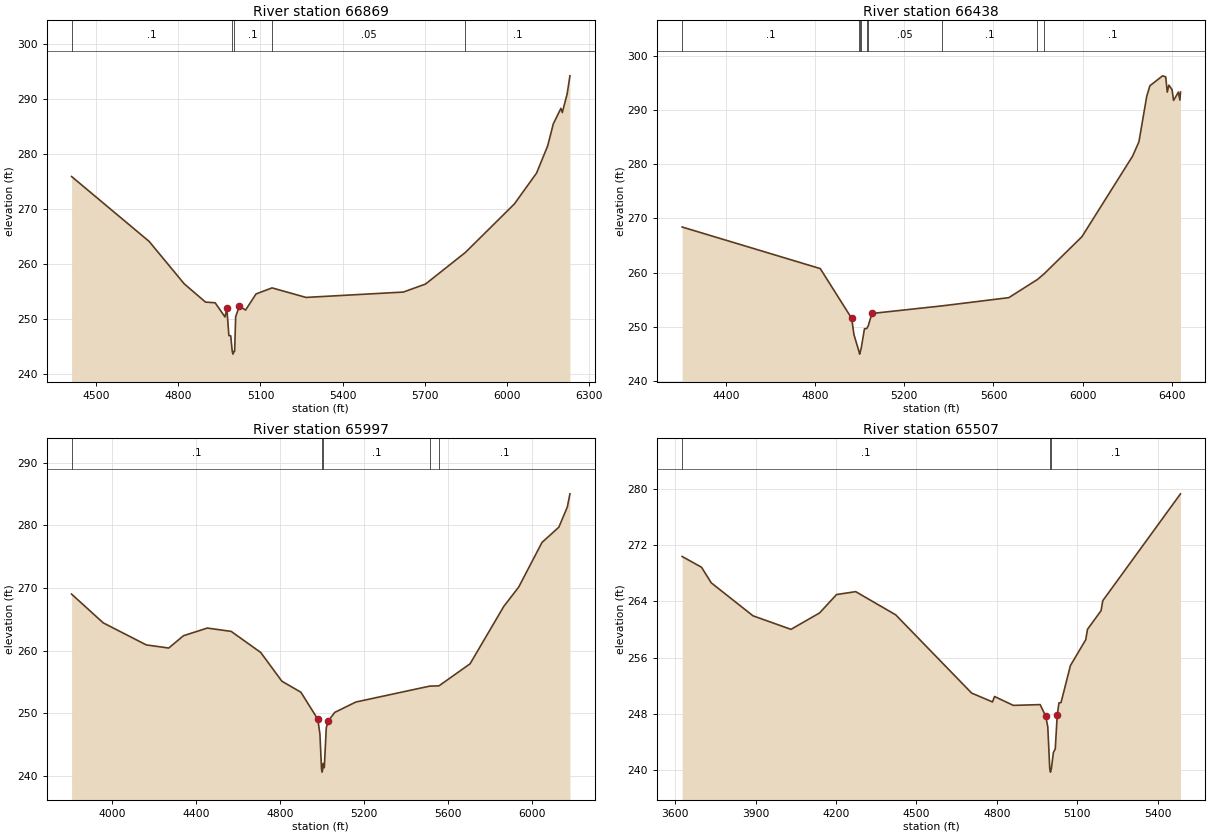
Type RM Length L Ch R = 1 ,66869   ,431,431,431
BEGIN DESCRIPTION:
SALT BRANCH 99.0
END DESCRIPTION:
XS GIS Cut Line= 3
      2218737.71     13308746.87      2219137.72     13308296.85
      2218937.71     13307096.81
#Sta/Elev= 30
  4410.7  275.87  4693.8  264.09  4821.7   256.4  4899.5  253.08  4934.6  252.96
  4970.6  250.39  4977.3  251.92  4984.8     247  4991.5  246.97    4997  244.14
  4999.8  243.64    5003  244.14  5005.7  244.14  5009.5  250.42  5022.9  252.35
  5045.7  251.64  5083.8  254.56  5142.3  255.66  5266.3  253.93  5621.1   254.9
  5702.2  256.35  5847.8  262.09  6026.6  270.89  6107.7   276.5  6148.3  281.45
  6168.5   285.4  6196.4  288.24  6201.5  287.48  6219.2  290.85  6229.4  294.14
#Mann= 5 ,-1 , 0
  4410.7      .1       0    4997     .07       0    5003      .1       0
  5142.3     .05       0  5847.8      .1       0
Bank Sta=4977.3,5022.9
XS Rating Curve= 0 ,0
Exp/Cntr=0.3,0.1

Type RM Length L Ch R = 1 ,66438   ,441,441,441
BEGIN DESCRIPTION:
SALT BRANCH 98.0
END DESCRIPTION:
XS GIS Cut Line= 4
      2219231.01     13308923.21       2219581.4     13308483.51
      2219443.98     13307260.49      2219121.86     13306958.93
#Sta/Elev= 30
  4204.2  268.41  4823.4  260.74  4964.3  251.56  4974.4  248.56    4997  245.46
  4999.8  244.96    5003  245.46  5007.1  246.07  5021.5  249.63  5032.1  249.69
  5038.9  250.23  5054.9  252.46  5369.1  253.86  5668.7  255.38  5797.1  258.73
  5827.4  259.79  5996.5  266.62  6223.7  281.49    6252  284.12  6287.2  292.56
  6301.3  294.47    6358   296.3  6372.2  296.11    6379  293.29  6386.3  294.58
  6400.5  293.77  6407.3  291.76  6428.8  293.29  6435.7  291.83  6438.4  293.31
#Mann= 9 ,-1 , 0
  4204.2      .1       0    4997     .07       0    5003      .1       0
  5007.1     .05       0  5032.1      .1       0  5038.9     .05       0
  5369.1      .1       0  5797.1     .05       0  5827.4      .1       0
Bank Sta=4964.3,5054.9
XS Rating Curve= 0 ,0
Exp/Cntr=0.3,0.1

Type RM Length L Ch R = 1 ,65997   ,490,490,490
BEGIN DESCRIPTION:
SALT BRANCH 97.0
END DESCRIPTION:
XS GIS Cut Line= 3
      2219437.11     13309218.69      2219945.55     13308662.15
      2220117.33     13307054.32
#Sta/Elev= 30
    3808  269.02  3958.6  264.43  4163.4  260.91  4270.1  260.41  4340.4  262.38
  4453.8   263.6  4567.1  263.07  4707.9   259.7  4808.5  255.11    4899  253.35
  4979.5  249.03  4989.5  246.65    4997  241.09  4999.8  240.59    5003  241.09
  5005.2  241.98  5010.2   241.3  5019.7  247.68  5029.8  248.79  5059.9  250.13
  5160.5  251.79  5512.1  254.33  5555.7  254.37  5703.6  257.89  5864.5  267.08
  5934.9  270.14  6045.9  277.28    6126  279.71  6166.2  282.91  6178.8  285.04
#Mann= 5 ,-1 , 0
    3808      .1       0    4997     .07       0    5003      .1       0
  5512.1     .05       0  5555.7      .1       0
Bank Sta=4979.5,5029.8
XS Rating Curve= 0 ,0
Exp/Cntr=0.3,0.1

Type RM Length L Ch R = 1 ,65507   ,400,400,400
BEGIN DESCRIPTION:
SALT BRANCH 96.0
END DESCRIPTION:
XS GIS Cut Line= 2
      2219547.93     13309319.54      2220762.93     13307913.61
#Sta/Elev= 30
  3626.3  270.36  3698.7  268.83  3734.8  266.62  3890.6  261.94  4032.1  260.02
  4138.5  262.34  4202.1  264.96  4273.4  265.37  4422.6  262.08  4705.6  250.98
  4783.5  249.72  4791.1  250.49  4861.4  249.23  4961.2  249.34    4982  247.69
  4989.7  246.18    4997  240.26  4999.8  239.76    5003  240.26  5010.5  242.54
  5017.6  243.06  5024.8  247.83  5031.4  249.59    5039  249.63  5074.2  254.89
  5131.2  258.55  5137.8  260.03  5188.2  262.66  5194.8  264.09  5484.5  279.25
#Mann= 3 ,-1 , 0
  3626.3      .1       0    4997     .07       0    5003      .1       0
Bank Sta=4982,5024.8
XS Rating Curve= 0 ,0
Exp/Cntr=0.3,0.1