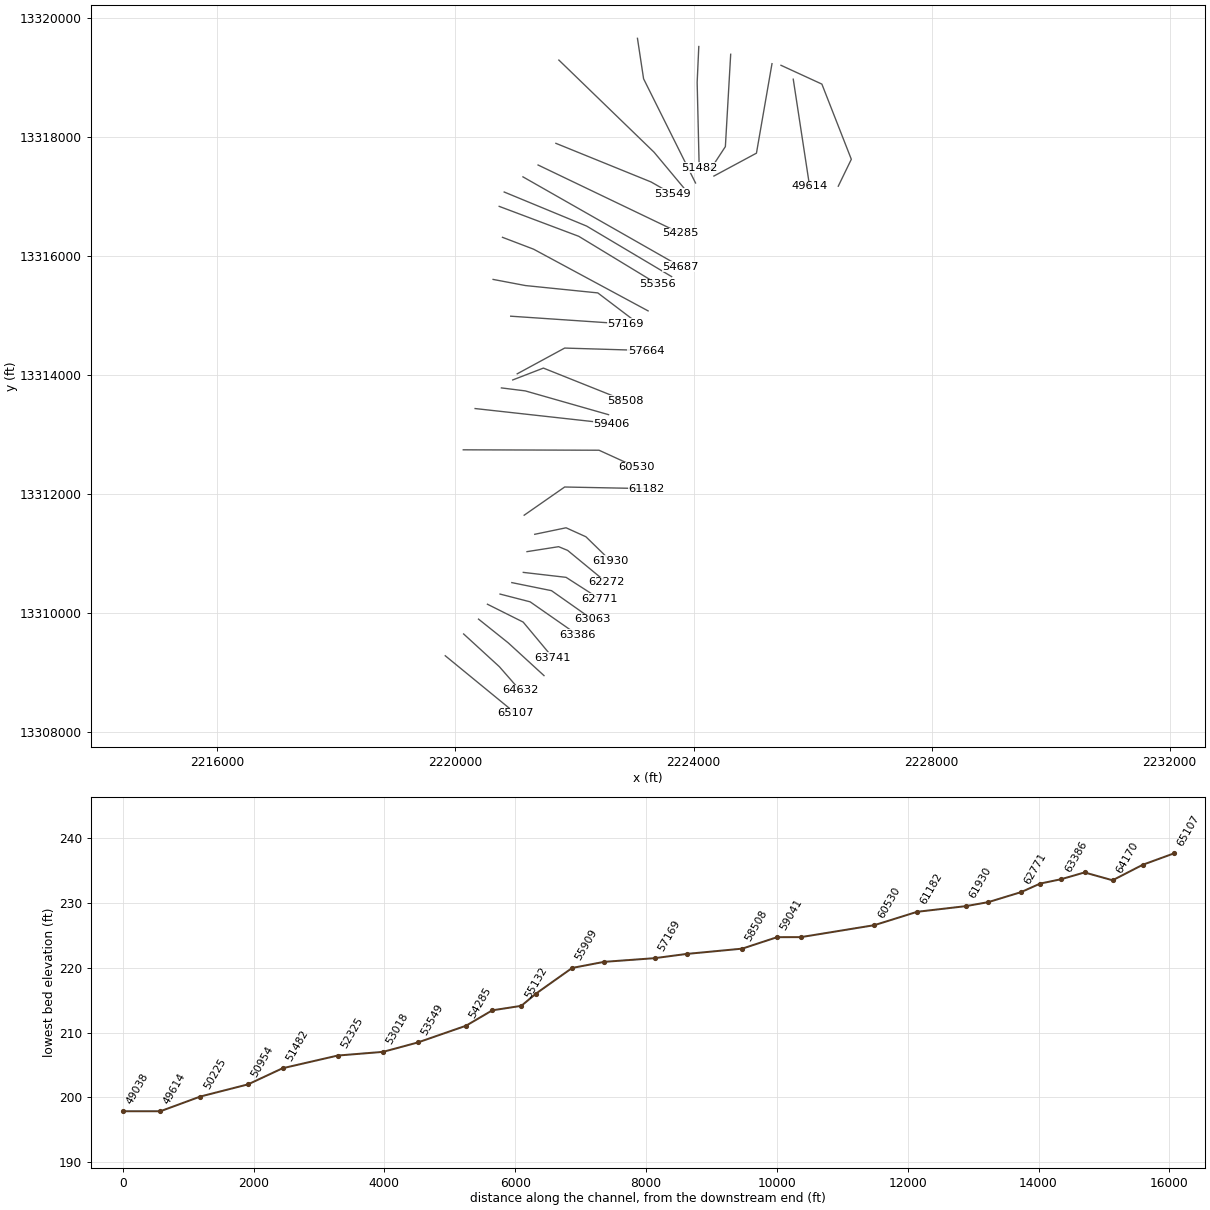
HEC-RAS study SALT BRANCH.prj: SALT BRANCH Base Level Engineering

--- SALT BRANCH.g01 (geometry) --- (continued)

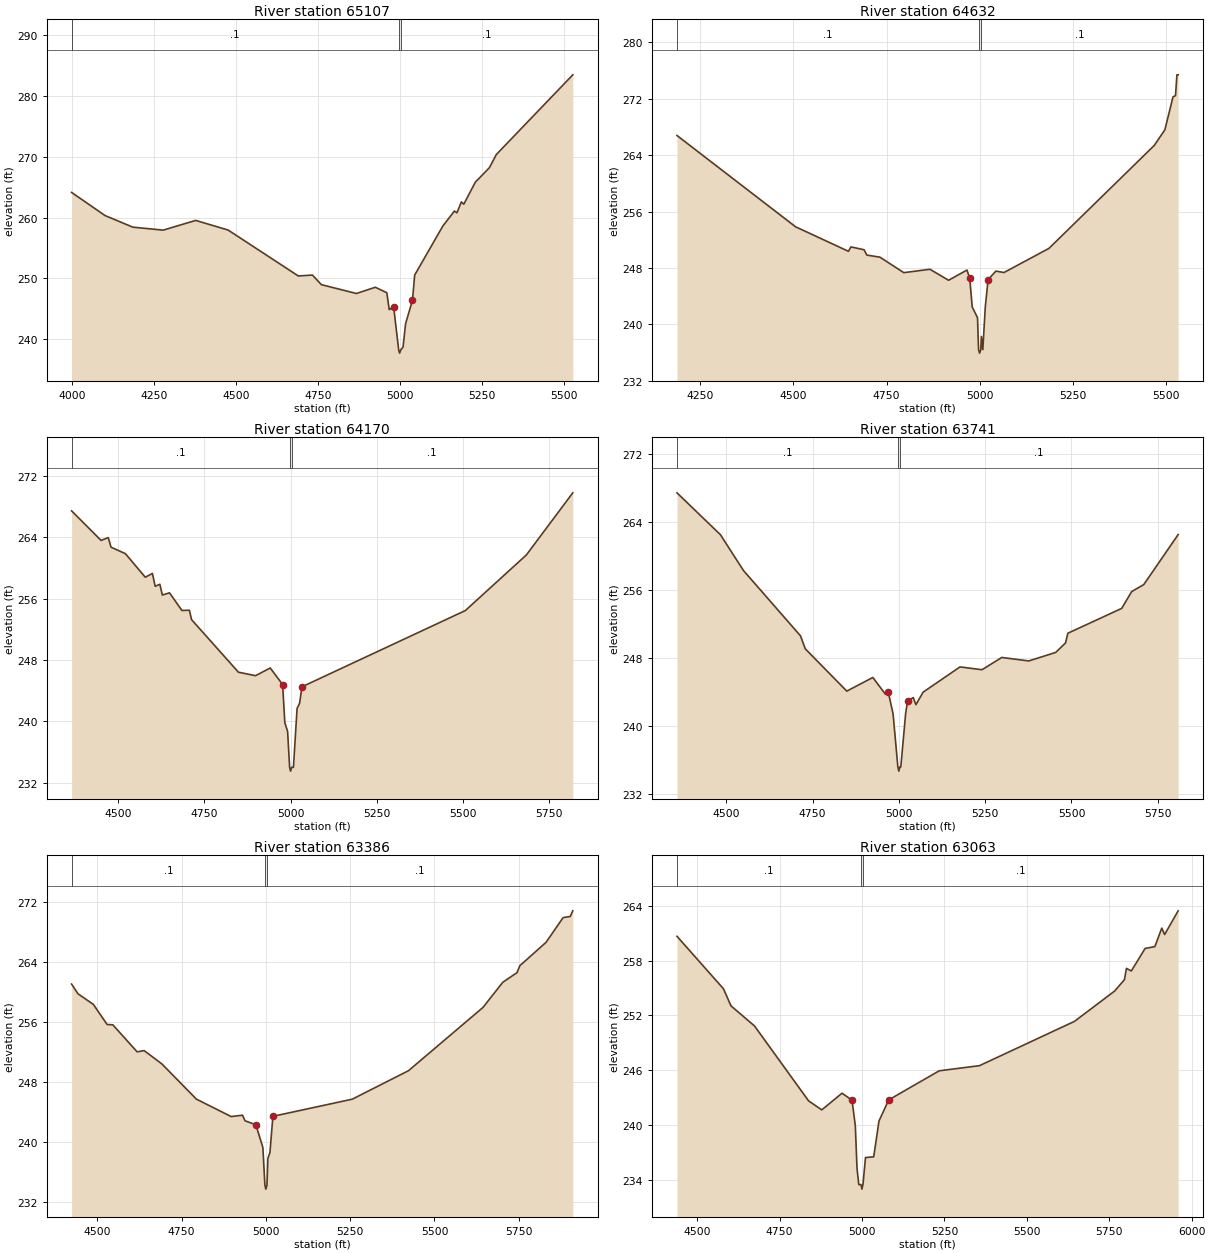
Type RM Length L Ch R = 1 ,65107   ,475,475,475
BEGIN DESCRIPTION:
SALT BRANCH 95.0
END DESCRIPTION:
XS GIS Cut Line= 2
      2219828.77     13309280.51      2221010.46      13308311.8
#Sta/Elev= 30
  3999.7  264.15  4101.7  260.34  4186.3  258.43  4278.9  257.94    4378  259.54
    4477  257.95  4690.9  250.39  4733.9  250.54  4761.2  248.96  4868.1   247.5
  4925.5  248.53  4960.7  247.63  4968.1  244.85  4981.5  245.31    4997  238.18
  4999.8  237.68    5003  238.18  5010.2  238.69  5018.1  242.56  5038.9  246.38
  5045.7  250.54  5131.5  258.61  5166.7  261.08  5174.6   260.8    5188  262.59
  5195.4  262.21  5230.6  265.84  5273.6  268.23  5294.4  270.38  5527.7  283.52
#Mann= 3 ,-1 , 0
  3999.7      .1       0    4997     .07       0    5003      .1       0
Bank Sta=4981.5,5038.9
XS Rating Curve= 0 ,0
Exp/Cntr=0.3,0.1

Type RM Length L Ch R = 1 ,64632   ,462,462,462
BEGIN DESCRIPTION:
SALT BRANCH 94.0
END DESCRIPTION:
XS GIS Cut Line= 3
      2220137.69     13309646.88      2220737.72     13309096.85
      2221087.73     13308696.85
#Sta/Elev= 30
  4187.3  266.79  4505.8  253.84  4647.6  250.37  4654.4  250.99  4689.6  250.59
    4697  249.83  4732.1  249.54  4796.3  247.34  4866.5  247.82  4916.5  246.26
  4965.8  247.71  4973.2  246.57    4980  242.46  4994.2  240.95    4997  236.43
  4999.8  235.93    5003  236.43  5004.6  238.29  5008.4  236.43    5015  242.45
  5022.6  246.36  5043.5  247.56  5065.3  247.36  5185.9  250.78  5468.7  265.38
  5497.2   267.6    5519  272.27  5525.7  272.44  5529.5  275.39  5532.8  275.39
#Mann= 3 ,-1 , 0
  4187.3      .1       0    4997     .07       0    5003      .1       0
Bank Sta=4973.2,5022.6
XS Rating Curve= 0 ,0
Exp/Cntr=0.3,0.1

Type RM Length L Ch R = 1 ,64170   ,429,429,429
BEGIN DESCRIPTION:
SALT BRANCH 93.0
END DESCRIPTION:
XS GIS Cut Line= 3
      2220387.73     13309896.84      2220887.72     13309496.85
      2221487.69     13308946.88
#Sta/Elev= 30
  4364.4  267.42    4450  263.57  4470.8  263.94  4478.8  262.69  4520.5  261.85
  4578.1  258.78  4598.9  259.27  4606.9   257.6  4620.5  257.86  4627.7  256.46
  4648.5  256.75  4684.5  254.45  4706.2  254.48  4712.6  253.25  4848.6  246.41
  4898.2  245.96  4940.7  246.96  4976.7  244.81  4983.1  239.83  4991.1  238.72
    4997  234.03  4999.8  233.53    5003  234.03  5008.1  234.03  5018.6  241.69
    5026  242.37  5032.8  244.51  5506.9  254.44  5683.9  261.68  5818.6  269.77
#Mann= 3 ,-1 , 0
  4364.4      .1       0    4997     .07       0    5003      .1       0
Bank Sta=4976.7,5032.8
XS Rating Curve= 0 ,0
Exp/Cntr=0.3,0.1

Type RM Length L Ch R = 1 ,63741   ,355,355,355
BEGIN DESCRIPTION:
SALT BRANCH 92.0
END DESCRIPTION:
XS GIS Cut Line= 3
      2220537.69     13310146.87      2221137.72     13309846.85
      2221637.73     13309246.84
#Sta/Elev= 30
  4357.1   267.4  4482.9  262.49    4550  258.27  4714.9  250.62  4728.9  249.09
  4849.1  244.13  4924.5  245.73  4960.9  243.77  4969.3  244.01  4983.2  241.46
    4997  235.24  4999.8  234.74    5003  235.24  5005.6  235.24  5019.6  241.52
  5025.2  242.96  5041.6  243.37  5049.4  242.54  5070.3  244.01    5177  246.97
  5240.8  246.64  5298.1  248.08  5376.2  247.67  5454.3  248.67  5482.9  249.79
  5489.4  250.92  5645.6  253.84  5674.3  255.81  5709.4  256.63    5809   262.5
#Mann= 3 ,-1 , 0
  4357.1      .1       0    4997     .07       0    5003      .1       0
Bank Sta=4969.3,5025.2
XS Rating Curve= 0 ,0
Exp/Cntr=0.3,0.1

Type RM Length L Ch R = 1 ,63386   ,323,323,323
BEGIN DESCRIPTION:
SALT BRANCH 91.0
END DESCRIPTION:
XS GIS Cut Line= 3
      2220749.33     13310317.81      2221254.52     13310187.61
      2222046.22      13309635.5
#Sta/Elev= 30
  4423.5  261.08  4442.3  259.79  4488.2  258.36  4528.9  255.68  4545.8  255.64
    4618  252.03  4638.7   252.2  4691.6  250.41  4793.6  245.72  4896.9  243.39
  4930.6  243.57  4938.2  242.82  4970.1   242.3    4991  239.26    4997   234.2
  4999.8   233.7    5003   234.2  5005.8  237.78  5011.9  238.58  5020.7  243.42
  5256.2  245.71  5422.9  249.51    5644  257.96  5702.9  261.33  5744.8   262.6
  5753.5  263.54  5831.2  266.66  5881.8  269.96  5902.7   270.1  5910.4  270.86
#Mann= 3 ,-1 , 0
  4423.5      .1       0    4997     .07       0    5003      .1       0
Bank Sta=4970.1,5020.7
XS Rating Curve= 0 ,0
Exp/Cntr=0.3,0.1

Type RM Length L Ch R = 1 ,63063   ,292,292,292
BEGIN DESCRIPTION:
SALT BRANCH 90.0
END DESCRIPTION:
XS GIS Cut Line= 3
      2220947.22     13310510.52      2221613.89     13310375.11
      2222300.59      13309891.3
#Sta/Elev= 30
  4438.8  260.65  4579.9  254.91  4602.6  253.05    4674  250.85  4838.2  242.66
  4878.1  241.68  4939.4   243.5  4969.9  242.74  4979.9  239.91    4985  235.27
  4990.3  233.52    4997  233.52  4999.8  233.02    5003  233.52  5010.7  236.47
  5035.6  236.55  5051.6  240.46  5081.1  242.77  5234.4  245.95  5356.4  246.51
  5644.6  251.35  5766.6  254.67  5796.2  255.91  5802.3  257.14  5817.1  256.86
  5858.9  259.32  5888.5  259.52  5909.4  261.54  5918.1  260.84  5959.1  263.43
#Mann= 3 ,-1 , 0
  4438.8      .1       0    4997     .07       0    5003      .1       0
Bank Sta=4969.9,5081.1
XS Rating Curve= 0 ,0
Exp/Cntr=0.3,0.1

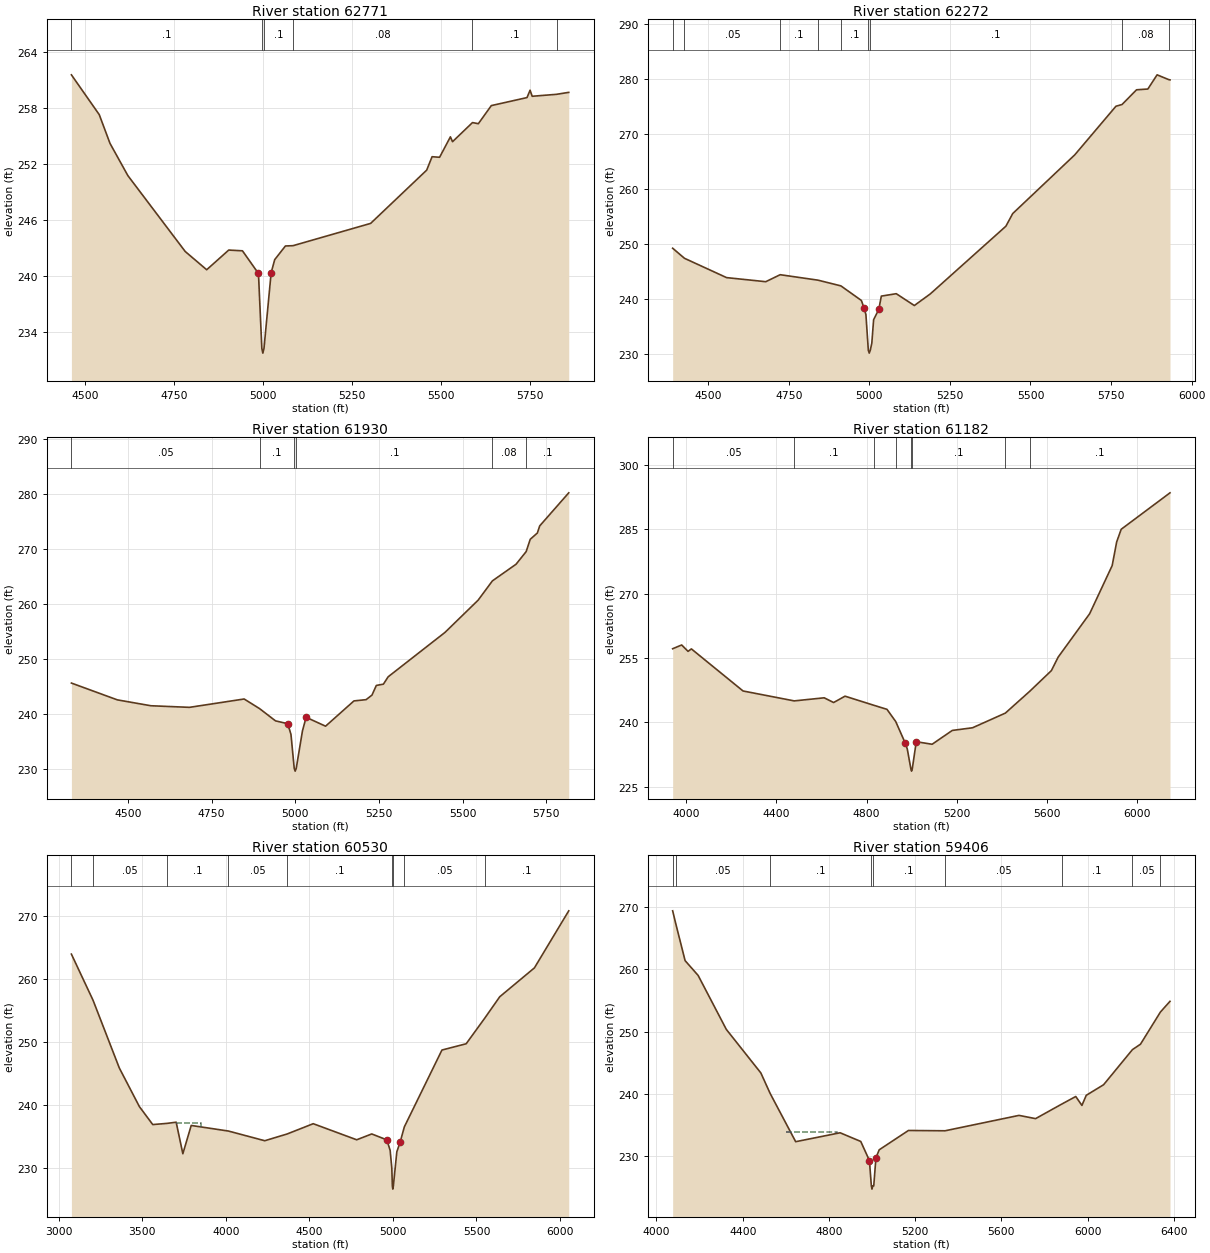
Type RM Length L Ch R = 1 ,62771   ,499,499,499
BEGIN DESCRIPTION:
SALT BRANCH 89.0
END DESCRIPTION:
XS GIS Cut Line= 3
      2221139.98     13310682.39      2221858.68     13310599.06
      2222426.38     13310234.49
#Sta/Elev= 30
  4461.6  261.54  4539.9  257.27  4570.1  254.19  4620.4  250.73  4781.5   242.6
  4841.9  240.64  4903.9  242.75  4942.5  242.67  4987.5  240.24    4997   232.2
  4999.8   231.7    5003   232.2  5023.1   240.3  5033.1  241.72  5063.3  243.19
  5084.6  243.22  5302.8  245.61  5460.4  251.32  5475.6  252.76  5496.7   252.7
  5527.1  254.89  5533.1  254.37  5589.2  256.42  5605.7   256.3  5642.1  258.24
  5742.5   259.1  5751.1  259.89    5757  259.24  5825.5  259.45  5859.8  259.66
#Mann= 6 ,-1 , 0
  4461.6      .1       0    4997     .07       0    5003      .1       0
  5084.6     .08       0  5589.2      .1       0  5825.5     .08       0
Bank Sta=4987.5,5023.1
XS Rating Curve= 0 ,0
Exp/Cntr=0.3,0.1

Type RM Length L Ch R = 1 ,62272   ,342,342,342
BEGIN DESCRIPTION:
SALT BRANCH 88.0
END DESCRIPTION:
XS GIS Cut Line= 4
      2221202.46     13311031.36      2221733.68     13311114.69
      2221884.73     13311052.19      2222534.24     13310516.99
#Sta/Elev= 30
    4390  249.22  4426.7  247.39  4557.3  243.88  4678.8  243.14  4723.5  244.41
  4840.6  243.42  4911.9  242.38  4975.4  239.73  4984.1  238.31  4989.5  237.17
    4997  230.66  4999.8  230.16    5003  230.66  5007.8  231.98  5013.4  236.24
  5029.5   238.1  5037.3  240.52  5083.6  240.96  5139.7  238.81  5189.2  240.92
  5423.7  253.22  5444.9  255.52  5637.4  266.19  5765.1  275.02  5784.1  275.34
    5829  278.01  5864.1  278.15  5892.8  280.73  5928.4  279.87  5932.8  279.81
#Mann= 9 ,-1 , 0
    4390      .1       0  4426.7     .05       0  4723.5      .1       0
  4840.6     .05       0  4911.9      .1       0    4997     .07       0
    5003      .1       0  5784.1     .08       0  5928.4      .1       0
Bank Sta=4984.1,5029.5
XS Rating Curve= 0 ,0
Exp/Cntr=0.3,0.1

Type RM Length L Ch R = 1 ,61930   ,748,748,748
BEGIN DESCRIPTION:
SALT BRANCH 87.0
END DESCRIPTION:
XS GIS Cut Line= 4
       2221332.6     13311323.01      2221858.68      13311432.4
      2222192.02     13311281.36      2222608.66     13310875.13
#Sta/Elev= 30
  4331.6  245.57  4468.9  242.51  4569.1  241.44  4684.1  241.15  4847.5  242.67
  4893.5  240.92  4941.1  238.69  4977.7  238.17  4987.3  236.22    4997  230.04
  4999.8  229.54    5003  230.04  5021.6  236.87  5032.6  239.34  5090.6  237.72
  5175.3  242.32  5211.6  242.55  5229.2  243.38  5242.2  245.14  5263.3  245.37
  5277.5  246.71  5447.2  254.79  5546.2  260.66  5588.8  264.17  5659.4   267.2
  5689.6   269.5  5701.8  271.74    5723  272.88  5730.1  274.18  5816.8   280.2
#Mann= 6 ,-1 , 0
  4331.6     .05       0  4893.5      .1       0    4997     .07       0
    5003      .1       0  5588.8     .08       0  5689.6      .1       0
Bank Sta=4977.7,5032.6
XS Rating Curve= 0 ,0
Exp/Cntr=0.3,0.1

Type RM Length L Ch R = 1 ,61182   ,652,652,652
BEGIN DESCRIPTION:
SALT BRANCH 85.0
END DESCRIPTION:
XS GIS Cut Line= 3
      2221154.81     13311644.09      2221835.04     13312118.19
      2223214.42     13312090.74
#Sta/Elev= 30
  3938.9  257.17    3979  258.05  4007.2  256.56  4022.1  257.13  4251.5  247.33
  4478.8  245.02  4611.9  245.74  4653.8  244.64  4704.4  246.12  4833.6  243.98
  4890.8  243.05  4929.7   240.2  4970.8  235.31  4980.8  233.85    4997  229.16
  4999.8  228.66    5003  229.16  5020.8  235.51  5091.2  234.92  5180.8  238.14
  5270.8  238.76  5416.6  242.18    5525  247.27  5620.9  252.07  5650.9  255.21
  5790.9  265.33  5890.9  276.54    5911  282.08    5931     285  6147.7  293.49
#Mann= 8 ,-1 , 0
  3938.9     .05       0  4478.8      .1       0  4833.6     .05       0
  4929.7      .1       0    4997     .07       0    5003      .1       0
  5416.6     .05       0    5525      .1       0
Bank Sta=4970.8,5020.8
XS Rating Curve= 0 ,0
Exp/Cntr=0.3,0.1

Type RM Length L Ch R = 1 ,60530   ,1124,1124,1124
BEGIN DESCRIPTION:
SALT BRANCH 84.0
END DESCRIPTION:
XS GIS Cut Line= 3
      2220131.03     13312743.44      2222412.19     13312736.57
      2223043.54     13312448.35
#Sta/Elev= 30
    3077  263.99  3206.5  256.65  3363.7  245.87  3483.7  239.73  3563.7  236.87
  3649.2  237.06  3703.7  237.25  3743.7  232.23  3793.7  236.73  4016.6  235.84
  4233.7   234.3  4367.1  235.37  4523.7  237.01  4783.7  234.45  4873.7  235.38
  4963.7  234.44  4983.7  232.78  4993.7  229.97    4997   227.1  4999.8   226.6
    5003   227.1  5023.7  232.53  5043.7  234.09  5068.8  236.51  5293.7  248.73
  5438.7  249.73  5548.9  253.77  5639.5  257.21  5846.8   261.8  6052.2  270.88
#Mann= 9 ,-1 , 0
    3077      .1       0  3206.5     .05       0  3649.2      .1       0
  4016.6     .05       0  4367.1      .1       0    4997     .07       0
    5003      .1       0  5068.8     .05       0  5548.9      .1       0
#XS Ineff= 1 ,-1
 3702.54 3853.45  237.05
Permanent Ineff=
       F
Bank Sta=4963.7,5043.7
XS Rating Curve= 0 ,0
Exp/Cntr=0.3,0.1

Type RM Length L Ch R = 1 ,59406   ,365,365,365
BEGIN DESCRIPTION:
SALT BRANCH 83.0
END DESCRIPTION:
XS GIS Cut Line= 2
      2220330.35      13313437.4      2222623.92     13313183.32
#Sta/Elev= 30
    4075   269.4  4089.4  267.34  4132.7  261.41  4193.1  259.04  4323.9  250.38
  4484.2  243.39  4527.2  240.11  4645.8  232.36    4852  233.79  4947.7   232.4
  4987.9  229.34    4997  225.25  4999.8  224.75    5003  225.25    5008  225.25
  5018.1  229.76  5033.4  231.06    5169  234.16  5338.9  234.11  5682.1  236.58
  5758.9  236.06  5881.2  238.41  5945.3  239.61  5973.9  238.18    5994   239.8
  6074.5   241.5  6208.3  247.13  6245.6     248  6338.3  253.17  6382.6  254.88
#Mann= 9 ,-1 , 0
    4075      .1       0  4089.4     .05       0  4527.2      .1       0
    4997     .07       0    5003      .1       0  5338.9     .05       0
  5881.2      .1       0  6208.3     .05       0  6338.3      .1       0
#XS Ineff= 1 ,-1
 4600.64 4836.43  233.89
Permanent Ineff=
       F
Bank Sta=4987.9,5018.1
XS Rating Curve= 0 ,0
Exp/Cntr=0.3,0.1

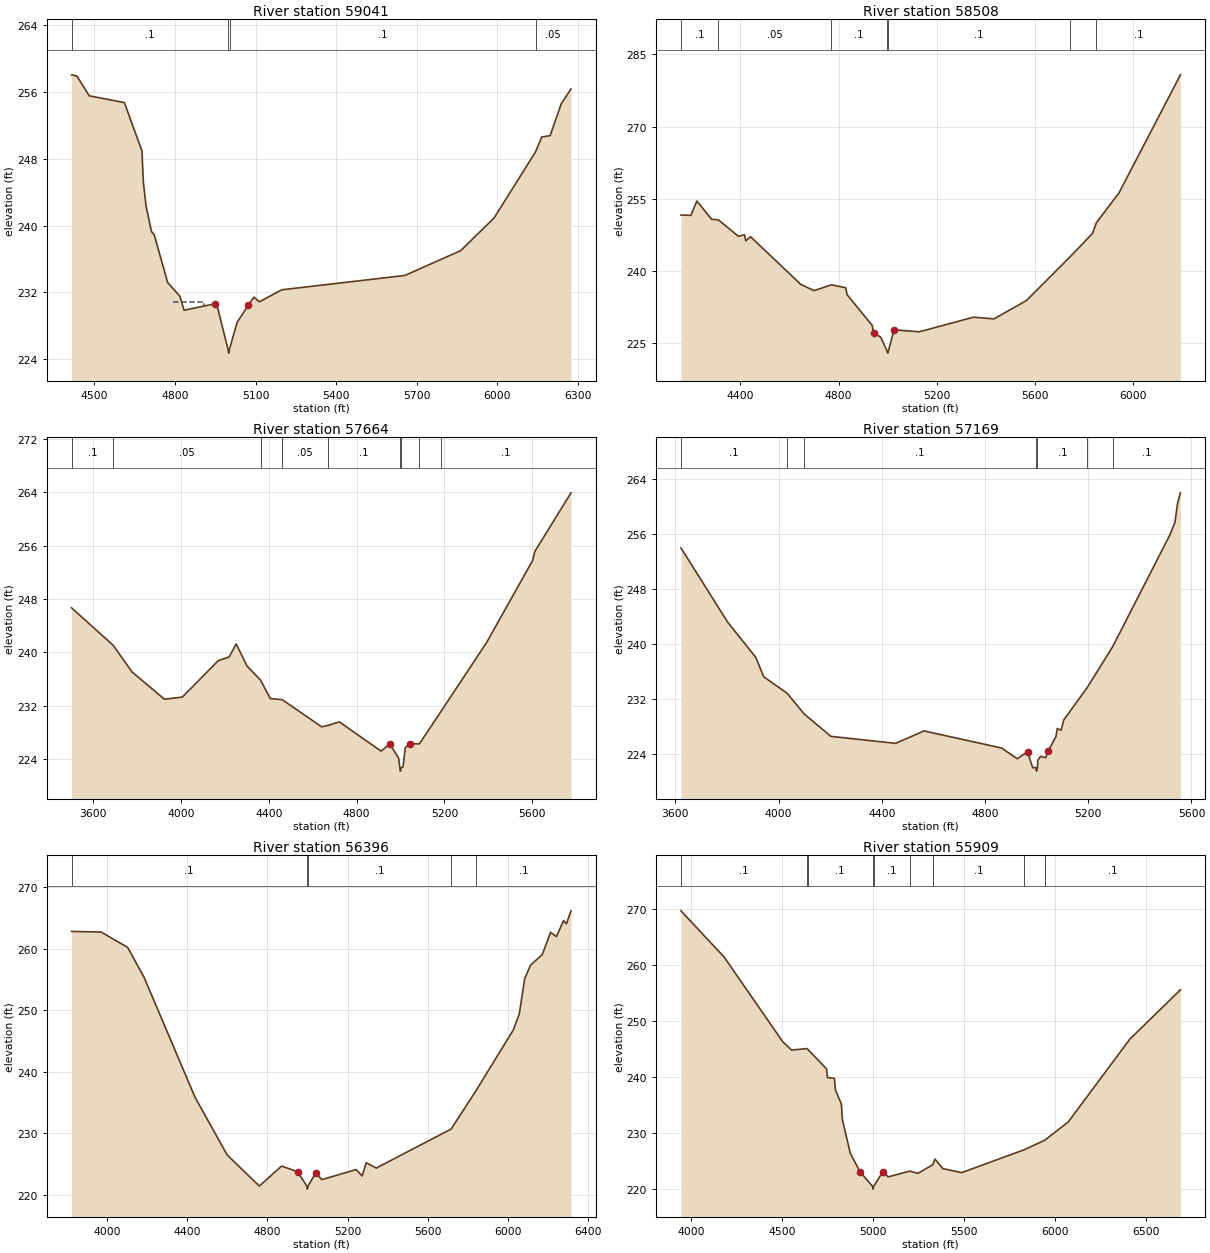
Type RM Length L Ch R = 1 ,59041   ,533,533,533
BEGIN DESCRIPTION:
SALT BRANCH 82.0
END DESCRIPTION:
XS GIS Cut Line= 3
       2220772.4     13313784.36      2221172.44     13313734.35
      2222572.46     13313334.35
#Sta/Elev= 30
  4414.8  258.03  4435.1  257.88  4480.6  255.52  4611.6  254.71    4677  248.92
  4682.2  245.19  4692.3  242.34  4712.4  239.28  4722.5  238.91  4772.9  233.18
    4818  231.55  4833.8  229.87  4948.3  230.64  4958.7  230.15    4997  225.24
  4999.8  224.74    5003  225.24  5031.5  228.43  5073.1  230.49  5093.9  231.44
  5113.9  230.88  5197.9  232.32  5655.5  234.03  5863.5     237  5987.5   240.9
  6142.1  248.82  6165.1   250.6  6196.3  250.75  6237.9  254.58    6274  256.33
#Mann= 4 ,-1 , 0
  4414.8      .1       0    4997     .07       0    5003      .1       0
  6142.1     .05       0
#XS Ineff= 1 ,-1
 4790.89  4906.8   230.9
Permanent Ineff=
       F
Bank Sta=4948.3,5073.1
XS Rating Curve= 0 ,0
Exp/Cntr=0.3,0.1

Type RM Length L Ch R = 1 ,58508   ,844,844,844
BEGIN DESCRIPTION:
SALT BRANCH 81.0
END DESCRIPTION:
XS GIS Cut Line= 3
      2220962.48     13313918.37      2221477.76     13314117.61
      2222851.94     13313567.94
#Sta/Elev= 30
  4158.7  251.63    4199  251.57  4223.6  254.54  4283.4  250.76  4311.3  250.63
  4392.5  247.21  4417.1  247.55  4422.5  246.29  4441.7  247.14  4646.8  237.22
  4700.5  235.94  4770.7  237.15  4829.3  236.54  4834.7   235.1    4937  228.73
  4942.4  227.25    4972  226.24    4997  223.47  4999.8  222.97    5003  223.47
  5025.8  227.82  5128.2  227.39    5349  230.43  5432.7  230.08  5564.4  233.88
  5741.8  242.95  5833.6  247.83  5848.9  250.02  5941.3  256.24  6191.2  280.74
#Mann= 7 ,-1 , 0
  4158.7      .1       0  4311.3     .05       0  4770.7      .1       0
    4997     .07       0    5003      .1       0  5741.8     .08       0
  5848.9      .1       0
Bank Sta=4942.4,5025.8
XS Rating Curve= 0 ,0
Exp/Cntr=0.3,0.1

Type RM Length L Ch R = 1 ,57664   ,495,495,495
BEGIN DESCRIPTION:
SALT BRANCH 80.0
END DESCRIPTION:
XS GIS Cut Line= 3
      2221038.03     13314021.43      2221835.04     13314454.29
      2223202.35     13314413.06
#Sta/Elev= 30
  3501.6  246.66  3691.3  241.04  3777.5  237.03  3924.8  232.95  4006.5  233.27
    4170  238.74  4219.4  239.28  4251.7  241.24  4301.1  237.92  4362.5  235.82
  4407.2  233.04  4461.3  232.88  4641.4   228.8  4670.4  229.02  4721.4  229.55
  4911.5  225.16  4951.5  226.24  4991.5   224.1    4997  222.66  4999.8  222.16
    5003  222.66  5011.5  222.79  5021.5  225.64  5041.5   226.3  5085.9  226.24
  5184.2  231.11  5391.7  241.43  5601.8  253.76  5611.8  255.12  5776.5  263.91
#Mann= 9 ,-1 , 0
  3501.6      .1       0  3691.3     .05       0  4362.5      .1       0
  4461.3     .05       0  4670.4      .1       0    4997     .07       0
    5003      .1       0  5085.9     .05       0  5184.2      .1       0
Bank Sta=4951.5,5041.5
XS Rating Curve= 0 ,0
Exp/Cntr=0.3,0.1

Type RM Length L Ch R = 1 ,57169   ,773,773,773
BEGIN DESCRIPTION:
Mapping XS d2c02b58
END DESCRIPTION:
XS GIS Cut Line= 2
      2220928.12     13314990.21      2222858.81     13314859.67
#Sta/Elev= 30
  3622.1  253.99  3802.1  243.23  3912.4  238.03  3942.4  235.24  4033.3  232.84
  4099.3  229.83    4203  226.56  4453.6  225.54  4563.8  227.35  4864.5  224.86
  4924.7  223.31  4964.8  224.31  4984.8     222    4997     222  4999.8   221.5
    5003     222  5004.9  223.07  5014.9  223.66  5034.9  223.44  5044.9  224.43
    5075  226.54    5080  227.71  5095.1  227.45  5105.1  228.95  5196.1  233.66
  5294.8  239.62    5516  255.85  5536.1  257.74  5546.1  260.51  5557.2     262
#Mann= 7 ,-1 , 0
  3622.1      .1       0  4033.3     .05       0  4099.3      .1       0
    4997     .07       0    5003      .1       0  5196.1     .05       0
  5294.8      .1       0
Bank Sta=4964.8,5044.9
XS Rating Curve= 0 ,0
Exp/Cntr=0.3,0.1

Type RM Length L Ch R = 1 ,56396   ,487,487,487
BEGIN DESCRIPTION:
Mapping XS 8e695e64
END DESCRIPTION:
XS GIS Cut Line= 4
      2220632.67     13315608.59      2221175.44     13315505.53
      2222391.58     13315381.85      2222961.83     13314949.01
#Sta/Elev= 30
  3823.7  262.79  3971.7  262.68  4103.7  260.19  4185.8  255.31  4438.8  235.91
  4599.6  226.49  4760.4  221.43    4871  224.67  4951.4  223.76    4997  221.43
  4999.8  220.93    5003  221.43  5041.9  223.58    5072  222.47  5242.9  224.11
  5273.1  223.08  5293.2  225.22  5343.4  224.35  5716.9  230.69  5843.1  237.04
  6027.7  246.84  6056.8  249.42  6083.9  255.15    6113  257.31  6171.2  259.03
  6212.9  262.64    6242  261.95  6277.3  264.54  6291.9  264.02  6314.5  266.13
#Mann= 5 ,-1 , 0
  3823.7      .1       0    4997     .07       0    5003      .1       0
  5716.9     .05       0  5843.1      .1       0
Bank Sta=4951.4,5041.9
XS Rating Curve= 0 ,0
Exp/Cntr=0.3,0.1

Type RM Length L Ch R = 1 ,55909   ,553,553,553
BEGIN DESCRIPTION:
SALT BRANCH 77.0
END DESCRIPTION:
XS GIS Cut Line= 3
      2220790.65      13316316.3      2221312.86     13316117.04
       2223236.7     13315079.53
#Sta/Elev= 30
    3944  269.72  4181.3  261.46  4502.9  246.35  4552.1  244.83  4636.5  245.11
  4640.2     245  4743.5   241.5  4749.2  239.94  4787.3  239.77  4792.9   237.7
  4825.4  235.22  4831.1  232.39  4874.8  226.38  4928.8  223.04    4997  220.49
  4999.8  219.99    5003  220.49  5053.8  223.13  5082.4  222.18  5201.5  223.21
  5246.2  222.81  5328.1  224.35  5339.5  225.36  5383.3  223.65  5487.1  222.94
  5829.6  227.02    5943  228.73  6071.8  231.98  6410.7  246.79  6688.7  255.61
#Mann= 9 ,-1 , 0
    3944      .1       0  4636.5     .05       0  4640.2      .1       0
    4997     .07       0    5003      .1       0  5201.5     .16       0
  5328.1      .1       0  5829.6     .05       0    5943      .1       0
Bank Sta=4928.8,5053.8
XS Rating Curve= 0 ,0
Exp/Cntr=0.3,0.1

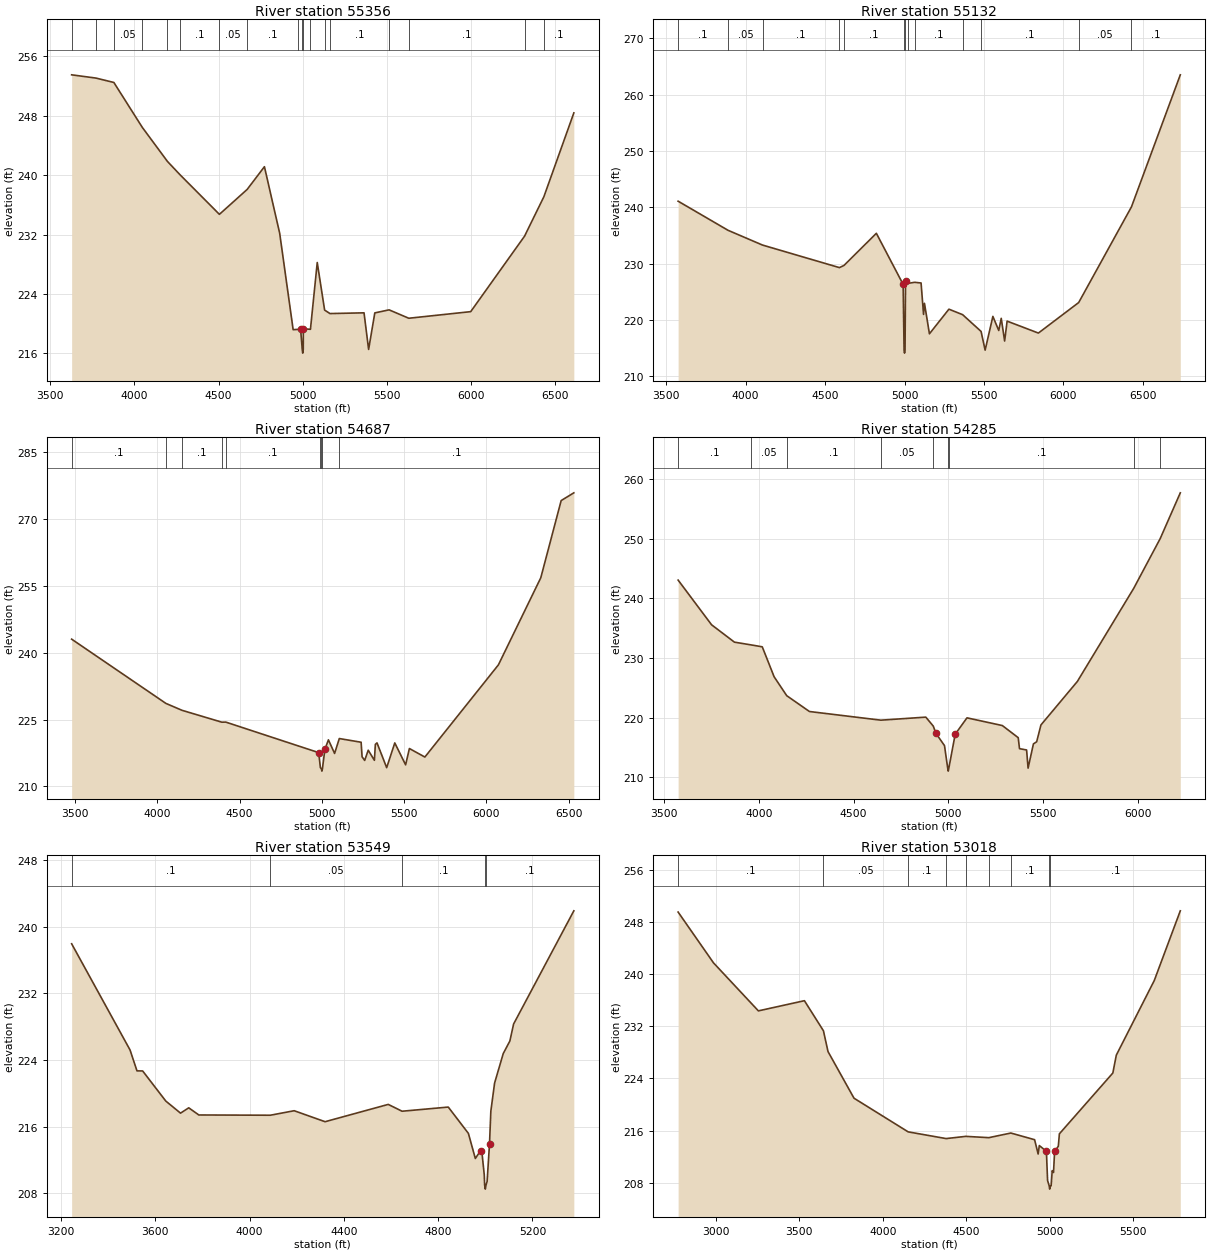
Type RM Length L Ch R = 1 ,55356   ,224,224,224
BEGIN DESCRIPTION:
Mapping XS 2fbdb859
END DESCRIPTION:
XS GIS Cut Line= 3
      2220735.06     13316836.87      2222071.89     13316333.39
      2223399.99     13315526.12
#Sta/Elev= 30
  3627.4  253.53    3772  253.09  3878.1   252.5  4047.3  246.44  4196.5  241.86
  4271.3  240.06    4505  234.73  4669.9  238.09  4772.4  241.15  4863.1  232.17
    4943  219.19  4972.4  219.23  4987.3  219.23    4997  216.53  4999.8  216.03
    5003  216.53  5003.4  219.31  5045.7  219.24  5086.1  228.24  5129.9  221.83
  5161.7  221.36    5364  221.46  5391.2  216.53    5428  221.45  5512.8  221.86
  5629.9  220.73  5997.6  221.62  6317.4  231.79  6432.1   237.1  6610.1   248.4
#Mann= 18 ,-1 , 0
  3627.4      .1       0    3772     .08       0  3878.1     .05       0
  4047.3      .1       0  4196.5     .05       0  4271.3      .1       0
    4505     .05       0  4669.9      .1       0  4972.4     .05       0
    4997    .033       0    5003     .05       0  5045.7      .1       0
  5129.9     .16       0  5161.7      .1       0  5512.8     .05       0
  5629.9      .1       0  6317.4     .05       0  6432.1      .1       0
Bank Sta=4987.3,5003.4
XS Rating Curve= 0 ,0
Exp/Cntr=0.3,0.1

Type RM Length L Ch R = 1 ,55132   ,445,445,445
BEGIN DESCRIPTION:
SALT BRANCH 76.0
END DESCRIPTION:
XS GIS Cut Line= 3
      2220819.24      13317078.2       2222204.7     13316505.27
      2223631.82     13315656.29
#Sta/Elev= 30
  3575.2  241.11  3889.5  235.94  4106.5  233.32  4590.1  229.32    4619  229.71
  4822.6  235.41  4991.1  226.34    4997  214.64  4999.8  214.14    5003  214.64
  5006.1  226.91  5020.5  226.52  5063.3  226.71  5103.9  226.59  5119.5  221.01
  5125.3  222.98  5156.5  217.57  5279.1  221.94  5365.2  220.97  5481.5  217.99
    5507  214.67  5555.7  220.66  5592.7  218.16  5608.3  220.32  5629.7  216.29
  5645.3  219.82    5842   217.7  6095.7  223.12  6427.8  240.11    6735  263.54
#Mann= 13 ,-1 , 0
  3575.2      .1       0  3889.5     .05       0  4106.5      .1       0
  4590.1     .05       0    4619      .1       0    4997     .07       0
    5003      .1       0  5020.5     .05       0  5063.3      .1       0
  5365.2     .05       0  5481.5      .1       0  6095.7     .05       0
  6427.8      .1       0
Bank Sta=4991.1,5006.1
XS Rating Curve= 0 ,0
Exp/Cntr=0.3,0.1

Type RM Length L Ch R = 1 ,54687   ,402,402,402
BEGIN DESCRIPTION:
SALT BRANCH 75.0
END DESCRIPTION:
XS GIS Cut Line= 2
      2221134.19     13317333.19      2223786.11     13315821.74
#Sta/Elev= 30
  3478.8  243.05  4051.9  228.63  4150.1  227.08  4391.8  224.42  4415.7  224.44
  4980.4  217.59  4990.7  214.23    4997  213.94  4999.8  213.44    5003  213.94
  5017.9   218.3  5039.5  220.46    5077  217.41  5105.7  220.75  5238.3  219.92
  5244.1  216.66  5259.9  215.85  5281.5  218.13    5319  215.87  5324.7  219.44
  5334.8  219.78  5393.6  214.22  5442.9  219.77  5508.7  214.85  5531.7  218.51
  5625.8   216.6  6072.7  237.28  6330.3  256.82  6454.2  274.14  6531.2  275.88
#Mann= 9 ,-1 , 0
  3478.8      .1       0  4051.9     .05       0  4150.1      .1       0
  4391.8     .05       0  4415.7      .1       0  4990.7     .05       0
    4997     .04       0    5003     .05       0  5105.7      .1       0
Bank Sta=4980.4,5017.9
XS Rating Curve= 0 ,0
Exp/Cntr=0.3,0.1

Type RM Length L Ch R = 1 ,54285   ,736,736,736
BEGIN DESCRIPTION:
SALT BRANCH 74.0
END DESCRIPTION:
XS GIS Cut Line= 2
      2221388.46     13317532.42       2223779.5       13316385.
#Sta/Elev= 30
  3573.3  243.04    3750  235.56  3870.8  232.65  3957.2   232.2  4017.7  231.87
  4080.1  226.87  4146.9  223.69  4266.9  221.04  4644.2  219.59  4881.3   220.1
    4921  218.59  4934.8  217.39  4980.1  215.33    4997  211.56  4999.8  211.06
    5003  211.56  5036.6  217.24  5098.9  219.98  5285.6  218.69  5369.4  216.66
  5376.2  214.82  5413.7   214.6  5421.5  211.56  5449.7  215.62  5466.8  215.97
  5489.4  218.79  5681.7  226.07  5979.2  241.65  6119.3  249.99  6225.4  257.65
#Mann= 9 ,-1 , 0
  3573.3      .1       0  3957.2     .05       0  4146.9      .1       0
  4644.2     .05       0    4921      .1       0    4997     .07       0
    5003      .1       0  5979.2     .05       0  6119.3      .1       0
Bank Sta=4934.8,5036.6
XS Rating Curve= 0 ,0
Exp/Cntr=0.3,0.1

Type RM Length L Ch R = 1 ,53549   ,531,531,531
BEGIN DESCRIPTION:
SALT BRANCH 73.0
END DESCRIPTION:
XS GIS Cut Line= 3
      2221687.69     13317896.87      2223287.72     13317246.85
      2223637.69     13317046.87
#Sta/Elev= 30
  3245.3  237.96    3493   225.2  3522.4  222.69  3546.5  222.68  3644.7  219.06
  3707.2  217.61    3742  218.25  3784.8  217.39  4088.2  217.36  4189.2   217.9
  4320.3  216.58  4588.1  218.66  4646.9  217.84  4842.8  218.34  4928.1  215.18
  4957.6  212.16  4980.2  213.12    4986  212.77  4995.4  210.21    4997  208.98
  4999.8  208.48    5003  208.98  5007.6  209.41  5017.7  213.91  5023.4  217.85
  5039.3  221.23    5076  224.77  5104.1  226.28  5119.9  228.32  5375.4  241.92
#Mann= 5 ,-1 , 0
  3245.3      .1       0  4088.2     .05       0  4646.9      .1       0
    4997     .07       0    5003      .1       0
Bank Sta=4980.2,5017.7
XS Rating Curve= 0 ,0
Exp/Cntr=0.3,0.1

Type RM Length L Ch R = 1 ,53018   ,693,693,693
BEGIN DESCRIPTION:
SALT BRANCH 72.0
END DESCRIPTION:
XS GIS Cut Line= 3
      2221737.73     13319296.85      2223337.72     13317746.85
      2223837.73     13317146.84
#Sta/Elev= 30
  2773.7  249.51  2985.8  241.72  3254.6  234.36  3530.4  235.92  3644.3  231.31
  3671.8  228.12  3827.5  220.97  4151.9  215.81  4379.5  214.78  4497.5  215.12
  4635.1  214.92  4767.1  215.63  4909.4  214.61  4930.7  212.41  4937.7  213.71
  4980.1  212.83  4987.3  208.34    4997  207.53  4999.8  207.03    5003  207.53
  5008.5  207.53    5015  209.87  5022.8  209.58  5029.3  212.81  5051.5   213.6
    5058  215.51  5378.2  224.83    5399  227.57  5626.2     239  5782.4   249.7
#Mann= 9 ,-1 , 0
  2773.7      .1       0  3644.3     .05       0  4151.9      .1       0
  4379.5     .05       0  4497.5      .1       0  4635.1     .05       0
  4767.1      .1       0    4997     .07       0    5003      .1       0
Bank Sta=4980.1,5029.3
XS Rating Curve= 0 ,0
Exp/Cntr=0.3,0.1

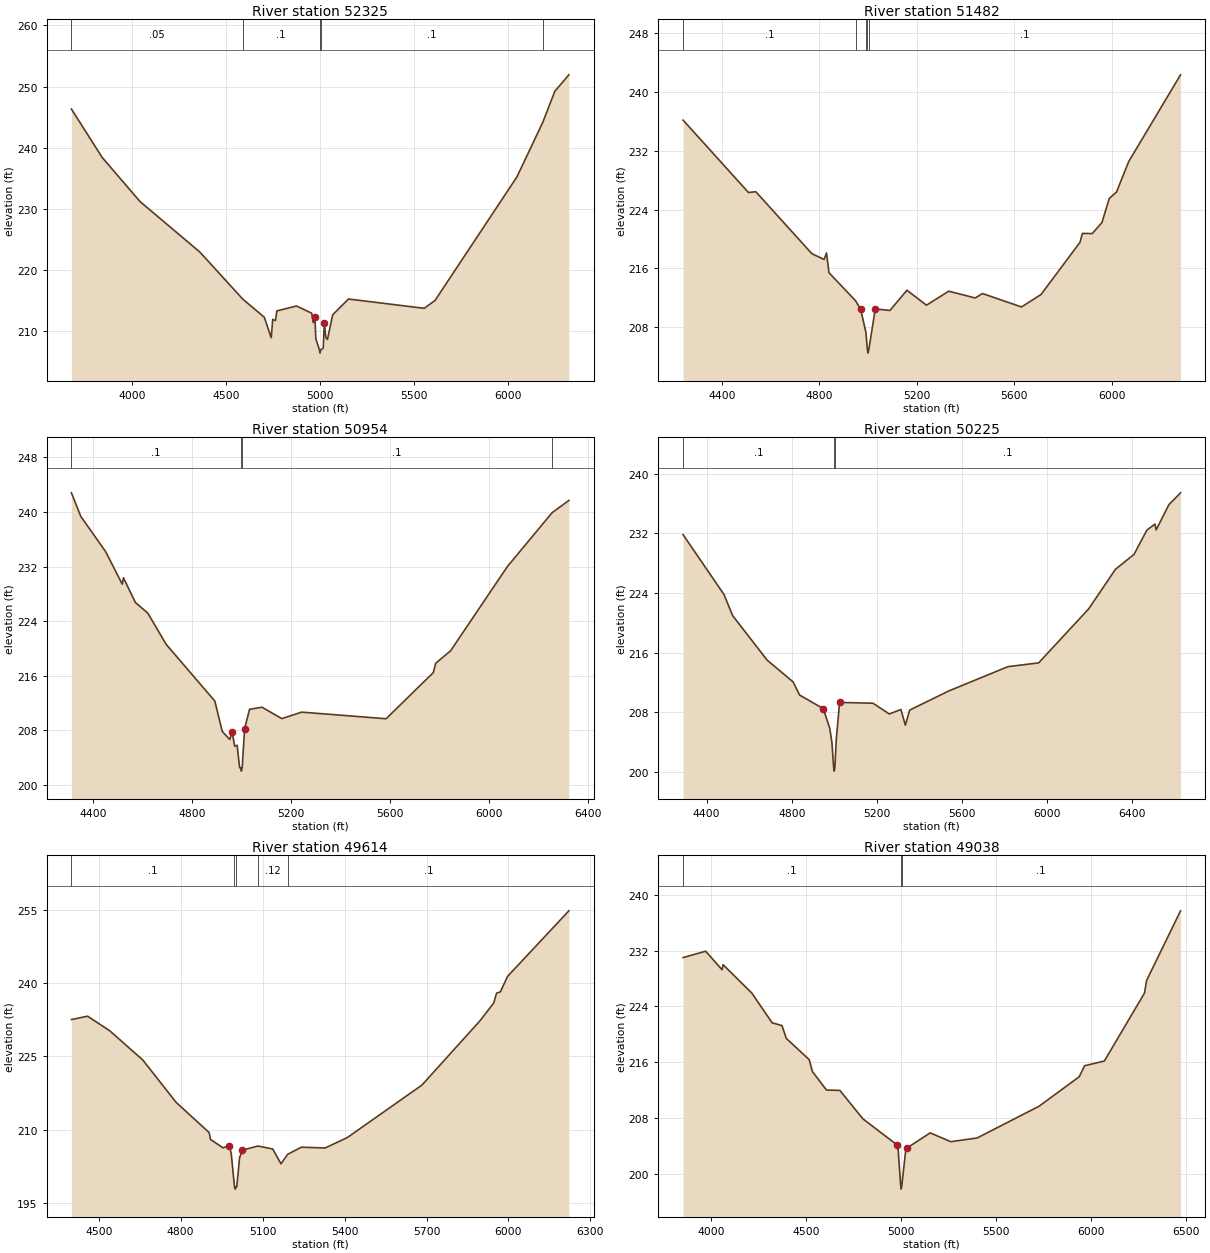
Type RM Length L Ch R = 1 ,52325   ,843,843,843
BEGIN DESCRIPTION:
SALT BRANCH 71.0
END DESCRIPTION:
XS GIS Cut Line= 3
      2223058.06     13319662.38      2223161.12     13318982.19
      2224033.72     13317230.12
#Sta/Elev= 30
  3677.7  246.33  3841.2  238.43  4042.5  231.22  4360.8  222.97  4588.8  215.29
  4703.5  212.32  4740.3  208.98  4748.2  211.97  4762.6  211.77  4770.6  213.36
  4874.3  214.16  4955.3  212.99  4963.7  211.46  4972.1  212.38  4977.7   208.8
    4997  206.96  4999.8  206.46    5003  206.96  5016.9  207.29  5022.5   211.4
  5030.7  209.02  5039.3   208.7  5067.2  212.73  5151.2   215.3  5554.2  213.78
  5611.7  215.08  6046.7  235.24  6184.6  244.18  6248.2  249.22    6323  251.92
#Mann= 5 ,-1 , 0
  3677.7     .05       0  4588.8      .1       0    4997     .07       0
    5003      .1       0  6184.6     .05       0
Bank Sta=4972.1,5022.5
XS Rating Curve= 0 ,0
Exp/Cntr=0.3,0.1

Type RM Length L Ch R = 1 ,51482   ,528,528,528
BEGIN DESCRIPTION:
SALT BRANCH 70.0
END DESCRIPTION:
XS GIS Cut Line= 3
      2224088.68     13319524.98       2224061.2     13318920.35
      2224095.56     13317484.32
#Sta/Elev= 30
  4240.6  236.14    4509  226.31    4539  226.42  4769.3     218  4819.3  217.22
  4829.3   218.1  4839.3  215.42  4948.6  211.61  4969.4  210.43  4990.9  207.34
    4997     205  4999.8   204.5    5003     205  5029.4  210.51  5089.4  210.29
  5159.4  213.04  5239.5  211.01    5331  212.91  5439.5  211.99  5469.5  212.59
  5629.6  210.77  5709.6  212.46  5869.6  219.54  5879.6  220.76  5919.7  220.73
  5959.7  222.23  5989.7  225.49  6019.7  226.39  6069.7  230.52  6282.3  242.29
#Mann= 5 ,-1 , 0
  4240.6      .1       0  4948.6     .07       0  4990.9      .1       0
    4997     .07       0    5003      .1       0
Bank Sta=4969.4,5029.4
XS Rating Curve= 0 ,0
Exp/Cntr=0.3,0.1

Type RM Length L Ch R = 1 ,50954   ,729,729,729
BEGIN DESCRIPTION:
SALT BRANCH 69.0
END DESCRIPTION:
XS GIS Cut Line= 3
      2224624.61     13319394.48      2224535.29     13317841.62
      2224287.92      13317463.7
#Sta/Elev= 30
    4314  242.81  4351.8  239.36  4451.8  234.21    4519  229.42    4524  230.36
    4572  226.74  4622.1  225.18  4696.2   220.6  4892.6  212.29  4922.6  207.84
  4952.7  206.66  4962.7  207.71  4972.7  205.66  4982.7   205.8  4992.7  202.51
    4997  202.51  4999.8  202.01    5003  202.51  5012.8  208.22  5032.8  211.07
  5082.9  211.38    5163  209.71  5243.2  210.66  5583.7  209.69    5774  216.45
    5784  217.83  5844.1  219.66  6073.6  232.03  6253.6   239.9  6321.1  241.69
#Mann= 4 ,-1 , 0
    4314      .1       0    4997     .07       0    5003      .1       0
  6253.6     .05       0
Bank Sta=4962.7,5012.8
XS Rating Curve= 0 ,0
Exp/Cntr=0.3,0.1

Type RM Length L Ch R = 1 ,50225   ,611,611,611
BEGIN DESCRIPTION:
SALT BRANCH 68.0
END DESCRIPTION:
XS GIS Cut Line= 3
      2225318.57     13319236.42      2225057.48     13317731.69
       2224342.9     13317346.92
#Sta/Elev= 30
  4289.3  231.82  4481.7   223.8  4522.3  220.97  4684.7     215  4806.5  212.09
  4836.9  210.33  4948.6   208.5    4979  205.86  4989.2  203.92    4997  200.63
  4999.8  200.13    5003  200.63  5009.5  204.38  5025.1  209.34    5182  209.23
  5258.8  207.79  5313.4  208.39  5334.3  206.29  5354.6  208.31  5537.2  210.86
  5816.4  214.13    5961  214.64  6196.3  221.88    6322  227.18  6409.6  229.19
  6469.7  232.43  6507.8  233.24  6513.5  232.46  6573.5  235.85  6628.1  237.43
#Mann= 3 ,-1 , 0
  4289.3      .1       0    4997     .07       0    5003      .1       0
Bank Sta=4948.6,5025.1
XS Rating Curve= 0 ,0
Exp/Cntr=0.3,0.1

Type RM Length L Ch R = 1 ,49614   ,576,576,576
BEGIN DESCRIPTION:
SALT BRANCH 67.0
END DESCRIPTION:
XS GIS Cut Line= 2
      2225675.85     13318975.36      2225950.69     13317175.12
#Sta/Elev= 30
    4400  232.51  4459.2   233.2  4540.1  230.23  4661.5  224.24  4782.9  215.62
  4904.3  209.41  4909.3  208.01  4954.9  206.31  4977.9  206.72  4985.2  205.09
    4997  198.36  4999.8  197.86    5003  198.36  5005.4  198.36  5015.6  204.25
  5025.7  205.82  5082.7  206.67  5136.9  206.06  5167.3  203.03  5191.7  204.98
  5241.9  206.43  5329.1  206.27  5410.1   208.4  5683.2  219.12  5895.6  232.25
  5946.2  235.92  5956.3   237.9  5970.5  238.18  5996.8  241.34  6221.1  254.73
#Mann= 5 ,-1 , 0
    4400      .1       0    4997     .07       0    5003      .1       0
  5082.7     .12       0  5191.7      .1       0
Bank Sta=4977.9,5025.7
XS Rating Curve= 0 ,0
Exp/Cntr=0.3,0.1

Type RM Length L Ch R = 1 ,49038   ,1288,1288,1288
BEGIN DESCRIPTION:
SALT BRANCH 66.0
END DESCRIPTION:
XS GIS Cut Line= 4
       2225469.7     13319208.94      2226156.81     13318892.86
      2226651.52     13317628.63       2226432.2     13317176.29
#Sta/Elev= 30
  3852.5     231  3971.4  231.91  4057.4  229.26  4062.9  229.98  4213.6  225.93
  4321.1  221.66  4372.6  221.27  4395.5  219.43  4515.9  216.39  4532.8  214.69
  4606.6  212.04  4677.1  211.99  4797.8  207.93  4978.4  204.18  4983.8   203.5
    4997  198.36  4999.8  197.86    5003  198.36  5023.3  203.38  5032.7  203.79
  5152.2  205.91  5260.6  204.65  5399.2  205.18  5724.7  209.72  5936.1  213.94
  5964.7  215.52  6068.4   216.2  6279.3  225.91  6290.7  227.73  6469.1  237.69
#Mann= 3 ,-1 , 0
  3852.5      .1       0    4997     .07       0    5003      .1       0
Bank Sta=4978.4,5032.7
XS Rating Curve= 0 ,0
Exp/Cntr=0.3,0.1