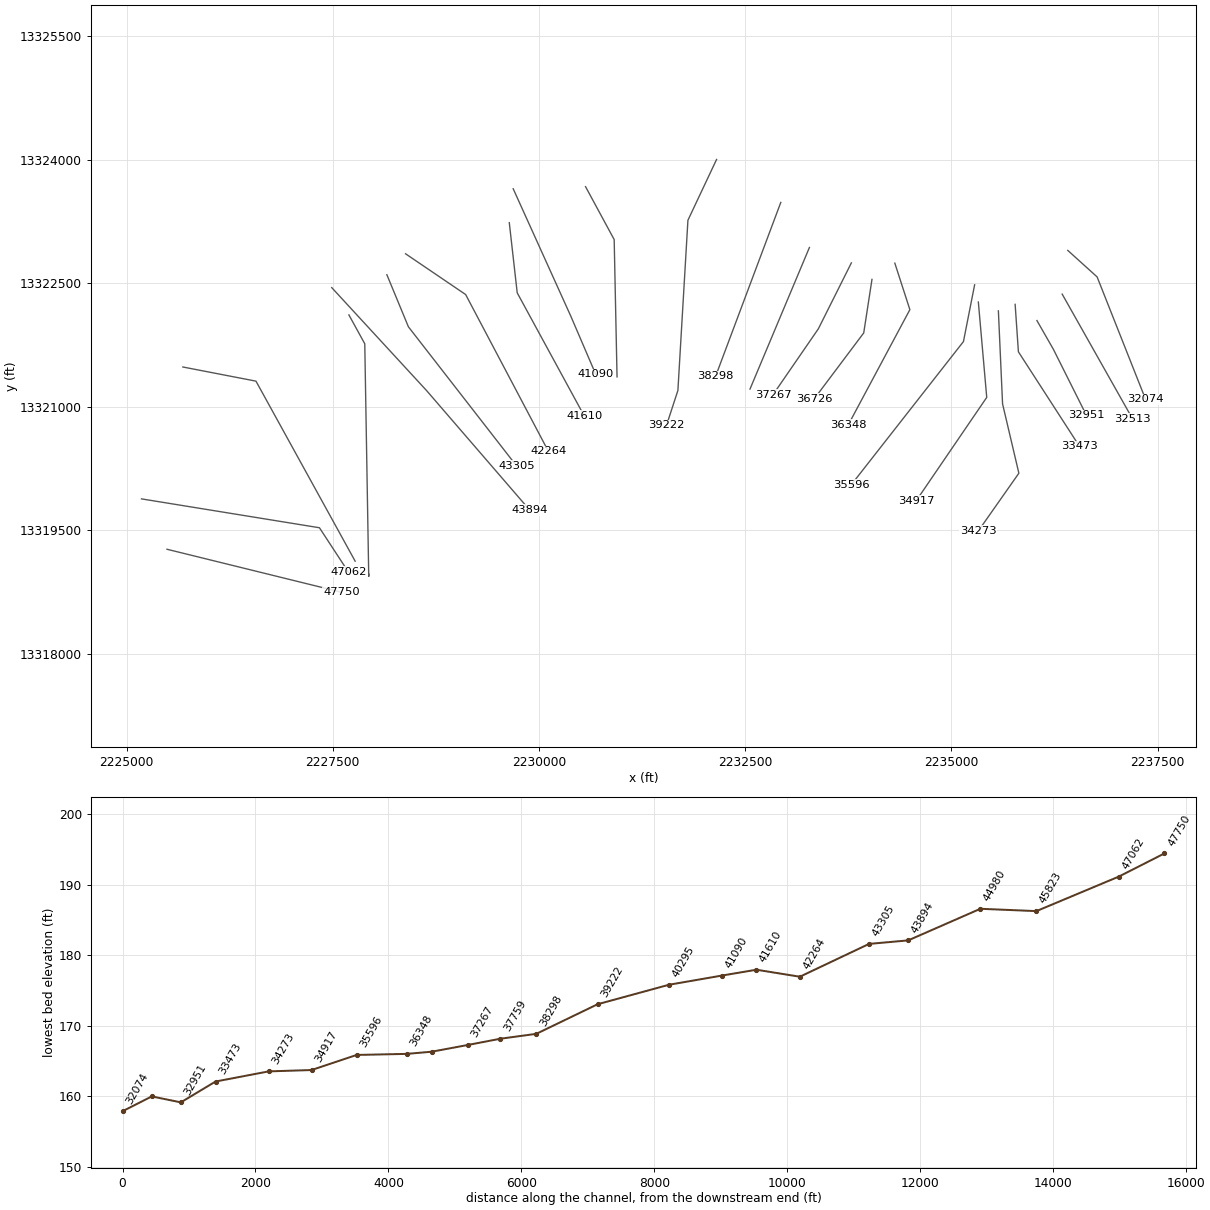
HEC-RAS study SALT BRANCH.prj: SALT BRANCH Base Level Engineering

--- SALT BRANCH.g01 (geometry) --- (continued)

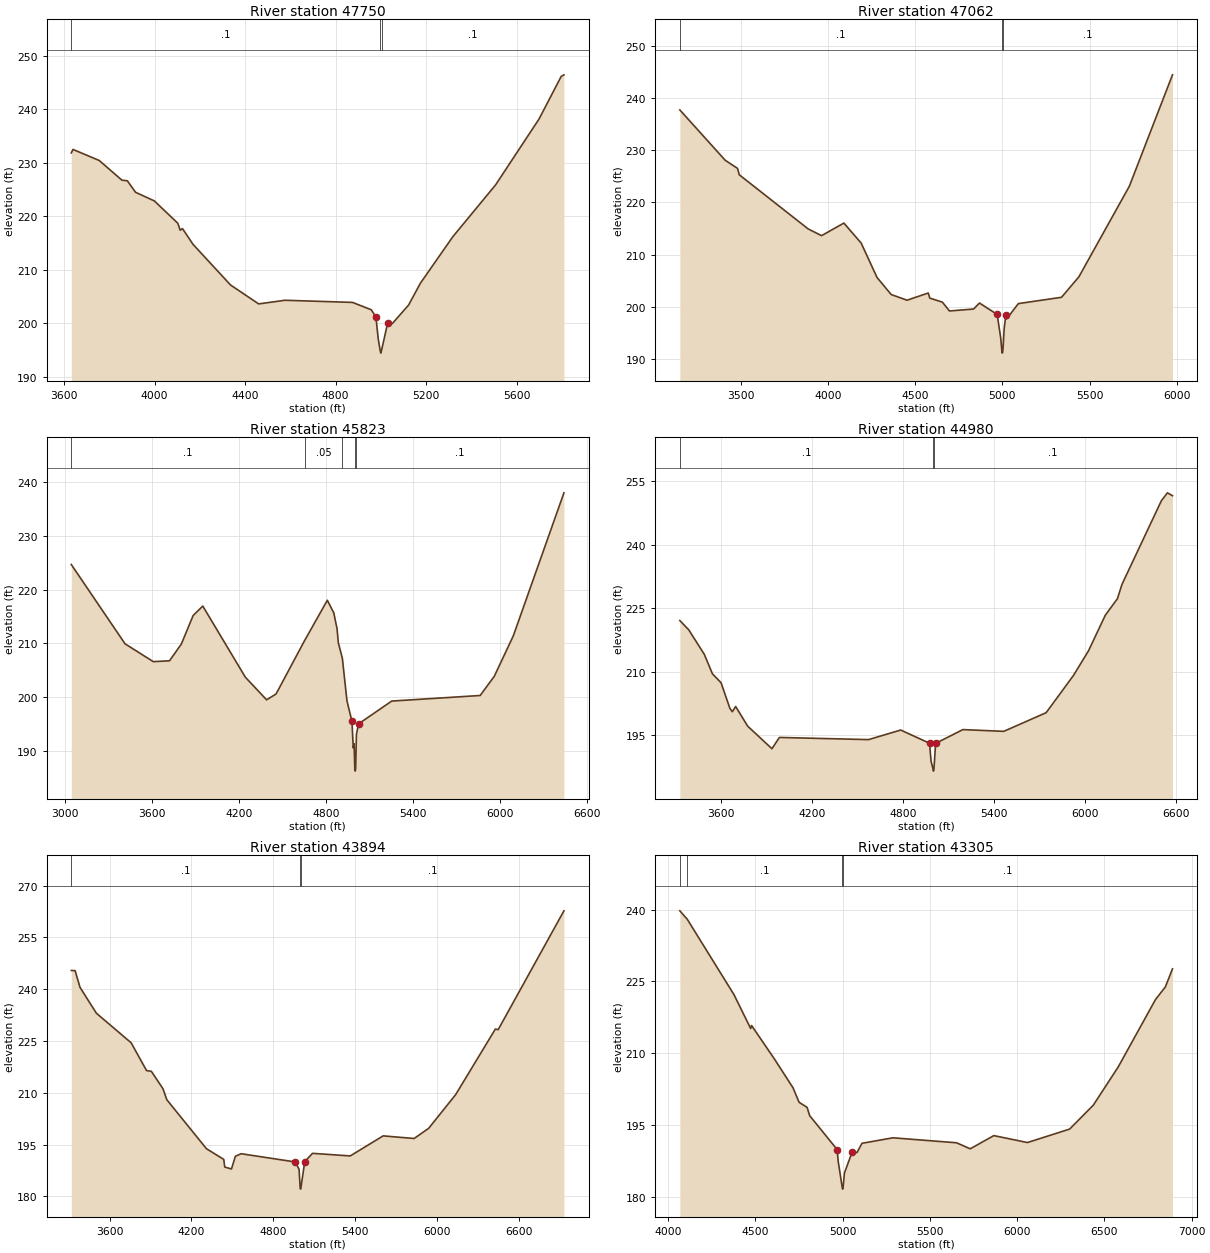
Type RM Length L Ch R = 1 ,47750   ,688,688,688
BEGIN DESCRIPTION:
SALT BRANCH 65.0
END DESCRIPTION:
XS GIS Cut Line= 2
       2225490.3     13319270.77      2227604.68     13318749.04
#Sta/Elev= 30
  3631.6  231.82  3639.2  232.47    3755  230.41  3855.5  226.73  3879.4  226.62
  3915.7  224.47  3998.7  222.86  4102.7  218.68    4113  217.39  4123.1  217.69
  4169.7  214.75  4335.6  207.16    4460  203.63  4576.5  204.31  4874.7  203.91
  4957.6  202.54  4978.2   201.2  4988.5   197.1    4997  194.94  4999.8  194.44
    5003  194.94  5029.7  199.98  5050.9  199.97  5122.4   203.4  5175.3  207.52
  5318.1  216.17  5507.1  225.84  5699.2  238.14  5797.4  246.11  5809.4   246.4
#Mann= 3 ,-1 , 0
  3631.6      .1       0    4997     .07       0    5003      .1       0
Bank Sta=4978.2,5029.7
XS Rating Curve= 0 ,0
Exp/Cntr=0.3,0.1

Type RM Length L Ch R = 1 ,47062   ,1239,1239,1239
BEGIN DESCRIPTION:
SALT BRANCH 64.0
END DESCRIPTION:
XS GIS Cut Line= 3
      2225181.16     13319882.27       2227338.6     13319531.85
        2227689.     13318995.95
#Sta/Elev= 30
  3149.9  237.71  3409.8  228.08  3480.7  226.52  3490.9  225.29    3886  214.93
  3962.7  213.64  4090.9  216.05  4189.9  212.22  4281.1  205.63  4362.1  202.37
  4453.3  201.28  4574.9  202.66  4583.5  201.69  4655.9  200.91  4696.5  199.22
  4834.9  199.59  4868.7  200.74    4970  198.56  4990.3  194.11    4997  191.65
  4999.8  191.15    5003  191.65  5010.5  195.89  5019.7  198.46  5024.7   197.7
  5091.6  200.63  5339.4  201.84  5438.8  205.75  5728.4   223.1  5975.9  244.43
#Mann= 3 ,-1 , 0
  3149.9      .1       0    4997     .07       0    5003      .1       0
Bank Sta=4970,5019.7
XS Rating Curve= 0 ,0
Exp/Cntr=0.3,0.1

Type RM Length L Ch R = 1 ,45823   ,843,843,843
BEGIN DESCRIPTION:
SALT BRANCH 62.0
END DESCRIPTION:
XS GIS Cut Line= 3
      2225682.73     13321483.18      2226569.07     13321311.41
      2227771.49     13319126.44
#Sta/Elev= 30
  3042.2  224.66    3413  209.92  3607.5  206.61  3719.6  206.77  3801.1  209.89
  3882.5  215.19  3948.8  216.94  4242.1  203.73  4388.9  199.51  4454.3  200.61
  4650.8  210.52  4807.5  218.02    4852  215.68  4874.8  212.71  4883.2  210.15
  4911.2  207.24  4942.9  199.33  4977.5  195.49  4986.4  190.59  4992.2  191.35
    4997  186.76  4999.8  186.26    5003  186.76  5008.2  193.12  5023.2  195.05
  5251.4  199.28  5861.5  200.32    5959   203.9  6089.7  211.39    6439  237.99
#Mann= 5 ,-1 , 0
  3042.2      .1       0  4650.8     .05       0  4911.2      .1       0
    4997     .07       0    5003      .1       0
Bank Sta=4977.5,5023.2
XS Rating Curve= 0 ,0
Exp/Cntr=0.3,0.1

Type RM Length L Ch R = 1 ,44980   ,1086,1086,1086
BEGIN DESCRIPTION:
SALT BRANCH 61.0
END DESCRIPTION:
XS GIS Cut Line= 4
      2227695.89      13322115.3      2227888.27     13321764.89
      2227936.37     13318940.96      2227936.37     13318968.48
#Sta/Elev= 30
  3325.9  222.13  3384.3  219.96  3487.5  214.14  3540.9  209.56  3597.9  207.46
  3656.2  201.41  3672.3  200.61  3694.1  201.85  3773.7   197.2  3933.7  191.88
  3982.8  194.54  4571.4  194.03  4783.8  196.29  4973.9  193.17  4983.9  188.94
    4997  187.09  4999.8  186.59    5003  187.09  5013.9  193.13  5193.9  196.39
  5463.9  195.98  5743.8  200.39    5924  209.18    6024  215.05    6134  223.39
    6214  227.29    6244  230.67  6504.1  250.41  6544.1  252.28  6577.5   251.6
#Mann= 3 ,-1 , 0
  3325.9      .1       0    4997     .07       0    5003      .1       0
Bank Sta=4973.9,5013.9
XS Rating Curve= 0 ,0
Exp/Cntr=0.3,0.1

Type RM Length L Ch R = 1 ,43894   ,589,589,589
BEGIN DESCRIPTION:
SALT BRANCH 59.0
END DESCRIPTION:
XS GIS Cut Line= 3
       2227487.7     13322446.88      2228637.72     13321196.85
      2229887.73     13319746.84
#Sta/Elev= 30
  3318.6  245.42  3346.7  245.37  3382.4  240.54  3502.7  233.04  3757.3  224.49
  3870.7  216.43  3905.9  216.22    3991  211.18  4019.3  207.99  4309.7  193.82
  4436.7  190.72  4444.1   188.5  4493.4  187.95  4521.8  191.62  4564.3  192.36
  4960.7  189.98  4989.1  187.86    4997  182.61  4999.8  182.11    5003  182.61
  5030.9  190.09  5087.9  192.47  5364.4  191.72  5605.7  197.53  5832.8  196.77
  5939.3   199.7  6137.8  209.49  6428.6  228.45  6449.4  228.29  6931.6  262.69
#Mann= 3 ,-1 , 0
  3318.6      .1       0    4997     .07       0    5003      .1       0
Bank Sta=4960.7,5030.9
XS Rating Curve= 0 ,0
Exp/Cntr=0.3,0.1

Type RM Length L Ch R = 1 ,43305   ,1041,1041,1041
BEGIN DESCRIPTION:
SALT BRANCH 58.0
END DESCRIPTION:
XS GIS Cut Line= 3
      2228156.25      13322603.1      2228417.33     13321971.01
      2229729.25     13320281.31
#Sta/Elev= 30
  4067.1  239.74  4109.6  237.98  4377.2  222.24  4472.9  215.16  4478.3  215.78
  4608.7  208.81  4715.2   202.8  4750.5  199.75  4796.5  198.68    4811  196.96
  4968.4  189.88  4974.8  187.34    4997  182.11  4999.8  181.61    5003  182.11
  5010.1  184.96  5053.5  189.27  5082.5  189.27  5110.7  191.18    5288  192.33
  5652.7  191.29  5731.1  190.03  5866.3  192.79  6059.1  191.34  6300.8  194.15
  6436.5  199.15  6579.3  207.14  6793.1  221.23  6849.2  223.84  6890.2  227.62
#Mann= 4 ,-1 , 0
  4067.1     .05       0  4109.6      .1       0    4997     .07       0
    5003      .1       0
Bank Sta=4968.4,5053.5
XS Rating Curve= 0 ,0
Exp/Cntr=0.3,0.1

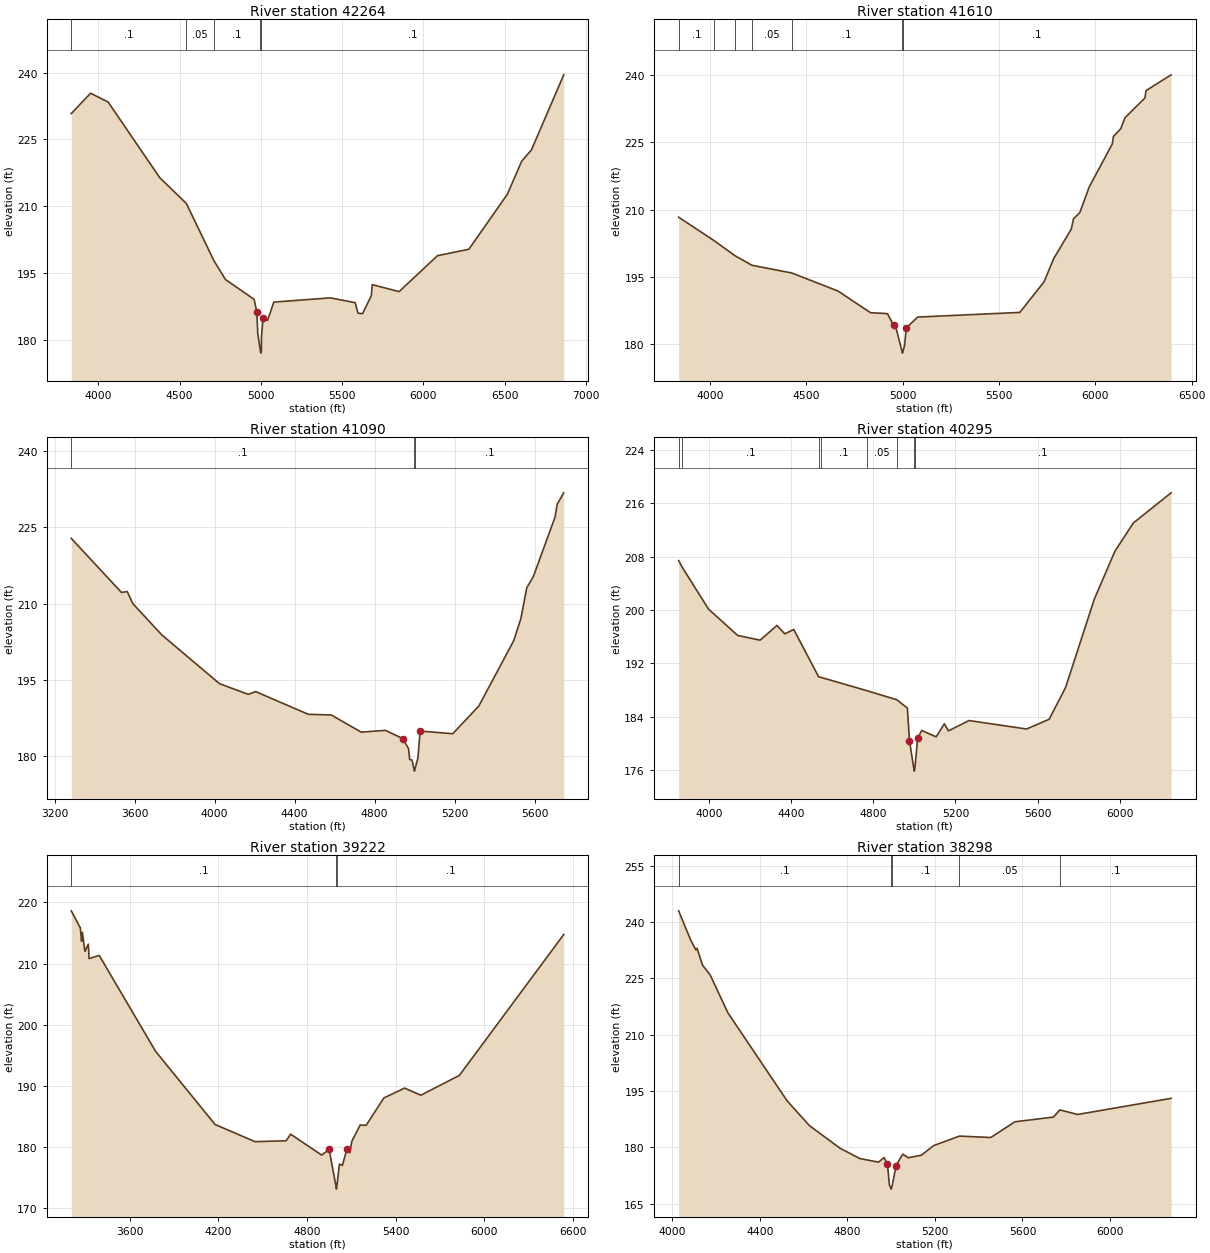
Type RM Length L Ch R = 1 ,42264   ,654,654,654
BEGIN DESCRIPTION:
SALT BRANCH 57.0
END DESCRIPTION:
XS GIS Cut Line= 3
      2228382.95     13322857.37      2229111.29     13322362.65
      2230112.95     13320462.24
#Sta/Elev= 30
  3833.9  230.79  3952.5  235.36  4060.3  233.39  4377.6   216.4  4541.6  210.59
  4710.7  197.76  4782.4  193.49  4958.7  189.04    4975  186.14  4980.9  181.32
    4997  177.46  4999.8  176.96    5003  177.46  5003.5  180.71  5013.4  184.84
  5041.1  184.34  5079.5  188.42  5426.3  189.38  5580.5  188.29  5596.9  185.94
  5625.2  185.82  5679.3  189.88    5685  192.35  5849.9  190.78  6086.5  198.86
  6279.1   200.3  6515.8  212.66  6603.9  220.07  6664.3  222.65  6862.6  239.49
#Mann= 5 ,-1 , 0
  3833.9      .1       0  4541.6     .05       0  4710.7      .1       0
    4997     .07       0    5003      .1       0
Bank Sta=4975,5013.4
XS Rating Curve= 0 ,0
Exp/Cntr=0.3,0.1

Type RM Length L Ch R = 1 ,41610   ,520,520,520
BEGIN DESCRIPTION:
SALT BRANCH 55.0
END DESCRIPTION:
XS GIS Cut Line= 3
      2229640.34     13323235.25      2229736.53     13322383.26
      2230547.32     13320892.25
#Sta/Elev= 30
  3838.7   208.3  4022.1  203.08  4130.8   199.7  4219.3  197.56  4425.8  195.84
  4664.7  191.83  4834.5  186.97  4921.9  186.77  4953.8  184.15  4965.6   183.7
    4997  178.45  4999.8  177.95    5003  178.45  5010.7  179.68  5019.7   183.6
    5079     186  5608.7  187.04  5734.1  193.85  5784.8  199.09  5875.7  205.65
  5887.2  207.96  5919.4  209.29  5968.8  215.06  6088.5  224.67  6094.2  226.32
  6132.2  228.05  6154.1   230.5  6257.6  234.91  6263.3  236.55  6393.3  240.08
#Mann= 7 ,-1 , 0
  3838.7      .1       0  4022.1     .05       0  4130.8      .1       0
  4219.3     .05       0  4425.8      .1       0    4997     .07       0
    5003      .1       0
Bank Sta=4953.8,5019.7
XS Rating Curve= 0 ,0
Exp/Cntr=0.3,0.1

Type RM Length L Ch R = 1 ,41090   ,795,795,795
BEGIN DESCRIPTION:
SALT BRANCH 54.0
END DESCRIPTION:
XS GIS Cut Line= 3
       2229687.7     13323646.89      2230387.72     13322096.85
      2230687.74     13321396.81
#Sta/Elev= 30
  3283.8  222.79  3534.8  212.19  3563.4  212.37    3592  209.97  3736.3  203.86
  4024.7  194.29  4168.9  192.19  4205.5  192.73  4468.9  188.27  4583.9  188.14
  4733.6  184.77  4854.7  185.12  4940.7  183.52  4970.3  181.53  4975.8  179.41
  4987.3   179.3    4997  177.62  4999.8  177.12    5003  177.62  5017.2  179.71
  5028.1  184.98  5191.3  184.46  5321.8  189.91  5495.9  202.71  5532.2  207.11
  5561.2   213.1  5593.8  215.26  5702.6  226.96  5713.5  229.51  5746.2  231.74
#Mann= 3 ,-1 , 0
  3283.8      .1       0    4997     .07       0    5003      .1       0
Bank Sta=4940.7,5028.1
XS Rating Curve= 0 ,0
Exp/Cntr=0.3,0.1

Type RM Length L Ch R = 1 ,40295   ,1073,1073,1073
BEGIN DESCRIPTION:
Mapping XS 3f760ebf
END DESCRIPTION:
XS GIS Cut Line= 3
      2230564.89     13323672.39      2230912.12     13323030.02
      2230946.84     13321363.39
#Sta/Elev= 30
  3852.7  207.42  3869.5  206.45  3998.2  200.13    4140  196.18  4249.4  195.47
  4331.3  197.68  4369.4  196.42  4413.1  197.07  4534.4  189.96  4544.2   189.9
  4771.3  187.87    4915  186.53  4966.2  185.28  4976.2   180.4    4997  176.32
  4999.8  175.82    5003  176.32  5016.2  180.79  5036.2  181.92  5106.2  180.96
  5146.2  182.92  5166.2  181.86  5266.2  183.41  5546.3  182.14  5656.3   183.6
  5736.3  188.37  5876.4  201.65  5976.4  208.81  6066.4  213.06  6249.9  217.58
#Mann= 8 ,-1 , 0
  3852.7     .05       0  3869.5      .1       0  4534.4     .05       0
  4544.2      .1       0  4771.3     .05       0    4915      .1       0
    4997     .07       0    5003      .1       0
Bank Sta=4976.2,5016.2
XS Rating Curve= 0 ,0
Exp/Cntr=0.3,0.1

Type RM Length L Ch R = 1 ,39222   ,924,924,924
BEGIN DESCRIPTION:
SALT BRANCH 52.0
END DESCRIPTION:
XS GIS Cut Line= 4
      2232153.45     13324002.27      2231806.22     13323264.39
      2231684.69     13321198.42       2231545.8     13320773.07
#Sta/Elev= 30
  3205.7  218.63  3266.9  215.83  3275.2  213.65  3280.7  215.11    3298  211.98
  3320.8  213.17  3326.3  210.81  3394.7  211.33    3776  195.63    4179  183.64
  4449.5  180.83  4659.8  180.98  4689.9  182.06  4900.3  178.63  4950.3  179.58
    4997  173.56  4999.8  173.06    5003  173.56  5020.5  177.16  5040.5  176.94
  5070.5  179.59  5090.6  179.02    5104  180.88  5160.7  183.56  5200.8   183.5
    5321  187.99  5461.2   189.6  5571.4  188.44  5831.9  191.68  6538.2  214.75
#Mann= 3 ,-1 , 0
  3205.7      .1       0    4997     .07       0    5003      .1       0
Bank Sta=4950.3,5070.5
XS Rating Curve= 0 ,0
Exp/Cntr=0.3,0.1

Type RM Length L Ch R = 1 ,38298   ,539,539,539
BEGIN DESCRIPTION:
Mapping XS dda8e61b
END DESCRIPTION:
XS GIS Cut Line= 2
      2232932.12     13323480.95      2232142.52     13321372.45
#Sta/Elev= 30
  4028.1  243.01    4082  235.39  4106.9  232.58  4112.3  233.05  4137.2  228.54
  4172.8  225.88  4252.9  215.87  4523.7  192.41  4625.2  185.83  4765.9  179.76
  4856.7     177  4942.2  176.05  4967.1  177.27  4982.8  175.53    4992  169.85
    4997  169.36  4999.8  168.86    5003  169.36  5022.3  175.14  5052.6  178.19
  5077.5  177.22  5138.1   177.9  5193.3  180.44  5312.1  182.99  5455.1  182.61
  5565.5   186.8  5741.8  188.06  5770.9  189.97  5852.2  188.75  6279.6  193.05
#Mann= 5 ,-1 , 0
  4028.1      .1       0    4997     .07       0    5003      .1       0
  5312.1     .05       0  5770.9      .1       0
Bank Sta=4982.8,5022.3
XS Rating Curve= 0 ,0
Exp/Cntr=0.3,0.1

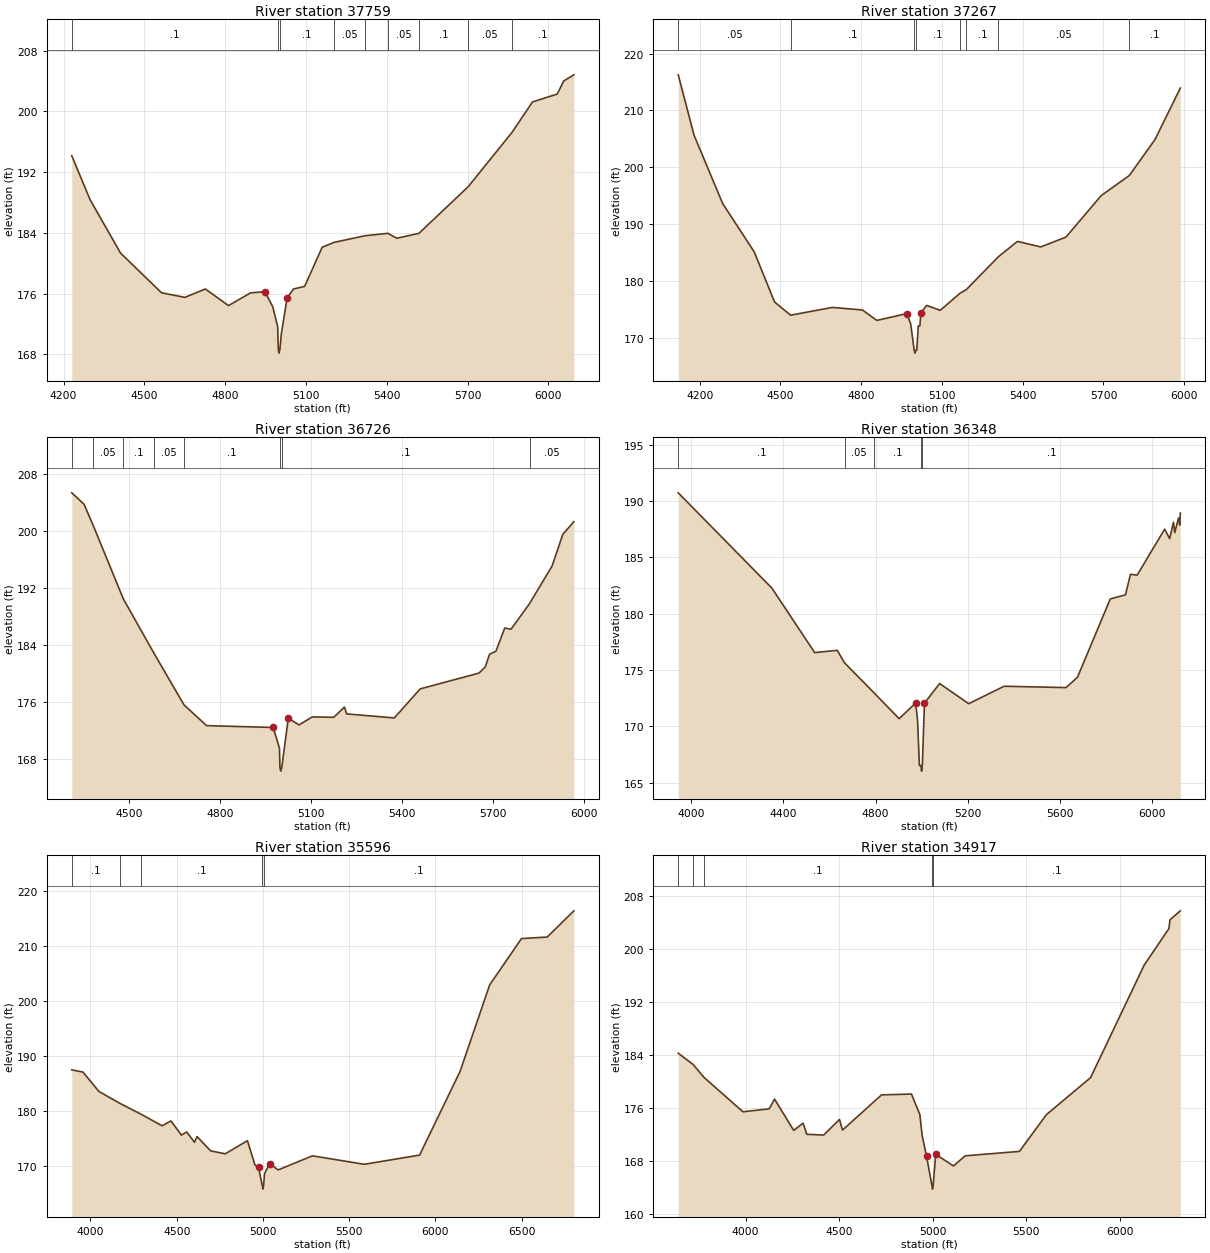
Type RM Length L Ch R = 1 ,37759   ,492,492,492
BEGIN DESCRIPTION:
Mapping XS bab9723a
END DESCRIPTION:
XS GIS Cut Line= 2
      2233279.36     13322934.11      2232558.86     13321215.32
#Sta/Elev= 30
  4230.4  194.16  4298.6  188.36  4411.8  181.33  4563.6  176.12  4650.3  175.51
  4726.2  176.62  4812.1  174.43  4894.3  176.11  4947.2  176.25  4976.4  174.29
  4994.8  171.67    4997  168.67  4999.8  168.17    5003  168.67  5008.1  170.66
  5029.8  175.45  5053.2  176.61  5094.9  176.96  5159.9  182.12  5204.8  182.76
  5317.4  183.62  5403.6  183.95  5436.9   183.3  5518.9  183.94    5702  190.09
  5864.8  197.25  5940.6  201.25  6032.6  202.29  6056.4  204.01  6094.1  204.82
#Mann= 9 ,-1 , 0
  4230.4      .1       0    4997     .07       0    5003      .1       0
  5204.8     .05       0  5317.4      .1       0  5403.6     .05       0
  5518.9      .1       0    5702     .05       0  5864.8      .1       0
Bank Sta=4947.2,5029.8
XS Rating Curve= 0 ,0
Exp/Cntr=0.3,0.1

Type RM Length L Ch R = 1 ,37267   ,541,541,541
BEGIN DESCRIPTION:
SALT BRANCH 48.0
END DESCRIPTION:
XS GIS Cut Line= 3
      2233787.73     13322746.88      2233387.72     13321946.85
      2232837.71     13321146.84
#Sta/Elev= 30
  4120.3  216.28    4179  205.67  4285.2  193.63  4402.6  185.11  4478.1  176.29
  4537.8  173.96  4693.3  175.33  4805.1  174.87  4858.2  173.04    4970  174.25
    4984   172.4    4997  167.78  4999.8  167.28    5003  167.78  5006.4  167.78
    5012  172.07  5017.8  172.07  5022.2  174.39  5043.2  175.68  5093.9  174.82
  5167.2  177.83  5190.6  178.46  5309.5  184.24  5380.7  186.95  5467.3  185.98
  5560.8  187.71  5691.3     195  5796.1  198.55  5891.5  204.88  5985.6  213.95
#Mann= 8 ,-1 , 0
  4120.3     .05       0  4537.8      .1       0    4997     .07       0
    5003      .1       0  5167.2     .05       0  5190.6      .1       0
  5309.5     .05       0  5796.1      .1       0
Bank Sta=4970,5022.2
XS Rating Curve= 0 ,0
Exp/Cntr=0.3,0.1

Type RM Length L Ch R = 1 ,36726   ,378,378,378
BEGIN DESCRIPTION:
SALT BRANCH 47.0
END DESCRIPTION:
XS GIS Cut Line= 3
      2234037.72     13322546.87      2233937.72     13321896.85
       2233337.7     13321096.83
#Sta/Elev= 30
  4309.7  205.35  4350.2  203.75  4379.3   200.9  4479.7   190.5    4580  182.94
  4680.4  175.61  4754.9  172.71  4974.7  172.45  4995.5  169.54    4997  166.83
  4999.8  166.33    5003  166.83  5024.7  173.76  5060.1  172.81  5103.8  173.93
  5174.7  173.88  5210.1  175.31  5217.4  174.35  5374.7  173.79  5460.1  177.86
  5653.8  180.07  5674.7  180.92  5689.2  182.72  5710.1  183.14  5739.2  186.39
  5760.1  186.23    5821  189.81  5895.5  195.08  5930.9  199.52  5967.4  201.31
#Mann= 8 ,-1 , 0
  4309.7      .1       0  4379.3     .05       0  4479.7      .1       0
    4580     .05       0  4680.4      .1       0    4997     .07       0
    5003      .1       0    5821     .05       0
Bank Sta=4974.7,5024.7
XS Rating Curve= 0 ,0
Exp/Cntr=0.3,0.1

Type RM Length L Ch R = 1 ,36348   ,752,752,752
BEGIN DESCRIPTION:
SALT BRANCH 46.0
END DESCRIPTION:
XS GIS Cut Line= 3
      2234314.91     13322743.53      2234497.19     13322179.32
       2233750.7     13320781.83
#Sta/Elev= 30
  3944.5  190.74  4350.9  182.27  4536.1  176.55  4634.2  176.75  4665.6  175.64
  4793.4  172.98  4902.5  170.68    4974  172.07  4982.4  170.55  4990.3  166.52
    4997  166.52  4999.8  166.02    5003  166.52  5012.3  172.06  5078.1   173.8
  5204.2  172.01  5357.8  173.56  5626.1  173.44  5675.7  174.35    5818  181.31
  5883.9  181.68  5905.8   183.5  5934.7  183.43  6053.8  187.51  6075.7  186.67
    6092  188.13  6097.7   187.2    6114  188.51  6119.6  187.87  6121.8  188.94
#Mann= 5 ,-1 , 0
  3944.5      .1       0  4665.6     .05       0  4793.4      .1       0
    4997     .07       0    5003      .1       0
Bank Sta=4974,5012.3
XS Rating Curve= 0 ,0
Exp/Cntr=0.3,0.1

Type RM Length L Ch R = 1 ,35596   ,679,679,679
BEGIN DESCRIPTION:
Mapping XS ccd08557
END DESCRIPTION:
XS GIS Cut Line= 3
      2235282.25     13322480.76      2235146.72     13321791.81
      2233785.85     13320052.61
#Sta/Elev= 30
  3891.5  187.54  3956.6  187.13    4049  183.61  4171.7  181.43  4293.2  179.48
  4415.3  177.37  4466.2  178.26  4527.4  175.68  4557.7  176.25  4603.2  174.38
  4617.7  175.42  4696.3  172.82  4781.4  172.29  4909.8  174.67  4953.1  170.27
    4974  169.81    4997  166.37  4999.8  165.87    5003  166.37  5009.2  168.67
  5038.1  170.51  5087.9  169.36  5286.8  171.92    5587  170.38  5907.8  172.05
  6142.2  187.23    6314  202.96  6498.5  211.38  6647.7  211.66    6802  216.42
#Mann= 5 ,-1 , 0
  3891.5      .1       0  4171.7     .05       0  4293.2      .1       0
    4997     .07       0    5003      .1       0
Bank Sta=4974,5038.1
XS Rating Curve= 0 ,0
Exp/Cntr=0.3,0.1

Type RM Length L Ch R = 1 ,34917   ,644,644,644
BEGIN DESCRIPTION:
SALT BRANCH 45.0
END DESCRIPTION:
XS GIS Cut Line= 3
      2235327.42     13322271.76      2235429.06      13321114.2
      2234571.74     13319856.41
#Sta/Elev= 30
  3640.3  184.26  3718.8  182.58  3779.3  180.57  3986.5  175.41  4127.1  175.86
  4155.2  177.33  4257.6   172.6  4307.8  173.69  4327.8  172.01  4418.2   171.9
  4502.3  174.25  4518.6  172.65  4727.1  177.96  4887.2  178.09    4932     175
  4944.3  171.85  4967.9  168.69    4997  164.23  4999.8  163.73    5003  164.23
  5016.9  168.99  5111.6  167.23  5174.5  168.76  5464.6  169.43  5608.2  174.97
  5844.6  180.56  6131.9  197.59  6263.4  203.07  6269.5  204.42  6324.5  205.76
#Mann= 5 ,-1 , 0
  3640.3      .1       0  3718.8     .05       0  3779.3      .1       0
    4997     .07       0    5003      .1       0
Bank Sta=4967.9,5016.9
XS Rating Curve= 0 ,0
Exp/Cntr=0.3,0.1

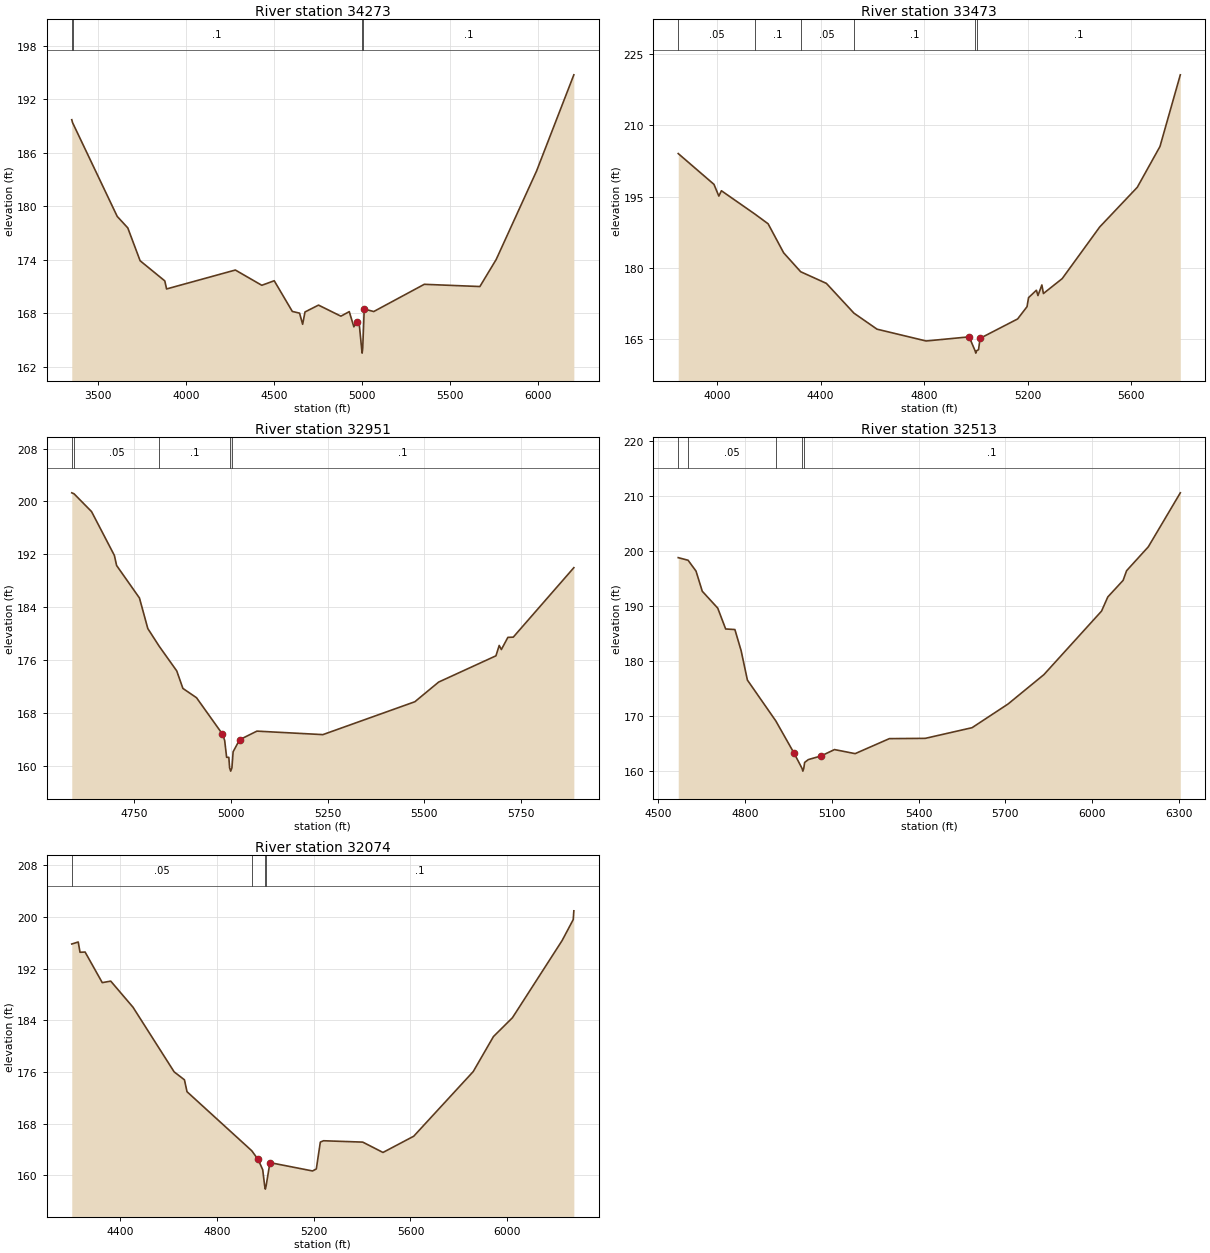
Type RM Length L Ch R = 1 ,34273   ,800,800,800
BEGIN DESCRIPTION:
Mapping XS ea9b0a17
END DESCRIPTION:
XS GIS Cut Line= 4
      2235570.23     13322164.49      2235621.05     13321035.14
      2235818.69     13320193.77      2235327.43     13319493.58
#Sta/Elev= 30
  3351.5  189.69  3356.1  189.36  3609.4  178.86  3669.5  177.57  3739.5  173.89
  3879.7  171.63  3889.7  170.73  4280.1  172.85  4430.2  171.14  4500.8  171.65
  4603.5  168.21  4644.6  168.02  4662.1  166.77  4675.4  168.15  4752.1  168.92
  4879.3  167.68  4926.8  168.19  4952.8  166.49  4969.2  166.99  4983.6  166.76
    4997  164.04  4999.8  163.54    5003  164.04  5011.7  168.48  5065.7   168.2
  5352.6  171.25  5668.1     171  5760.5  174.02  5989.9  183.94  6201.6  194.72
#Mann= 4 ,-1 , 0
  3351.5     .05       0  3356.1      .1       0    4997     .07       0
    5003      .1       0
Bank Sta=4969.2,5011.7
XS Rating Curve= 0 ,0
Exp/Cntr=0.3,0.1

Type RM Length L Ch R = 1 ,33473   ,522,522,522
BEGIN DESCRIPTION:
SALT BRANCH 44.0
END DESCRIPTION:
XS GIS Cut Line= 3
      2235773.52     13322243.51      2235813.04     13321667.58
      2236552.58     13320521.57
#Sta/Elev= 30
  3849.3  204.02  3987.5  197.55  4006.3  195.09  4016.3  196.21  4145.2  191.33
  4196.8  189.27  4256.9  183.17  4322.6   179.2  4422.1  176.75  4528.6   170.5
  4617.9  167.13  4807.8  164.65  4974.1  165.52    4997   162.6  4999.8   162.1
    5003   162.6  5010.4  162.83  5016.4  165.21  5161.5  169.28  5197.8  171.85
  5203.8  173.76  5234.1  175.31  5240.1  174.19  5255.3  176.42  5261.2  174.62
  5333.8  177.75    5479  188.61  5624.2  196.94  5711.9  205.51  5790.5  220.56
#Mann= 6 ,-1 , 0
  3849.3     .05       0  4145.2      .1       0  4322.6     .05       0
  4528.6      .1       0    4997     .07       0    5003      .1       0
Bank Sta=4974.1,5016.4
XS Rating Curve= 0 ,0
Exp/Cntr=0.3,0.1

Type RM Length L Ch R = 1 ,32951   ,438,438,438
BEGIN DESCRIPTION:
SALT BRANCH 43.0
END DESCRIPTION:
XS GIS Cut Line= 3
      2236037.74     13322046.82      2236237.72     13321696.85
      2236637.72     13320896.85
#Sta/Elev= 30
  4589.1  201.31    4595  201.16  4640.2  198.47  4699.2  191.83    4705   190.3
    4764  185.38  4785.6  180.75  4814.9  178.08  4860.4  174.33  4876.3  171.68
  4911.5  170.27  4978.5  164.76  4984.2  163.81  4989.3  161.24    4995  161.24
    4997  159.65  4999.8  159.15    5003  159.65  5006.1  162.09  5022.9  163.91
  5067.6  165.21  5238.1  164.68  5475.7  169.66  5537.2  172.64  5685.3  176.62
  5693.7  178.19  5699.3  177.57  5716.1  179.41  5730.1  179.45  5886.6  189.97
#Mann= 5 ,-1 , 0
  4589.1      .1       0    4595     .05       0  4814.9      .1       0
    4997     .07       0    5003      .1       0
Bank Sta=4978.5,5022.9
XS Rating Curve= 0 ,0
Exp/Cntr=0.3,0.1

Type RM Length L Ch R = 1 ,32513   ,439,439,439
BEGIN DESCRIPTION:
SALT BRANCH 42.0
END DESCRIPTION:
XS GIS Cut Line= 2
      2236343.82      13322367.8      2237196.48     13320854.48
#Sta/Elev= 30
  4568.7  198.81  4602.7  198.34  4630.2  196.37  4651.9   192.7  4705.4  189.63
  4732.8  185.84  4764.7  185.74  4786.3  181.89    4808  176.55  4906.4  169.11
  4969.8  163.22    4997  160.49  4999.8  159.99    5003  160.49    5006  161.57
  5018.9  162.09  5063.3  162.76  5109.3  163.91  5180.7  163.17  5299.2   165.9
  5423.5  165.95  5585.3  167.89  5709.6  172.19  5833.8  177.54  6033.2  189.09
  6054.9  191.67  6107.8  194.68  6119.9  196.44  6195.1  200.79  6305.7   210.6
#Mann= 5 ,-1 , 0
  4568.7      .1       0  4602.7     .05       0  4906.4      .1       0
    4997     .07       0    5003      .1       0
Bank Sta=4969.8,5063.3
XS Rating Curve= 0 ,0
Exp/Cntr=0.3,0.1

Type RM Length L Ch R = 1 ,32074   ,648,648,648
BEGIN DESCRIPTION:
SALT BRANCH 41.0
END DESCRIPTION:
XS GIS Cut Line= 3
      2236411.56     13322898.61      2236767.34     13322576.71
      2237354.58     13321091.69
#Sta/Elev= 30
  4199.1  195.79  4225.8   196.1  4233.3  194.51  4254.2  194.55  4325.2  189.82
  4360.3  190.05  4452.3  186.02  4622.6  176.02  4665.2  174.79  4675.8  172.95
  4943.4  163.83  4969.9  162.48  4988.9  160.89    4997  158.39  4999.8  157.89
    5003  158.39  5018.7  161.99  5194.9   160.7  5210.6  161.01  5227.2  165.16
  5240.3  165.37  5402.6  165.16  5486.4  163.56  5613.5  166.07  5859.5  176.06
  5943.3  181.48  6021.8  184.39  6227.2  196.32  6273.2  199.56  6275.8  200.92
#Mann= 4 ,-1 , 0
  4199.1     .05       0  4943.4      .1       0    4997     .07       0
    5003      .1       0
Bank Sta=4969.9,5018.7
XS Rating Curve= 0 ,0
Exp/Cntr=0.3,0.1