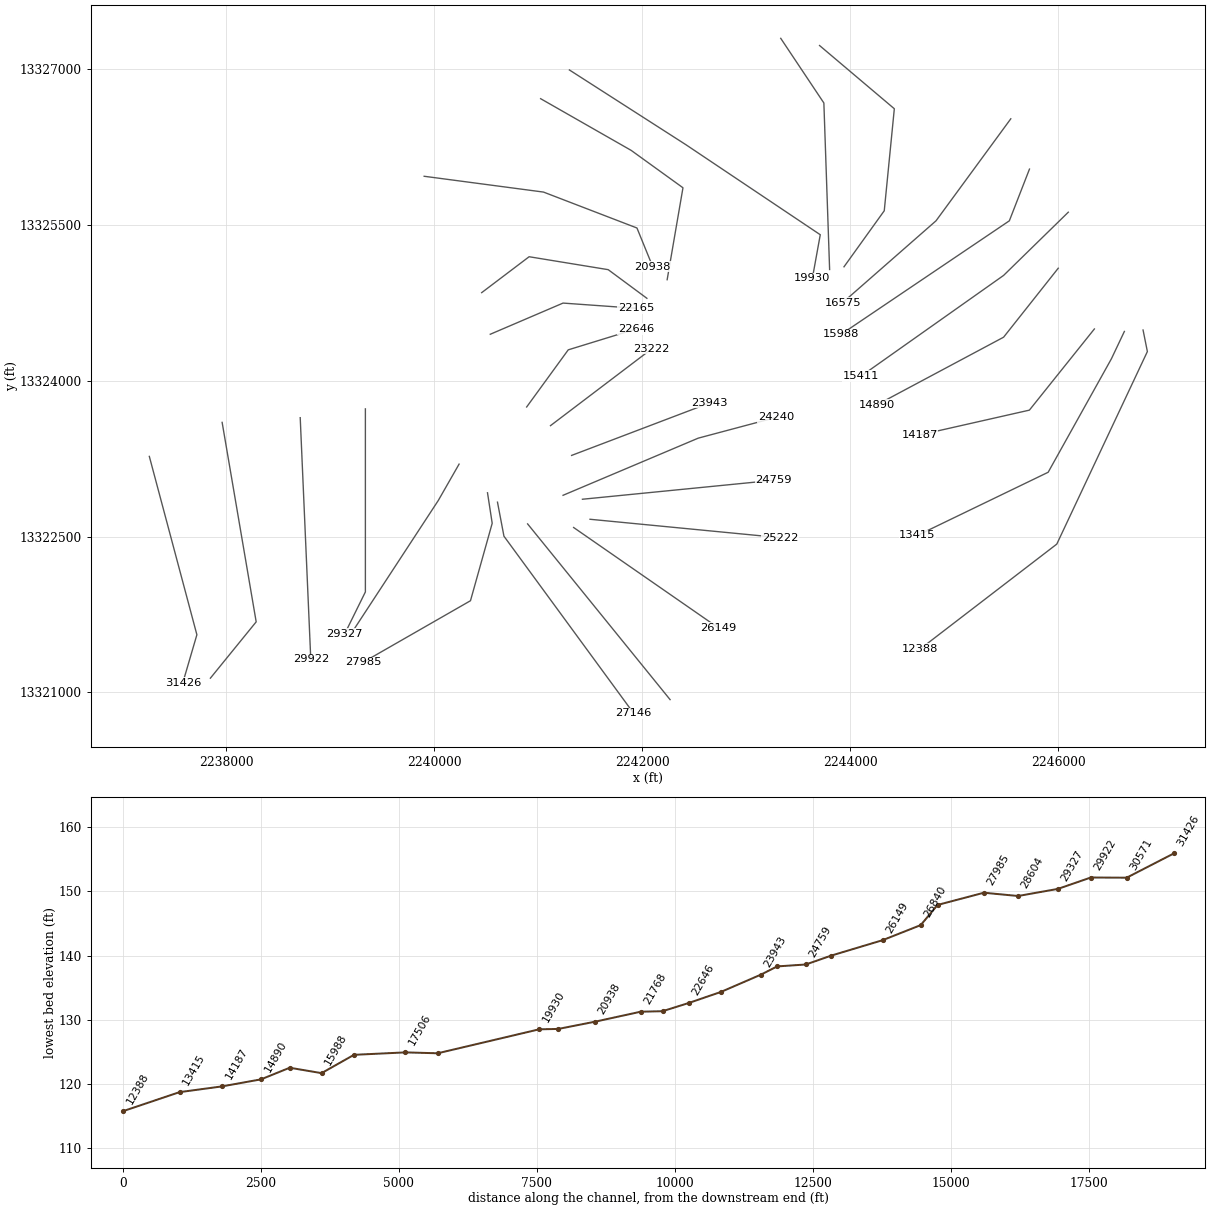
HEC-RAS study SALT BRANCH.prj: SALT BRANCH Base Level Engineering

--- SALT BRANCH.g01 (geometry) --- (continued)

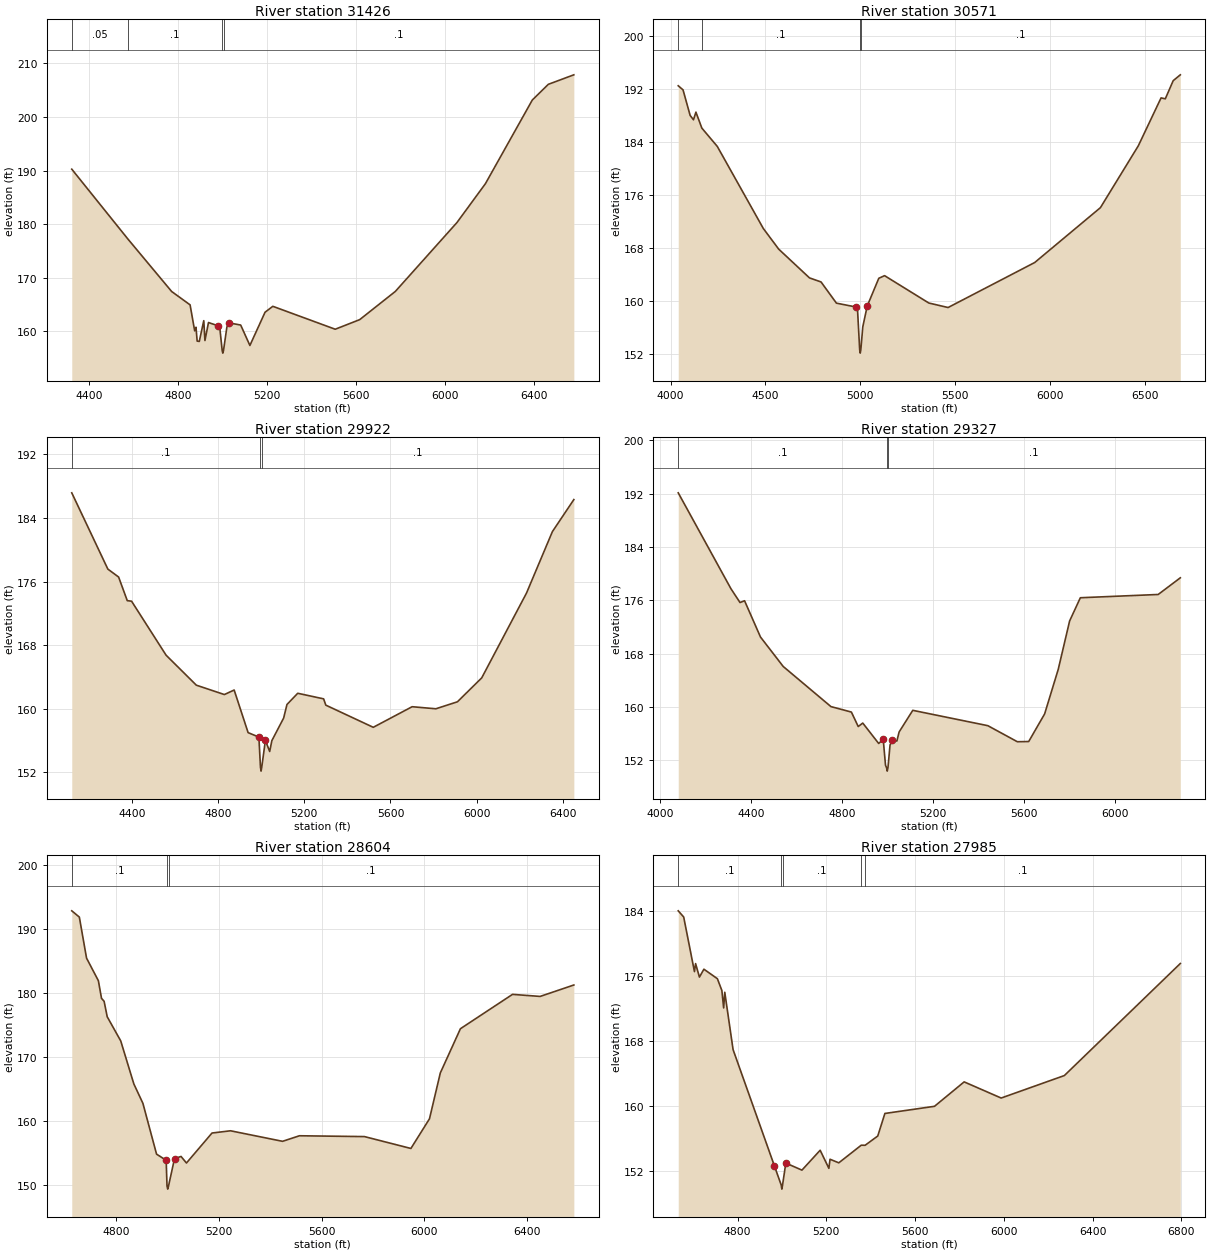
Type RM Length L Ch R = 1 ,31426   ,855,855,855
BEGIN DESCRIPTION:
SALT BRANCH 40.0
END DESCRIPTION:
XS GIS Cut Line= 3
      2237258.62     13323271.23        2237716.     13321554.64
      2237580.52     13321091.74
#Sta/Elev= 30
  4320.3  190.25  4573.4  177.18  4769.8  167.41  4852.6  164.92  4873.3  160.07
  4879.2  160.74  4884.4  158.15    4894   158.1  4914.2  161.97  4919.4  158.26
  4935.4  161.62  4976.8  161.04  4987.2  160.26    4997  156.41  4999.8  155.91
    5003  156.41  5018.2  160.78  5028.6  161.55  5080.3  161.15  5121.7  157.34
  5189.8  163.54  5224.8  164.65  5505.6  160.37  5615.6  162.16  5776.1  167.43
  6053.1  180.28  6181.3  187.54  6392.3  203.16  6464.4  206.09  6579.1  207.86
#Mann= 4 ,-1 , 0
  4320.3     .05       0  4573.4      .1       0    4997     .07       0
    5003      .1       0
Bank Sta=4976.8,5028.6
XS Rating Curve= 0 ,0
Exp/Cntr=0.3,0.1

Type RM Length L Ch R = 1 ,30571   ,649,649,649
BEGIN DESCRIPTION:
SALT BRANCH 39.0
END DESCRIPTION:
XS GIS Cut Line= 3
      2237958.81     13323598.77      2238286.32     13321678.87
      2237845.88     13321136.78
#Sta/Elev= 30
  4040.7  192.47    4066  191.85  4103.5  187.99  4121.1  187.34  4133.9  188.49
  4165.2  186.08  4246.5  183.32    4489  170.94  4570.2  167.82  4732.5  163.48
  4793.3  162.87  4874.5  159.67  4975.9   159.1  4986.1  158.45    4997  152.63
  4999.8  152.13    5003  152.63  5013.4   156.1  5036.8  159.24  5097.7  163.42
  5128.1  163.82  5361.4  159.69  5462.9  159.01  5919.4   165.8  6265.8  174.08
  6465.5  183.41  6585.4  190.64  6607.7   190.5  6649.4  193.24  6686.8  194.12
#Mann= 4 ,-1 , 0
  4040.7     .05       0  4165.2      .1       0    4997     .07       0
    5003      .1       0
Bank Sta=4975.9,5036.8
XS Rating Curve= 0 ,0
Exp/Cntr=0.3,0.1

Type RM Length L Ch R = 1 ,29922   ,595,595,595
BEGIN DESCRIPTION:
SALT BRANCH 37.0
END DESCRIPTION:
XS GIS Cut Line= 2
      2238709.83     13323643.96      2238811.47     13321317.48
#Sta/Elev= 30
  4121.8  187.16  4289.1  177.57  4339.1  176.57  4379.2   173.6  4399.2  173.53
  4559.3  166.74  4699.5  162.97  4829.6  161.79    4875  162.36  4939.7     157
  4989.7  156.44    4997  152.66  4999.8  152.16    5003  152.66  5019.8  156.02
  5039.8  154.63  5049.8  155.99  5104.6  158.84  5119.9  160.54  5169.9  161.95
    5290  161.25    5300  160.46  5520.2  157.67  5700.4  160.26  5810.5     160
  5910.6  160.88  6023.3  163.89  6230.9  174.55    6351  182.28  6450.5  186.31
#Mann= 3 ,-1 , 0
  4121.8      .1       0    4997     .07       0    5003      .1       0
Bank Sta=4989.7,5019.8
XS Rating Curve= 0 ,0
Exp/Cntr=0.3,0.1

Type RM Length L Ch R = 1 ,29327   ,723,723,723
BEGIN DESCRIPTION:
Mapping XS 36723d39
END DESCRIPTION:
XS GIS Cut Line= 3
      2239336.62     13323728.62      2239336.62     13321966.86
      2239139.01     13321565.98
#Sta/Elev= 30
  4080.4  192.14  4312.2  177.76  4352.2  175.68  4372.2  175.95  4442.2  170.51
  4542.2  166.09  4752.2  160.07  4842.2  159.25  4872.2  157.08  4892.2   157.6
  4962.2  154.54  4982.2  155.16  4992.2  151.28    4997  150.89  4999.8  150.39
    5003  150.89  5012.2  154.32  5022.2     155  5042.2  154.91  5052.2  156.27
  5112.2  159.51  5442.2  157.21  5572.2   154.8  5622.2  154.83  5692.2  158.97
  5752.2  165.67  5802.2  172.92  5849.4   176.4  6191.8  176.89  6289.1  179.39
#Mann= 3 ,-1 , 0
  4080.4      .1       0    4997     .07       0    5003      .1       0
Bank Sta=4982.2,5022.2
XS Rating Curve= 0 ,0
Exp/Cntr=0.3,0.1

Type RM Length L Ch R = 1 ,28604   ,619,619,619
BEGIN DESCRIPTION:
SALT BRANCH 35.0
END DESCRIPTION:
XS GIS Cut Line= 3
      2240237.73     13323196.88      2240037.72     13322846.85
       2239187.7     13321546.82
#Sta/Elev= 30
  4625.9  192.88  4655.4   191.9  4683.5  185.47  4729.6  181.93  4741.8  179.17
  4751.9  178.71  4764.1  176.28  4816.7   172.5  4867.8  165.76  4903.1  162.72
  4956.3  154.76  4993.8   153.8    4997  149.78  4999.8  149.28    5003  149.78
  5026.2  154.05  5051.7   154.4  5072.8  153.37  5172.4  158.07  5244.6  158.42
  5447.2  156.77  5513.1  157.64  5766.5  157.51  5947.4  155.65  6019.8   160.3
    6062  167.48  6140.4  174.41  6343.3  179.79    6451  179.47  6582.3  181.26
#Mann= 3 ,-1 , 0
  4625.9      .1       0    4997     .07       0    5003      .1       0
Bank Sta=4993.8,5026.2
XS Rating Curve= 0 ,0
Exp/Cntr=0.3,0.1

Type RM Length L Ch R = 1 ,27985   ,839,839,839
BEGIN DESCRIPTION:
SALT BRANCH 34.0
END DESCRIPTION:
XS GIS Cut Line= 4
      2240511.14      13322921.2      2240556.32     13322627.53
      2240347.39     13321882.16      2239314.04     13321289.25
#Sta/Elev= 30
  4532.9  184.07  4557.5  183.31    4606  176.58  4611.1  177.57  4628.4  175.91
  4648.6  176.88  4709.3  175.71  4729.5  174.26  4737.6  172.11  4742.6  174.04
  4780.1  166.97  4965.7   152.7    4997  150.29  4999.8  149.79    5003  150.29
  5017.7     153  5090.4  152.13  5172.5  154.58  5211.8  152.35    5217  153.47
  5256.5  153.03  5357.7   155.2    5375  155.19    5432  156.33  5464.2  159.11
  5687.7  159.99  5821.4     163  5988.2  161.01    6273  163.78  6795.5  177.58
#Mann= 5 ,-1 , 0
  4532.9      .1       0    4997     .07       0    5003      .1       0
  5357.7     .05       0    5375      .1       0
Bank Sta=4965.7,5017.7
XS Rating Curve= 0 ,0
Exp/Cntr=0.3,0.1

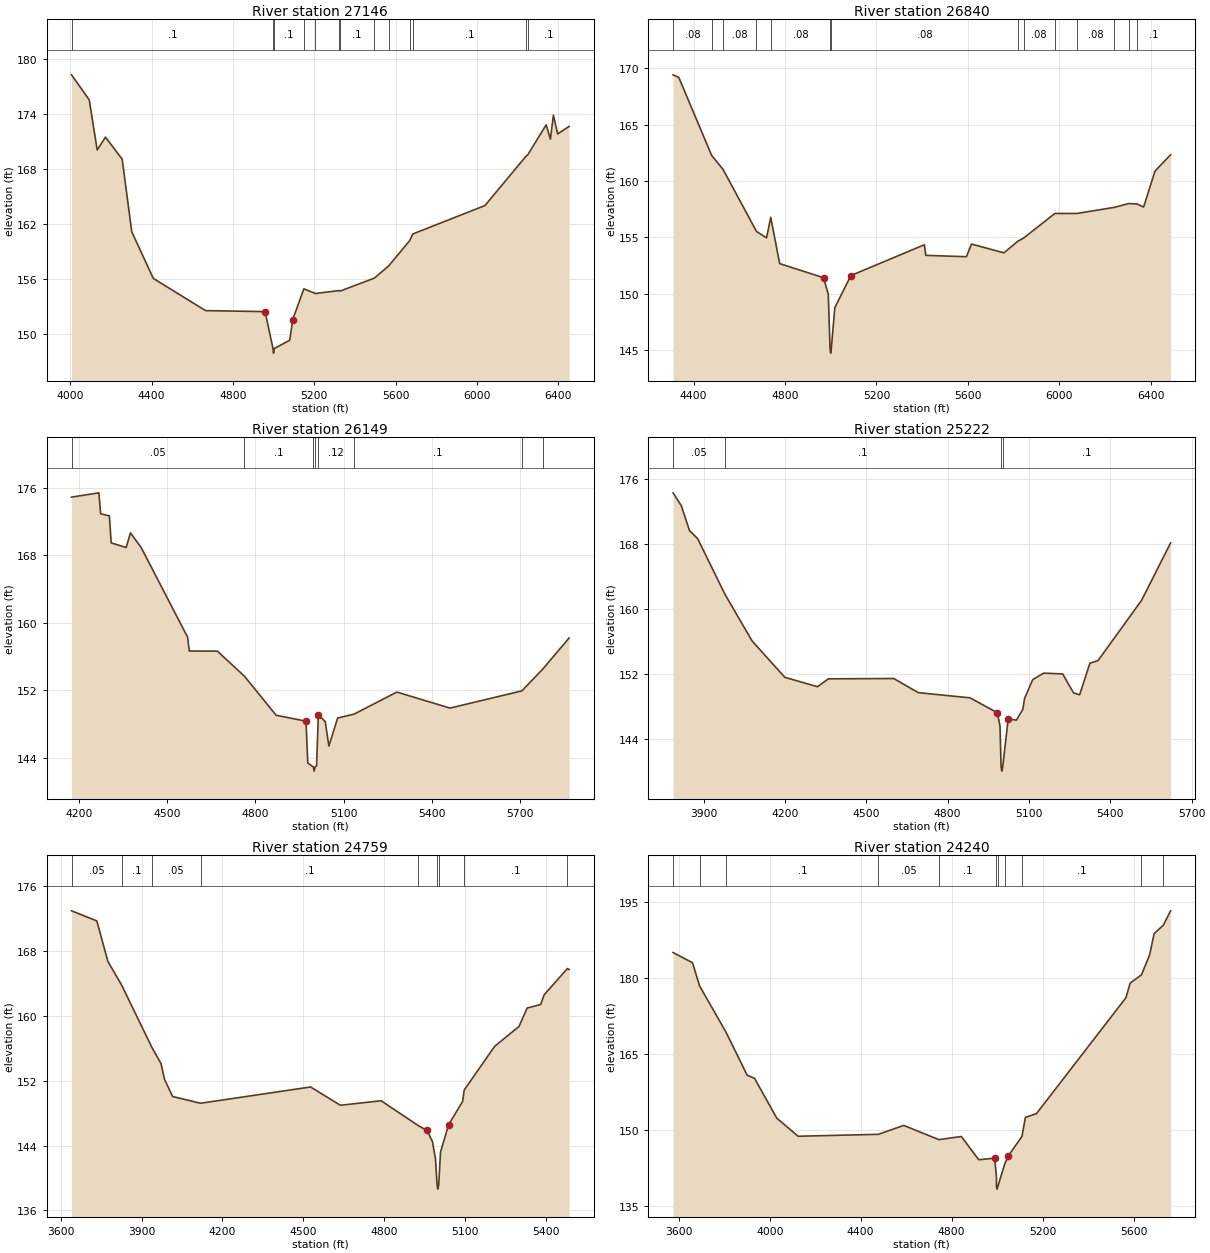
Type RM Length L Ch R = 1 ,27146   ,306,306,306
BEGIN DESCRIPTION:
SALT BRANCH 33.0
END DESCRIPTION:
XS GIS Cut Line= 3
      2240607.15      13322830.8      2240669.26      13322503.3
      2241917.19     13320797.98
#Sta/Elev= 30
  4006.5  178.27  4093.6  175.53  4132.7  170.06  4173.4  171.47  4255.5  169.06
  4302.7  161.13  4408.5  156.05  4665.6  152.53  4958.3  152.42    4997  148.39
  4999.8  147.89    5003  148.39  5079.5   149.3  5094.1  151.55  5148.7  154.91
  5205.8   154.4  5322.1  154.72  5325.6  154.65  5495.5  156.08    5565  157.39
  5668.8  160.16  5684.7   160.9  6039.2     164  6240.7  169.37  6249.4  169.53
  6340.3  172.81  6361.1  171.25  6375.8  173.86  6396.6  171.82    6453  172.64
#Mann= 13 ,-1 , 0
  4006.5      .1       0    4997     .07       0    5003      .1       0
  5148.7     .08       0  5205.8      .1       0  5322.1     .08       0
  5325.6      .1       0  5495.5     .08       0    5565      .1       0
  5668.8     .08       0  5684.7      .1       0  6240.7     .08       0
  6249.4      .1       0
Bank Sta=4958.3,5094.1
XS Rating Curve= 0 ,0
Exp/Cntr=0.3,0.1

Type RM Length L Ch R = 1 ,26840   ,691,691,691
BEGIN DESCRIPTION:
SALT BRANCH 32.0
END DESCRIPTION:
XS GIS Cut Line= 2
      2240896.83     13322621.58      2242267.16     13320930.36
#Sta/Elev= 30
  4310.3   169.4  4335.6  169.17  4479.4  162.25  4528.9  161.03  4675.4  155.53
  4719.3  154.96  4737.7  156.78  4776.8  152.68  4968.6  151.43  4989.4  149.97
    4997  145.25  4999.8  144.75    5003  145.25  5018.2  148.79  5088.6  151.62
  5409.8  154.35  5416.2  153.41  5593.7  153.29    5616  154.41  5757.9  153.63
  5818.6  154.66  5843.9  154.94  5980.6  157.12  6077.1  157.12  6240.5  157.66
  6304.5     158  6340.2  157.96    6369  157.69  6418.6  160.87    6487  162.32
#Mann= 14 ,-1 , 0
  4310.3     .08       0  4479.4      .1       0  4528.9     .08       0
  4675.4     .05       0  4737.7     .08       0    4997     .07       0
    5003     .08       0  5818.6      .1       0  5843.9     .08       0
  5980.6      .1       0  6077.1     .08       0  6240.5      .1       0
  6304.5     .05       0  6340.2      .1       0
Bank Sta=4968.6,5088.6
XS Rating Curve= 0 ,0
Exp/Cntr=0.3,0.1

Type RM Length L Ch R = 1 ,26149   ,927,927,927
BEGIN DESCRIPTION:
SALT BRANCH 31.0
END DESCRIPTION:
XS GIS Cut Line= 2
      2241339.51     13322586.88      2242728.41     13321623.33
#Sta/Elev= 30
  4175.6  174.87  4268.4  175.38  4274.5   172.9  4304.2  172.65  4310.3  169.45
    4361   168.9  4375.8  170.63  4411.6  168.93  4569.7  158.29  4575.8  156.63
    4671  156.62  4762.9  153.65  4870.9  149.02  4972.2  148.32  4978.3  143.36
    4997   142.9  4999.8   142.4    5003   142.9    5008  143.03  5012.3   147.3
  5014.1  149.09  5037.5  148.26  5049.9  145.37  5079.6  148.69  5135.7  149.16
    5281  151.77  5461.3  149.87  5705.6  151.91  5776.5  154.49    5866  158.18
#Mann= 8 ,-1 , 0
  4175.6     .05       0  4762.9      .1       0    4997     .07       0
    5003      .1       0  5012.3     .12       0  5135.7      .1       0
  5705.6     .05       0  5776.5      .1       0
Bank Sta=4972.2,5014.1
XS Rating Curve= 0 ,0
Exp/Cntr=0.3,0.1

Type RM Length L Ch R = 1 ,25222   ,463,463,463
BEGIN DESCRIPTION:
SALT BRANCH 30.0
END DESCRIPTION:
XS GIS Cut Line= 2
      2241497.29      13322666.2      2243324.04     13322489.25
#Sta/Elev= 30
    3787   174.3  3817.6  172.71  3847.7  169.65  3877.9  168.65  3978.5   161.8
  4078.8  156.04  4199.4  151.57  4319.9  150.41  4360.1  151.38  4601.2  151.42
  4691.6  149.68  4882.5  149.04    4983  147.21  4993.1  145.56    4997  140.51
  4999.8  140.01    5003  140.51  5023.2  146.44  5053.3  146.29  5077.6  147.64
  5083.5  148.96  5113.6  151.28  5153.8  152.08  5224.1  151.99  5264.3  149.65
  5286.8  149.41  5324.6  153.31  5354.7  153.63  5515.5  161.07  5622.3  168.13
#Mann= 4 ,-1 , 0
    3787     .05       0  3978.5      .1       0    4997     .07       0
    5003      .1       0
Bank Sta=4983,5023.2
XS Rating Curve= 0 ,0
Exp/Cntr=0.3,0.1

Type RM Length L Ch R = 1 ,24759   ,519,519,519
BEGIN DESCRIPTION:
SALT BRANCH 29.0
END DESCRIPTION:
XS GIS Cut Line= 2
       2241424.3     13322858.91      2243262.79      13323041.2
#Sta/Elev= 30
  3639.7  172.94  3733.6   171.7  3774.8  166.69  3825.6  163.79  3938.3  156.08
  3971.7  154.12  3984.8  152.17  4014.9  150.04  4118.9  149.21  4527.4  151.22
    4638  148.96  4789.1  149.52  4927.4  146.45  4959.6  145.86  4979.7  144.49
  4990.9   142.4    4997  139.12  4999.8  138.62    5003  139.12  5009.8  143.19
  5039.9  146.57  5091.8  149.43  5097.7  150.84  5210.8  156.23  5301.2  158.68
  5331.4  160.95  5381.6  161.39  5394.6  162.59  5480.9  165.82  5487.2   165.7
#Mann= 9 ,-1 , 0
  3639.7     .05       0  3825.6      .1       0  3938.3     .05       0
  4118.9      .1       0  4927.4     .16       0    4997     .07       0
    5003     .16       0  5097.7      .1       0  5480.9     .05       0
Bank Sta=4959.6,5039.9
XS Rating Curve= 0 ,0
Exp/Cntr=0.3,0.1

Type RM Length L Ch R = 1 ,24240   ,297,297,297
BEGIN DESCRIPTION:
SALT BRANCH 28.0
END DESCRIPTION:
XS GIS Cut Line= 3
      2241237.74     13322896.86      2242537.72     13323446.85
      2243287.68     13323646.84
#Sta/Elev= 30
    3575  185.04  3660.6  183.02  3691.6  178.46  3808.7  169.24    3901  160.81
  3933.3   160.2    4031  152.34    4125  148.76  4477.7  149.14  4589.5   150.9
  4743.9  148.09  4842.7  148.71  4919.2  144.12  4989.1  144.43  4996.9  140.87
    4997  138.82  4999.8  138.32    5003  138.82  5033.1  143.26  5049.3  144.89
  5109.2  148.73  5124.3  152.49  5172.8  153.22  5566.1   176.1  5584.9  178.99
  5634.5  180.63  5670.2  184.53  5690.3  188.77  5730.9  190.45  5762.7  193.27
#Mann= 11 ,-1 , 0
    3575     .08       0  3691.6     .05       0  3808.7      .1       0
  4477.7     .05       0  4743.9      .1       0    4997     .07       0
    5003      .1       0  5033.1     .05       0  5109.2      .1       0
  5634.5     .08       0  5730.9     .05       0
Bank Sta=4989.1,5049.3
XS Rating Curve= 0 ,0
Exp/Cntr=0.3,0.1

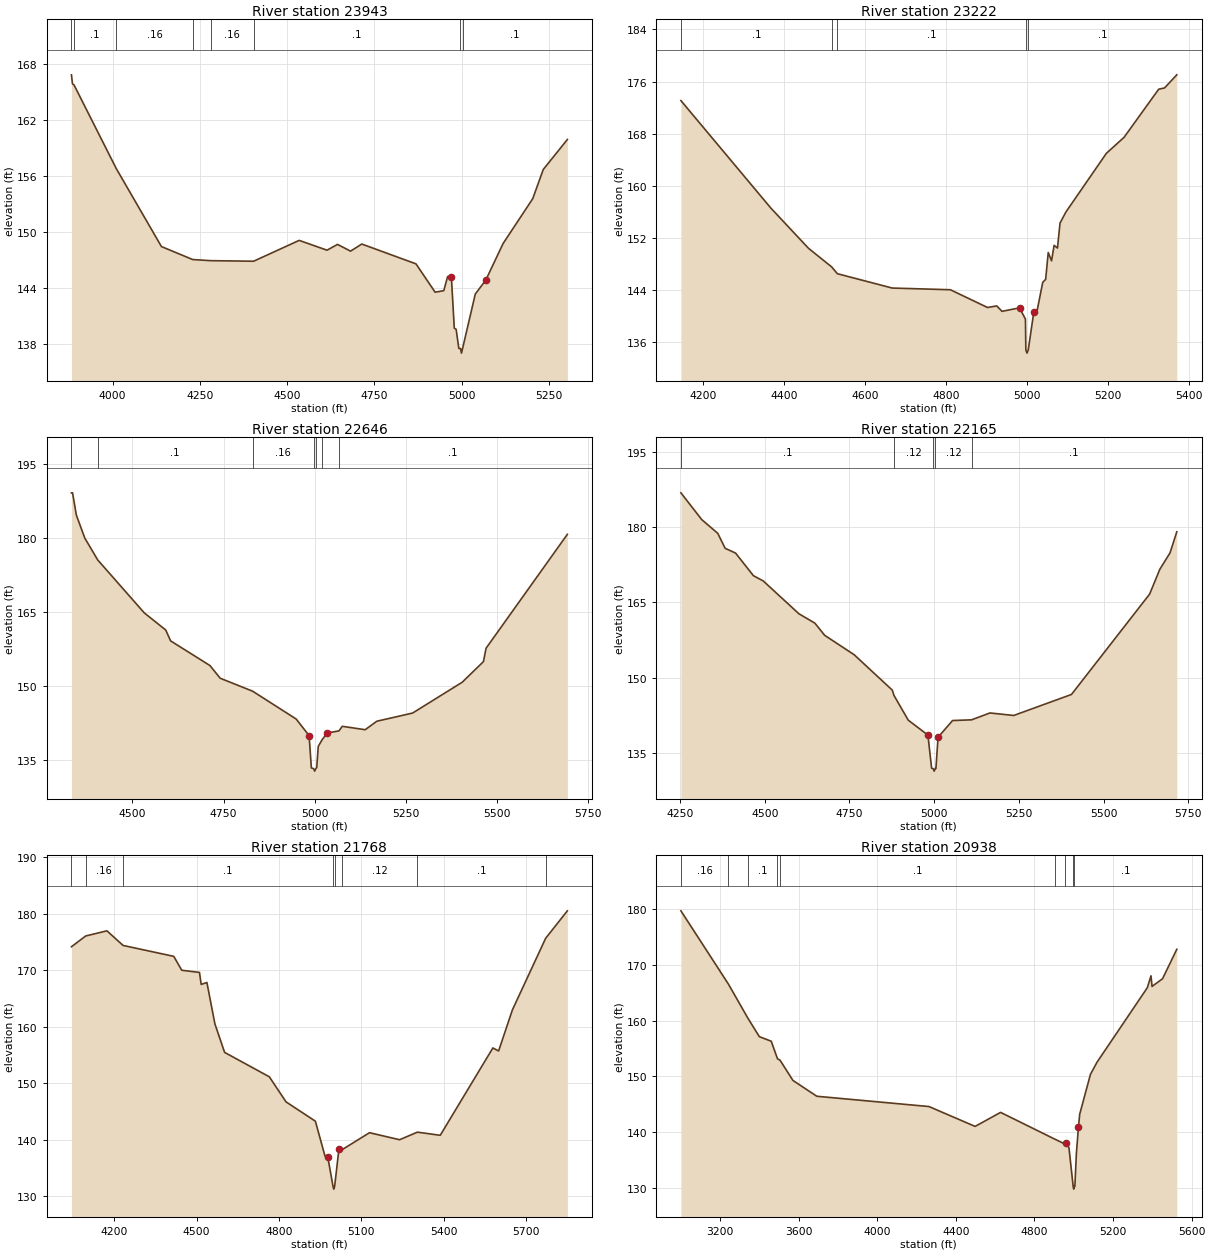
Type RM Length L Ch R = 1 ,23943   ,721,721,721
BEGIN DESCRIPTION:
SALT BRANCH 27.0
END DESCRIPTION:
XS GIS Cut Line= 2
      2241320.18     13323280.79      2242648.34     13323786.01
#Sta/Elev= 30
  3882.2   166.8  3885.1  165.83  3889.4  165.73  4010.5  156.78    4140  148.43
  4229.7  147.04  4281.6  146.92  4404.1  146.86  4534.8  149.09  4614.5  148.04
  4644.6  148.66    4682  147.94  4714.1   148.7  4869.4  146.58  4924.3  143.55
  4949.1  143.71  4960.2  145.23  4970.9  145.18  4979.2  139.69  4984.5  139.58
  4992.3  137.53    4997  137.53  4999.8  137.03    5003  137.53  5039.4  143.35
  5069.5  144.84    5119  148.75    5204  153.55  5234.1  156.67  5303.2  159.88
#Mann= 8 ,-1 , 0
  3882.2     .16       0  3889.4      .1       0  4010.5     .16       0
  4229.7      .1       0  4281.6     .16       0  4404.1      .1       0
    4997     .07       0    5003      .1       0
Bank Sta=4970.9,5069.5
XS Rating Curve= 0 ,0
Exp/Cntr=0.3,0.1

Type RM Length L Ch R = 1 ,23222   ,576,576,576
BEGIN DESCRIPTION:
SALT BRANCH 26.0
END DESCRIPTION:
XS GIS Cut Line= 2
      2241117.04     13323567.24      2242091.04     13324306.86
#Sta/Elev= 30
  4146.3  173.08  4367.9  156.61  4461.1  150.42    4518  147.58  4532.2  146.53
  4667.4  144.33  4810.9  144.07  4902.4  141.35  4925.2  141.59  4938.2  140.76
  4981.4  141.29    4996  139.57    4997  134.85  4999.8  134.35    5003  134.85
  5016.8  140.73  5025.1  140.95  5038.7  145.22  5045.9  145.66  5052.2  149.78
  5060.4   148.5  5066.7  150.88    5075  150.47  5081.3  154.29  5095.8  155.99
  5195.6  164.99  5239.3  167.45  5324.6  174.82  5339.1  175.02  5369.3  177.03
#Mann= 5 ,-1 , 0
  4146.3      .1       0    4518     .16       0  4532.2      .1       0
    4997     .07       0    5003      .1       0
Bank Sta=4981.4,5016.8
XS Rating Curve= 0 ,0
Exp/Cntr=0.3,0.1

Type RM Length L Ch R = 1 ,22646   ,481,481,481
BEGIN DESCRIPTION:
SALT BRANCH 25.0
END DESCRIPTION:
XS GIS Cut Line= 3
      2240887.75     13323746.89      2241287.72     13324296.85
      2241937.72     13324496.85
#Sta/Elev= 30
  4332.8   189.1  4335.8   189.1  4346.3  184.56  4369.5   179.9  4404.9  175.48
  4532.5  164.75  4591.3  161.28  4604.8  159.07  4712.6  154.07  4740.8  151.49
  4829.8  148.86  4949.1  143.22  4984.6  139.86  4990.8   133.3    4997  133.15
  4999.8  132.65    5003  133.15  5005.5  133.37  5009.7  137.66  5020.4  139.03
  5034.4  140.39  5066.5  140.81  5075.6  141.74  5138.4  141.05  5170.4  142.77
  5268.5  144.43  5404.5  150.68  5462.7  154.86  5469.9  157.57  5692.9  180.68
#Mann= 7 ,-1 , 0
  4332.8     .08       0  4404.9      .1       0  4829.8     .16       0
    4997     .07       0    5003     .16       0  5020.4     .16       0
  5066.5      .1       0
Bank Sta=4984.6,5034.4
XS Rating Curve= 0 ,0
Exp/Cntr=0.3,0.1

Type RM Length L Ch R = 1 ,22165   ,397,397,397
BEGIN DESCRIPTION:
SALT BRANCH 24.0
END DESCRIPTION:
XS GIS Cut Line= 3
      2240537.75     13324446.87      2241237.72     13324746.85
      2241937.69     13324696.86
#Sta/Elev= 30
  4252.6  186.85  4314.2   181.5  4361.4  178.77  4383.1  175.79    4414  174.83
  4466.5  170.33  4495.5  169.28  4600.7  162.74  4647.9  160.86  4676.9  158.43
  4763.9  154.56  4876.3  147.51  4881.3  146.45  4923.5  141.51  4981.5  138.54
  4992.4  131.93    4997  131.85  4999.8  131.35    5003  131.85  5005.1  131.85
  5011.4   138.1  5054.2  141.44  5110.3  141.58  5164.5  142.95  5234.7  142.45
  5405.1  146.64  5635.7  166.65  5665.8   171.6  5695.9  174.87  5715.9  179.08
#Mann= 5 ,-1 , 0
  4252.6      .1       0  4881.3     .12       0    4997     .07       0
    5003     .12       0  5110.3      .1       0
Bank Sta=4981.5,5011.4
XS Rating Curve= 0 ,0
Exp/Cntr=0.3,0.1

Type RM Length L Ch R = 1 ,21768   ,830,830,830
BEGIN DESCRIPTION:
SALT BRANCH 23.0
END DESCRIPTION:
XS GIS Cut Line= 4
      2240455.13     13324847.27      2240911.43     13325192.96
        2241672.      13325068.5      2242044.01     13324792.94
#Sta/Elev= 30
  4044.4  174.19    4096  176.09  4173.6  177.01  4232.4  174.42    4417  172.49
  4446.1  170.03  4510.6  169.64  4516.9  167.52  4537.7  167.86  4566.8  160.54
  4602.2  155.48  4765.1  151.16  4825.9  146.72  4932.8   143.3  4967.8  137.12
  4977.9  136.98    4997  131.77  4999.8  131.27    5003  131.77  5018.4  138.31
  5028.3   138.2  5129.9  141.26  5239.6  140.02  5304.3  141.36  5387.5   140.8
  5579.3  156.27  5600.2  155.73  5650.2  162.99  5771.4  175.68  5850.5  180.55
#Mann= 8 ,-1 , 0
  4044.4      .1       0    4096     .16       0  4232.4      .1       0
    4997     .07       0    5003      .1       0  5028.3     .12       0
  5304.3      .1       0  5771.4     .08       0
Bank Sta=4977.9,5018.4
XS Rating Curve= 0 ,0
Exp/Cntr=0.3,0.1

Type RM Length L Ch R = 1 ,20938   ,663,663,663
BEGIN DESCRIPTION:
SALT BRANCH 22.0
END DESCRIPTION:
XS GIS Cut Line= 4
      2239901.94     13325967.36      2241049.72     13325815.24
      2241948.57     13325469.53      2242100.68     13325096.19
#Sta/Elev= 30
  3000.5  179.76    3242   166.6  3341.5  160.45  3399.7  157.13  3460.3  156.31
  3492.1  153.15  3504.8  152.91  3570.7  149.26  3692.3  146.41  4263.3  144.56
  4497.9  140.99  4627.6  143.51  4904.1  138.69  4953.4  137.86  4959.7  138.05
  4975.7  137.15    4997  130.21  4999.8  129.71    5003  130.21  5005.7  130.21
  5013.3  136.07    5024  140.92  5030.3  143.19    5085  150.35  5118.2  152.52
  5374.4  165.93  5393.1  168.07  5398.5  166.16    5452  167.55  5524.5  172.84
#Mann= 9 ,-1 , 0
  3000.5     .16       0    3242     .08       0  3341.5      .1       0
  3492.1     .05       0  3504.8      .1       0  4904.1     .16       0
  4953.4      .1       0    4997     .07       0    5003      .1       0
Bank Sta=4959.7,5024
XS Rating Curve= 0 ,0
Exp/Cntr=0.3,0.1

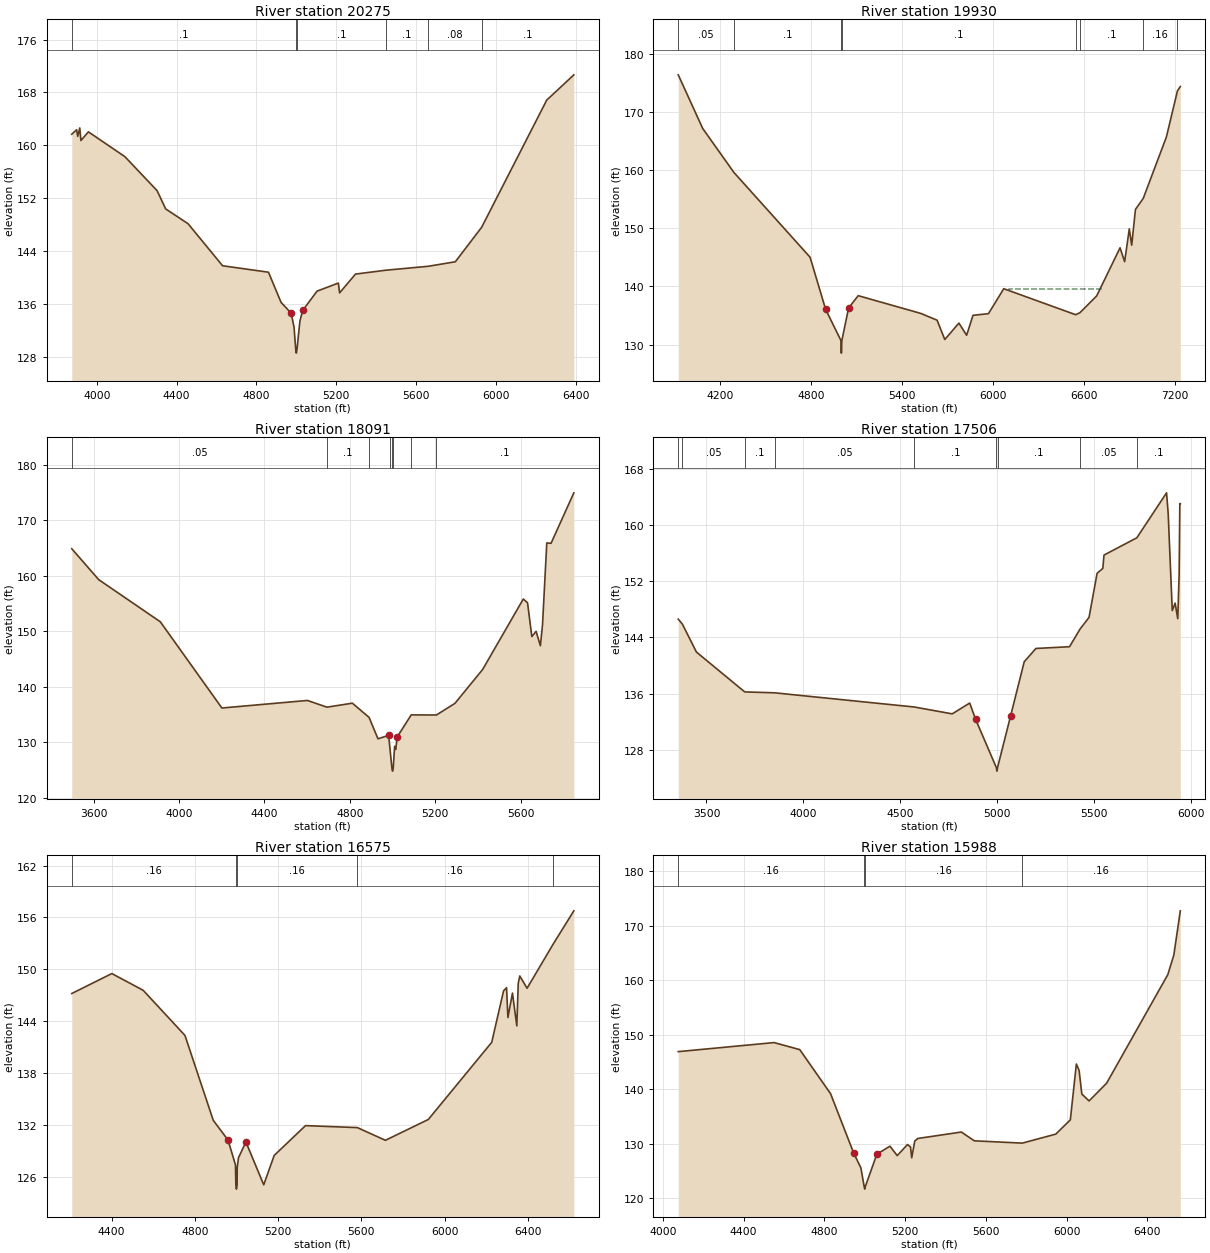
Type RM Length L Ch R = 1 ,20275   ,345,345,345
BEGIN DESCRIPTION:
Mapping XS 7770361e
END DESCRIPTION:
XS GIS Cut Line= 4
      2241022.07     13326714.09      2241893.26     13326216.27
      2242391.09     13325856.73      2242238.99     13324971.78
#Sta/Elev= 30
  3874.9  161.68  3899.1  162.36  3904.9  161.36    3915  162.63  3920.7  160.73
  3958.2  162.04    4141  158.29  4302.2  153.16  4345.4  150.39  4457.3  148.16
  4630.5   141.8  4860.4  140.82  4923.5  136.26  4973.8  134.64  4988.5  132.52
    4997  129.09  4999.8  128.59    5003  129.09  5017.9  133.44  5031.8  135.04
  5103.8  137.96  5210.5  139.18  5216.8   137.7  5296.4  140.54  5447.3  141.12
  5661.3  141.72  5796.6   142.4  5928.6  147.62  6254.3  166.83  6390.3  170.66
#Mann= 6 ,-1 , 0
  3874.9      .1       0    4997     .07       0    5003      .1       0
  5447.3      .1       0  5661.3     .08       0  5928.6      .1       0
Bank Sta=4973.8,5031.8
XS Rating Curve= 0 ,0
Exp/Cntr=0.3,0.1

Type RM Length L Ch R = 1 ,19930   ,1839,1839,1839
BEGIN DESCRIPTION:
Mapping XS ae6cc46e
END DESCRIPTION:
XS GIS Cut Line= 4
      2241298.64     13326990.67      2242418.75     13326271.59
      2243711.63     13325404.68      2243635.65     13324985.49
#Sta/Elev= 30
  3923.1  176.43    4085  167.18  4291.1  159.61  4793.2  145.04  4896.2  136.05
    4997   130.7  4999.8  128.53    5003   130.7  5047.5  136.29  5110.9  138.42
  5523.4  135.37  5631.5   134.2  5682.5  130.87  5775.5   133.7  5826.5   131.6
  5868.6  135.04  5970.6  135.32  6071.6  139.62  6546.4  135.14  6574.4  135.49
  6684.9  138.38  6839.1  146.66  6869.5  144.27    6900  149.92    6916  147.11
  6940.7  153.26  6992.3  155.17  7145.1  165.74    7218  173.68  7236.8  174.41
#Mann= 8 ,-1 , 0
  3923.1     .05       0  4291.1      .1       0    4997     .07       0
    5003      .1       0  6546.4     .05       0  6574.4      .1       0
  6992.3     .16       0    7218      .1       0
#XS Ineff= 1 ,-1
 6106.59 6732.37  139.64
Permanent Ineff=
       F
Bank Sta=4896.2,5047.5
XS Rating Curve= 0 ,0
Exp/Cntr=0.3,0.1

Type RM Length L Ch R = 1 ,18091   ,585,585,585
BEGIN DESCRIPTION:
SALT BRANCH 18.0
END DESCRIPTION:
XS GIS Cut Line= 3
      2243331.41     13327294.93      2243746.29     13326672.61
      2243801.54      13325070.2
#Sta/Elev= 30
  3497.6  164.86  3623.8  159.29  3912.3   151.7  4200.7  136.17  4601.5  137.53
  4692.6  136.32  4811.6  137.04  4889.9  134.48  4931.7  130.62  4981.7  131.25
  4988.6  128.53    4997   125.3  4999.8   124.8    5003   125.3  5009.6  129.27
  5014.6  128.71  5021.8  130.96  5087.3  134.93  5205.2  134.91  5291.9     137
    5422  143.12  5612.1   155.8  5632.1  155.12  5652.1  149.04  5672.1  149.97
  5692.2  147.39  5702.2  151.16  5722.2   165.9  5742.2  165.84  5848.9  174.93
#Mann= 8 ,-1 , 0
  3497.6     .05       0  4692.6      .1       0  4889.9     .05       0
  4988.6      .1       0    4997     .07       0    5003      .1       0
  5087.3     .05       0  5205.2      .1       0
Bank Sta=4981.7,5021.8
XS Rating Curve= 0 ,0
Exp/Cntr=0.3,0.1

Type RM Length L Ch R = 1 ,17506   ,931,931,931
BEGIN DESCRIPTION:
SALT BRANCH 17.0
END DESCRIPTION:
XS GIS Cut Line= 4
       2243704.8     13327225.76      2244423.89      13326617.3
      2244327.09     13325635.47      2243939.87     13325096.13
#Sta/Elev= 30
  3354.3   146.6  3375.8  145.89  3448.2  141.91  3697.6  136.23  3851.6   136.1
  4572.7  134.08    4769   133.1  4859.4  134.64  4889.6  132.33    4997  125.44
  4999.8  124.94    5003  125.44  5070.4  132.79  5140.8  140.52  5201.1  142.42
  5374.8  142.67  5429.2  145.19  5475.5  146.85  5517.2  153.14  5546.7  153.83
  5552.8  155.73  5722.3  158.19  5875.8   164.6  5884.3   161.6  5905.2  147.82
    5920  148.88  5933.6  146.67  5940.8  153.01  5944.3  163.06  5946.8  163.06
#Mann= 9 ,-1 , 0
  3354.3      .1       0  3375.8     .05       0  3697.6      .1       0
  3851.6     .05       0  4572.7      .1       0    4997     .07       0
    5003      .1       0  5429.2     .05       0  5722.3      .1       0
Bank Sta=4889.6,5070.4
XS Rating Curve= 0 ,0
Exp/Cntr=0.3,0.1

Type RM Length L Ch R = 1 ,16575   ,587,587,587
BEGIN DESCRIPTION:
SALT BRANCH 16.0
END DESCRIPTION:
XS GIS Cut Line= 3
      2245544.01      13326520.5      2244824.92     13325538.67
      2243926.89     13324751.17
#Sta/Elev= 30
  4208.9   147.2  4401.4  149.51  4551.9  147.57  4752.6  142.35  4888.5  132.52
  4959.5  130.24  4995.1  127.36    4997  125.06  4999.8  124.56    5003  125.06
  5003.5  127.07  5009.7  128.19  5045.2  130.02  5130.9  125.06  5181.1  128.46
  5331.6  131.91  5580.6  131.68  5715.3  130.21  5921.3  132.62  6225.9  141.55
  6282.8  147.51  6297.1  147.87  6303.7  144.42  6325.5  147.25  6346.4  143.45
  6353.2  148.37  6360.6  149.23  6395.8  147.81  6518.8  152.83  6620.3  156.77
#Mann= 5 ,-1 , 0
  4208.9     .16       0    4997     .07       0    5003     .16       0
  5580.6     .16       0  6518.8     .05       0
Bank Sta=4959.5,5045.2
XS Rating Curve= 0 ,0
Exp/Cntr=0.3,0.1

Type RM Length L Ch R = 1 ,15988   ,577,577,577
BEGIN DESCRIPTION:
SALT BRANCH 15.0
END DESCRIPTION:
XS GIS Cut Line= 3
      2245723.77     13326036.48      2245530.17     13325538.67
      2243912.44     13324446.36
#Sta/Elev= 30
  4076.4   146.9  4550.9  148.56  4678.1  147.27  4830.7   139.2  4944.8  128.35
  4980.8   125.6    4997  122.21  4999.8  121.71    5003  122.21  5059.9  128.11
  5124.7  129.58  5160.7  127.85  5211.6  129.88  5226.6  129.44  5232.6  127.45
  5247.6  130.51  5262.5  130.99  5478.3  132.17  5542.6  130.56  5780.2  130.14
  5945.9  131.79  6017.9   134.4  6047.8  144.63  6061.4  143.45  6074.9  139.13
  6110.8  137.87  6197.7  141.12  6500.5     161  6530.4  164.59  6562.5   172.7
#Mann= 4 ,-1 , 0
  4076.4     .16       0    4997     .07       0    5003     .16       0
  5780.2     .16       0
Bank Sta=4944.8,5059.9
XS Rating Curve= 0 ,0
Exp/Cntr=0.3,0.1

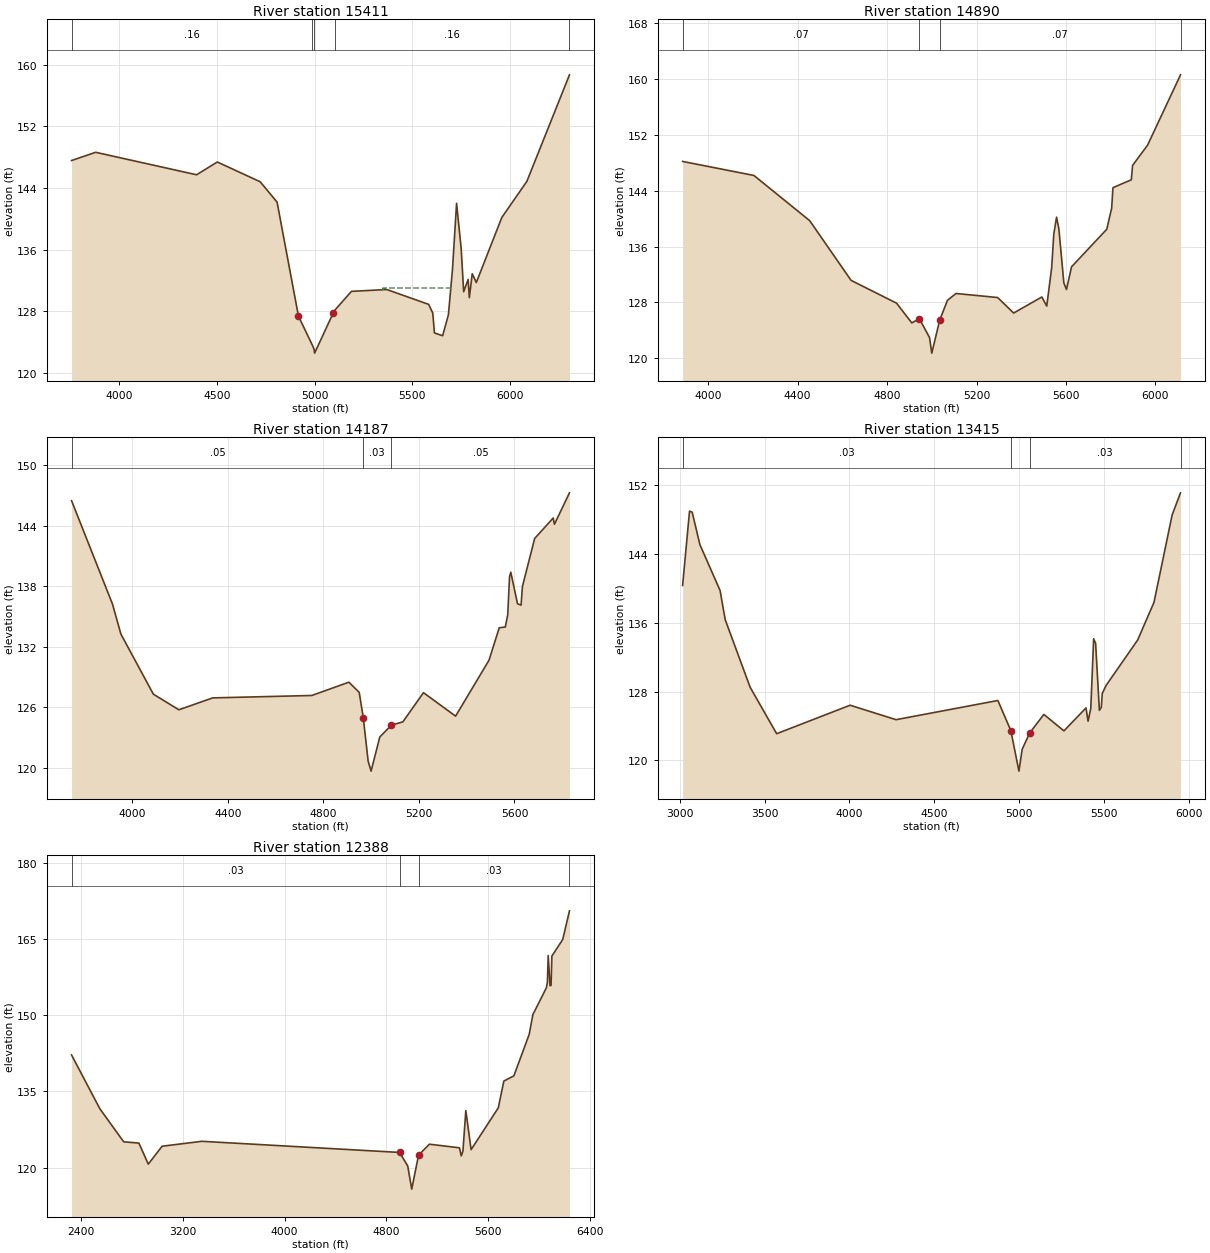
Type RM Length L Ch R = 1 ,15411   ,521,521,521
BEGIN DESCRIPTION:
SALT BRANCH 14.0
END DESCRIPTION:
XS GIS Cut Line= 3
      2246097.16     13325621.65      2245474.86     13325013.19
      2244105.85      13324045.2
#Sta/Elev= 30
  3756.4  147.56  3879.7  148.63  4395.9  145.71  4501.9  147.37  4721.5   144.8
  4807.7  142.16  4917.2  127.34  4988.7  123.56    4997  123.05  4999.8  122.55
  5095.7  127.81  5101.9  128.09    5188  130.57    5369  130.81  5583.2  128.88
  5604.1  127.76  5612.7  125.17  5654.6  124.81  5684.1  127.53    5705  133.43
  5725.9  142.01  5749.4  136.13  5762.2  130.53  5785.1  132.12  5791.2  129.76
    5806  132.86  5826.9  131.72  5957.4  140.17  6085.4  144.85  6303.4  158.69
#Mann= 5 ,-1 , 0
  3756.4     .16       0  4988.7     .07       0    4997     .16       0
  5101.9     .16       0  6303.4     .05       0
#XS Ineff= 2 ,-1
 5351.14 5698.86  131.01 5727.84 6208.52  140.36
Permanent Ineff=
       F       F
Bank Sta=4917.2,5095.7
XS Rating Curve= 0 ,0
Exp/Cntr=0.3,0.1

Type RM Length L Ch R = 1 ,14890   ,703,703,703
BEGIN DESCRIPTION:
SALT BRANCH 13.0
END DESCRIPTION:
XS GIS Cut Line= 3
      2246000.34     13325082.32      2245474.86     13324418.56
      2244257.93     13323768.61
#Sta/Elev= 30
  3885.7  148.19  4204.6  146.18  4453.9  139.71  4638.9  131.16  4842.4  127.89
  4910.4  125.07  4944.4  125.66  4989.8  122.97  4999.8  120.74  5035.1  125.45
  5069.9  128.31  5108.1  129.28  5294.3   128.7  5365.8  126.48  5491.9  128.78
  5513.8  127.47  5535.8  132.97  5545.3  137.78  5557.7  140.21    5568  138.55
  5590.3   130.8    5602  129.85  5624.7   133.1  5782.2  138.48  5804.1   141.5
  5809.8  144.43  5891.9  145.56  5897.6  147.62  5964.8  150.53  6111.9  160.59
#Mann= 4 ,-1 , 0
  3885.7     .07       0  4944.4     .05       0  5035.1     .07       0
  6111.9     .05       0
#XS Ineff= 2 , 0
                         5559.09          139.73
Permanent Ineff=
       F       F
Bank Sta=4944.4,5035.1
XS Rating Curve= 0 ,0
Exp/Cntr=0.3,0.1

Type RM Length L Ch R = 1 ,14187   ,772,772,772
BEGIN DESCRIPTION:
Mapping XS 044be641
END DESCRIPTION:
XS GIS Cut Line= 3
      2246347.94     13324497.79      2245722.96     13323716.55
      2244665.63     13323476.96
#Sta/Elev= 30
  3745.8   146.5  3917.1  136.24  3952.3  133.26  4088.3  127.29  4195.2  125.74
  4336.5  126.92  4751.6  127.16  4906.9  128.48  4950.1  127.47    4967  124.97
  4987.5  120.65  4999.8  119.65  5036.3  123.04  5084.6  124.21  5132.8  124.54
  5219.1  127.44  5353.6  125.11  5493.3  130.65  5536.4  133.88  5561.7  133.96
  5571.9  135.17  5579.5  138.96  5584.7   139.4  5612.9  136.27  5627.8  136.13
  5633.4  137.98  5684.7  142.75  5762.3  144.78  5767.4  144.16  5830.4  147.28
#Mann= 3 , 0 , 0
  3745.8     .05       0    4967     .03       0  5084.6     .05       0
#XS Ineff= 2 , 0
         4907.67  128.35
Permanent Ineff=
       F       F
Bank Sta=4967,5084.6
XS Rating Curve= 0 ,0
Exp/Cntr=0.3,0.1

Type RM Length L Ch R = 1 ,13415   ,1027,1027,1027
BEGIN DESCRIPTION:
Mapping XS 2f948451
END DESCRIPTION:
XS GIS Cut Line= 4
      2246636.45     13324473.85        2246512.     13324211.13
      2245903.55     13323118.67      2244646.82     13322511.02
#Sta/Elev= 30
  3015.8  140.33  3056.7  148.98  3072.3  148.85  3117.8  145.08    3237  139.74
    3267  136.36  3414.4  128.49  3570.6   123.1  4003.8  126.41  4274.8  124.73
  4875.6  126.96  4952.2  123.45  4999.8  118.75  5018.9  121.29  5063.3  123.19
  5146.8  125.34  5265.3  123.43  5395.3   126.1  5407.6  124.56  5423.5  126.04
  5440.5  134.13  5452.1  133.61  5474.3  125.82  5485.4  126.15  5491.2  127.77
  5513.8  128.71  5700.1  133.99  5796.4  138.37  5903.5  148.53  5952.9   151.1
#Mann= 4 ,-1 , 0
  3015.8     .03       0  4952.2    .025       0  5063.3     .03       0
  5952.9      .1       0
Bank Sta=4952.2,5063.3
XS Rating Curve= 0 ,0
Exp/Cntr=0.3,0.1

Type RM Length L Ch R = 1 ,12388   ,0,0,0
BEGIN DESCRIPTION:
SALT BRANCH 1.0
END DESCRIPTION:
XS GIS Cut Line= 4
      2246816.23     13324487.71      2246857.72     13324280.27
      2245986.52     13322427.24      2244672.83     13321417.78
#Sta/Elev= 30
  2324.5  142.18  2546.6  131.61  2734.5  125.09    2854  124.84    2928   120.7
  3036.5  124.22  3349.5  125.19    4904     123  4968.4  120.34  4999.8  115.78
  5053.6  122.47  5138.7  124.62  5375.3  123.91  5389.3  122.32  5402.4  123.24
  5425.2  131.24  5466.8  123.55  5680.7  131.78  5724.2  137.04  5803.1  138.07
  5923.6  146.23  5952.6  150.12  6058.6  155.39  6066.8  156.51  6073.1  161.74
  6087.6   155.8  6095.5  155.87  6102.1  161.64  6187.3   164.9  6240.4  170.54
#Mann= 4 ,-1 , 0
  2324.5     .03       0    4904    .025       0  5053.6     .03       0
  6240.4      .1       0
Bank Sta=4904,5053.6
XS Rating Curve= 0 ,0
Exp/Cntr=0.3,0.1

Chan Stop Cuts=-1
Use User Specified Reach Order=0
Composite Channel Slope=5