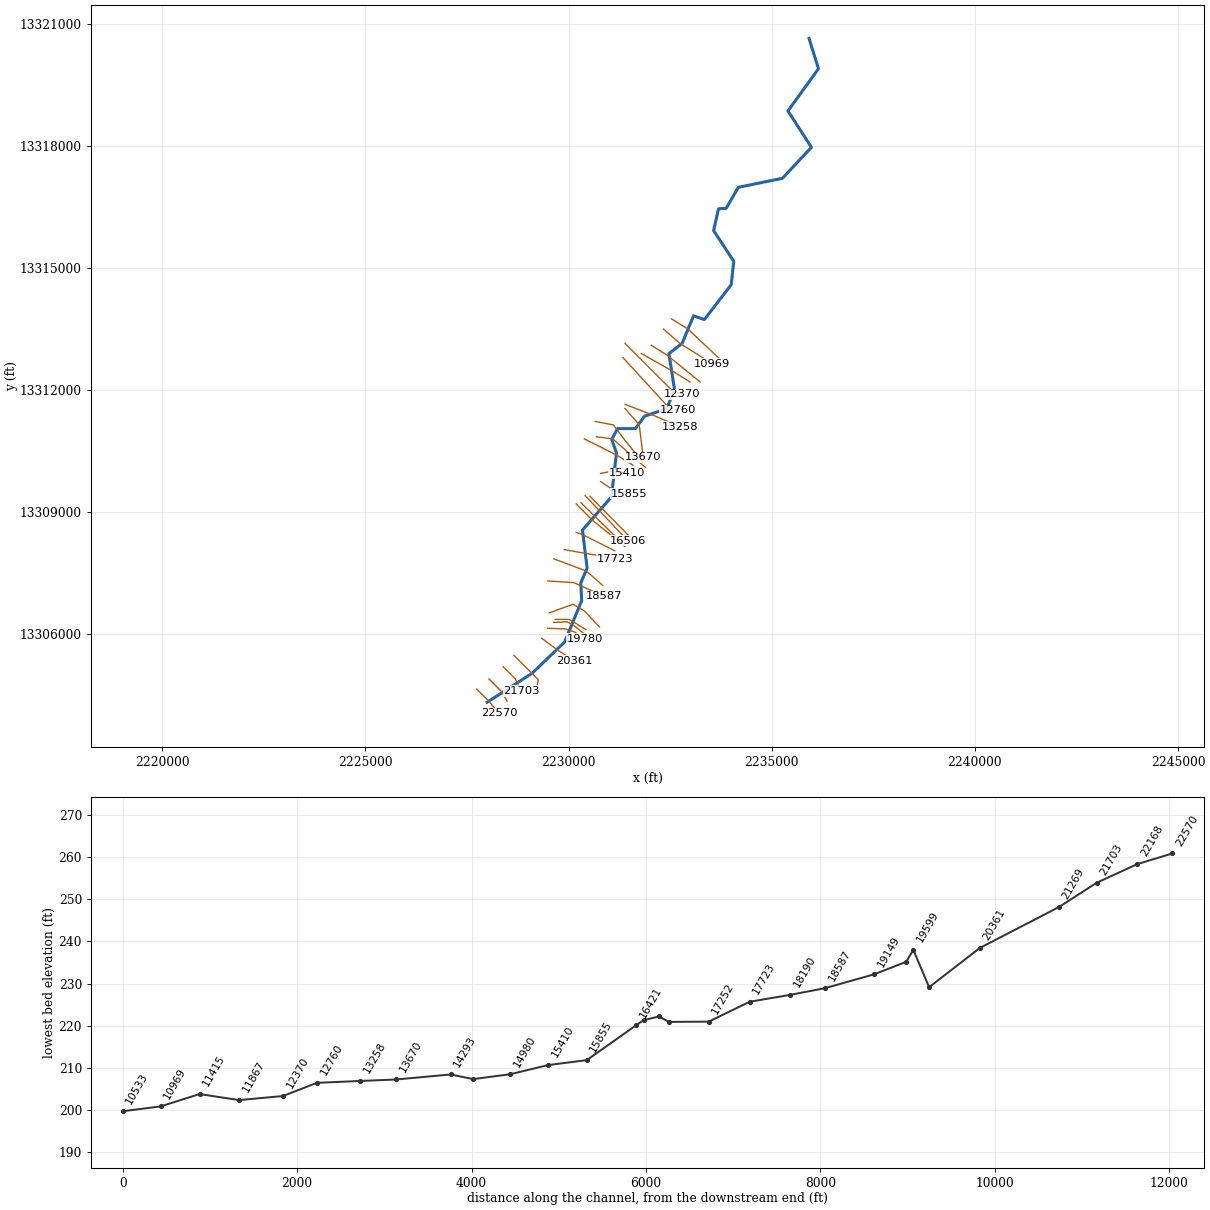
--- SOUTH FORK SALT BRANCH.prj (project) ---

Proj Title=SOUTH FORK SALT BRANCH Base Level Engineering
Current Plan=p01
Default Exp/Contr=0.3,0.1
English Units
Geom File=g01
Flow File=f01
Plan File=p01
BEGIN DESCRIPTION:
SOUTH FORK SALT BRANCH
END DESCRIPTION:

--- SOUTH FORK SALT BRANCH.p01 (plan) ---

Plan Title=Multiple Run
Short Identifier=Multiple
Geom File=g01
Flow File=f01
Subcritical Flow
K Sum by GR= 0
Std Step Tol= 0.01
Critical Tol= 0.01
Num of Std Step Trials= 20
Max Error Tol= 0.3
Flow Tol Ratio= 0.001
Split Flow NTrial= 30
Split Flow Tol= 0.02
Split Flow Ratio= 0.02
Log Output Level= 0
Friction Slope Method= 1
Unsteady Friction Slope Method= 2
Unsteady Bridges Friction Slope Method= 1
Parabolic Critical Depth
Global Vel Dist=  1 , 1 , 1
Global Log Level= 0
CheckData=True
Encroach Param= -1, 0, 0, 0
BEGIN DESCRIPTION:
Multiple Run
END DESCRIPTION:

--- SOUTH FORK SALT BRANCH.f01 (steady flow) ---

Flow Title=Multiple
Number of Profiles=7
Profile Names=10-year,25-year,50-year,1pct_min,100-year,1pct_plu,500-year
River Rch & RM= SOUTH FORK SALT ,Reach-1,22570
     200     275     338     305     412     558     624
River Rch & RM= SOUTH FORK SALT ,Reach-1,20361
     324     458     571     525     710     960    1111
River Rch & RM= SOUTH FORK SALT ,Reach-1,18587
     457     657     829     769    1040    1406    1661
River Rch & RM= SOUTH FORK SALT ,Reach-1,16795
     510     735     928     860    1163    1573    1858
River Rch & RM= SOUTH FORK SALT ,Reach-1,11415
     596     865    1097    1021    1381    1867    2223
River Rch & RM= SOUTH FORK SALT ,Reach-1,9072
     670     976    1241    1158    1566    2118    2534
River Rch & RM= SOUTH FORK SALT ,Reach-1,7269
     732    1067    1358    1268    1714    2318    2776
River Rch & RM= SOUTH FORK SALT ,Reach-1,2286
     760    1108    1411    1318    1782    2410    2887
Boundary for River Rch & Prof#=SOUTH FORK SALT ,Reach-1,1
Up Type=0
Dn Type=3
Dn Slope=0.005
Boundary for River Rch & Prof#=SOUTH FORK SALT ,Reach-1,2
Up Type=0
Dn Type=3
Dn Slope=0.005
Boundary for River Rch & Prof#=SOUTH FORK SALT ,Reach-1,3
Up Type=0
Dn Type=3
Dn Slope=0.005
Boundary for River Rch & Prof#=SOUTH FORK SALT ,Reach-1,4
Up Type=0
Dn Type=3
Dn Slope=0.005
Boundary for River Rch & Prof#=SOUTH FORK SALT ,Reach-1,5
Up Type=0
Dn Type=3
Dn Slope=0.005
Boundary for River Rch & Prof#=SOUTH FORK SALT ,Reach-1,6
Up Type=0
Dn Type=3
Dn Slope=0.005
Boundary for River Rch & Prof#=SOUTH FORK SALT ,Reach-1,7
Up Type=0
Dn Type=3
Dn Slope=0.005

--- SOUTH FORK SALT BRANCH.g01 (geometry) ---

Geom Title=Existing Conditions

River Reach=SOUTH FORK SALT ,Reach-1
Reach XY= 30
      2227995.31     13304320.68      2229100.58     13305031.71
      2229901.97     13305799.87      2230323.11     13306817.77
      2230301.49     13307256.41      2230456.94     13307617.30
      2230341.55     13308552.65      2231056.30     13309372.60
      2231178.19     13310456.93      2231062.91     13310779.26
      2231203.36     13311049.87      2231646.32     13311050.48
      2231868.77     13311354.31      2232411.47     13311537.37
      2232607.58     13312006.24      2232469.82     13312893.70
      2232795.61     13313147.64      2233075.22     13313824.57
      2233340.80     13313729.56      2234002.89     13314587.87
      2234064.71     13315165.59      2233569.54     13315919.67
      2233690.06     13316456.30      2233877.72     13316466.86
      2234178.78     13316983.56      2235263.41     13317204.99
      2235976.31     13317967.45      2235398.53     13318860.47
      2236149.57     13319899.01      2235917.72     13320646.85

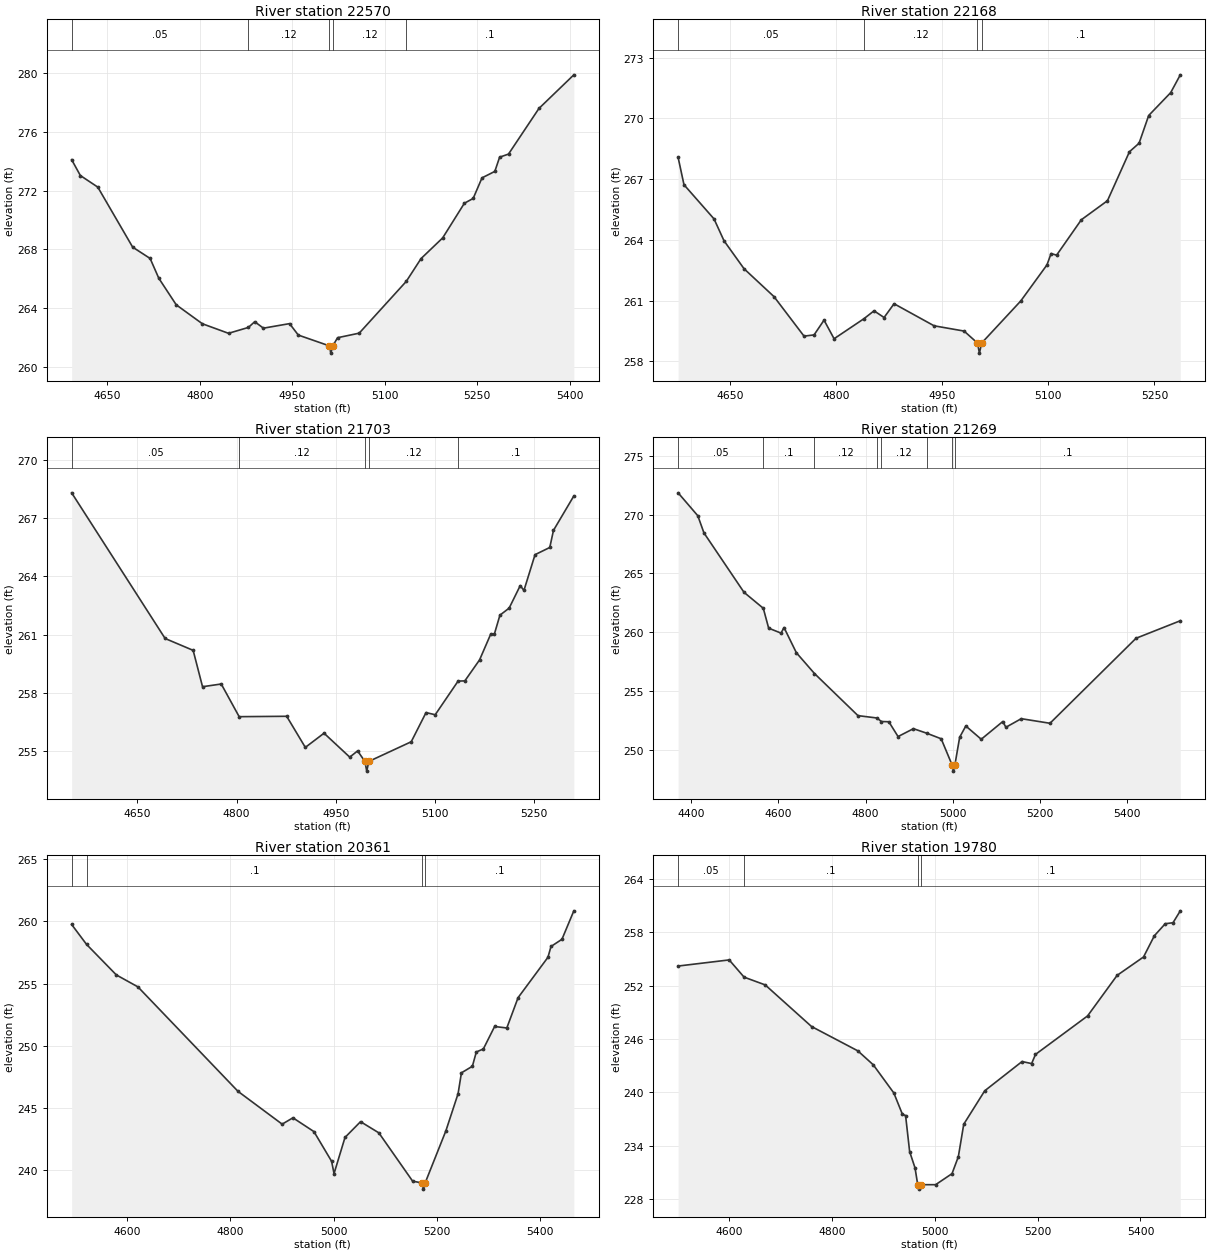
Type RM Length L Ch R = 1,22570,402,402,402
BEGIN DESCRIPTION:
SOUTH FORK SALT BRANCH 49.0
END DESCRIPTION:
XS GIS Cut Line= 3
      2227737.74     13304646.84      2228037.72     13304346.85
      2228287.69     13304046.89
#Sta/Elev= 30
  4592.0  274.12  4606.1  273.04  4634.4  272.25  4691.0  268.16  4719.3  267.39
  4733.4  266.04  4761.7  264.23  4804.1  262.94  4846.5  262.29  4878.7  262.69
  4889.0  263.08  4903.1  262.64  4945.5  262.95  4959.7  262.17  5009.7  261.44
  5012.5  260.94  5015.7  261.44  5023.4  261.99  5058.5  262.30  5134.9  265.83
  5158.8  267.38  5193.9  268.79  5229.1  271.15  5243.4  271.48  5257.7  272.88
  5278.5  273.32  5286.3  274.29  5300.7  274.50  5350.1  277.61  5406.7  279.90
#Mann=5,-1,0
  4592.0    0.05       0  4878.7    0.12       0  5009.7    0.07       0
  5015.7    0.12       0  5134.9     0.1       0
Bank Sta=5009.7,5015.7
Exp/Cntr=0.3,0.1

Type RM Length L Ch R = 1,22168,465,465,465
BEGIN DESCRIPTION:
SOUTH FORK SALT BRANCH 48.0
END DESCRIPTION:
XS GIS Cut Line= 3
      2228041.82     13304892.75      2228337.72     13304596.85
      2228487.72     13304346.86
#Sta/Elev= 30
  4576.6  268.07  4584.9  266.72  4627.4  265.03  4641.5  263.95  4669.8  262.57
  4712.2  261.19  4754.6  259.24  4768.8  259.30  4782.9  260.03  4797.1  259.11
  4839.3  260.10  4853.6  260.49  4867.8  260.16  4881.9  260.84  4938.5  259.75
  4980.9  259.49  4999.8  258.90  5002.6  258.40  5005.8  258.90  5061.1  260.98
  5098.1  262.76  5103.9  263.32  5111.7  263.24  5146.7  264.99  5183.6  265.93
  5214.7  268.35  5228.3  268.77  5241.9  270.14  5273.0  271.27  5286.6  272.15
#Mann=4,-1,0
  4576.6    0.05       0  4839.3    0.12       0  4999.8    0.07       0
  5005.8     0.1       0
Bank Sta=4999.8,5005.8
Exp/Cntr=0.3,0.1

Type RM Length L Ch R = 1,21703,434,434,434
BEGIN DESCRIPTION:
SOUTH FORK SALT BRANCH 47.0
END DESCRIPTION:
XS GIS Cut Line= 3
      2228387.73     13305196.84      2228687.72     13304896.85
      2228837.74     13304596.82
#Sta/Elev= 30
  4550.6  268.29  4692.0  260.80  4734.4  260.19  4748.6  258.32  4776.9  258.46
  4804.0  256.78  4875.9  256.80  4904.1  255.20  4932.4  255.93  4971.3  254.70
  4983.2  255.02  4994.2  254.48  4997.0  253.98  5000.2  254.48  5064.3  255.49
  5086.7  256.99  5100.6  256.88  5135.2  258.61  5145.4  258.62  5167.7  259.70
  5184.5  261.02  5190.1  261.03  5198.5  262.00  5212.4  262.36  5229.2  263.52
  5234.8  263.27  5251.6  265.11  5273.9  265.48  5279.5  266.36  5310.3  268.13
#Mann=5,-1,0
  4550.6    0.05       0  4804.0    0.12       0  4994.2    0.07       0
  5000.2    0.12       0  5135.2     0.1       0
Bank Sta=4994.2,5000.2
Exp/Cntr=0.3,0.1

Type RM Length L Ch R = 1,21269,908,908,908
BEGIN DESCRIPTION:
SOUTH FORK SALT BRANCH 46.0
END DESCRIPTION:
XS GIS Cut Line= 3
      2228653.59     13305476.58      2229253.57     13304876.60
      2229203.58     13304576.64
#Sta/Elev= 30
  4369.7  271.86  4414.9  269.91  4429.0  268.45  4520.9  263.40  4565.2  262.04
  4577.5  260.35  4605.8  259.93  4612.8  260.40  4641.1  258.26  4682.7  256.49
  4782.5  252.91  4825.9  252.71  4836.3  252.41  4853.3  252.39  4874.5  251.13
  4909.8  251.80  4940.7  251.41  4973.5  250.94  4998.8  248.69  5001.5  248.19
  5004.8  248.69  5015.9  251.07  5030.0  252.03  5065.4  250.90  5114.9  252.41
  5122.0  251.92  5157.3  252.65  5223.2  252.26  5420.7  259.49  5522.3  260.98
#Mann=8,-1,0
  4369.7    0.05       0  4565.2     0.1       0  4682.7    0.12       0
  4825.9     0.1       0  4836.3    0.12       0  4940.7     0.1       0
  4998.8    0.07       0  5004.8     0.1       0
Bank Sta=4998.8,5004.8
Exp/Cntr=0.3,0.1

Type RM Length L Ch R = 1,20361,581,581,581
BEGIN DESCRIPTION:
SOUTH FORK SALT BRANCH 44.0
END DESCRIPTION:
XS GIS Cut Line= 3
      2229337.70     13305896.87      2229737.72     13305596.85
      2230137.70     13305346.87
#Sta/Elev= 30
  4493.2  259.75  4522.0  258.15  4579.7  255.69  4621.4  254.73  4815.1  246.32
  4900.5  243.68  4921.4  244.19  4962.0  243.08  4996.2  240.69  5000.9  239.70
  5022.1  242.61  5052.2  243.88  5087.6  242.98  5153.0  239.09  5171.2  238.95
  5174.0  238.45  5177.2  238.95  5217.3  243.14  5240.9  246.13  5247.4  247.81
  5268.6  248.34  5276.2  249.49  5289.8  249.73  5311.6  251.54  5335.2  251.42
  5357.0  253.86  5414.8  257.11  5420.7  257.98  5441.9  258.56  5464.9  260.85
#Mann=4,-1,0
  4493.2    0.05       0  4522.0     0.1       0  5171.2    0.07       0
  5177.2     0.1       0
Bank Sta=5171.2,5177.2
Exp/Cntr=0.3,0.1

Type RM Length L Ch R = 1,19780,181,181,181
BEGIN DESCRIPTION:
Mapping XS dbb8d995
END DESCRIPTION:
XS GIS Cut Line= 4
      2229488.52     13306139.82      2229926.05     13306122.46
      2230148.27     13306049.54      2230403.94     13305883.70
#Sta/Elev= 30
  4501.0  254.22  4600.3  254.91  4629.3  252.97  4670.3  252.10  4760.4  247.42
  4850.5  244.68  4880.5  243.11  4920.5  239.94  4937.2  237.54  4943.3  237.41
  4951.2  233.35  4961.7  231.51  4966.9  229.63  4969.7  229.13  4972.9  229.63
  5001.7  229.63  5033.6  230.87  5045.9  232.78  5056.4  236.43  5097.2  240.19
  5169.8  243.48  5188.4  243.25  5195.9  244.28  5297.2  248.61  5354.6  253.17
  5406.0  255.24  5427.1  257.63  5448.2  258.98  5463.3  259.09  5477.5  260.43
#Mann=4,-1,0
  4501.0    0.05       0  4629.3     0.1       0  4966.9    0.07       0
  4972.9     0.1       0
Bank Sta=4966.9,4972.9
Exp/Cntr=0.3,0.1

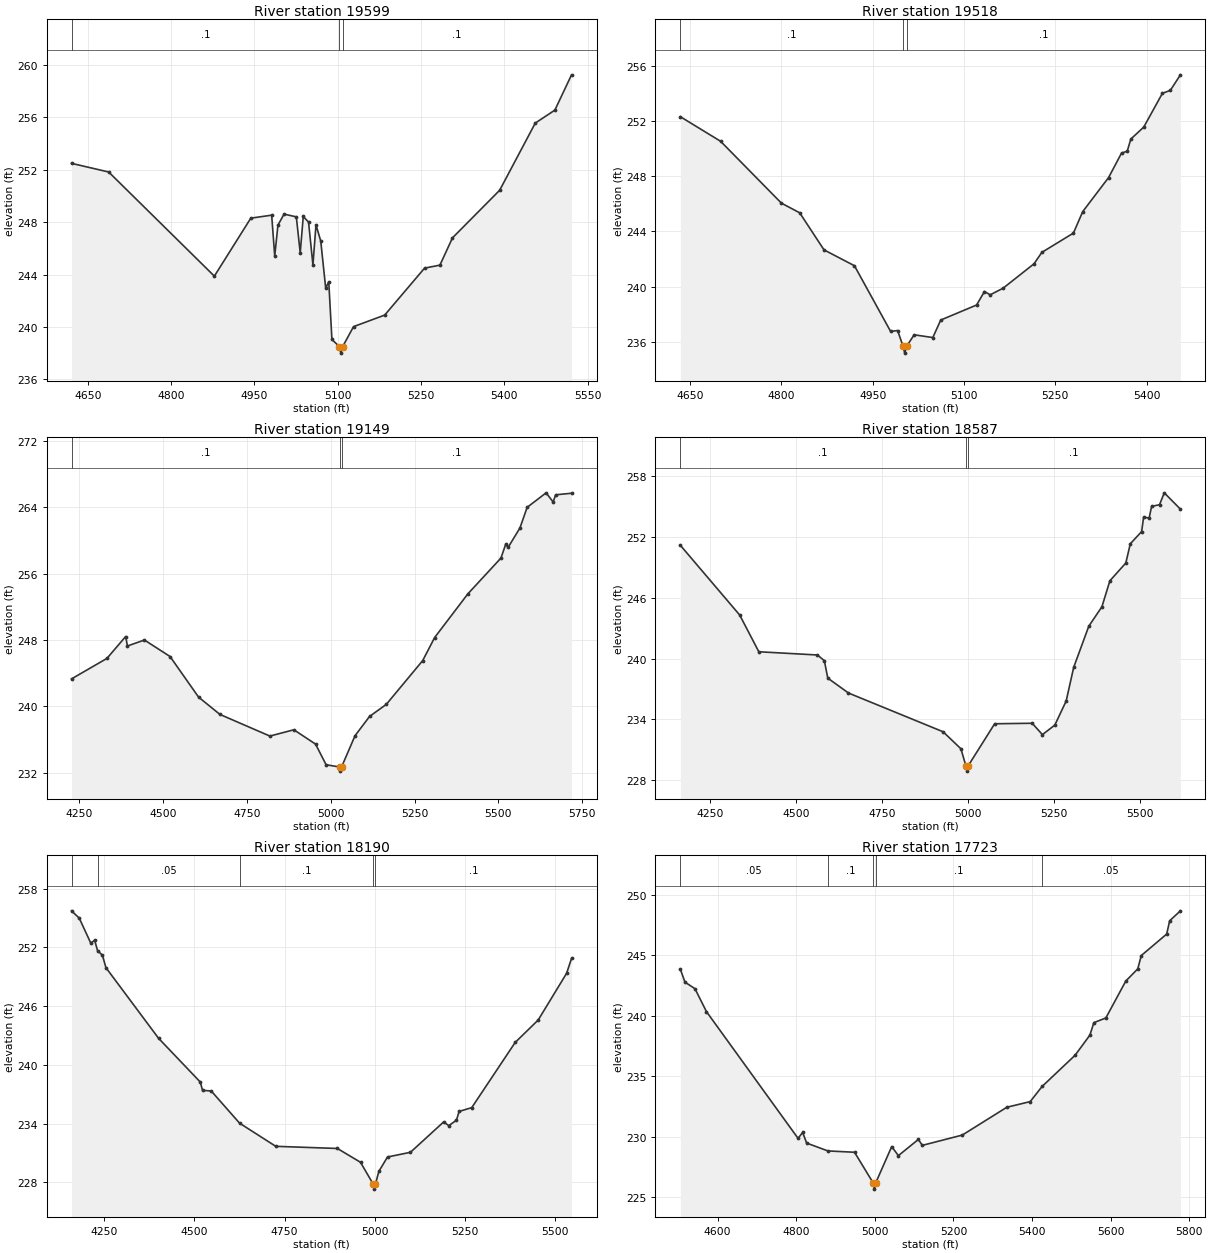
Type RM Length L Ch R = 1,19599,81,81,81
BEGIN DESCRIPTION:
Mapping XS 4efaa064
END DESCRIPTION:
XS GIS Cut Line= 4
      2229630.92     13306282.18      2229953.83     13306299.54
      2230089.25     13306237.04      2230426.06     13305973.15
#Sta/Elev= 30
  4620.7  252.48  4687.6  251.82  4877.9  243.88  4943.5  248.30  4981.1  248.53
  4986.6  245.41  4992.4  247.77  5003.4  248.61  5025.5  248.40  5032.5  245.66
  5038.0  248.43  5047.5  248.00  5055.4  244.73  5060.9  247.79  5069.5  246.55
  5078.4  242.96  5083.9  243.45  5089.6  239.05  5103.0  238.51  5105.7  238.01
  5109.0  238.51  5128.5  240.03  5184.6  240.91  5256.4  244.49  5284.1  244.72
  5306.7  246.80  5391.7  250.43  5455.8  255.55  5491.1  256.54  5521.1  259.23
#Mann=3,-1,0
  4620.7     0.1       0  5103.0    0.07       0  5109.0     0.1       0
Bank Sta=5103,5109
Exp/Cntr=0.3,0.1

Type RM Length L Ch R = 1,19518,369,369,369
BEGIN DESCRIPTION:
SOUTH FORK SALT BRANCH 42.0
END DESCRIPTION:
XS GIS Cut Line= 3
      2229671.76     13306358.66      2230021.75     13306358.66
      2230421.76     13306108.65
#Sta/Elev= 30
  4634.0  252.32  4700.0  250.54  4800.0  246.05  4830.0  245.35  4870.0  242.66
  4920.0  241.51  4979.5  236.74  4991.0  236.81  4999.8  235.67  5002.6  235.17
  5005.8  235.67  5018.1  236.50  5048.8  236.30  5061.8  237.57  5120.7  238.66
  5133.7  239.64  5143.1  239.40  5164.3  239.88  5215.1  241.65  5228.0  242.48
  5279.9  243.88  5295.2  245.44  5337.7  247.91  5358.9  249.68  5368.3  249.82
  5374.2  250.70  5395.5  251.57  5426.1  254.02  5439.1  254.23  5455.7  255.36
#Mann=3,-1,0
  4634.0     0.1       0  4999.8    0.07       0  5005.8     0.1       0
Bank Sta=4999.8,5005.8
Exp/Cntr=0.3,0.1

Type RM Length L Ch R = 1,19149,562,562,562
BEGIN DESCRIPTION:
SOUTH FORK SALT BRANCH 41.0
END DESCRIPTION:
XS GIS Cut Line= 4
      2229521.58     13306516.57      2230110.08     13306730.09
      2230380.91     13306573.84      2230761.09     13306172.83
#Sta/Elev= 30
  4226.9  243.32  4332.4  245.79  4388.3  248.43  4393.7  247.29  4444.3  248.01
  4520.7  246.02  4605.8  241.12  4669.6  239.03  4818.5  236.42  4890.0  237.18
  4954.7  235.45  4986.2  232.96  5026.3  232.69  5029.1  232.19  5032.3  232.69
  5072.4  236.46  5115.8  238.79  5165.6  240.24  5274.3  245.53  5309.9  248.31
  5409.0  253.58  5507.7  257.90  5521.9  259.57  5529.1  259.19  5564.3  261.53
  5585.8  264.02  5642.4  265.77  5663.4  264.66  5670.7  265.53  5718.2  265.72
#Mann=3,-1,0
  4226.9     0.1       0  5026.3    0.07       0  5032.3     0.1       0
Bank Sta=5026.3,5032.3
Exp/Cntr=0.3,0.1

Type RM Length L Ch R = 1,18587,397,397,397
BEGIN DESCRIPTION:
SOUTH FORK SALT BRANCH 40.0
END DESCRIPTION:
XS GIS Cut Line= 3
      2229490.29     13307303.01      2230130.91     13307261.34
      2230870.49     13306928.01
#Sta/Elev= 30
  4163.9  251.16  4336.2  244.29  4391.8  240.67  4562.2  240.35  4582.2  239.79
  4592.2  238.07  4652.4  236.60  4927.4  232.78  4979.2  231.10  4993.8  229.40
  4996.6  228.90  4999.8  229.40  5077.2  233.57  5186.3  233.62  5216.0  232.50
  5252.1  233.44  5285.0  235.81  5306.9  239.13  5350.8  243.19  5389.0  245.11
  5412.1  247.67  5458.4  249.42  5471.5  251.32  5504.4  252.52  5510.1  253.93
  5526.3  253.86  5533.3  255.00  5556.4  255.17  5570.2  256.34  5617.1  254.73
#Mann=3,-1,0
  4163.9     0.1       0  4993.8    0.07       0  4999.8     0.1       0
Bank Sta=4993.8,4999.8
Exp/Cntr=0.3,0.1

Type RM Length L Ch R = 1,18190,467,467,467
BEGIN DESCRIPTION:
SOUTH FORK SALT BRANCH 39.0
END DESCRIPTION:
XS GIS Cut Line= 3
      2229637.69     13307846.86      2230437.72     13307546.85
      2230837.69     13307196.88
#Sta/Elev= 30
  4159.5  255.73  4180.9  254.98  4212.9  252.43  4223.6  252.73  4231.7  251.65
  4245.0  251.21  4254.8  249.93  4400.7  242.72  4516.4  238.25  4522.6  237.40
  4546.7  237.34  4625.4  234.05  4725.6  231.69  4896.4  231.47  4960.5  230.06
  4995.8  227.82  4998.5  227.32  5001.8  227.82  5011.3  229.13  5035.3  230.60
  5098.9  231.08  5190.9  234.18  5205.2  233.80  5226.5  234.36  5233.7  235.25
  5268.8  235.64  5389.3  242.30  5452.9  244.58  5531.7  249.35  5545.4  250.87
#Mann=5,-1,0
  4159.5     0.1       0  4231.7    0.05       0  4625.4     0.1       0
  4995.8    0.07       0  5001.8     0.1       0
Bank Sta=4995.8,5001.8
Exp/Cntr=0.3,0.1

Type RM Length L Ch R = 1,17723,471,471,471
BEGIN DESCRIPTION:
SOUTH FORK SALT BRANCH 38.0
END DESCRIPTION:
XS GIS Cut Line= 2
      2229891.31     13308073.85      2231144.62     13307855.43
#Sta/Elev= 30
  4505.3  243.84  4516.9  242.79  4542.3  242.25  4571.4  240.36  4804.6  229.87
  4816.3  230.36  4826.5  229.48  4880.5  228.83  4948.3  228.72  4996.0  226.17
  4998.8  225.67  5002.0  226.17  5042.9  229.19  5059.9  228.44  5110.7  229.78
  5120.8  229.29  5222.4  230.14  5335.7  232.44  5395.3  232.91  5425.5  234.16
  5509.4  236.74  5547.2  238.41  5557.3  239.44  5587.8  239.83  5638.5  242.88
  5669.0  243.89  5677.9  244.99  5742.6  246.77  5750.2  247.87  5777.5  248.69
#Mann=5,-1,0
  4505.3    0.05       0  4880.5     0.1       0  4996.0    0.07       0
  5002.0     0.1       0  5425.5    0.05       0
Bank Sta=4996,5002
Exp/Cntr=0.3,0.1

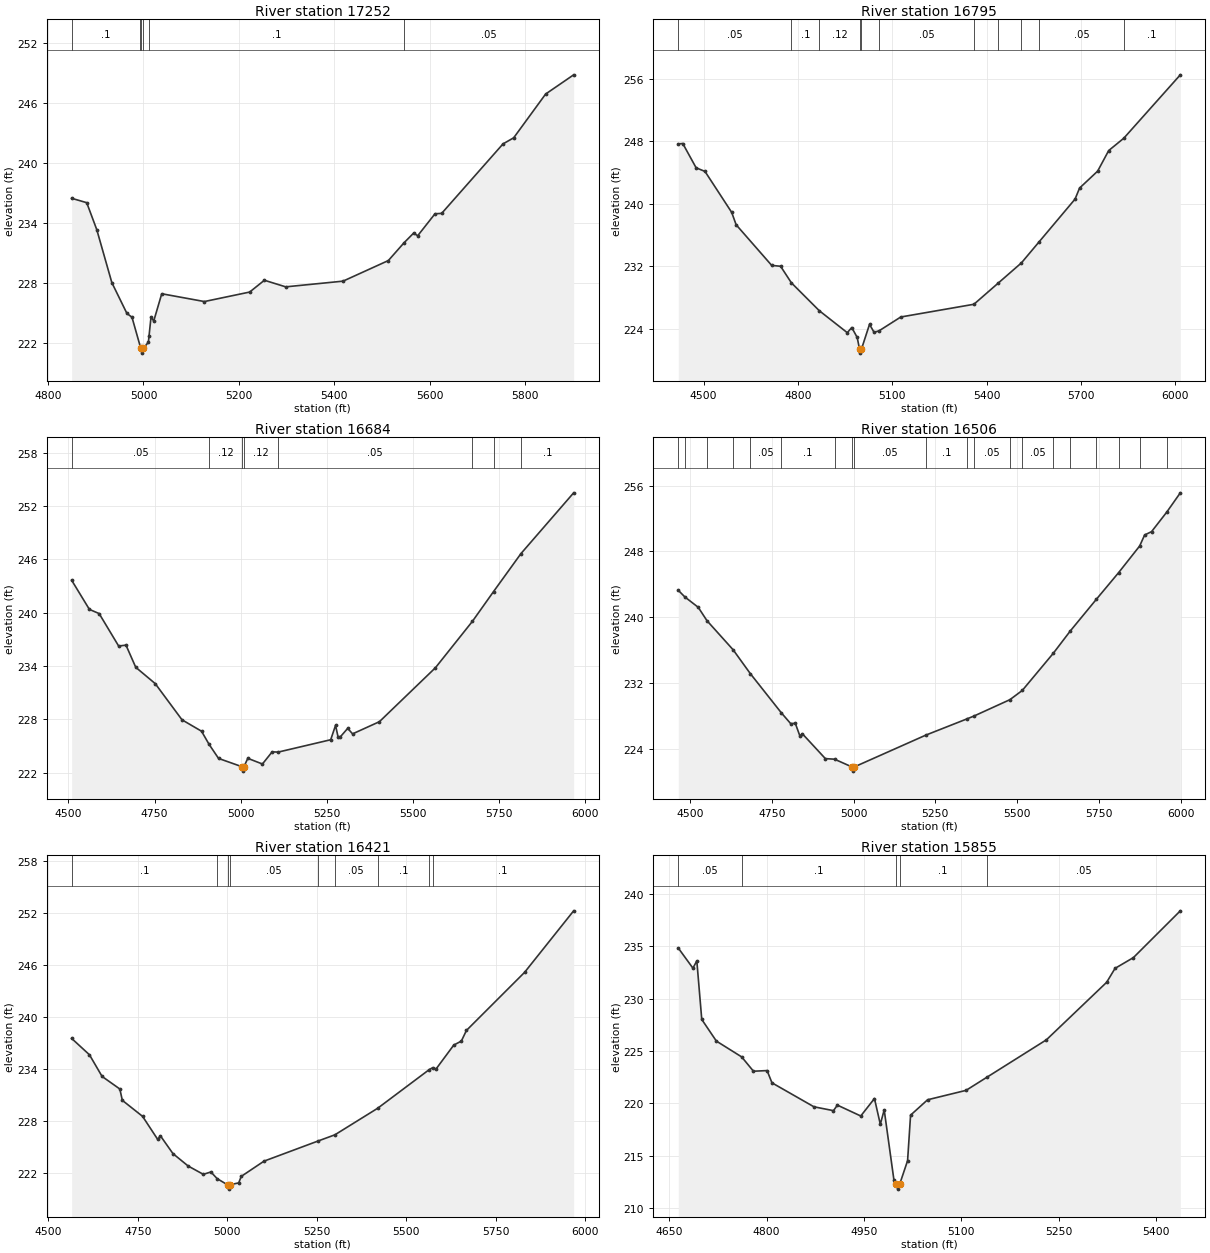
Type RM Length L Ch R = 1,17252,457,457,457
BEGIN DESCRIPTION:
SOUTH FORK SALT BRANCH 37.0
END DESCRIPTION:
XS GIS Cut Line= 3
      2230187.73     13308496.85      2230337.72     13308446.85
      2231137.69     13308046.87
#Sta/Elev= 30
  4849.4  236.43  4881.0  235.99  4902.1  233.29  4933.7  227.99  4965.3  224.91
  4975.9  224.53  4993.5  221.56  4994.0  221.44  4996.7  220.94  5000.0  221.44
  5010.3  222.03  5011.6  222.62  5015.9  224.58  5021.5  224.15  5038.3  226.88
  5127.7  226.10  5222.7  227.05  5253.5  228.23  5298.2  227.57  5418.4  228.14
  5513.4  230.20  5546.5  231.99  5566.5  232.95  5574.9  232.68  5611.2  234.88
  5625.2  234.92  5753.8  241.87  5776.2  242.48  5843.2  246.86  5901.9  248.78
#Mann=6,-1,0
  4849.4     0.1       0  4993.5    0.12       0  4994.0    0.07       0
  5000.0    0.12       0  5011.6     0.1       0  5546.5    0.05       0
Bank Sta=4994,5000
Exp/Cntr=0.3,0.1

Type RM Length L Ch R = 1,16795,111,111,111
BEGIN DESCRIPTION:
SOUTH FORK SALT BRANCH 36.0
END DESCRIPTION:
XS GIS Cut Line= 3
      2230187.69     13309196.89      2230587.72     13308796.85
      2231387.72     13308146.86
#Sta/Elev= 30
  4419.7  247.69  4433.9  247.74  4476.3  244.63  4504.6  244.16  4589.4  238.92
  4603.6  237.33  4716.7  232.12  4745.0  232.01  4779.3  229.89  4868.2  226.31
  4957.1  223.50  4971.3  224.16  4988.6  222.89  4996.1  221.38  4998.8  220.88
  5002.1  221.38  5027.8  224.57  5042.2  223.55  5057.8  223.73  5127.2  225.51
  5359.8  227.14  5437.0  229.85  5510.8  232.44  5566.7  235.12  5681.5  240.62
  5695.8  242.03  5753.3  244.20  5788.5  246.84  5836.3  248.41  6016.2  256.54
#Mann=11,-1,0
  4419.7    0.05       0  4779.3     0.1       0  4868.2    0.12       0
  4996.1    0.07       0  5002.1    0.12       0  5057.8    0.05       0
  5359.8     0.1       0  5437.0    0.05       0  5510.8     0.1       0
  5566.7    0.05       0  5836.3     0.1       0
Bank Sta=4996.1,5002.1
Exp/Cntr=0.3,0.1

Type RM Length L Ch R = 1,16684,178,178,178
BEGIN DESCRIPTION:
Mapping XS d0f2f4c4
END DESCRIPTION:
XS GIS Cut Line= 2
      2230302.81     13309224.87      2231348.34     13308210.55
#Sta/Elev= 30
  4509.3  243.65  4560.8  240.37  4589.1  239.90  4645.7  236.25  4667.0  236.35
  4695.3  233.86  4751.9  232.02  4829.6  227.95  4886.2  226.67  4908.3  225.18
  4935.6  223.61  5003.3  222.68  5006.1  222.18  5009.3  222.68  5020.5  223.62
  5062.9  222.98  5091.2  224.35  5108.6  224.32  5261.0  225.71  5275.1  227.33
  5282.3  226.04  5289.3  226.05  5310.4  226.99  5324.5  226.37  5402.4  227.74
  5565.0  233.81  5672.3  239.03  5733.5  242.37  5813.2  246.65  5966.0  253.48
#Mann=8,-1,0
  4509.3    0.05       0  4908.3    0.12       0  5003.3    0.07       0
  5009.3    0.12       0  5108.6    0.05       0  5672.3     0.1       0
  5733.5    0.05       0  5813.2     0.1       0
Bank Sta=5003.3,5009.3
Exp/Cntr=0.3,0.1

Type RM Length L Ch R = 1,16506,85,85,85
BEGIN DESCRIPTION:
Mapping XS 76cbd568
END DESCRIPTION:
XS GIS Cut Line= 2
      2230406.95     13309401.97      2231463.50     13308288.17
#Sta/Elev= 30
  4464.1  243.26  4484.6  242.44  4525.0  241.20  4551.8  239.57  4631.9  236.03
  4684.1  233.15  4779.3  228.37  4807.8  227.06  4821.9  227.10  4836.1  225.54
  4843.3  225.84  4913.8  222.81  4941.9  222.74  4995.7  221.79  4998.4  221.29
  5001.7  221.79  5221.3  225.67  5345.7  227.62  5368.6  227.99  5478.0  229.97
  5515.9  231.09  5610.4  235.59  5663.2  238.34  5742.7  242.18  5810.6  245.41
  5875.0  248.65  5890.2  249.99  5911.3  250.39  5957.9  252.77  5999.3  255.11
#Mann=20,-1,0
  4464.1    0.05       0  4484.6     0.1       0  4551.8    0.05       0
  4631.9     0.1       0  4684.1    0.05       0  4779.3     0.1       0
  4941.9    0.05       0  4995.7    0.03       0  5001.7    0.05       0
  5221.3     0.1       0  5345.7    0.08       0  5368.6    0.05       0
  5478.0    0.08       0  5515.9    0.05       0  5610.4    0.08       0
  5663.2     0.1       0  5742.7    0.05       0  5810.6     0.1       0
  5875.0    0.05       0  5957.9     0.1       0
Bank Sta=4995.7,5001.7
Exp/Cntr=0.3,0.1

Type RM Length L Ch R = 1,16421,566,566,566
BEGIN DESCRIPTION:
Mapping XS 65f36fd6
END DESCRIPTION:
XS GIS Cut Line= 2
      2230526.74     13309386.35      2231511.11     13308386.35
#Sta/Elev= 30
  4564.9  237.49  4614.7  235.60  4650.0  233.10  4699.6  231.65  4706.6  230.34
  4763.2  228.49  4805.6  225.82  4812.8  226.26  4848.1  224.19  4890.5  222.76
  4932.9  221.80  4954.2  222.07  4971.6  221.30  5000.6  220.59  5003.4  220.09
  5006.6  220.59  5031.9  220.81  5039.0  221.56  5102.6  223.32  5252.7  225.63
  5300.7  226.36  5420.1  229.42  5564.5  233.89  5574.5  234.12  5583.5  233.96
  5633.0  236.72  5654.2  237.18  5668.4  238.41  5831.0  245.12  5968.1  252.22
#Mann=9,-1,0
  4564.9     0.1       0  4971.6    0.05       0  5000.6    0.03       0
  5006.6    0.05       0  5252.7     0.1       0  5300.7    0.05       0
  5420.1     0.1       0  5564.5    0.05       0  5574.5     0.1       0
Bank Sta=5000.6,5006.6
Exp/Cntr=0.3,0.1

Type RM Length L Ch R = 1,15855,445,445,445
BEGIN DESCRIPTION:
SOUTH FORK SALT BRANCH 34.0
END DESCRIPTION:
XS GIS Cut Line= 3
      2230787.72     13309746.86      2231087.72     13309546.85
      2231487.75     13309446.85
#Sta/Elev= 30
  4664.1  234.83  4686.6  232.91  4692.6  233.61  4700.2  228.01  4722.7  225.94
  4761.6  224.43  4779.8  223.06  4800.8  223.12  4808.3  221.95  4872.9  219.66
  4903.0  219.29  4909.0  219.82  4945.0  218.78  4966.1  220.45  4975.1  217.99
  4981.1  219.36  4996.1  212.65  4999.1  212.29  5001.9  211.79  5005.1  212.29
  5017.1  214.51  5021.7  218.86  5047.9  220.33  5107.1  221.23  5138.6  222.46
  5230.8  226.06  5323.6  231.56  5336.5  232.89  5364.8  233.92  5437.0  238.39
#Mann=5,-1,0
  4664.1    0.05       0  4761.6     0.1       0  4999.1    0.07       0
  5005.1     0.1       0  5138.6    0.05       0
Bank Sta=4999.1,5005.1
Exp/Cntr=0.3,0.1

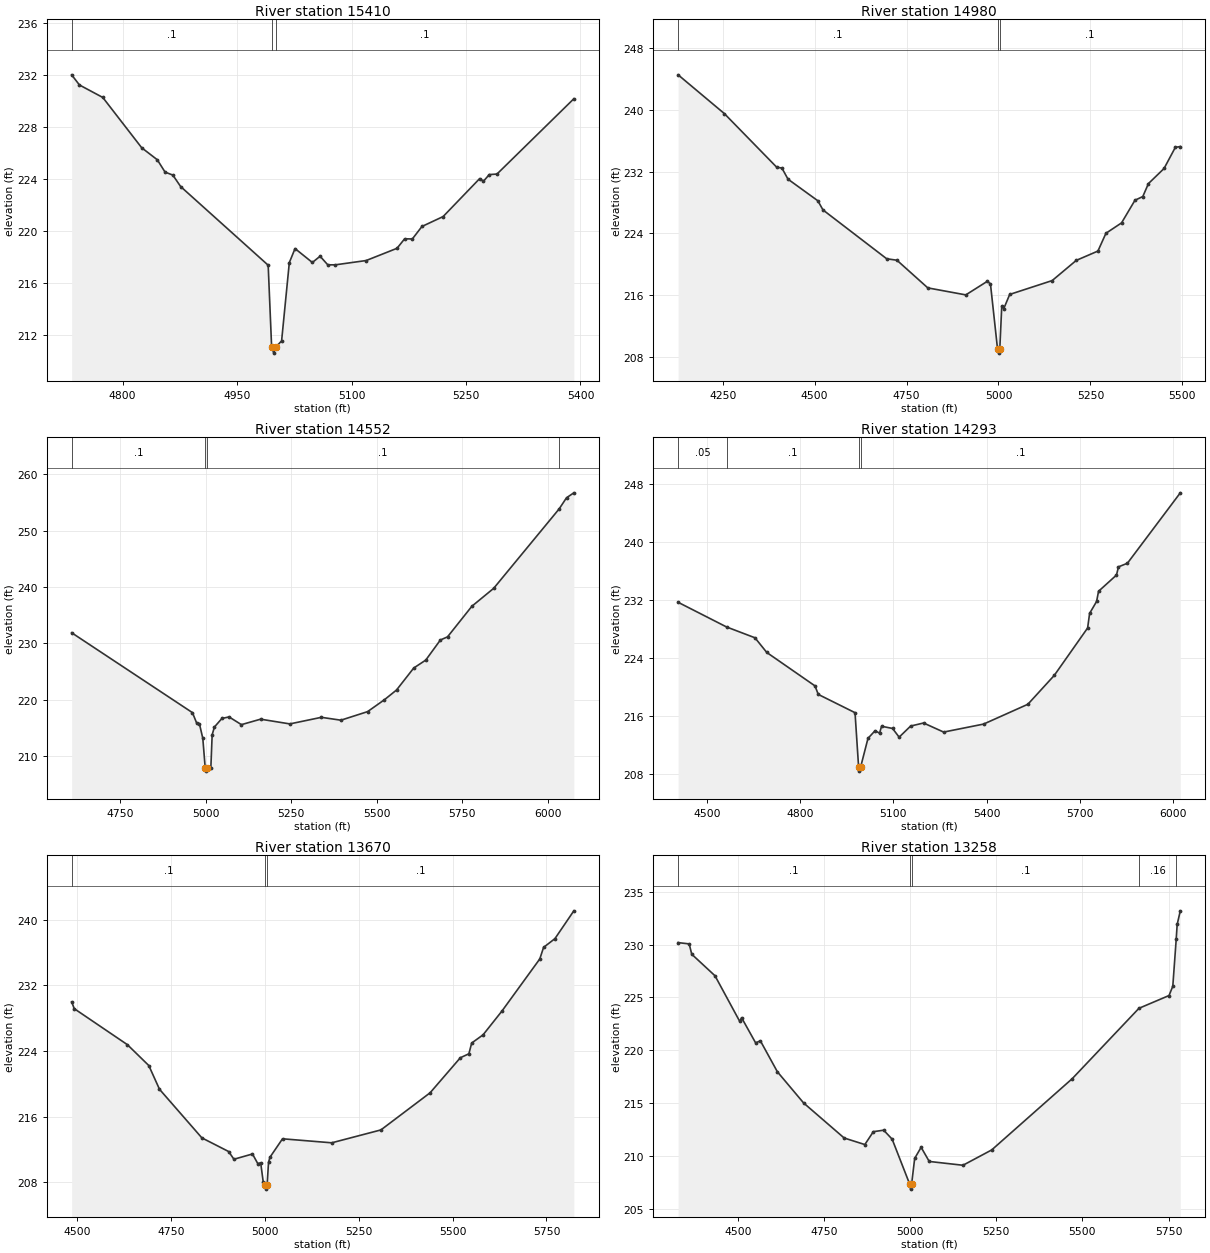
Type RM Length L Ch R = 1,15410,430,430,430
BEGIN DESCRIPTION:
SOUTH FORK SALT BRANCH 33.0
END DESCRIPTION:
XS GIS Cut Line= 3
      2230787.74     13309946.86      2231037.72     13309996.85
      2231437.68     13309946.86
#Sta/Elev= 30
  4733.3  232.01  4743.5  231.23  4774.1  230.27  4825.1  226.40  4845.5  225.48
  4855.7  224.53  4865.9  224.30  4876.1  223.42  4990.8  217.37  4995.3  211.11
  4998.1  210.61  5001.3  211.11  5008.4  211.55  5018.5  217.57  5026.0  218.65
  5048.7  217.58  5058.8  218.06  5068.9  217.40  5078.9  217.40  5119.2  217.73
  5159.6  218.67  5169.6  219.40  5179.7  219.39  5192.3  220.35  5220.0  221.11
  5267.9  224.03  5272.9  223.83  5280.5  224.34  5290.6  224.38  5391.3  230.17
#Mann=3,-1,0
  4733.3     0.1       0  4995.3    0.07       0  5001.3     0.1       0
Bank Sta=4995.3,5001.3
Exp/Cntr=0.3,0.1

Type RM Length L Ch R = 1,14980,428,428,428
BEGIN DESCRIPTION:
SOUTH FORK SALT BRANCH 32.0
END DESCRIPTION:
XS GIS Cut Line= 3
      2230387.76     13310796.83      2231187.72     13310396.85
      2231587.74     13310146.84
#Sta/Elev= 30
  4128.5  244.58  4254.2  239.55  4396.8  232.58  4410.8  232.48  4427.5  231.03
  4508.6  228.23  4522.6  227.04  4695.9  220.70  4723.8  220.51  4807.7  216.92
  4911.1  216.01  4969.8  217.78  4978.2  217.43  4997.5  208.95  5000.3  208.45
  5003.5  208.95  5008.9  214.55  5014.5  214.24  5030.5  216.07  5146.1  217.87
  5211.6  220.49  5270.5  221.70  5292.3  224.01  5334.8  225.36  5371.3  228.30
  5392.6  228.78  5407.9  230.46  5450.4  232.42  5481.0  235.16  5494.6  235.27
#Mann=3,-1,0
  4128.5     0.1       0  4997.5    0.07       0  5003.5     0.1       0
Bank Sta=4997.5,5003.5
Exp/Cntr=0.3,0.1

Type RM Length L Ch R = 1,14552,259,259,259
BEGIN DESCRIPTION:
SOUTH FORK SALT BRANCH 31.0
END DESCRIPTION:
XS GIS Cut Line= 3
      2230687.75     13310846.85      2231087.72     13310796.85
      2231887.72     13310096.85
#Sta/Elev= 30
  4609.2  231.87  4961.9  217.67  4974.5  215.77  4982.1  215.72  4992.1  213.11
  4999.2  207.78  5002.0  207.28  5005.2  207.78  5015.6  207.88  5019.4  213.74
  5026.0  215.12  5047.9  216.64  5068.8  216.91  5104.8  215.54  5160.8  216.51
  5246.2  215.67  5338.3  216.84  5395.3  216.33  5473.1  217.85  5522.4  219.97
  5557.6  221.69  5607.9  225.60  5643.0  227.01  5685.7  230.58  5706.6  231.14
  5777.7  236.58  5841.3  239.76  6032.5  253.88  6053.9  255.85  6075.3  256.73
#Mann=4,-1,0
  4609.2     0.1       0  4999.2    0.07       0  5005.2     0.1       0
  6032.5    0.05       0
Bank Sta=4999.2,5005.2
Exp/Cntr=0.3,0.1

Type RM Length L Ch R = 1,14293,623,623,623
BEGIN DESCRIPTION:
SOUTH FORK SALT BRANCH 30.0
END DESCRIPTION:
XS GIS Cut Line= 4
      2230655.20     13311226.63      2231102.27     13311139.82
      2231380.04     13310775.23      2231818.38     13310228.40
#Sta/Elev= 30
  4408.0  231.64  4563.8  228.24  4655.1  226.75  4693.0  224.73  4848.1  220.12
  4858.6  218.95  4976.8  216.43  4988.4  208.88  4991.1  208.38  4994.4  208.88
  5018.5  212.90  5041.3  213.95  5055.7  213.61  5062.1  214.56  5097.4  214.26
  5118.6  213.06  5155.6  214.59  5197.2  215.01  5261.7  213.76  5390.1  214.86
  5532.5  217.59  5617.4  221.57  5724.6  228.10  5731.0  230.11  5753.4  231.75
  5759.8  233.16  5817.4  235.39  5823.8  236.52  5852.6  237.02  6022.6  246.72
#Mann=4,-1,0
  4408.0    0.05       0  4563.8     0.1       0  4988.4    0.07       0
  4994.4     0.1       0
Bank Sta=4988.4,4994.4
Exp/Cntr=0.3,0.1

Type RM Length L Ch R = 1,13670,412,412,412
BEGIN DESCRIPTION:
SOUTH FORK SALT BRANCH 29.0
END DESCRIPTION:
XS GIS Cut Line= 3
      2231387.72     13311546.86      2231737.72     13311146.85
      2231837.72     13310346.89
#Sta/Elev= 30
  4485.2  229.99  4492.3  229.16  4633.7  224.78  4690.7  222.24  4719.2  219.35
  4832.1  213.43  4903.3  211.77  4917.5  210.83  4966.9  211.47  4981.1  210.29
  4988.7  210.40  4995.4  208.10  4999.9  207.69  5002.7  207.19  5005.9  207.69
  5009.6  210.44  5013.4  211.07  5046.9  213.32  5178.0  212.83  5309.0  214.40
  5440.0  218.92  5520.6  223.19  5543.3  223.67  5550.8  224.98  5581.1  225.98
  5631.5  228.88  5732.2  235.22  5742.3  236.63  5772.5  237.69  5822.9  241.08
#Mann=3,-1,0
  4485.2     0.1       0  4999.9    0.07       0  5005.9     0.1       0
Bank Sta=4999.9,5005.9
Exp/Cntr=0.3,0.1

Type RM Length L Ch R = 1,13258,498,498,498
BEGIN DESCRIPTION:
SOUTH FORK SALT BRANCH 28.0
END DESCRIPTION:
XS GIS Cut Line= 3
      2231387.73     13311646.85      2232037.72     13311396.85
      2232737.73     13311096.85
#Sta/Elev= 30
  4326.2  230.18  4358.3  230.06  4365.8  229.08  4433.3  227.04  4505.1  222.72
  4510.5  223.07  4551.2  220.69  4565.1  220.88  4614.4  217.95  4690.5  215.00
  4808.3  211.68  4868.3  211.06  4893.0  212.28  4923.0  212.42  4947.6  211.57
  4998.2  207.34  5000.9  206.84  5004.2  207.34  5013.0  209.75  5031.7  210.80
  5055.3  209.46  5153.2  209.10  5236.6  210.55  5470.5  217.30  5664.1  223.96
  5751.5  225.17  5762.4  226.05  5772.3  230.50  5775.1  231.90  5784.2  233.19
#Mann=5,-1,0
  4326.2     0.1       0  4998.2    0.07       0  5004.2     0.1       0
  5664.1    0.16       0  5772.3     0.1       0
Bank Sta=4998.2,5004.2
Exp/Cntr=0.3,0.1

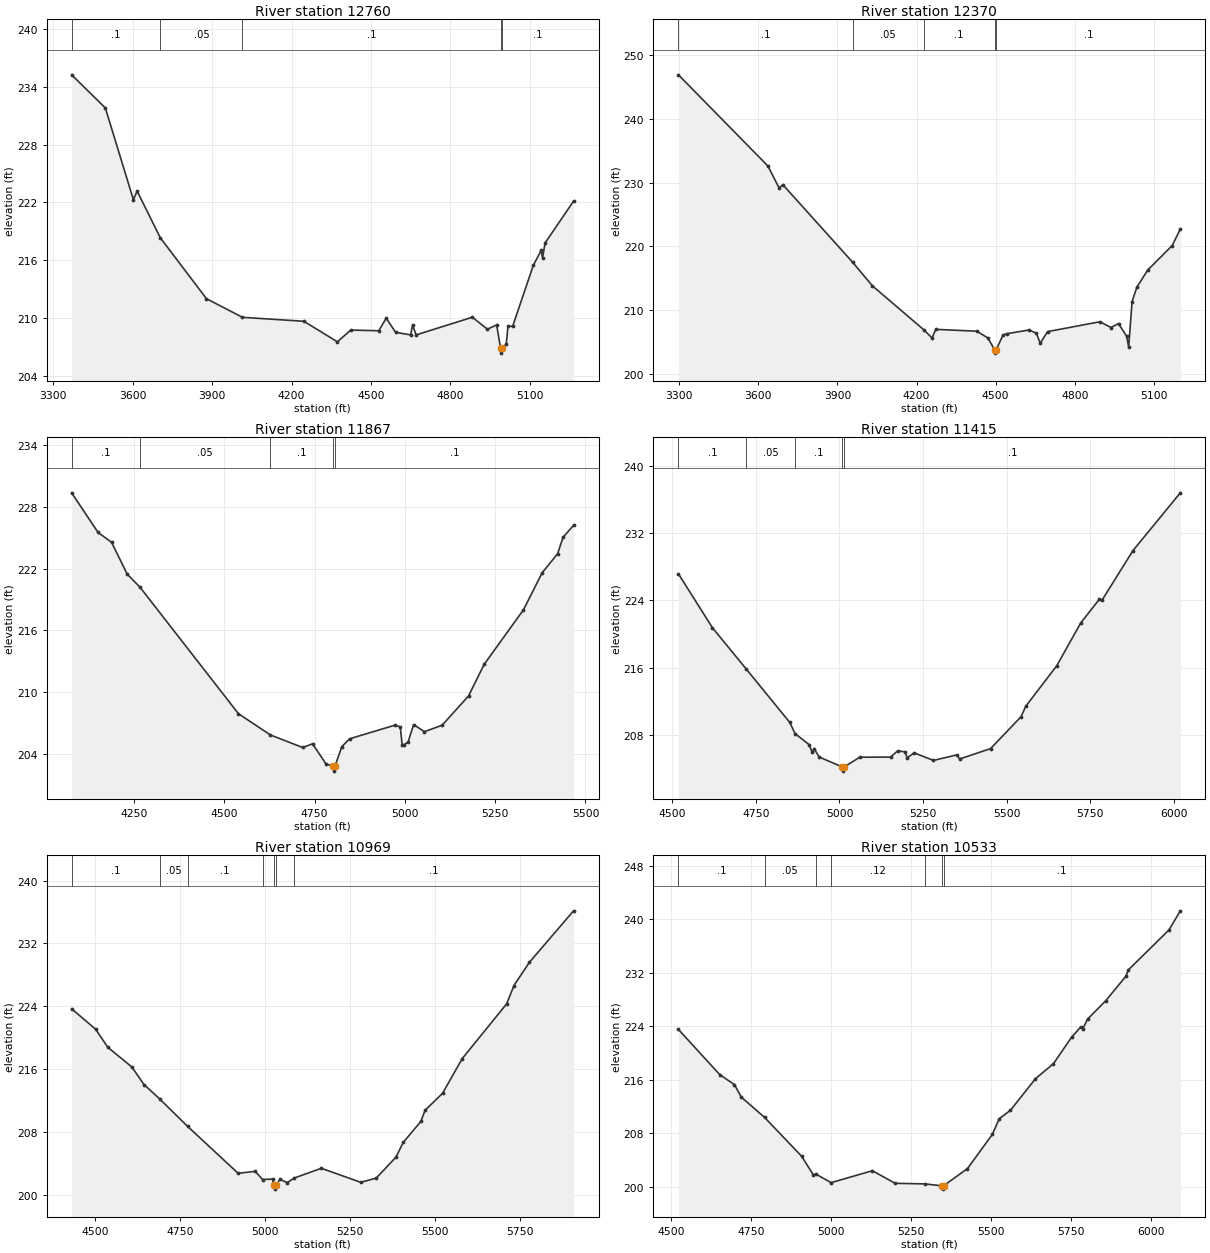
Type RM Length L Ch R = 1,12760,390,390,390
BEGIN DESCRIPTION:
SOUTH FORK SALT BRANCH 27.0
END DESCRIPTION:
XS GIS Cut Line= 3
      2231337.69     13312796.88      2232437.72     13311596.85
      2232687.74     13311496.85
#Sta/Elev= 30
  3368.9  235.23  3496.3  231.80  3602.3  222.29  3616.5  223.18  3704.1  218.34
  3878.6  212.03  4014.7  210.10  4246.7  209.69  4373.7  207.56  4423.7  208.78
  4529.7  208.71  4558.1  210.02  4593.2  208.55  4650.0  208.28  4657.4  209.28
  4671.2  208.28  4883.7  210.11  4940.4  208.87  4975.5  209.31  4990.4  206.89
  4993.2  206.39  4996.4  206.89  5011.6  207.32  5018.4  209.20  5035.9  209.16
  5113.9  215.48  5143.6  217.04  5149.0  216.26  5158.4  217.80  5266.1  222.14
#Mann=5,-1,0
  3368.9     0.1       0  3704.1    0.05       0  4014.7     0.1       0
  4990.4    0.07       0  4996.4     0.1       0
Bank Sta=4990.4,4996.4
Exp/Cntr=0.3,0.1

Type RM Length L Ch R = 1,12370,503,503,503
BEGIN DESCRIPTION:
SOUTH FORK SALT BRANCH 26.0
END DESCRIPTION:
XS GIS Cut Line= 3
      2231387.73     13313146.85      2232587.72     13311946.85
      2232787.72     13311896.85
#Sta/Elev= 30
  3297.1  246.93  3636.5  232.62  3678.9  229.17  3693.1  229.69  3957.6  217.52
  4032.5  213.82  4227.1  206.93  4258.8  205.63  4272.9  206.98  4428.5  206.69
  4470.9  205.62  4496.2  203.75  4498.9  203.25  4502.2  203.75  4527.5  206.07
  4541.6  206.29  4626.4  206.88  4654.7  206.38  4668.9  204.79  4697.2  206.63
  4895.2  208.17  4937.6  207.27  4965.9  207.89  4996.7  205.90  5004.5  204.21
  5017.3  211.33  5035.4  213.58  5076.6  216.29  5169.4  220.13  5200.3  222.72
#Mann=5,-1,0
  3297.1     0.1       0  3957.6    0.05       0  4227.1     0.1       0
  4496.2    0.07       0  4502.2     0.1       0
Bank Sta=4496.2,4502.2
Exp/Cntr=0.3,0.1

Type RM Length L Ch R = 1,11867,452,452,452
BEGIN DESCRIPTION:
SOUTH FORK SALT BRANCH 25.0
END DESCRIPTION:
XS GIS Cut Line= 3
      2231787.73     13312896.85      2232587.72     13312446.85
      2232987.75     13312196.83
#Sta/Elev= 30
  4077.4  229.38  4150.4  225.53  4188.0  224.56  4231.3  221.46  4266.5  220.20
  4539.2  207.88  4627.8  205.81  4717.0  204.59  4744.4  204.95  4782.0  202.97
  4800.7  202.79  4803.5  202.29  4806.7  202.79  4825.4  204.67  4847.1  205.44
  4972.3  206.76  4987.3  206.60  4992.4  204.87  4998.2  204.87  5008.8  205.12
  5024.2  206.82  5054.2  206.13  5103.2  206.76  5176.3  209.61  5219.3  212.67
  5328.4  218.00  5380.3  221.61  5422.7  223.44  5438.1  225.06  5467.0  226.21
#Mann=5,-1,0
  4077.4     0.1       0  4266.5    0.05       0  4627.8     0.1       0
  4800.7    0.07       0  4806.7     0.1       0
Bank Sta=4800.7,4806.7
Exp/Cntr=0.3,0.1

Type RM Length L Ch R = 1,11415,446,446,446
BEGIN DESCRIPTION:
SOUTH FORK SALT BRANCH 24.0
END DESCRIPTION:
XS GIS Cut Line= 3
      2232037.71     13313096.86      2232437.72     13312846.85
      2233237.73     13312196.85
#Sta/Elev= 30
  4517.8  227.15  4619.8  220.74  4721.0  215.84  4851.0  209.52  4867.2  208.17
  4908.7  206.89  4918.2  205.97  4924.1  206.40  4939.4  205.40  5008.1  204.23
  5010.8  203.73  5014.1  204.23  5060.6  205.38  5153.3  205.40  5174.1  206.14
  5195.7  206.02  5202.9  205.32  5223.7  205.90  5281.2  205.00  5351.5  205.66
  5359.5  205.17  5452.1  206.40  5543.6  210.19  5557.7  211.43  5650.4  216.24
  5722.2  221.32  5778.2  224.14  5786.1  224.03  5878.6  229.91  6020.3  236.76
#Mann=5,-1,0
  4517.8     0.1       0  4721.0    0.05       0  4867.2     0.1       0
  5008.1    0.07       0  5014.1     0.1       0
Bank Sta=5008.1,5014.1
Exp/Cntr=0.3,0.1

Type RM Length L Ch R = 1,10969,436,436,436
BEGIN DESCRIPTION:
SOUTH FORK SALT BRANCH 23.0
END DESCRIPTION:
XS GIS Cut Line= 3
      2232337.70     13313496.87      2232737.72     13313146.85
      2233537.69     13312646.87
#Sta/Elev= 30
  4431.7  223.70  4502.4  221.10  4538.0  218.81  4608.7  216.31  4644.3  214.08
  4690.9  212.23  4772.8  208.75  4921.0  202.80  4970.9  203.05  4992.9  202.01
  5022.2  202.07  5025.7  201.29  5028.4  200.79  5031.7  201.29  5044.0  202.02
  5065.2  201.62  5086.0  202.20  5165.5  203.44  5281.6  201.65  5327.0  202.20
  5384.8  204.86  5406.0  206.72  5457.9  209.39  5470.3  210.81  5521.6  212.96
  5579.4  217.37  5710.3  224.35  5731.5  226.66  5776.9  229.61  5906.6  236.15
#Mann=7,-1,0
  4431.7     0.1       0  4690.9    0.05       0  4772.8     0.1       0
  4992.9    0.12       0  5025.7    0.07       0  5031.7    0.12       0
  5086.0     0.1       0
Bank Sta=5025.7,5031.7
Exp/Cntr=0.3,0.1

Type RM Length L Ch R = 1,10533,442,442,442
BEGIN DESCRIPTION:
SOUTH FORK SALT BRANCH 22.0
END DESCRIPTION:
XS GIS Cut Line= 3
      2232537.75     13313746.84      2232937.72     13313496.85
      2233737.76     13312746.82
#Sta/Elev= 30
  4523.0  223.50  4652.7  216.73  4698.1  215.26  4719.3  213.40  4792.2  210.36
  4908.0  204.56  4944.5  201.77  4951.6  201.91  5000.2  200.61  5129.2  202.39
  5200.0  200.51  5293.1  200.42  5345.5  200.14  5348.3  199.64  5351.5  200.14
  5426.2  202.71  5503.9  207.81  5525.4  210.15  5560.6  211.43  5638.7  216.14
  5694.9  218.39  5751.5  222.33  5779.9  223.86  5787.2  223.64  5801.3  225.04
  5858.0  227.78  5921.5  231.47  5928.4  232.38  6055.8  238.37  6091.3  241.23
#Mann=7,-1,0
  4523.0     0.1       0  4792.2    0.05       0  4951.6     0.1       0
  5000.2    0.12       0  5293.1     0.1       0  5345.5    0.07       0
  5351.5     0.1       0
Bank Sta=5345.5,5351.5
Exp/Cntr=0.3,0.1