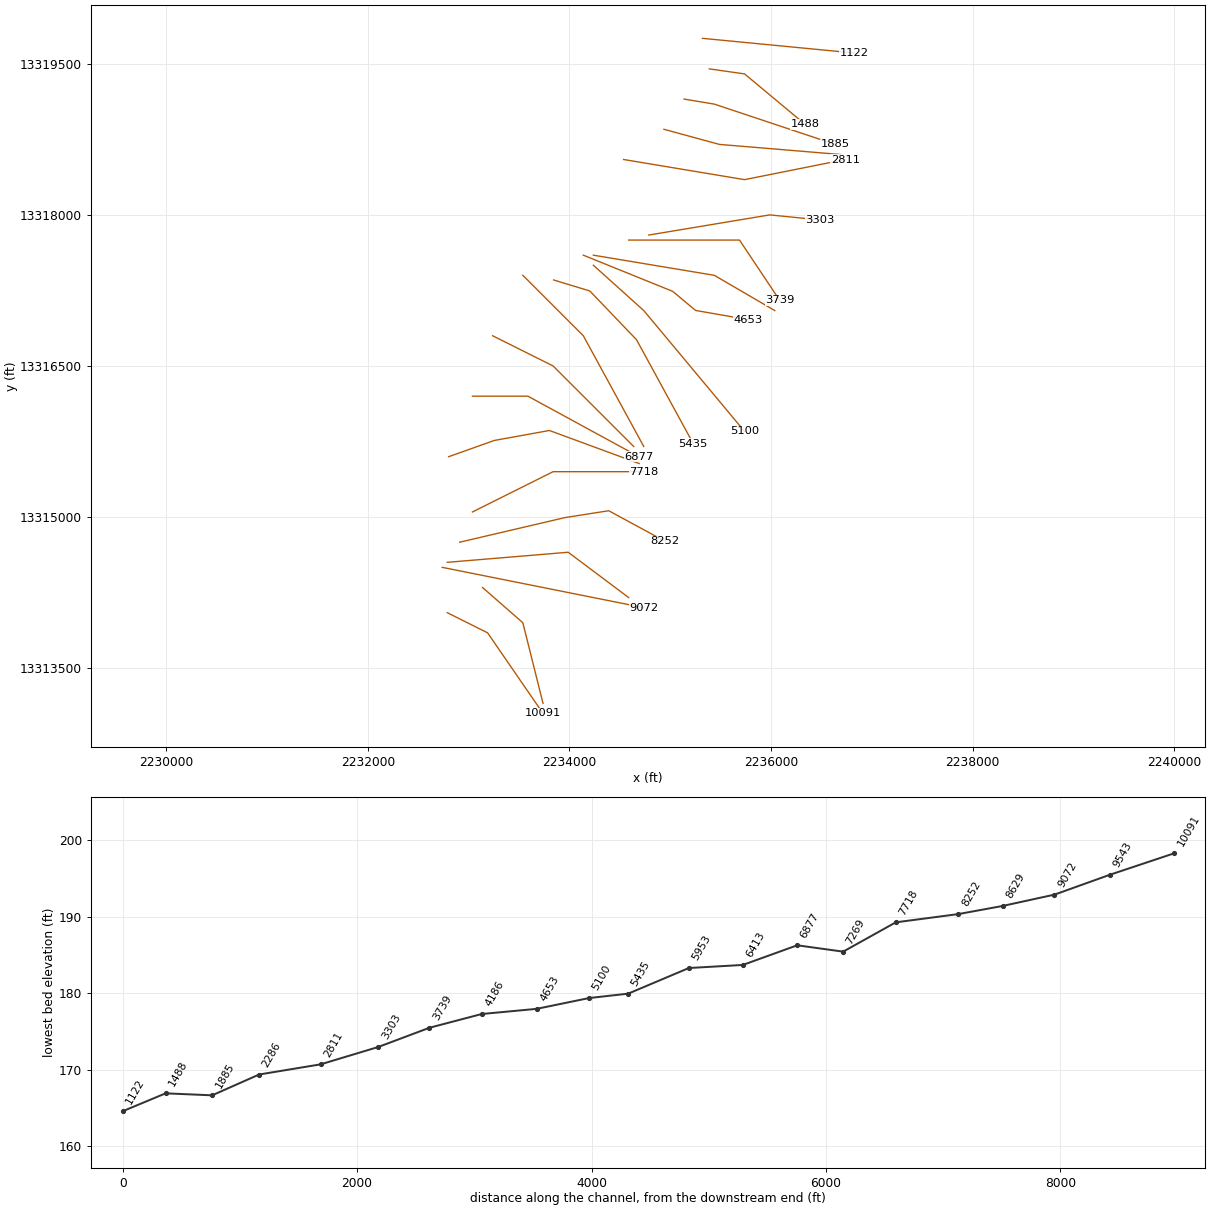
HEC-RAS study SOUTH FORK SALT BRANCH.prj: SOUTH FORK SALT BRANCH Base Level Engineering

--- SOUTH FORK SALT BRANCH.g01 (geometry) --- (continued)

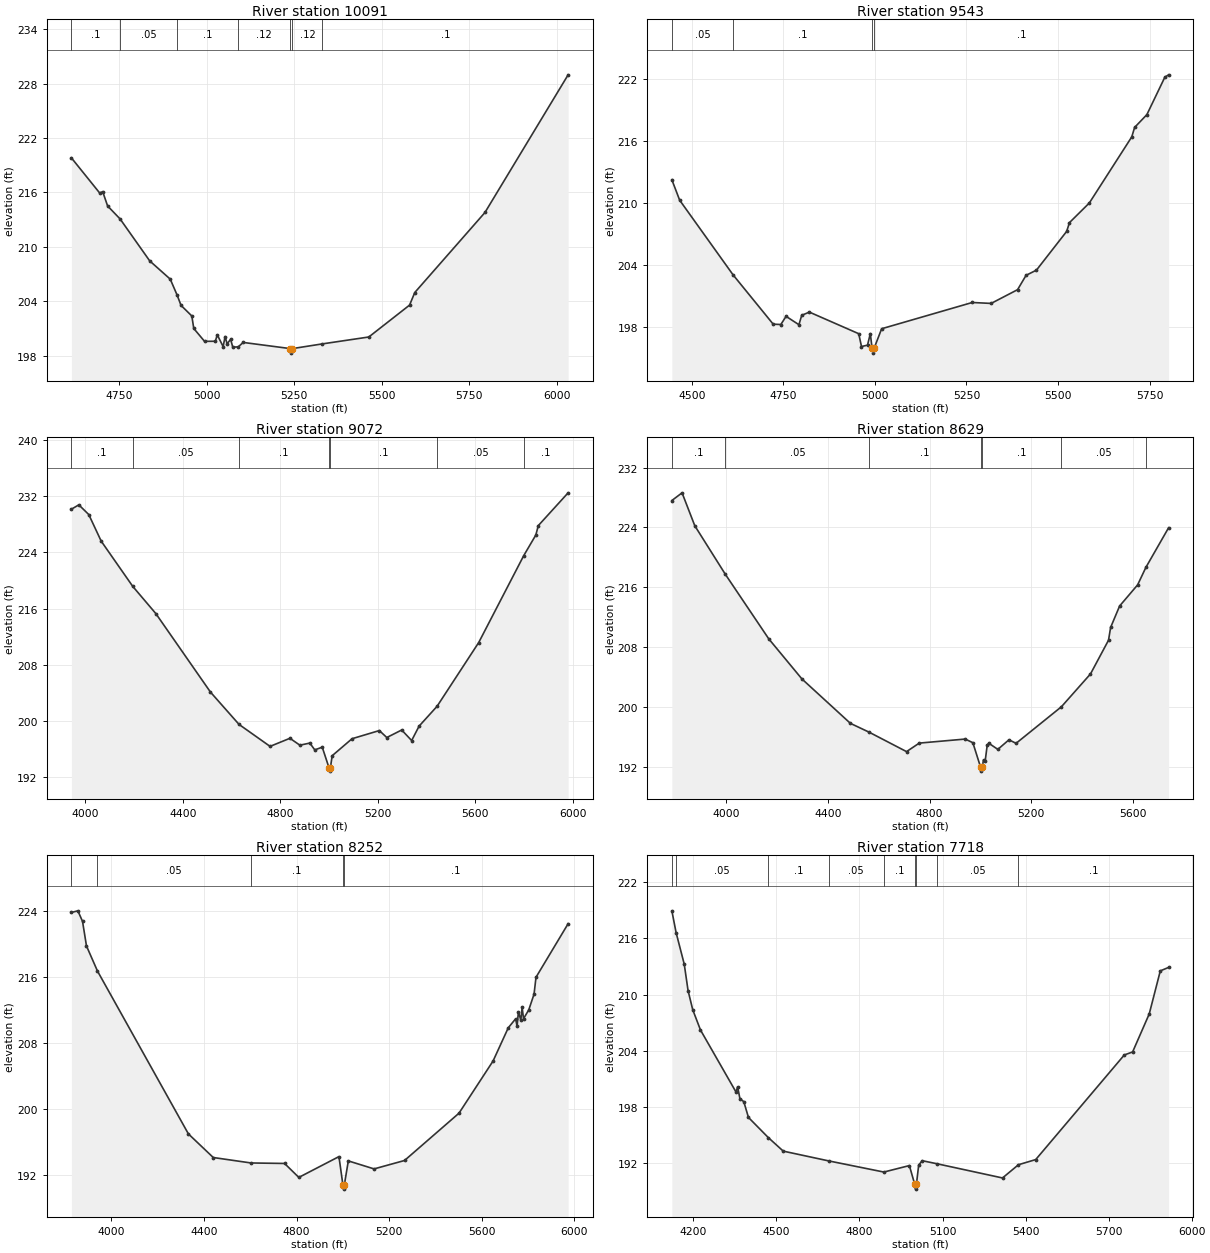
Type RM Length L Ch R = 1,10091,548,548,548
BEGIN DESCRIPTION:
SOUTH FORK SALT BRANCH 21.0
END DESCRIPTION:
XS GIS Cut Line= 3
      2232787.73     13314046.85      2233187.72     13313846.85
      2233737.71     13313046.88
#Sta/Elev= 30
  4614.0  219.82  4695.0  215.93  4703.4  216.09  4717.4  214.51  4753.2  213.07
  4837.6  208.45  4896.3  206.43  4916.1  204.65  4927.0  203.54  4957.8  202.37
  4963.4  200.99  4994.1  199.57  5024.9  199.58  5030.5  200.29  5047.2  198.99
  5052.8  200.10  5058.4  199.30  5068.6  199.79  5074.7  198.93  5090.3  198.96
  5104.5  199.45  5238.9  198.77  5241.6  198.27  5244.9  198.77  5330.5  199.29
  5463.0  200.05  5579.4  203.57  5594.3  204.96  5794.6  213.79  6032.0  228.98
#Mann=7,-1,0
  4614.0     0.1       0  4753.2    0.05       0  4916.1     0.1       0
  5090.3    0.12       0  5238.9    0.07       0  5244.9    0.12       0
  5330.5     0.1       0
Bank Sta=5238.9,5244.9
Exp/Cntr=0.3,0.1

Type RM Length L Ch R = 1,9543,471,471,471
BEGIN DESCRIPTION:
SOUTH FORK SALT BRANCH 20.0
END DESCRIPTION:
XS GIS Cut Line= 3
      2233137.73     13314296.85      2233537.72     13313946.85
      2233737.72     13313146.87
#Sta/Elev= 30
  4445.7  212.25  4467.0  210.27  4612.9  203.04  4722.4  198.27  4743.2  198.24
  4757.5  199.03  4792.6  198.22  4800.2  199.13  4821.1  199.44  4955.8  197.35
  4963.4  196.11  4979.8  196.24  4987.5  197.36  4992.2  195.97  4995.0  195.47
  4998.2  195.97  5018.4  197.83  5265.8  200.37  5317.3  200.28  5389.5  201.61
  5412.7  203.00  5441.0  203.50  5523.5  207.25  5531.2  208.10  5585.4  210.00
  5701.3  216.40  5709.0  217.31  5742.5  218.55  5791.5  222.17  5801.8  222.40
#Mann=4,-1,0
  4445.7    0.05       0  4612.9     0.1       0  4992.2    0.07       0
  4998.2     0.1       0
Bank Sta=4992.2,4998.2
Exp/Cntr=0.3,0.1

Type RM Length L Ch R = 1,9072,443,443,443
BEGIN DESCRIPTION:
SOUTH FORK SALT BRANCH 19.0
END DESCRIPTION:
XS GIS Cut Line= 3
      2232737.73     13314496.85      2233737.72     13314296.85
      2234737.72     13314096.85
#Sta/Elev= 30
  3942.1  230.13  3972.7  230.75  4013.5  229.37  4064.5  225.59  4194.2  219.15
  4288.8  215.29  4513.2  204.12  4630.6  199.52  4757.9  196.40  4839.5  197.55
  4880.3  196.57  4921.1  196.87  4941.5  195.90  4972.1  196.29  4999.7  193.38
  5002.4  192.88  5005.7  193.38  5012.9  195.07  5094.5  197.49  5206.6  198.65
  5237.2  197.66  5298.4  198.73  5339.2  197.23  5369.8  199.28  5443.6  202.10
  5614.6  211.17  5799.6  223.54  5849.1  226.46  5859.3  227.80  5981.7  232.46
#Mann=7,-1,0
  3942.1     0.1       0  4194.2    0.05       0  4630.6     0.1       0
  4999.7    0.07       0  5005.7     0.1       0  5443.6    0.05       0
  5799.6     0.1       0
Bank Sta=4999.7,5005.7
Exp/Cntr=0.3,0.1

Type RM Length L Ch R = 1,8629,377,377,377
BEGIN DESCRIPTION:
SOUTH FORK SALT BRANCH 18.0
END DESCRIPTION:
XS GIS Cut Line= 3
      2232787.75     13314546.86      2233987.72     13314646.85
      2234587.69     13314196.87
#Sta/Elev= 30
  3786.1  227.60  3826.2  228.63  3876.4  224.22  3996.9  217.71  4167.4  209.09
  4297.8  203.73  4488.5  197.79  4562.7  196.60  4709.3  194.01  4759.4  195.15
  4940.1  195.69  4970.2  195.20  5000.8  191.90  5003.5  191.40  5006.8  191.90
  5012.1  192.92  5018.4  192.69  5026.7  194.89  5032.9  195.13  5068.4  194.31
  5112.1  195.59  5140.2  195.12  5318.5  200.01  5432.9  204.40  5503.8  208.91
  5512.1  210.62  5547.5  213.49  5618.4  216.32  5650.9  218.66  5740.2  223.96
#Mann=7,-1,0
  3786.1     0.1       0  3996.9    0.05       0  4562.7     0.1       0
  5000.8    0.07       0  5006.8     0.1       0  5318.5    0.05       0
  5650.9     0.1       0
Bank Sta=5000.8,5006.8
Exp/Cntr=0.3,0.1

Type RM Length L Ch R = 1,8252,534,534,534
BEGIN DESCRIPTION:
SOUTH FORK SALT BRANCH 17.0
END DESCRIPTION:
XS GIS Cut Line= 4
      2232910.75     13314746.59      2233957.59     13314991.38
      2234389.88     13315059.09      2234947.14     13314757.02
#Sta/Elev= 30
  3827.0  223.86  3855.0  224.06  3875.2  222.78  3892.3  219.80  3939.8  216.76
  4332.7  197.03  4440.1  194.17  4603.1  193.51  4748.2  193.45  4809.8  191.76
  4983.2  194.28  5000.4  190.84  5003.2  190.34  5006.4  190.84  5023.7  193.76
  5135.0  192.79  5266.6  193.81  5501.9  199.54  5649.3  205.87  5714.9  209.89
  5746.7  210.98  5752.9  210.07  5758.6  211.81  5769.1  210.83  5774.8  212.35
  5780.8  210.99  5803.5  212.06  5826.3  213.97  5834.7  216.01  5973.5  222.50
#Mann=5,-1,0
  3827.0     0.1       0  3939.8    0.05       0  4603.1     0.1       0
  5000.4    0.07       0  5006.4     0.1       0
Bank Sta=5000.4,5006.4
Exp/Cntr=0.3,0.1

Type RM Length L Ch R = 1,7718,449,449,449
BEGIN DESCRIPTION:
SOUTH FORK SALT BRANCH 16.0
END DESCRIPTION:
XS GIS Cut Line= 3
      2233037.76     13315046.88      2233837.72     13315446.85
      2234737.74     13315446.85
#Sta/Elev= 30
  4122.3  218.92  4137.7  216.59  4167.0  213.24  4180.9  210.41  4197.7  208.38
  4225.7  206.22  4354.2  199.60  4359.8  200.16  4368.2  198.90  4382.2  198.58
  4399.0  196.90  4470.8  194.75  4524.7  193.31  4688.5  192.27  4888.1  191.08
  4980.3  191.77  4999.7  189.76  5002.5  189.26  5005.7  189.76  5013.9  191.82
  5026.7  192.29  5080.7  191.96  5316.7  190.45  5374.3  191.86  5436.7  192.41
  5756.7  203.56  5786.7  203.88  5846.7  207.93  5886.7  212.52  5916.7  212.89
#Mann=9,-1,0
  4122.3     0.1       0  4137.7    0.05       0  4470.8     0.1       0
  4688.5    0.05       0  4888.1     0.1       0  4999.7    0.07       0
  5005.7     0.1       0  5080.7    0.05       0  5374.3     0.1       0
Bank Sta=4999.7,5005.7
Exp/Cntr=0.3,0.1

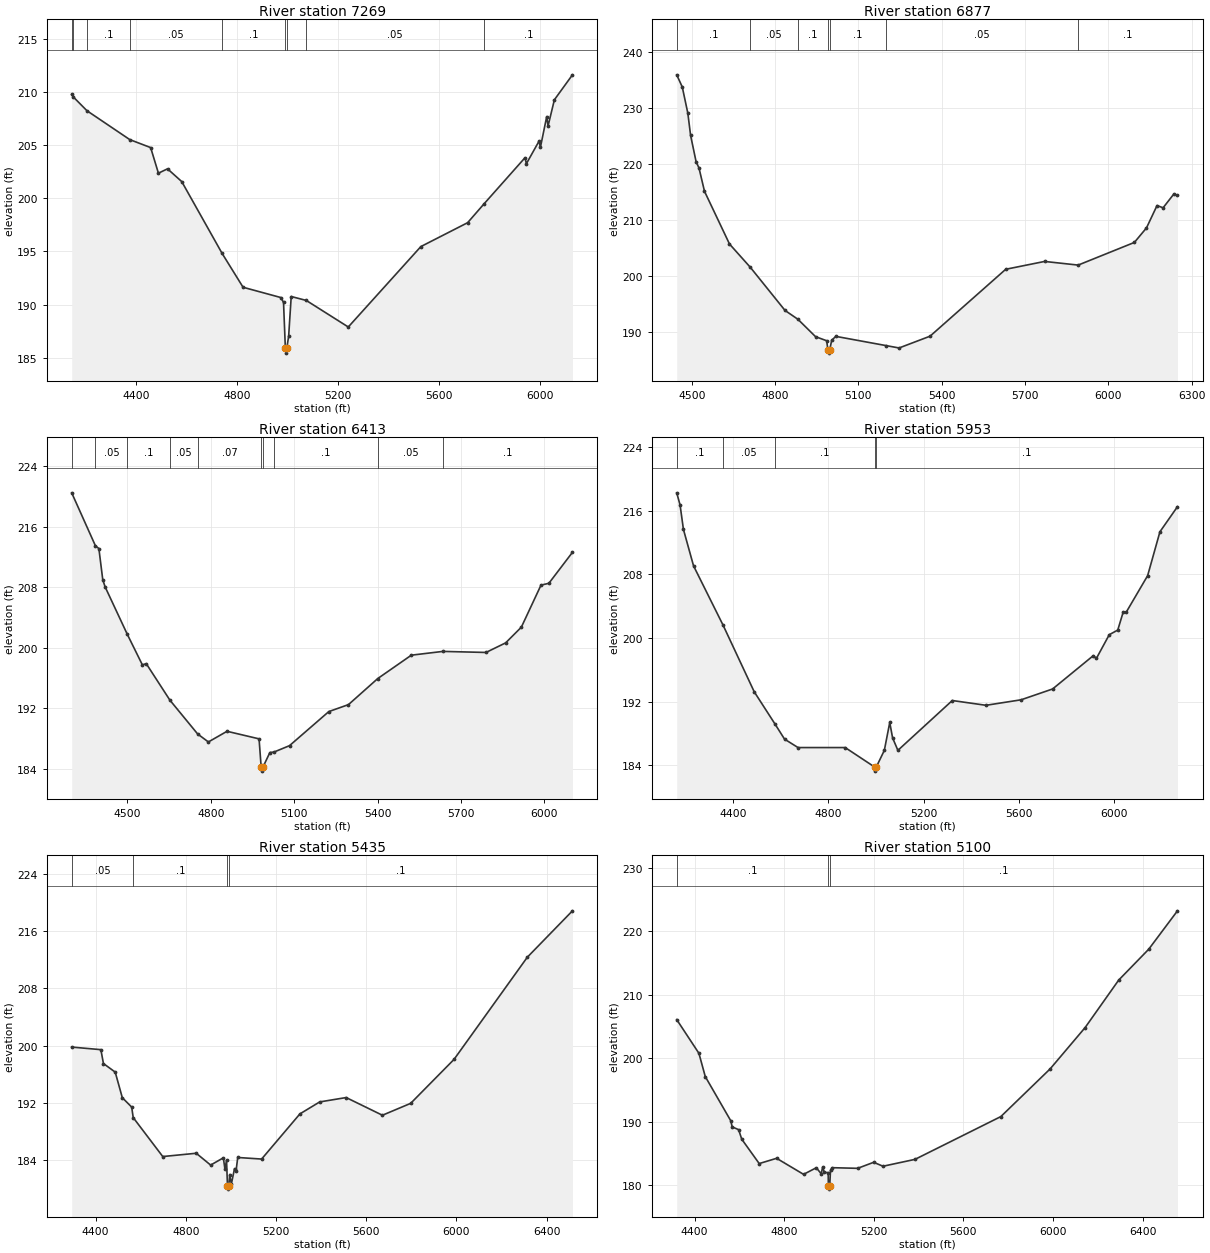
Type RM Length L Ch R = 1,7269,392,392,392
BEGIN DESCRIPTION:
SOUTH FORK SALT BRANCH 15.0
END DESCRIPTION:
XS GIS Cut Line= 4
      2232801.30     13315595.53      2233254.47     13315757.00
      2233801.34     13315855.96      2234691.98     13315527.83
#Sta/Elev= 30
  4143.3  209.78  4150.4  209.53  4203.8  208.25  4373.7  205.53  4456.4  204.78
  4487.2  202.37  4523.3  202.78  4579.7  201.58  4740.0  194.81  4823.0  191.63
  4973.2  190.66  4983.4  190.20  4990.6  185.93  4993.3  185.43  4996.6  185.93
  5003.7  187.02  5013.9  190.76  5073.6  190.39  5240.2  187.89  5528.0  195.46
  5713.6  197.71  5779.6  199.51  5941.2  203.83  5946.5  203.26  5996.8  205.39
  6002.1  204.79  6027.2  207.70  6032.5  206.81  6057.6  209.28  6129.3  211.63
#Mann=9,-1,0
  4143.3     0.1       0  4150.4    0.05       0  4203.8     0.1       0
  4373.7    0.05       0  4740.0     0.1       0  4990.6    0.07       0
  4996.6     0.1       0  5073.6    0.05       0  5779.6     0.1       0
Bank Sta=4990.6,4996.6
Exp/Cntr=0.3,0.1

Type RM Length L Ch R = 1,6877,464,464,464
BEGIN DESCRIPTION:
SOUTH FORK SALT BRANCH 14.0
END DESCRIPTION:
XS GIS Cut Line= 3
      2233037.77     13316196.85      2233587.72     13316196.85
      2234687.76     13315596.83
#Sta/Elev= 30
  4446.0  235.89  4466.0  233.72  4486.0  229.05  4496.0  225.08  4516.0  220.34
  4526.0  219.31  4546.0  215.12  4636.0  205.72  4710.9  201.57  4836.0  193.87
  4882.3  192.30  4946.0  189.19  4986.0  188.47  4990.5  186.76  4993.2  186.26
  4996.5  186.76  5004.0  188.55  5018.7  189.25  5198.0  187.62  5246.6  187.18
  5358.1  189.28  5630.5  201.21  5770.5  202.61  5891.4  201.96  6093.8  206.00
  6137.4  208.59  6175.4  212.58  6197.2  212.18  6235.2  214.59  6249.0  214.41
#Mann=7,-1,0
  4446.0     0.1       0  4710.9    0.05       0  4882.3     0.1       0
  4990.5    0.07       0  4996.5     0.1       0  5198.0    0.05       0
  5891.4     0.1       0
Bank Sta=4990.5,4996.5
Exp/Cntr=0.3,0.1

Type RM Length L Ch R = 1,6413,460,460,460
BEGIN DESCRIPTION:
SOUTH FORK SALT BRANCH 13.0
END DESCRIPTION:
XS GIS Cut Line= 3
      2233237.74     13316796.84      2233837.72     13316496.85
      2234637.74     13315696.83
#Sta/Elev= 30
  4299.4  220.51  4384.8  213.50  4397.2  213.14  4411.2  209.01  4419.6  208.07
  4499.5  201.79  4553.7  197.75  4567.7  197.91  4652.8  193.08  4752.8  188.60
  4791.3  187.55  4858.4  188.96  4973.7  187.96  4981.3  184.19  4984.1  183.69
  4987.3  184.19  5012.6  186.15  5027.1  186.21  5083.3  187.06  5224.8  191.57
  5295.5  192.49  5400.9  195.94  5521.7  199.03  5635.3  199.53  5790.4  199.39
  5861.2  200.66  5917.7  202.74  5988.4  208.30  6016.7  208.54  6101.6  212.64
#Mann=10,-1,0
  4299.4     0.1       0  4384.8    0.05       0  4499.5     0.1       0
  4652.8    0.05       0  4752.8    0.07       0  4981.3    0.07       0
  4987.3    0.07       0  5027.1     0.1       0  5400.9    0.05       0
  5635.3     0.1       0
Bank Sta=4981.3,4987.3
Exp/Cntr=0.3,0.1

Type RM Length L Ch R = 1,5953,518,518,518
BEGIN DESCRIPTION:
SOUTH FORK SALT BRANCH 12.0
END DESCRIPTION:
XS GIS Cut Line= 3
      2233537.75     13317396.82      2234137.72     13316796.85
      2234737.73     13315696.84
#Sta/Elev= 30
  4164.1  218.25  4178.2  216.72  4192.3  213.65  4234.8  209.07  4358.9  201.61
  4489.3  193.26  4576.7  189.20  4616.6  187.31  4673.2  186.25  4871.2  186.25
  4995.4  183.79  4998.2  183.29  5001.4  183.79  5035.4  185.90  5058.1  189.40
  5070.0  187.47  5092.3  185.90  5320.6  192.16  5462.0  191.56  5609.2  192.25
  5741.6  193.61  5912.5  197.80  5925.3  197.45  5979.4  200.43  6015.0  201.01
  6037.8  203.27  6050.6  203.26  6140.3  207.84  6192.0  213.36  6265.6  216.51
#Mann=5,-1,0
  4164.1     0.1       0  4358.9    0.05       0  4576.7     0.1       0
  4995.4    0.07       0  5001.4     0.1       0
Bank Sta=4995.4,5001.4
Exp/Cntr=0.3,0.1

Type RM Length L Ch R = 1,5435,335,335,335
BEGIN DESCRIPTION:
SOUTH FORK SALT BRANCH 11.0
END DESCRIPTION:
XS GIS Cut Line= 4
      2233843.04     13317350.74      2234202.38     13317241.38
      2234665.92     13316757.00      2235228.40     13315725.79
#Sta/Elev= 30
  4293.8  199.78  4423.1  199.42  4434.6  197.48  4486.8  196.28  4518.2  192.71
  4559.8  191.40  4566.6  189.93  4697.6  184.49  4846.1  184.95  4909.9  183.30
  4966.3  184.31  4973.5  182.71  4980.4  183.99  4984.6  180.44  4987.4  179.94
  4990.6  180.44  4994.5  181.98  5001.8  180.66  5015.9  182.81  5022.8  182.52
  5030.1  184.36  5136.0  184.14  5305.9  190.45  5393.6  192.12  5510.9  192.73
  5671.7  190.26  5797.0  191.92  5989.3  198.06  6314.3  212.33  6514.5  218.81
#Mann=4,-1,0
  4293.8    0.05       0  4566.6     0.1       0  4984.6    0.07       0
  4990.6     0.1       0
Bank Sta=4984.6,4990.6
Exp/Cntr=0.3,0.1

Type RM Length L Ch R = 1,5100,447,447,447
BEGIN DESCRIPTION:
SOUTH FORK SALT BRANCH 10.0
END DESCRIPTION:
XS GIS Cut Line= 3
      2234237.75     13317496.83      2234737.72     13317046.85
      2235737.73     13315846.85
#Sta/Elev= 30
  4320.5  206.09  4419.5  200.78  4447.9  197.11  4561.5  190.15  4568.2  189.17
  4596.6  188.74  4610.8  187.23  4688.6  183.39  4766.3  184.22  4886.6  181.69
  4943.4  182.73  4965.1  181.79  4971.8  182.83  4979.3  182.00  4996.4  181.96
  4997.3  179.86  5000.0  179.36  5003.3  179.86  5006.8  182.34  5014.6  182.74
  5127.9  182.64  5199.5  183.59  5241.1  182.97  5383.7  184.05  5767.0  190.80
  5987.0  198.32  6143.2  204.84  6292.9  212.32  6427.0  217.19  6555.2  223.24
#Mann=3,-1,0
  4320.5     0.1       0  4997.3    0.07       0  5003.3     0.1       0
Bank Sta=4997.3,5003.3
Exp/Cntr=0.3,0.1

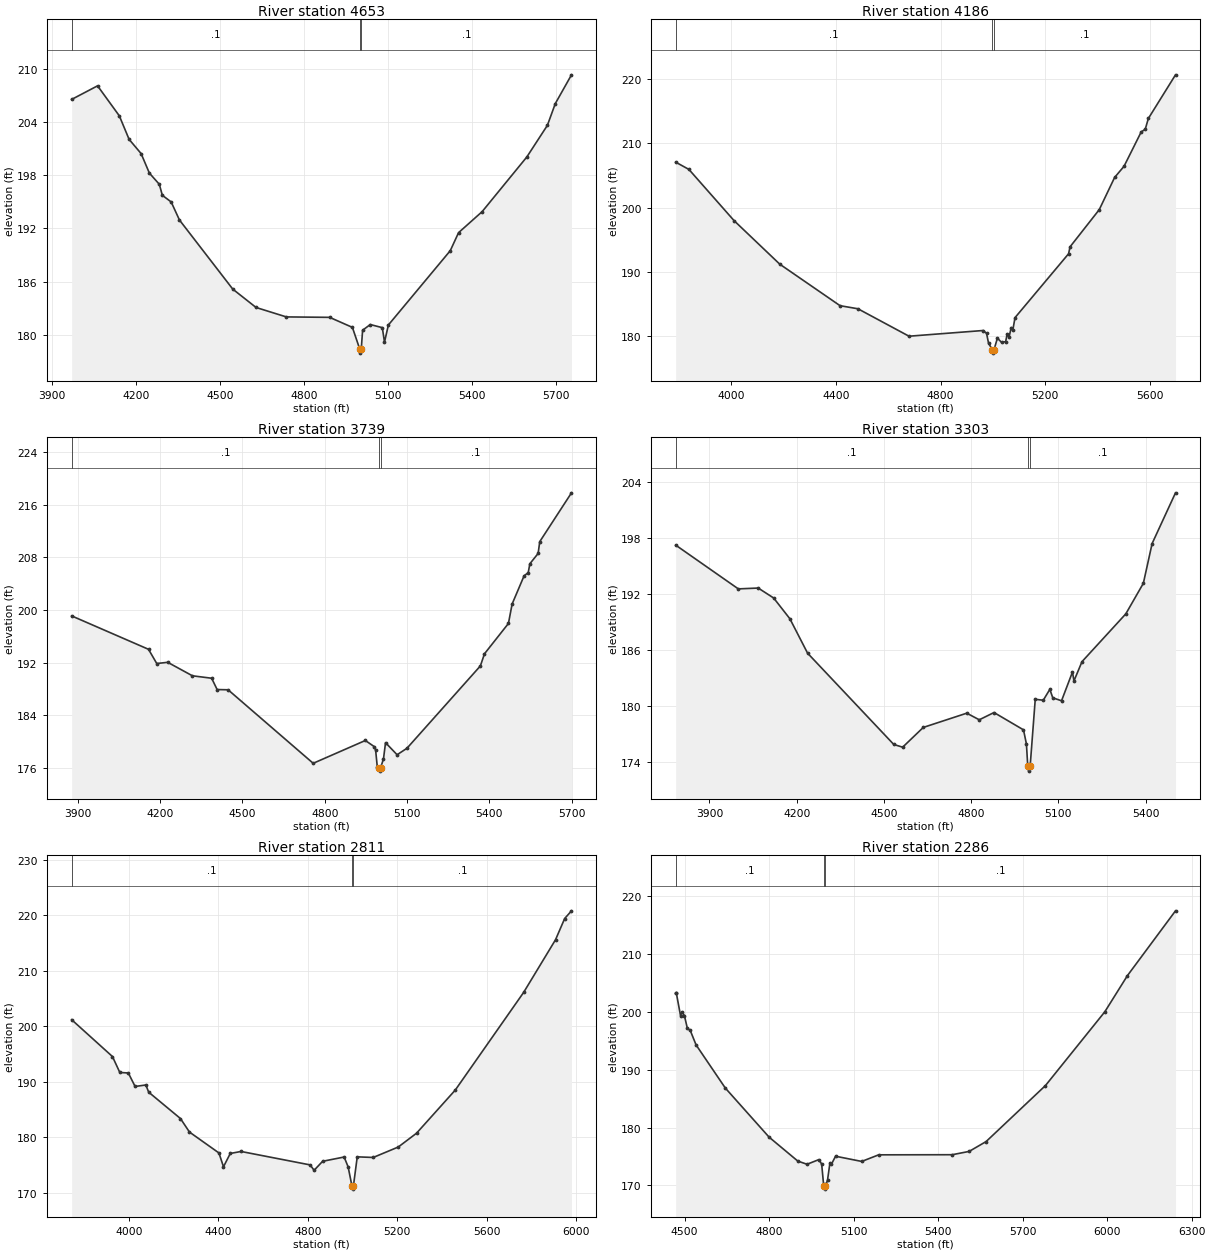
Type RM Length L Ch R = 1,4653,467,467,467
BEGIN DESCRIPTION:
SOUTH FORK SALT BRANCH 9.0
END DESCRIPTION:
XS GIS Cut Line= 4
      2234137.77     13317596.84      2235025.45     13317237.23
      2235251.61     13317048.07      2235774.67     13316956.57
#Sta/Elev= 30
  3970.2  206.53  4062.6  208.06  4140.3  204.68  4175.2  202.03  4218.0  200.43
  4247.5  198.23  4283.0  196.97  4293.8  195.73  4325.3  194.98  4354.8  192.95
  4545.1  185.16  4628.3  183.09  4736.2  182.03  4890.8  181.98  4972.0  180.85
  4997.7  178.45  5000.4  177.95  5003.7  178.45  5008.4  180.53  5035.8  181.17
  5078.7  180.82  5086.5  179.19  5100.4  181.12  5321.2  189.49  5350.8  191.52
  5435.0  193.89  5594.5  200.05  5667.8  203.61  5696.0  206.06  5753.8  209.30
#Mann=3,-1,0
  3970.2     0.1       0  4997.7    0.07       0  5003.7     0.1       0
Bank Sta=4997.7,5003.7
Exp/Cntr=0.3,0.1

Type RM Length L Ch R = 1,4186,447,447,447
BEGIN DESCRIPTION:
SOUTH FORK SALT BRANCH 8.0
END DESCRIPTION:
XS GIS Cut Line= 3
      2234237.68     13317596.86      2235437.72     13317396.85
      2236037.71     13317046.86
#Sta/Elev= 30
  3786.8  207.08  3837.5  205.94  4009.9  197.96  4184.8  191.16  4415.4  184.68
  4483.8  184.20  4679.0  179.92  4962.8  180.81  4975.5  180.36  4983.1  178.84
  4997.9  177.78  5000.6  177.28  5003.9  177.78  5017.0  179.62  5032.8  178.96
  5048.5  179.08  5054.3  180.22  5061.3  179.76  5070.0  181.27  5075.8  180.84
  5084.4  182.82  5289.1  192.78  5294.9  193.87  5406.5  199.67  5465.2  204.69
  5501.2  206.43  5566.9  211.80  5582.2  212.20  5594.2  213.89  5698.0  220.70
#Mann=3,-1,0
  3786.8     0.1       0  4997.9    0.07       0  5003.9     0.1       0
Bank Sta=4997.9,5003.9
Exp/Cntr=0.3,0.1

Type RM Length L Ch R = 1,3739,436,436,436
BEGIN DESCRIPTION:
SOUTH FORK SALT BRANCH 7.0
END DESCRIPTION:
XS GIS Cut Line= 3
      2234587.69     13317746.85      2235687.72     13317746.85
      2236087.70     13317146.89
#Sta/Elev= 30
  3877.9  199.09  4157.9  194.01  4187.9  191.85  4227.9  192.03  4317.9  189.98
  4387.9  189.61  4407.9  187.89  4447.9  187.85  4757.9  176.67  4947.9  180.14
  4980.9  179.19  4985.4  178.66  4991.4  176.13  4997.5  175.98  5000.2  175.48
  5003.5  175.98  5014.0  177.35  5021.5  179.81  5063.6  177.97  5099.6  178.96
  5367.0  191.48  5382.0  193.33  5469.2  197.94  5482.7  200.90  5526.3  205.19
  5541.3  205.67  5547.3  207.02  5577.4  208.59  5583.4  210.39  5699.0  217.81
#Mann=3,-1,0
  3877.9     0.1       0  4997.5    0.07       0  5003.5     0.1       0
Bank Sta=4997.5,5003.5
Exp/Cntr=0.3,0.1

Type RM Length L Ch R = 1,3303,492,492,492
BEGIN DESCRIPTION:
SOUTH FORK SALT BRANCH 6.0
END DESCRIPTION:
XS GIS Cut Line= 3
      2234787.69     13317796.85      2235987.72     13317996.85
      2236487.74     13317946.85
#Sta/Elev= 30
  3783.8  197.23  3999.3  192.53  4067.7  192.62  4120.9  191.55  4176.7  189.32
  4237.5  185.63  4534.0  175.83  4564.5  175.54  4635.4  177.66  4785.0  179.19
  4828.0  178.48  4878.7  179.26  4980.1  177.40  4990.2  175.88  4994.8  173.47
  4997.6  172.97  5000.8  173.47  5002.9  173.47  5020.5  180.68  5048.1  180.58
  5070.7  181.75  5080.8  180.84  5110.9  180.52  5148.6  183.61  5153.6  182.65
  5181.3  184.72  5332.0  189.85  5392.3  193.13  5422.5  197.40  5502.9  202.84
#Mann=3,-1,0
  3783.8     0.1       0  4994.8    0.07       0  5000.8     0.1       0
Bank Sta=4994.8,5000.8
Exp/Cntr=0.3,0.1

Type RM Length L Ch R = 1,2811,525,525,525
BEGIN DESCRIPTION:
SOUTH FORK SALT BRANCH 5.0
END DESCRIPTION:
XS GIS Cut Line= 3
      2234537.69     13318546.86      2235737.72     13318346.85
      2236737.73     13318546.86
#Sta/Elev= 30
  3743.9  201.20  3926.4  194.57  3959.4  191.70  3997.4  191.61  4027.8  189.18
  4075.9  189.45  4088.6  188.15  4230.6  183.41  4271.1  180.97  4402.9  177.21
  4423.2  174.72  4453.6  177.12  4501.7  177.48  4810.9  175.06  4828.7  174.09
  4866.7  175.71  4963.0  176.48  4980.9  174.71  4998.3  171.20  5001.0  170.70
  5004.3  171.20  5021.7  176.51  5093.1  176.40  5205.2  178.28  5286.8  180.76
  5460.2  188.53  5766.1  206.11  5908.9  215.60  5949.7  219.41  5980.3  220.80
#Mann=3,-1,0
  3743.9     0.1       0  4998.3    0.07       0  5004.3     0.1       0
Bank Sta=4998.3,5004.3
Exp/Cntr=0.3,0.1

Type RM Length L Ch R = 1,2286,401,401,401
BEGIN DESCRIPTION:
SOUTH FORK SALT BRANCH 4.0
END DESCRIPTION:
XS GIS Cut Line= 3
      2234937.74     13318846.85      2235487.72     13318696.85
      2236687.69     13318596.86
#Sta/Elev= 30
  4468.5  203.16  4471.1  203.16  4485.8  199.31  4490.9  199.97  4499.6  199.31
  4509.9  197.14  4520.3  196.76  4541.0  194.26  4644.7  186.82  4800.2  178.34
  4902.1  174.21  4934.9  173.66  4976.4  174.46  4986.7  173.72  4994.1  169.87
  4996.9  169.37  5000.1  169.87  5007.5  170.91  5016.1  173.91  5021.3  173.66
  5036.0  175.05  5128.9  174.15  5189.1  175.29  5450.0  175.31  5510.2  175.88
  5570.4  177.58  5781.1  187.25  5991.9  199.99  6072.1  206.23  6242.7  217.41
#Mann=3,-1,0
  4468.5     0.1       0  4994.1    0.07       0  5000.1     0.1       0
Bank Sta=4994.1,5000.1
Exp/Cntr=0.3,0.1

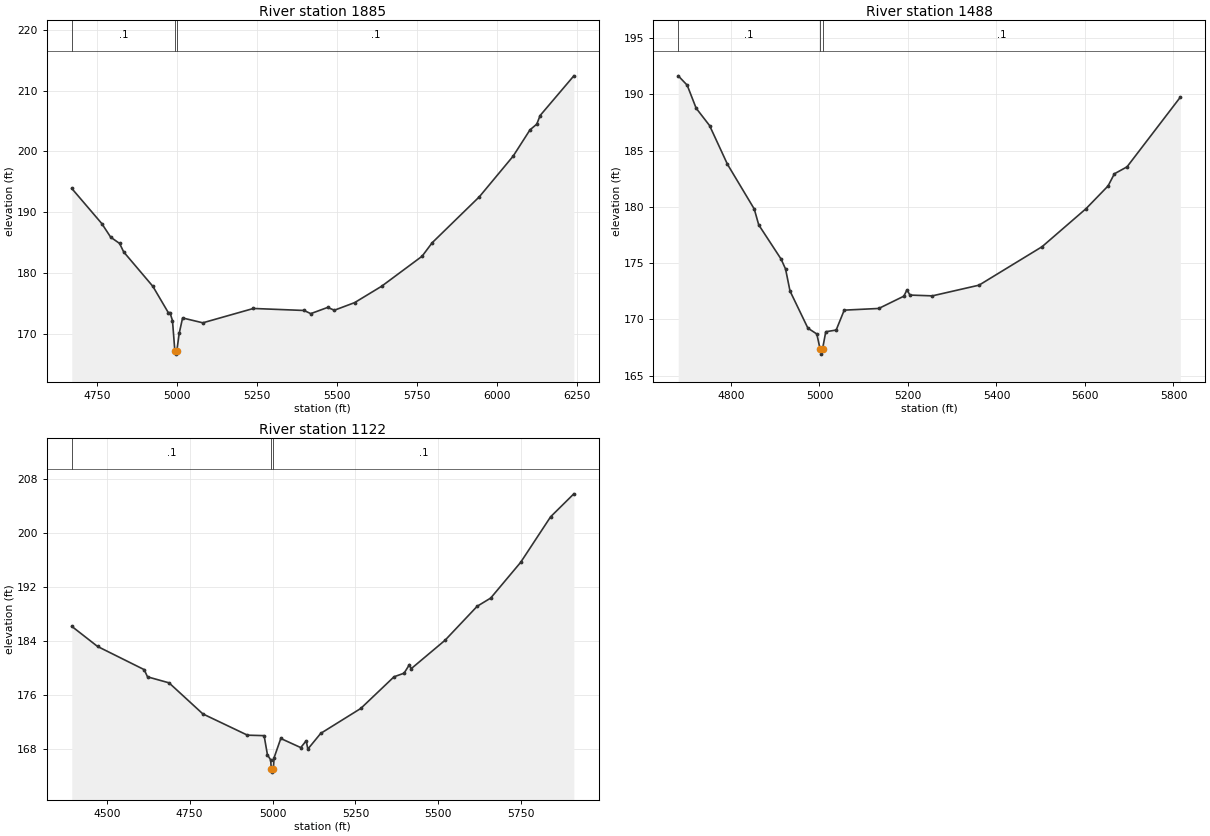
Type RM Length L Ch R = 1,1885,397,397,397
BEGIN DESCRIPTION:
SOUTH FORK SALT BRANCH 3.0
END DESCRIPTION:
XS GIS Cut Line= 3
      2235137.72     13319146.85      2235437.72     13319096.85
      2236637.68     13318696.87
#Sta/Elev= 30
  4671.1  193.90  4764.9  188.12  4792.8  185.88  4820.6  184.85  4833.3  183.46
  4924.5  177.80  4972.7  173.48  4977.9  173.48  4985.8  172.17  4993.3  167.15
  4996.1  166.65  4999.3  167.15  5006.9  170.09  5017.4  172.60  5080.6  171.80
  5238.8  174.16  5396.9  173.83  5418.0  173.31  5470.7  174.33  5491.7  173.87
  5555.0  175.12  5639.3  177.81  5765.8  182.75  5797.4  184.97  5945.0  192.54
  6050.4  199.21  6103.1  203.54  6124.2  204.47  6134.7  205.89  6240.1  212.42
#Mann=3,-1,0
  4671.1     0.1       0  4993.3    0.07       0  4999.3     0.1       0
Bank Sta=4993.3,4999.3
Exp/Cntr=0.3,0.1

Type RM Length L Ch R = 1,1488,366,366,366
BEGIN DESCRIPTION:
SOUTH FORK SALT BRANCH 2.0
END DESCRIPTION:
XS GIS Cut Line= 3
      2235387.68     13319446.86      2235737.72     13319396.85
      2236337.70     13318896.87
#Sta/Elev= 30
  4680.9  191.65  4701.1  190.82  4721.4  188.77  4751.7  187.23  4792.1  183.79
  4852.7  179.81  4862.8  178.40  4913.3  175.36  4923.4  174.48  4933.5  172.52
  4973.9  169.22  4994.1  168.70  5001.2  167.41  5003.9  166.91  5007.2  167.41
  5014.3  168.90  5037.8  169.05  5056.0  170.82  5134.1  170.97  5190.7  172.06
  5197.9  172.63  5204.4  172.16  5255.1  172.09  5360.6  173.04  5503.1  176.46
  5602.7  179.85  5652.2  181.86  5666.5  182.94  5695.1  183.56  5815.5  189.75
#Mann=3,-1,0
  4680.9     0.1       0  5001.2    0.07       0  5007.2     0.1       0
Bank Sta=5001.2,5007.2
Exp/Cntr=0.3,0.1

Type RM Length L Ch R = 1,1122,777,777,777
BEGIN DESCRIPTION:
Mapping XS a4d998ab
END DESCRIPTION:
XS GIS Cut Line= 2
      2235320.40     13319750.06      2236827.36     13319604.23
#Sta/Elev= 30
  4394.6  186.19  4472.3  183.21  4612.9  179.77  4623.0  178.70  4687.9  177.81
  4790.0  173.20  4924.4  170.05  4974.6  169.98  4984.7  167.13  4994.3  166.39
  4996.3  165.07  4999.1  164.57  5002.3  165.07  5004.8  166.72  5024.9  169.56
  5085.1  168.21  5101.5  169.22  5106.5  167.99  5145.4  170.32  5266.0  174.01
  5366.4  178.71  5396.6  179.24  5412.9  180.52  5417.9  179.90  5520.1  184.12
  5617.2  189.17  5657.8  190.38  5748.2  195.68  5838.6  202.44  5908.6  205.84
#Mann=3,-1,0
  4394.6     0.1       0  4996.3    0.07       0  5002.3     0.1       0
Bank Sta=4996.3,5002.3
Exp/Cntr=0.3,0.1