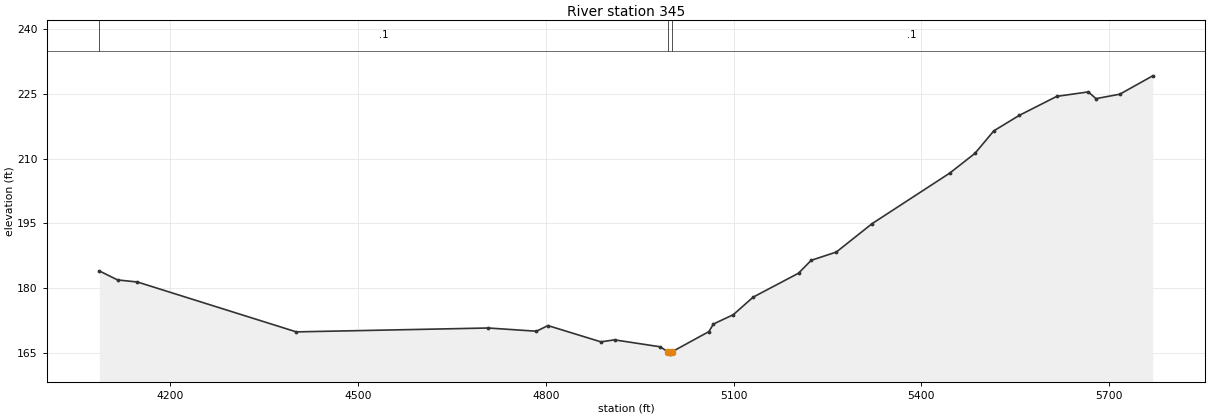
HEC-RAS study SOUTH FORK SALT BRANCH.prj: SOUTH FORK SALT BRANCH Base Level Engineering

--- SOUTH FORK SALT BRANCH.g01 (geometry) --- (continued)

Type RM Length L Ch R = 1,345,0,0,0
BEGIN DESCRIPTION:
SOUTH FORK SALT BRANCH 1.0
END DESCRIPTION:
XS GIS Cut Line= 3
      2235190.24     13320034.79      2236216.27     13320388.95
      2236809.99     13320321.24
#Sta/Elev= 30
  4086.6  183.97  4115.7  181.88  4147.4  181.40  4401.3  169.83  4708.1  170.73
  4785.0  169.98  4803.3  171.29  4887.9  167.52  4909.7  167.98  4983.1  166.36
  4995.0  165.17  4997.8  164.67  5001.0  165.17  5060.4  169.89  5067.8  171.66
  5099.5  173.82  5131.2  177.89  5203.7  183.44  5223.8  186.42  5264.1  188.35
  5321.2  194.93  5445.2  206.65  5485.5  211.23  5515.7  216.46  5556.0  220.02
  5616.3  224.46  5666.7  225.49  5678.9  223.93  5717.0  224.96  5769.6  229.22
#Mann=3,-1,0
  4086.6     0.1       0  4995.0    0.07       0  5001.0     0.1       0
Bank Sta=4995,5001
Exp/Cntr=0.3,0.1

Chan Stop Cuts=-1