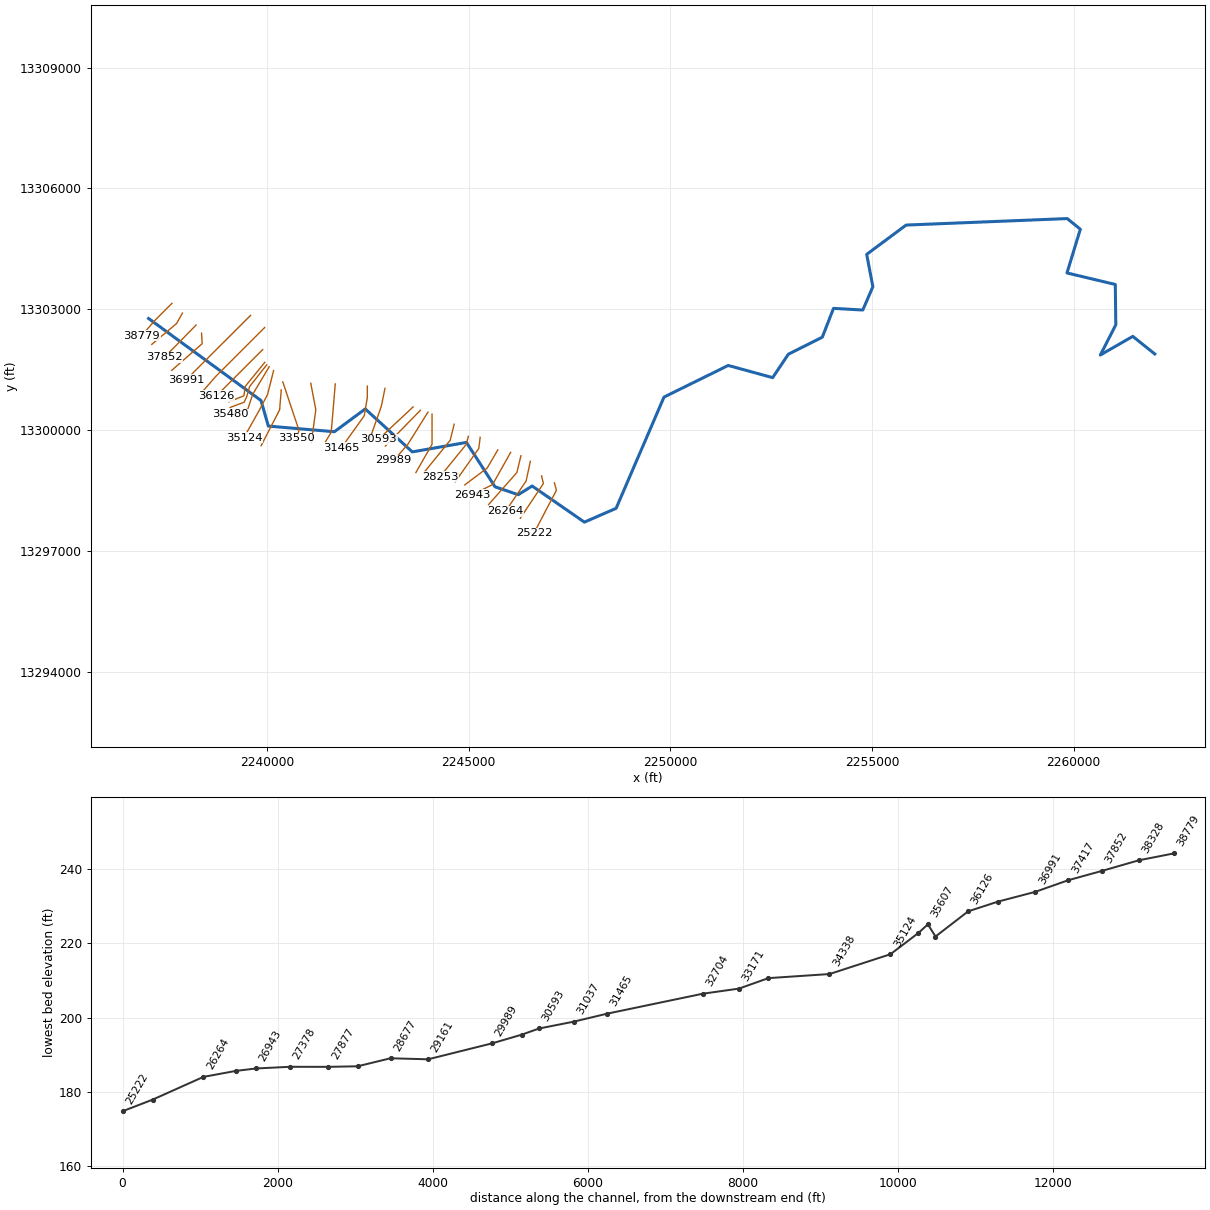
--- TIMON CREEK.prj (project) ---

Proj Title=TIMON CREEK Base Level Engineering
Current Plan=p01
Default Exp/Contr=0.3,0.1
English Units
Geom File=g01
Flow File=f01
Plan File=p01
Y Axis Title=Elevation
X Axis Title(PF)=Main Channel Distance
X Axis Title(XS)=Station
BEGIN DESCRIPTION:
TIMON CREEK
END DESCRIPTION:
DSS Export Rating Curves= 0
DSS Export Rating Curve Sorted= 0
DSS Export Volume Flow Curves= 0
DXF OffsetX= 0
DXF OffsetY= 0
DXF ScaleX= 1
DXF ScaleY= 10

--- TIMON CREEK.p01 (plan) ---

Plan Title=Multiple Run
Short Identifier=Multiple
Geom File=g01
Flow File=f01
Subcritical Flow
K Sum by GR= 0
Std Step Tol= 0.01
Critical Tol= 0.01
Num of Std Step Trials= 20
Max Error Tol= 0.3
Flow Tol Ratio= 0.001
Split Flow NTrial= 30
Split Flow Tol= 0.02
Split Flow Ratio= 0.02
Log Output Level= 0
Friction Slope Method= 1
Unsteady Friction Slope Method= 2
Unsteady Bridges Friction Slope Method= 1
Parabolic Critical Depth
Global Vel Dist=  1 , 1 , 1
Global Log Level= 0
CheckData=True
Encroach Param= -1, 0, 0, 0
BEGIN DESCRIPTION:
Multiple Run
END DESCRIPTION:

--- TIMON CREEK.f01 (steady flow) ---

Flow Title=Multiple
Number of Profiles=7
Profile Names=10-year,25-year,50-year,1pct_min,100-year,1pct_plu,500-year
River Rch & RM= TIMON CREEK,Reach-1,38779
     354     503     629     579     783    1059    1231
River Rch & RM= TIMON CREEK,Reach-1,33550
     439     628     789     728     985    1332    1560
River Rch & RM= TIMON CREEK,Reach-1,27378
     523     752     948     877    1186    1605    1889
River Rch & RM= TIMON CREEK,Reach-1,21338
     620     897    1136    1056    1428    1931    2292
River Rch & RM= TIMON CREEK,Reach-1,19572
     643     931    1178    1094    1480    2002    2372
River Rch & RM= TIMON CREEK,Reach-1,15634
     724    1052    1337    1245    1684    2277    2716
River Rch & RM= TIMON CREEK,Reach-1,11060
     741    1075    1363    1268    1714    2318    2753
Boundary for River Rch & Prof#=TIMON CREEK,Reach-1,1
Up Type=0
Dn Type=3
Dn Slope=0.005
Boundary for River Rch & Prof#=TIMON CREEK,Reach-1,2
Up Type=0
Dn Type=3
Dn Slope=0.005
Boundary for River Rch & Prof#=TIMON CREEK,Reach-1,3
Up Type=0
Dn Type=3
Dn Slope=0.005
Boundary for River Rch & Prof#=TIMON CREEK,Reach-1,4
Up Type=0
Dn Type=3
Dn Slope=0.005
Boundary for River Rch & Prof#=TIMON CREEK,Reach-1,5
Up Type=0
Dn Type=3
Dn Slope=0.005
Boundary for River Rch & Prof#=TIMON CREEK,Reach-1,6
Up Type=0
Dn Type=3
Dn Slope=0.005
Boundary for River Rch & Prof#=TIMON CREEK,Reach-1,7
Up Type=0
Dn Type=3
Dn Slope=0.005

--- TIMON CREEK.g01 (geometry) ---

Geom Title=Existing Conditions
Program Version=4.10

River Reach=TIMON CREEK     ,Reach-1
Reach XY= 30
      2237058.95     13302769.99      2239846.58     13300735.33
      2240029.04     13300099.75      2241667.04     13299959.82
       2242431.8     13300525.79      2243598.84     13299459.39
      2244941.07     13299694.68      2245650.99     13298592.44
      2246225.66     13298397.03       2246570.5     13298612.77
      2247867.04     13297716.33       2248652.8     13298058.69
        2249841.     13300820.03      2251433.52     13301604.93
      2252535.75     13301302.27      2252923.16     13301882.13
      2253766.71     13302306.66      2254044.74       13303022.
      2254770.03     13302980.66      2255020.88     13303557.75
      2254867.39     13304361.84      2255844.37     13305089.26
       2259840.4     13305250.44      2260165.85     13304986.94
      2259834.83      13303900.5      2261033.01       13303615.
      2261045.19      13302612.6      2260661.94     13301863.69
      2261466.74     13302326.95      2262011.66     13301889.74

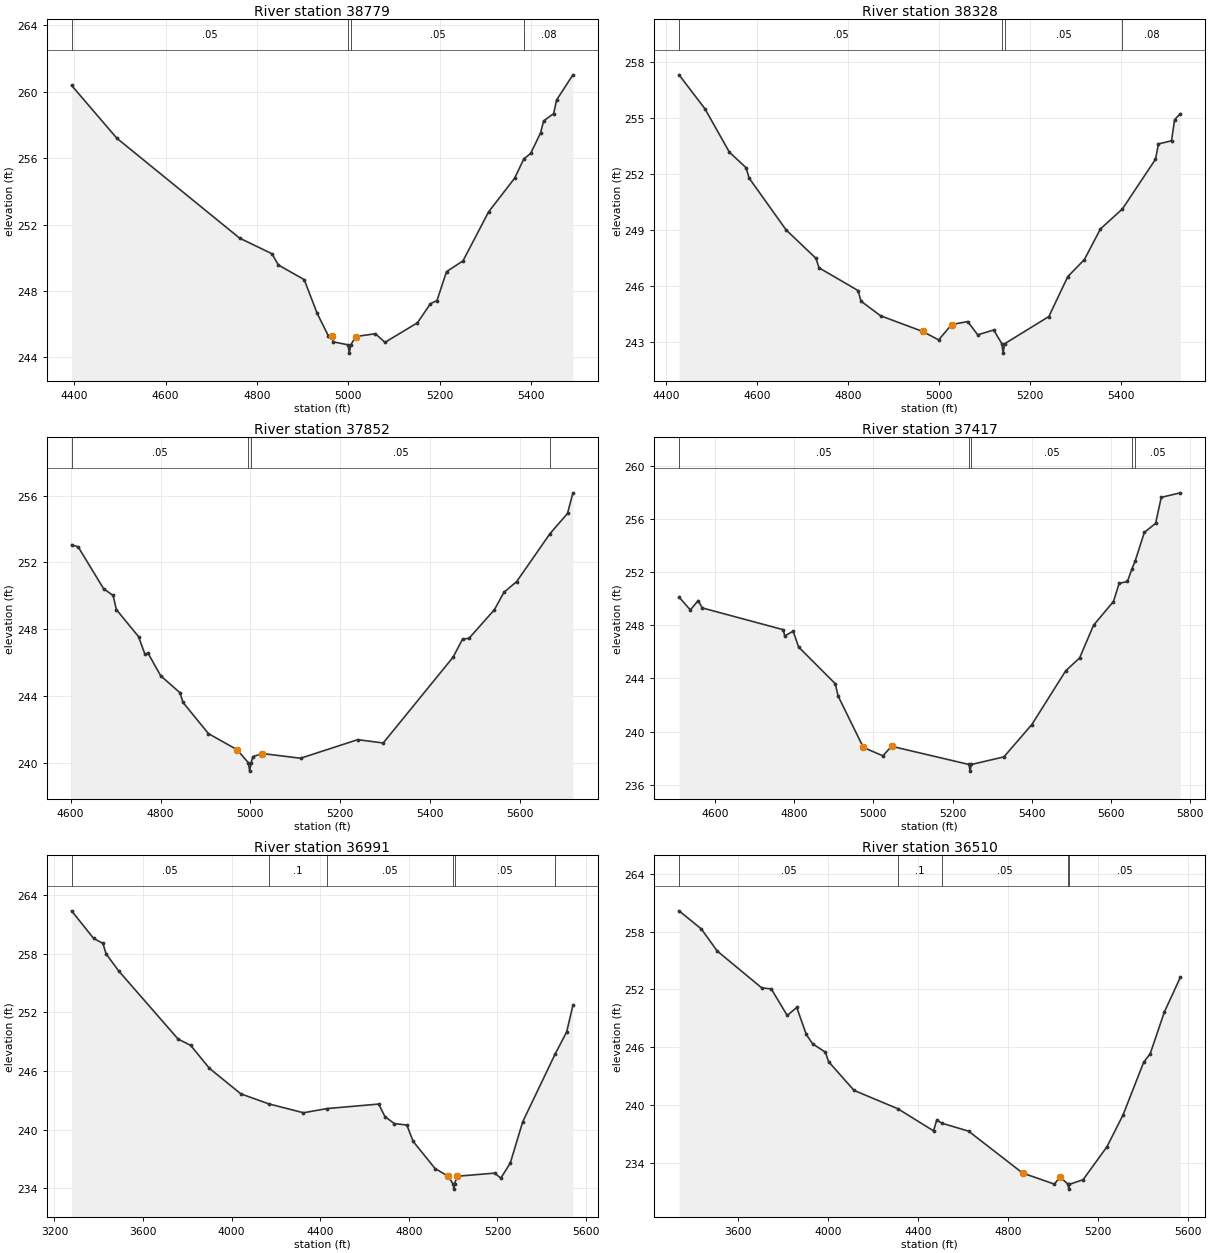
Type RM Length L Ch R = 1 ,38779   ,451,451,451
BEGIN DESCRIPTION:
TIMON CREEK 74.0
END DESCRIPTION:
XS GIS Cut Line= 3
      2237637.74     13303146.88      2237237.72     13302746.85
      2236887.74     13302346.87
#Sta/Elev= 30
  4394.4  260.38  4493.4   257.2  4762.1  251.18  4832.8  250.24    4847  249.56
  4903.5  248.68  4931.8  246.65  4956.6  245.28  4963.4  245.28  4967.2  244.93
  4999.4  244.75  5002.1  244.25  5005.4  244.75  5016.6  245.25  5059.3  245.42
  5080.2   244.9  5151.4  246.08  5179.8  247.23  5194.1  247.42    5215  249.16
    5251  249.81    5307  252.76    5364  254.79  5384.3  255.96  5399.1  256.28
  5420.9  257.53  5427.6  258.25  5449.4  258.68    5456  259.51  5491.6  261.02
#Mann= 4 ,-1 , 0
  4394.4     .05       0  4999.4     .03       0  5005.4     .05       0
  5384.3     .08       0
Bank Sta=4963.4,5016.6
XS Rating Curve= 0 ,0
Exp/Cntr=0.3,0.1

Type RM Length L Ch R = 1 ,38328   ,476,476,476
BEGIN DESCRIPTION:
TIMON CREEK 73.0
END DESCRIPTION:
XS GIS Cut Line= 3
      2237898.44     13302905.24      2237752.59      13302644.8
      2237138.03      13302129.2
#Sta/Elev= 30
  4428.7   257.3  4485.6  255.48  4539.2  253.16  4575.8  252.33  4582.6  251.77
  4663.7     249  4729.5  247.47  4735.9  246.97  4821.8  245.75  4828.3  245.18
  4871.2   244.4  4963.6  243.56  4998.7  243.11  5027.3  243.93  5062.5  244.09
  5084.5  243.38  5119.7  243.64  5137.5   242.9  5140.3   242.4  5143.5   242.9
  5240.7  244.36  5282.3   246.5  5318.7  247.41  5353.9  249.05  5402.2  250.12
  5474.8  252.78  5481.4   253.6    5510  253.77  5516.8   254.9  5529.4  255.22
#Mann= 4 ,-1 , 0
  4428.7     .05       0  5137.5     .03       0  5143.5     .05       0
  5402.2     .08       0
Bank Sta=4963.6,5027.3
XS Rating Curve= 0 ,0
Exp/Cntr=0.3,0.1

Type RM Length L Ch R = 1 ,37852   ,435,435,435
BEGIN DESCRIPTION:
TIMON CREEK 72.0
END DESCRIPTION:
XS GIS Cut Line= 3
      2238236.96     13302608.34      2237997.38     13302363.55
      2237455.89     13301811.65
#Sta/Elev= 30
  4602.1  253.06  4616.8  252.93  4673.4  250.43  4694.5  250.03  4701.7  249.19
  4751.1  247.57  4765.3  246.52  4772.3  246.58  4800.5  245.23    4843  244.23
  4850.1  243.64  4906.7  241.78  4970.3  240.82  4995.6  240.04  4998.3  239.54
  5001.6  240.04  5005.7  240.41  5026.9  240.59  5111.7  240.31    5239  241.42
  5295.6  241.22  5451.2  246.35  5472.3  247.43  5486.5  247.47  5543.1  249.18
  5564.3  250.22  5592.6  250.86    5667  253.73  5705.8  254.93  5717.8  256.16
#Mann= 4 ,-1 , 0
  4602.1     .05       0  4995.6     .03       0  5001.6     .05       0
    5667     .08       0
Bank Sta=4970.3,5026.9
XS Rating Curve= 0 ,0
Exp/Cntr=0.3,0.1

Type RM Length L Ch R = 1 ,37417   ,426,426,426
BEGIN DESCRIPTION:
TIMON CREEK 71.0
END DESCRIPTION:
XS GIS Cut Line= 3
      2238372.38     13302405.18      2238388.01      13302144.8
      2237632.78     13301483.33
#Sta/Elev= 30
  4509.9  250.11  4538.3  249.15  4558.3  249.85  4568.3   249.3    4773  247.66
  4776.5  247.19  4797.7  247.55  4811.6  246.36  4904.1   243.6  4911.3  242.67
  4974.9  238.81  5024.2  238.18    5046   238.9  5241.4  237.53  5244.1  237.03
  5247.4  237.53  5329.5   238.1    5400  240.53  5485.4  244.57  5520.6  245.54
  5555.7     248    5606  249.78  5620.2  251.14  5641.1  251.29  5652.2   252.2
  5660.6  252.82  5683.8  254.97  5712.3  255.66  5726.5  257.61  5774.7  257.95
#Mann= 5 ,-1 , 0
  4509.9     .05       0  5241.4     .03       0  5247.4     .05       0
  5652.2     .08       0  5660.6     .05       0
Bank Sta=4974.9,5046
XS Rating Curve= 0 ,0
Exp/Cntr=0.3,0.1

Type RM Length L Ch R = 1 ,36991   ,481,481,481
BEGIN DESCRIPTION:
TIMON CREEK 70.0
END DESCRIPTION:
XS GIS Cut Line= 3
       2239587.7     13302846.84      2238387.72     13301646.85
      2237987.73     13301246.87
#Sta/Elev= 30
  3277.7  262.42  3376.7   259.6  3419.1  259.08  3433.2  258.02  3489.8  256.27
  3758.5  249.27  3815.1  248.63  3899.9  246.27  4041.4  243.66  4167.6  242.63
  4324.2  241.72  4431.3  242.15  4663.6  242.61  4691.9  241.33  4734.3  240.61
  4790.9  240.46  4819.2  238.79  4918.2     236  4978.3   235.2    5000  234.39
  5002.8  233.89    5006  234.39  5017.2  235.21  5186.9  235.53  5215.1  235.02
  5257.6  236.56  5314.1  240.81    5460  247.73  5512.1     250  5540.4  252.73
#Mann= 6 ,-1 , 0
  3277.7     .05       0  4167.6      .1       0  4431.3     .05       0
    5000     .03       0    5006     .05       0    5460     .08       0
Bank Sta=4978.3,5017.2
XS Rating Curve= 0 ,0
Exp/Cntr=0.3,0.1

Type RM Length L Ch R = 1 ,36510   ,384,384,384
BEGIN DESCRIPTION:
TIMON CREEK 69.0
END DESCRIPTION:
XS GIS Cut Line= 3
      2239937.69     13302546.83      2238737.72     13301346.85
      2238387.74     13300946.87
#Sta/Elev= 30
  3337.5  260.15  3436.5  258.27  3507.2  255.98  3705.2  252.15  3747.6  252.04
  3818.3  249.29  3860.7  250.12  3903.1  247.32  3931.4  246.34    3988  245.48
  4002.1   244.5  4115.3  241.51  4310.6   239.6  4468.8  237.31    4483  238.42
  4506.4   238.1  4624.4  237.28  4864.8  232.93  5006.2  231.78    5031  232.53
  5067.1  231.76  5069.9  231.26  5073.1  231.76  5133.7  232.24    5240  235.67
  5311.2  238.96  5403.3  244.45  5431.7   245.3  5495.3  249.67    5566  253.25
#Mann= 5 ,-1 , 0
  3337.5     .05       0  4310.6      .1       0  4506.4     .05       0
  5067.1     .03       0  5073.1     .05       0
Bank Sta=4864.8,5031
XS Rating Curve= 0 ,0
Exp/Cntr=0.3,0.1

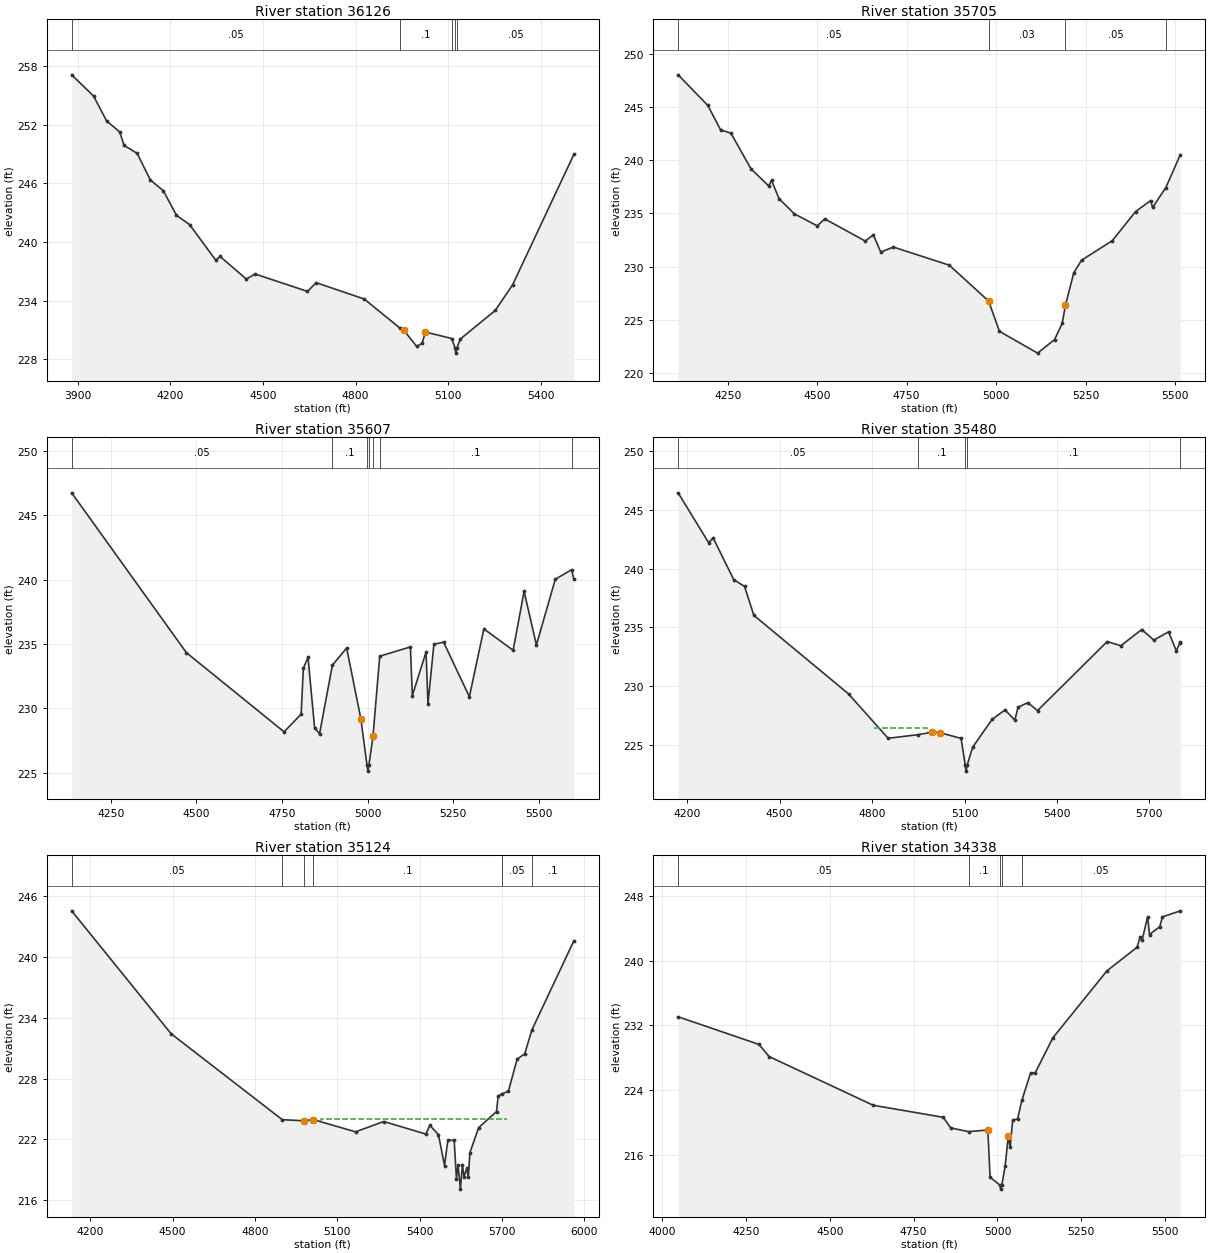
Type RM Length L Ch R = 1 ,36126   ,421,421,421
BEGIN DESCRIPTION:
TIMON CREEK 68.0
END DESCRIPTION:
XS GIS Cut Line= 3
      2239887.75     13301996.88      2239087.72     13301196.85
      2238737.71     13300846.85
#Sta/Elev= 30
  3880.4  257.09  3951.2  254.93  3993.6  252.38    4036  251.25  4050.1  249.88
  4092.6  249.06    4135  246.35  4177.4  245.24  4219.9  242.73  4262.3  241.78
  4347.1  238.14  4361.3  238.52  4446.1  236.21  4474.4  236.73  4644.1  234.95
  4672.4  235.84    4828  234.17    4944  231.19  4955.2  231.02  4997.7  229.33
  5015.3  229.64    5026   230.8    5112  230.13  5121.9  229.14  5124.7  228.64
  5127.9  229.14  5139.1  230.08  5252.2     233  5308.8  235.64  5506.8  248.95
#Mann= 5 ,-1 , 0
  3880.4     .05       0    4944      .1       0    5112     .05       0
  5121.9     .07       0  5127.9     .05       0
Bank Sta=4955.2,5026
XS Rating Curve= 0 ,0
Exp/Cntr=0.3,0.1

Type RM Length L Ch R = 1 ,35705   ,98,98,98
BEGIN DESCRIPTION:
Mapping XS 4290be1e
END DESCRIPTION:
XS GIS Cut Line= 4
      2239940.07     13301681.24      2239453.98     13301083.44
       2239423.6      13300853.4      2239052.01     13300702.17
#Sta/Elev= 30
  4111.3  248.04  4194.3  245.16  4230.2  242.85  4258.7  242.56  4314.9   239.2
  4364.5  237.59  4372.4  238.11  4393.2   236.4  4436.3  234.96  4500.3  233.83
  4521.1  234.49  4634.6   232.4  4656.9     233  4677.7  231.36  4712.8  231.84
  4869.4  230.13  4979.2  226.76  5009.5  223.91  5116.1  221.86  5163.4  223.13
  5184.9  224.66  5193.9  226.36  5217.3  229.42  5238.9   230.6    5325  232.44
  5390.1  235.18  5432.1  236.21  5437.5  235.56  5474.6  237.44    5515  240.52
#Mann= 4 ,-1 , 0
  4111.3     .05       0  4979.2     .03       0  5193.9     .05       0
  5474.6     .05       0
Bank Sta=4979.2,5193.9
XS Rating Curve= 0 ,0
Exp/Cntr=0.3,0.1

Type RM Length L Ch R = 1 ,35607   ,127,127,127
BEGIN DESCRIPTION:
Mapping XS 31677cf8
END DESCRIPTION:
XS GIS Cut Line= 5
      2239986.93     13301618.72      2239562.49     13301079.09
      2239493.05      13300831.7      2239427.94     13300692.81
      2239081.68     13300562.96
#Sta/Elev= 30
  4135.6  246.73  4470.5  234.33    4756  228.18  4805.8  229.55  4812.3  233.11
  4825.9  233.96  4845.2  228.49  4859.6  228.02  4897.1  233.35  4938.7  234.69
  4980.3  229.19    4998  225.63  5000.8  225.13    5004  225.63  5015.7  227.84
  5035.4  234.05    5125  234.77  5130.6  230.99  5170.7  234.37  5176.2  230.33
  5193.5  234.97  5221.9  235.14  5297.2   230.9  5339.5  236.17    5425  234.51
    5457  239.08    5493  234.92  5548.1  240.02  5595.5  240.76  5602.3  240.04
#Mann= 7 ,-1 , 0
  4135.6     .05       0  4897.1      .1       0    4998     .07       0
    5004      .1       0  5015.7     .05       0  5035.4      .1       0
  5595.5     .05       0
Bank Sta=4980.3,5015.7
XS Rating Curve= 0 ,0
Exp/Cntr=0.3,0.1

Type RM Length L Ch R = 1 ,35480   ,356,356,356
BEGIN DESCRIPTION:
Mapping XS 19726b24
END DESCRIPTION:
XS GIS Cut Line= 4
      2240049.47     13301571.89      2239640.61     13300888.12
      2239519.09      13300519.2      2239091.08     13300398.15
#Sta/Elev= 30
  4170.5  246.46  4269.6  242.21  4284.1  242.62  4351.1  239.06  4386.1  238.48
  4416.3  236.02  4723.7  229.32  4852.1  225.54  4950.2  225.85  4993.6  226.05
  5020.1  226.02  5088.9  225.53  5102.4  223.24  5105.1  222.74  5108.4  223.24
  5126.4  224.78  5189.6  227.15  5231.7  227.96  5263.3  227.08  5273.8  228.18
  5305.4  228.58    5337   227.9    5563  233.78  5607.3  233.43  5675.3  234.81
  5714.4  233.91  5762.3  234.61  5787.5  232.99  5798.7  233.65  5800.4  233.76
#Mann= 5 ,-1 , 0
  4170.5     .05       0  4950.2      .1       0  5102.4     .07       0
  5108.4      .1       0  5798.7     .05       0
#XS Ineff= 2 ,-1
 4806.98 4978.65  226.39  5025.3 5161.14  225.92
Permanent Ineff=
       T       T
Bank Sta=4993.6,5020.1
XS Rating Curve= 0 ,0
Exp/Cntr=0.3,0.1

Type RM Length L Ch R = 1 ,35124   ,786,786,786
BEGIN DESCRIPTION:
Mapping XS 1ad0b389
END DESCRIPTION:
XS GIS Cut Line= 4
      2240158.84     13301478.12       2240007.8     13300879.17
      2239804.67     13300493.76      2239424.46     13299816.67
#Sta/Elev= 30
    4132  244.54  4494.3  232.42  4899.4  223.94  4979.6  223.83  5012.3  223.95
  5166.5  222.74  5269.4  223.76  5422.7  222.52  5437.2  223.38  5468.5  222.47
  5490.7  219.42  5502.9  221.93  5525.9  221.89  5534.1  218.13  5539.8  219.45
  5548.6  217.09  5555.8  219.51  5561.5  218.31  5571.7  219.14  5577.4  218.24
  5583.2  220.69  5615.1  223.16  5680.1  224.74  5686.4  226.29  5701.2   226.5
  5723.5  226.75  5755.3  229.91  5782.8  230.44  5809.4  232.81  5961.9  241.58
#Mann= 6 ,-1 , 0
    4132     .05       0  4899.4      .1       0  4979.6     .07       0
  5012.3      .1       0  5701.2     .05       0  5809.4      .1       0
#XS Ineff= 1 ,-1
 5038.94 5719.78  224.02
Permanent Ineff=
       T
Bank Sta=4979.6,5012.3
XS Rating Curve= 0 ,0
Exp/Cntr=0.3,0.1

Type RM Length L Ch R = 1 ,34338   ,788,788,788
BEGIN DESCRIPTION:
TIMON CREEK 64.0
END DESCRIPTION:
XS GIS Cut Line= 3
      2240348.03     13300997.53       2240309.2     13300505.59
      2239849.58     13299612.26
#Sta/Elev= 30
  4047.4  233.06  4288.8  229.64  4318.9  228.14  4629.4  222.12  4838.3  220.63
  4860.5  219.32  4913.7  218.86  4971.4  219.06    4978  213.23  5007.1  212.25
  5009.8  211.75  5013.1  212.25    5023   214.6  5032.3  218.27  5037.9  216.94
  5045.5   220.3  5060.1  220.42  5072.7  222.71  5098.8   226.1    5113  226.16
  5165.3  230.46  5326.7  238.74  5416.6  241.66  5425.8  242.93  5431.4   242.5
    5448  245.43  5453.6  243.23  5484.1   244.2  5492.3  245.41  5545.5  246.16
#Mann= 5 ,-1 , 0
  4047.4     .05       0  4913.7      .1       0  5007.1     .07       0
  5013.1      .1       0  5072.7     .05       0
Bank Sta=4971.4,5032.3
XS Rating Curve= 0 ,0
Exp/Cntr=0.3,0.1

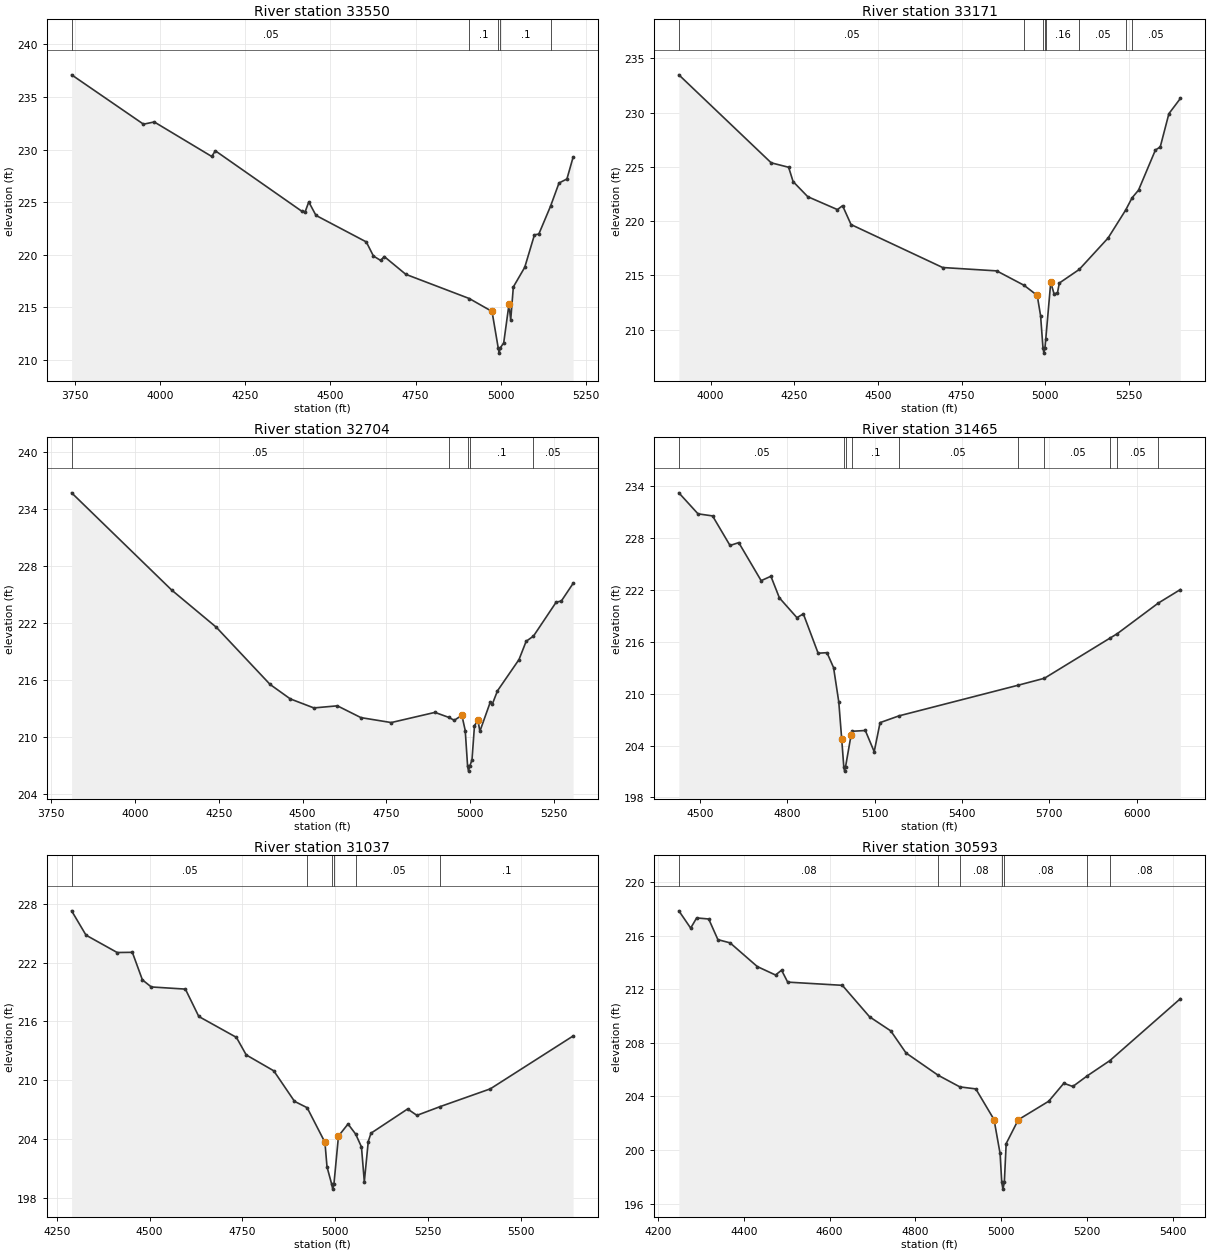
Type RM Length L Ch R = 1 ,33550   ,379,379,379
BEGIN DESCRIPTION:
TIMON CREEK 63.0
END DESCRIPTION:
XS GIS Cut Line= 3
      2240387.72     13301196.86      2240787.72     13299996.85
      2240737.71     13299796.83
#Sta/Elev= 30
    3741   237.1  3951.8  232.41  3983.5  232.62  4152.1  229.34  4162.6  229.88
  4415.6  224.15  4426.2  224.09  4436.7  225.02  4457.8  223.74  4605.4  221.22
  4626.4  219.88  4647.5  219.46  4658.1  219.83  4721.3  218.14  4907.5  215.84
  4974.3  214.61  4992.4  211.15  4995.1  210.65  4998.4  211.15  5008.5  211.61
    5024  215.28  5029.1  213.81  5036.8  216.94  5070.3  218.81  5098.7  221.89
  5111.6  221.97    5146  224.62  5170.8  226.82    5194   227.2  5212.1  229.27
#Mann= 5 ,-1 , 0
    3741     .05       0  4907.5      .1       0  4992.4     .07       0
  4998.4      .1       0    5146     .05       0
Bank Sta=4974.3,5024
XS Rating Curve= 0 ,0
Exp/Cntr=0.3,0.1

Type RM Length L Ch R = 1 ,33171   ,467,467,467
BEGIN DESCRIPTION:
TIMON CREEK 62.0
END DESCRIPTION:
XS GIS Cut Line= 3
      2241080.71      13301162.2      2241205.71     13300509.38
       2241094.6       13299683.
#Sta/Elev= 30
  3905.3  233.48  4181.2  225.37  4233.3  224.96  4246.7  223.64  4290.4  222.25
  4379.1  221.06  4394.5  221.42  4419.8  219.68  4693.6  215.72  4855.1  215.41
  4936.9  214.08  4976.1  213.15  4986.2  211.28  4993.3  208.33  4996.1  207.83
  4999.3  208.33  5001.6   209.1  5016.5  214.35  5026.6  213.28  5036.7   213.4
  5042.2  214.29  5101.6  215.54  5187.9  218.44  5240.3  221.01  5259.7  222.15
  5278.8  222.85  5329.3  226.55  5343.7  226.83  5369.6   229.9  5403.8   231.3
#Mann= 8 ,-1 , 0
  3905.3     .05       0  4936.9      .1       0  4993.3     .07       0
  4999.3      .1       0  5001.6     .16       0  5101.6     .05       0
  5240.3      .1       0  5259.7     .05       0
Bank Sta=4976.1,5016.5
XS Rating Curve= 0 ,0
Exp/Cntr=0.3,0.1

Type RM Length L Ch R = 1 ,32704   ,1239,1239,1239
BEGIN DESCRIPTION:
TIMON CREEK 61.0
END DESCRIPTION:
XS GIS Cut Line= 3
      2241687.72     13301146.82      2241587.72     13299946.85
      2241437.71     13299696.83
#Sta/Elev= 30
  3811.1  235.73  4109.6   225.5  4242.6  221.59  4403.1  215.57  4463.3  214.05
  4533.6   213.1  4603.8  213.32    4674  212.08  4764.4  211.56  4894.8  212.63
  4935.5  212.11  4952.5   211.8  4975.1  212.32  4985.1  210.72  4992.2  206.95
  4994.9  206.45  4998.2  206.95  5005.2  207.61  5012.7  211.24    5023   211.8
  5028.8  210.64  5059.9  213.72  5065.8  213.49  5081.3   214.9  5145.5  218.19
  5166.8  220.11  5188.7  220.66  5256.2  224.22  5271.8  224.35  5306.8   226.2
#Mann= 5 ,-1 , 0
  3811.1     .05       0  4935.5      .1       0  4992.2     .07       0
  4998.2      .1       0  5188.7     .05       0
Bank Sta=4975.1,5023
XS Rating Curve= 0 ,0
Exp/Cntr=0.3,0.1

Type RM Length L Ch R = 1 ,31465   ,428,428,428
BEGIN DESCRIPTION:
TIMON CREEK 60.0
END DESCRIPTION:
XS GIS Cut Line= 4
      2242483.49      13301092.7      2242483.49     13300807.99
       2242407.1      13300356.6      2241837.63     13299557.95
#Sta/Elev= 30
    4427  233.24  4492.8  230.81  4542.8  230.57  4602.8  227.15  4632.8  227.48
  4709.8  223.08  4743.3  223.59  4772.5  221.09  4832.8   218.8  4854.8  219.24
  4905.6  214.69    4936  214.75  4958.7  213.02  4976.6  209.05  4986.7  204.73
  4993.8  201.55  4996.6  201.05  4999.8  201.55  5019.1  205.27    5023  205.66
  5067.8  205.75  5098.3   203.3  5118.5  206.66  5183.3  207.44  5591.1  210.97
  5683.2  211.79  5910.3  216.47  5933.3  216.94  6074.3  220.48  6150.4  222.05
#Mann= 10 ,-1 , 0
    4427     .05       0  4993.8     .03       0  4999.8     .05       0
    5023      .1       0  5183.3     .05       0  5591.1      .1       0
  5683.2     .05       0  5910.3      .1       0  5933.3     .05       0
  6074.3      .1       0
Bank Sta=4986.7,5019.1
XS Rating Curve= 0 ,0
Exp/Cntr=0.3,0.1

Type RM Length L Ch R = 1 ,31037   ,444,444,444
BEGIN DESCRIPTION:
Mapping XS 2b83b60a
END DESCRIPTION:
XS GIS Cut Line= 3
        2242921.      13301037.2      2242830.71     13300592.72
      2242532.42      13299746.4
#Sta/Elev= 30
    4290  227.28  4328.8   224.8  4412.8  223.03  4453.6  223.05  4480.7  220.24
  4504.6  219.52  4596.5   219.3  4632.6  216.51  4733.9  214.38  4760.4  212.59
  4834.6  210.97  4890.4  207.86  4924.5  207.21  4972.4  203.68    4978  201.18
  4990.6  199.41  4993.4  198.91  4996.6  199.41  5008.9  204.32  5034.6  205.55
  5055.2  204.52  5070.8  203.21  5078.5  199.66  5089.1  203.76  5096.4  204.61
  5195.1  207.08  5220.2  206.43  5283.3  207.33  5417.8  209.13  5640.9  214.52
#Mann= 6 ,-1 , 0
    4290     .05       0  4924.5      .1       0  4990.6     .07       0
  4996.6      .1       0  5055.2     .05       0  5283.3      .1       0
Bank Sta=4972.4,5008.9
XS Rating Curve= 0 ,0
Exp/Cntr=0.3,0.1

Type RM Length L Ch R = 1 ,30593   ,224,224,224
BEGIN DESCRIPTION:
Mapping XS 533a1f00
END DESCRIPTION:
XS GIS Cut Line= 2
      2243618.01     13300575.16      2242763.88     13299776.58
#Sta/Elev= 30
  4248.4  217.85  4275.9  216.56  4289.9  217.32    4318  217.24  4339.4   215.7
  4367.8  215.46  4431.3  213.69  4473.8  213.06  4487.9  213.42  4502.1  212.53
  4629.6  212.29  4693.1  209.94  4742.5  208.89  4778.1  207.24  4852.9  205.58
  4903.6  204.71  4940.8  204.56  4983.3  202.27  4997.4  199.74  5001.3  197.58
    5004  197.08  5007.3  197.58  5011.6  200.48  5039.9  202.26  5110.8  203.64
    5146  204.98    5167  204.74  5200.9  205.54  5253.3  206.67  5417.7  211.29
#Mann= 7 ,-1 , 0
  4248.4     .08       0  4852.9      .1       0  4903.6     .08       0
  5001.3     .07       0  5007.3     .08       0  5200.9     .05       0
  5253.3     .08       0
Bank Sta=4983.3,5039.9
XS Rating Curve= 0 ,0
Exp/Cntr=0.3,0.1

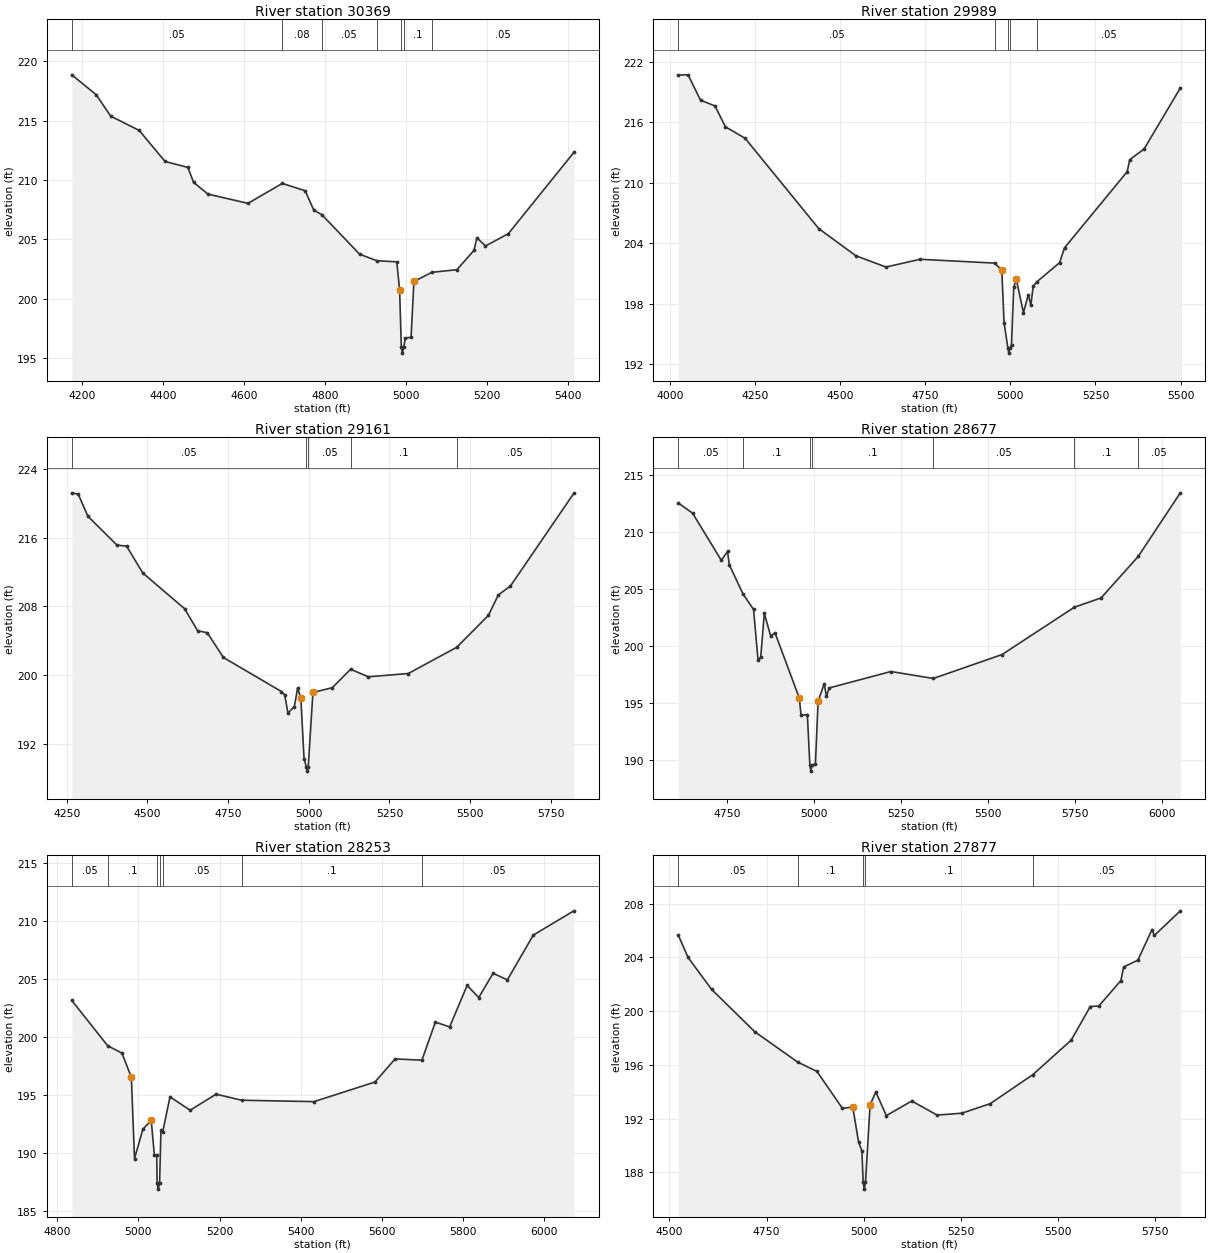
Type RM Length L Ch R = 1 ,30369   ,380,380,380
BEGIN DESCRIPTION:
Mapping XS e1659c6a
END DESCRIPTION:
XS GIS Cut Line= 2
      2243798.59     13300491.85      2242931.61     13299604.05
#Sta/Elev= 30
  4174.3  218.87  4235.1  217.18  4270.4  215.39  4341.1  214.18  4404.8  211.57
  4461.2  211.07  4475.4  209.81  4510.8  208.82  4609.8  208.04  4694.6  209.72
  4751.3   209.1  4772.4  207.47  4792.6  207.08  4885.6  203.76  4927.9  203.21
  4977.6  203.11  4984.6  200.73  4988.8  195.92  4991.5  195.42  4994.8  195.92
  4998.7   196.7  5012.9  196.75  5019.9  201.46  5064.3  202.23  5126.1  202.45
  5168.5  204.08  5175.5  205.14  5196.8  204.45  5253.4  205.49  5415.2  212.33
#Mann= 7 ,-1 , 0
  4174.3     .05       0  4694.6     .08       0  4792.6     .05       0
  4927.9      .1       0  4988.8     .07       0  4994.8      .1       0
  5064.3     .05       0
Bank Sta=4984.6,5019.9
XS Rating Curve= 0 ,0
Exp/Cntr=0.3,0.1

Type RM Length L Ch R = 1 ,29989   ,828,828,828
BEGIN DESCRIPTION:
TIMON CREEK 57.0
END DESCRIPTION:
XS GIS Cut Line= 3
      2243987.73     13300446.87      2243487.72     13299646.85
      2243137.73     13299246.87
#Sta/Elev= 30
  4024.5  220.71  4053.4  220.73    4090  218.21  4132.4  217.64  4163.1  215.57
  4220.9  214.43  4437.2  205.46  4546.3  202.76  4634.8  201.64    4735  202.41
  4954.4  202.03    4975  201.31  4981.7  196.12  4992.9  193.59  4995.7  193.09
  4998.9  193.59  5003.5  193.94  5010.1  199.66  5017.7  200.41  5038.6  197.11
  5052.9   198.9  5060.4  197.87  5067.1  199.72  5077.5  200.16  5144.9  202.08
  5159.2  203.55  5343.3  211.11  5350.9  212.31  5393.1  213.37  5499.4  219.42
#Mann= 5 ,-1 , 0
  4024.5     .05       0  4954.4      .1       0  4992.9     .07       0
  4998.9      .1       0  5077.5     .05       0
Bank Sta=4975,5017.7
XS Rating Curve= 0 ,0
Exp/Cntr=0.3,0.1

Type RM Length L Ch R = 1 ,29161   ,484,484,484
BEGIN DESCRIPTION:
TIMON CREEK 55.0
END DESCRIPTION:
XS GIS Cut Line= 3
      2244087.72     13300396.89      2244087.72     13299646.85
       2243687.7     13298946.82
#Sta/Elev= 30
  4265.3  221.23  4285.3  221.07  4315.3   218.5  4405.3  215.14  4435.3  215.01
  4485.3  211.89  4615.3  207.71  4655.3  205.15  4685.3  204.92  4735.3  202.03
  4915.3  198.06  4925.3  197.68  4935.3  195.56  4955.3  196.31  4965.3  198.46
  4975.3  197.36  4985.3  190.25  4992.3  189.28  4995.1  188.78  4998.3  189.28
  5012.8  197.95  5072.9  198.51  5129.6  200.66  5184.5  199.78  5308.3  200.16
  5458.6  203.22  5556.7  206.94  5587.6  209.33    5625  210.36  5821.6  221.18
#Mann= 5 ,-1 , 0
  4265.3     .05       0  4992.3     .03       0  4998.3     .05       0
  5129.6      .1       0  5458.6     .05       0
Bank Sta=4975.3,5012.8
XS Rating Curve= 0 ,0
Exp/Cntr=0.3,0.1

Type RM Length L Ch R = 1 ,28677   ,424,424,424
BEGIN DESCRIPTION:
TIMON CREEK 54.0
END DESCRIPTION:
XS GIS Cut Line= 3
      2244637.72     13300146.87      2244537.72     13299746.85
      2243887.72     13298946.85
#Sta/Elev= 30
  4609.4  212.56  4650.6  211.67  4733.1  207.54  4751.1  208.31  4756.3  207.14
  4795.7  204.58  4825.9  203.23  4838.8  198.78  4846.5  199.06  4856.8  202.89
  4874.8  200.93  4887.7  201.17  4957.3  195.47  4962.5  193.94  4980.5  194.02
  4987.8  189.56  4990.5  189.06  4993.8  189.56  5003.7   189.7  5011.4  195.18
  5028.9  196.72  5035.4  195.62  5043.3  196.35  5220.7  197.79  5342.4  197.18
  5540.3  199.28  5748.3  203.43  5824.8  204.24  5931.4  207.87  6052.5  213.45
#Mann= 7 ,-1 , 0
  4609.4     .05       0  4795.7      .1       0  4987.8     .07       0
  4993.8      .1       0  5342.4     .05       0  5748.3      .1       0
  5931.4     .05       0
Bank Sta=4957.3,5011.4
XS Rating Curve= 0 ,0
Exp/Cntr=0.3,0.1

Type RM Length L Ch R = 1 ,28253   ,376,376,376
BEGIN DESCRIPTION:
TIMON CREEK 53.0
END DESCRIPTION:
XS GIS Cut Line= 3
      2244987.71     13299846.81      2244937.72     13299646.85
      2244287.71     13298846.85
#Sta/Elev= 30
    4836  203.16  4924.4  199.26  4959.6  198.62  4982.8  196.54  4990.6  189.53
  5011.2  192.07  5031.8  192.82  5039.5  189.81  5045.3  189.81  5046.3   187.4
    5049   186.9  5052.3   187.4  5055.7  191.97  5060.1  191.84    5078  194.85
  5127.6   193.7  5191.5  195.08  5254.8  194.56  5432.9  194.44    5583  196.13
  5632.6  198.12  5698.6  198.01  5731.7  201.29  5766.9  200.88    5810  204.45
  5838.7  203.41  5873.9   205.5  5909.1  204.93    5973  208.79  6072.9  210.88
#Mann= 7 ,-1 , 0
    4836     .05       0  4924.4      .1       0  5046.3     .07       0
  5052.3      .1       0  5060.1     .05       0  5254.8      .1       0
  5698.6     .05       0
Bank Sta=4982.8,5031.8
XS Rating Curve= 0 ,0
Exp/Cntr=0.3,0.1

Type RM Length L Ch R = 1 ,27877   ,499,499,499
BEGIN DESCRIPTION:
TIMON CREEK 52.0
END DESCRIPTION:
XS GIS Cut Line= 3
      2245282.11     13299821.91      2245247.38      13299544.1
      2244664.05     13298717.72
#Sta/Elev= 30
  4522.9  205.66  4548.2  203.99  4608.6  201.62  4719.5  198.47  4829.8  196.21
  4879.7  195.51    4945  192.77    4972  192.84  4986.8  190.25  4995.4  189.59
  4998.6  187.25  5001.3  186.75  5004.6  187.25  5016.4  193.03  5031.2  193.98
  5058.2  192.22  5123.5  193.31  5188.8  192.26  5252.4   192.4  5325.4  193.11
  5434.6  195.26  5533.5  197.83  5582.9  200.34  5604.9  200.38  5661.5  202.27
  5668.6  203.28  5705.3  203.79  5741.6  206.07  5747.7  205.63  5814.4  207.46
#Mann= 5 ,-1 , 0
  4522.9     .05       0  4829.8      .1       0  4998.6     .07       0
  5004.6      .1       0  5434.6     .05       0
Bank Sta=4972,5016.4
XS Rating Curve= 0 ,0
Exp/Cntr=0.3,0.1

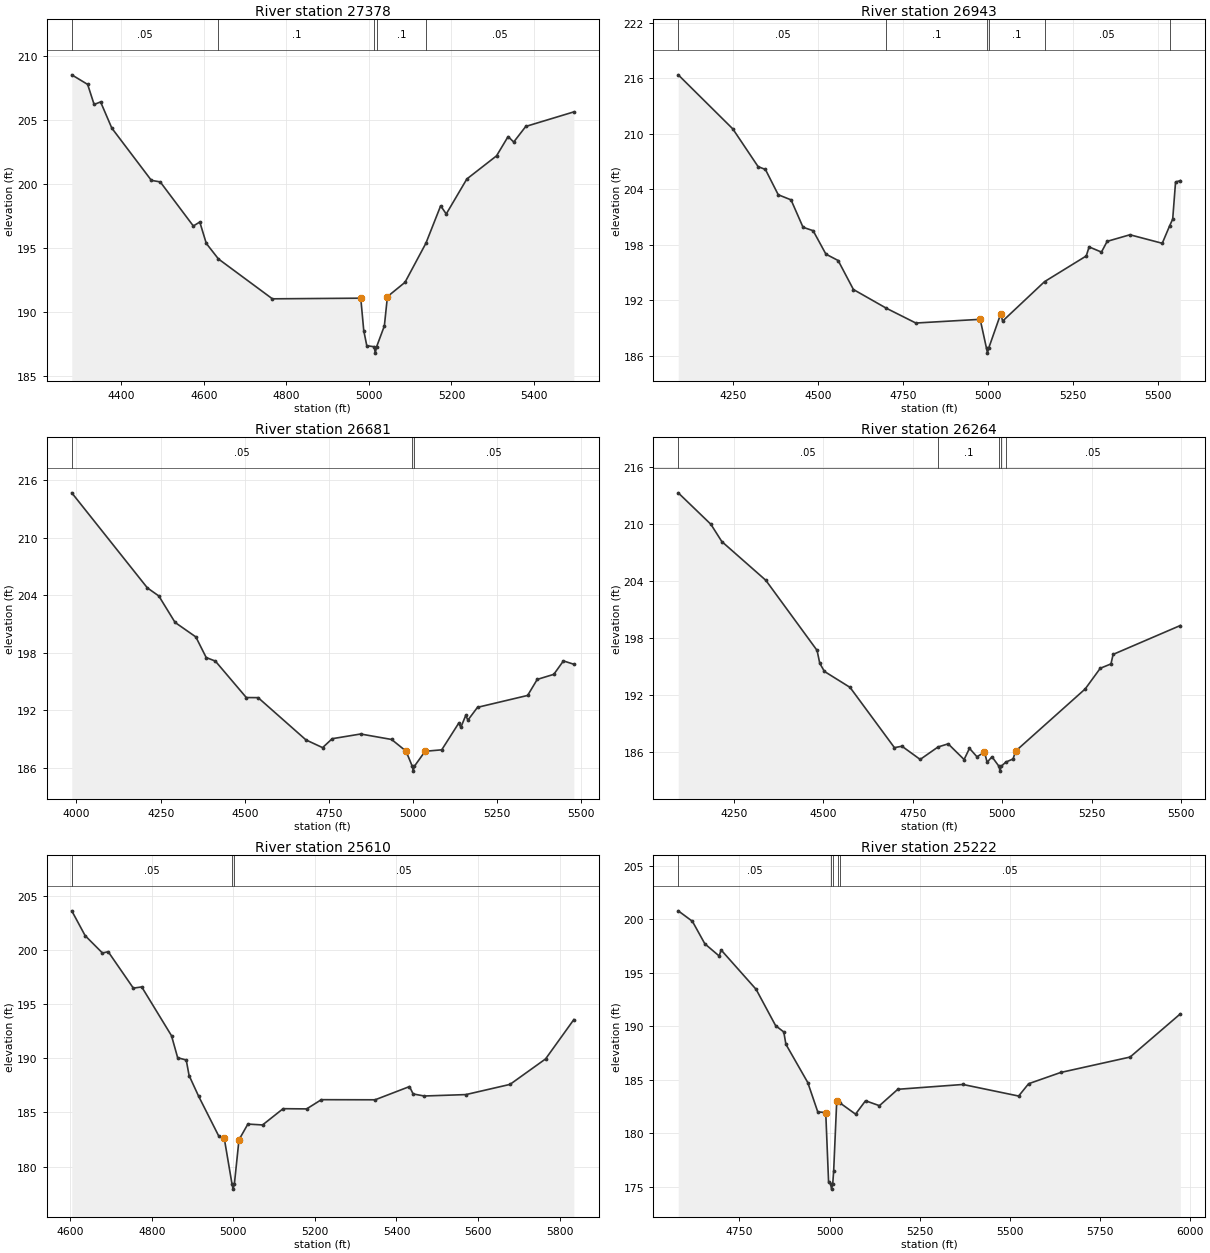
Type RM Length L Ch R = 1 ,27378   ,435,435,435
BEGIN DESCRIPTION:
TIMON CREEK 51.0
END DESCRIPTION:
XS GIS Cut Line= 3
      2245719.61     13299509.39      2245455.71     13299057.99
      2244900.17     13298641.34
#Sta/Elev= 30
  4279.5  208.54    4318  207.79  4333.7  206.22  4349.4  206.42  4376.6  204.37
  4472.5  200.28    4494  200.16  4574.2  196.71  4589.9  197.02  4605.6  195.35
  4635.1  194.13  4765.9  191.01  4980.2  191.06  4987.4  188.53  4994.8  187.34
  5012.6  187.26  5015.4  186.76  5018.6  187.26  5037.4  188.89  5044.8  191.18
  5087.4   192.3  5138.1  195.36  5173.9  198.29  5187.4  197.65  5237.4  200.39
  5309.4   202.2  5337.4  203.71    5351  203.28  5380.2   204.5  5496.8  205.64
#Mann= 5 ,-1 , 0
  4279.5     .05       0  4635.1      .1       0  5012.6     .07       0
  5018.6      .1       0  5138.1     .05       0
Bank Sta=4980.2,5044.8
XS Rating Curve= 0 ,0
Exp/Cntr=0.3,0.1

Type RM Length L Ch R = 1 ,26943   ,262,262,262
BEGIN DESCRIPTION:
TIMON CREEK 50.0
END DESCRIPTION:
XS GIS Cut Line= 3
      2246037.72     13299446.85      2245587.72     13298646.85
      2245087.71     13298396.85
#Sta/Elev= 30
  4088.6  216.36  4249.2  210.52  4323.5  206.45  4345.1  206.14  4382.8  203.41
  4420.4  202.86  4455.7   199.9  4485.4  199.53    4523     197    4559  196.31
  4603.9  193.18  4701.2  191.15  4787.5  189.56  4976.8  189.96  4995.5  186.81
  4998.3  186.31  5001.5  186.81  5037.2  190.55  5042.8  189.77  5166.2  194.03
  5288.8   196.8  5297.2  197.78  5333.5  197.22  5350.3  198.38  5417.3  199.09
  5512.4  198.17  5533.8  200.03  5543.1  200.78  5551.5  204.78  5565.5  204.94
#Mann= 6 ,-1 , 0
  4088.6     .05       0  4701.2      .1       0  4995.5     .07       0
  5001.5      .1       0  5166.2     .05       0  5533.8      .1       0
Bank Sta=4976.8,5037.2
XS Rating Curve= 0 ,0
Exp/Cntr=0.3,0.1

Type RM Length L Ch R = 1 ,26681   ,417,417,417
BEGIN DESCRIPTION:
TIMON CREEK 49.0
END DESCRIPTION:
XS GIS Cut Line= 3
      2246292.63     13299365.25      2246192.33     13298947.36
      2245490.35     13298150.66
#Sta/Elev= 30
    3986  214.66  4210.6  204.75  4244.6  203.91  4292.9  201.15  4354.6  199.64
  4385.4  197.49  4412.6  197.12  4504.5  193.32  4539.6  193.31  4681.9   188.9
  4731.2   188.1  4759.7  189.03  4844.2  189.52  4936.2  188.95  4978.9  187.74
  4997.7  186.15  5000.4  185.65  5003.7  186.15  5035.8  187.72  5085.1  187.87
  5135.4  190.64    5142  190.22  5156.3  191.45  5162.9  190.97  5191.4   192.3
  5340.3  193.54  5368.8  195.21  5418.1  195.74  5446.6  197.14  5477.6  196.79
#Mann= 3 ,-1 , 0
    3986     .05       0  4997.7    .035       0  5003.7     .05       0
Bank Sta=4978.9,5035.8
XS Rating Curve= 0 ,0
Exp/Cntr=0.3,0.1

Type RM Length L Ch R = 1 ,26264   ,654,654,654
BEGIN DESCRIPTION:
TIMON CREEK 48.0
END DESCRIPTION:
XS GIS Cut Line= 3
      2246526.62     13299225.96      2246420.76     13298735.64
       2245914.7     13297990.45
#Sta/Elev= 30
  4094.7  213.32  4185.9  210.01  4216.5  208.19  4339.3  204.12  4482.5  196.74
    4490  195.39    4503  194.53  4574.6  192.85  4698.6  186.51  4719.6  186.66
  4770.5  185.27  4820.3  186.58  4848.7  186.91  4893.2  185.26  4908.2  186.44
  4929.1  185.55  4950.1  186.04  4957.5  184.97  4971.1  185.55  4990.7  184.54
  4993.5  184.04  4996.7  184.54  5009.7  184.99    5030  185.32  5036.9  186.14
  5231.5  192.69  5273.5  194.86  5303.4  195.32  5309.4  196.32  5497.1  199.36
#Mann= 5 ,-1 , 0
  4094.7     .05       0  4820.3      .1       0  4990.7     .07       0
  4996.7      .1       0  5009.7     .05       0
Bank Sta=4950.1,5036.9
XS Rating Curve= 0 ,0
Exp/Cntr=0.3,0.1

Type RM Length L Ch R = 1 ,25610   ,388,388,388
BEGIN DESCRIPTION:
TIMON CREEK 47.0
END DESCRIPTION:
XS GIS Cut Line= 3
       2246805.2     13298863.76      2246849.76     13298674.36
      2246276.25     13297811.31
#Sta/Elev= 30
    4604  203.59  4636.8   201.3  4679.2   199.7  4693.3  199.82  4754.9  196.46
  4775.5  196.57  4848.5  192.07  4863.6  190.04  4884.6  189.83  4891.6   188.4
  4914.7  186.51  4963.7  182.86  4977.8  182.61  4996.7  178.42  4999.4  177.92
  5002.7  178.42  5013.9  182.47  5035.7  183.92  5071.7  183.84  5122.1  185.34
  5179.8  185.32  5215.8  186.17  5347.6  186.16  5431.9  187.38  5440.8   186.7
  5467.9  186.51  5570.1  186.64  5678.3  187.58  5765.5  189.93  5834.8  193.56
#Mann= 3 ,-1 , 0
    4604     .05       0  4996.7     .03       0  5002.7     .05       0
Bank Sta=4977.8,5013.9
XS Rating Curve= 0 ,0
Exp/Cntr=0.3,0.1

Type RM Length L Ch R = 1 ,25222   ,480,480,480
BEGIN DESCRIPTION:
TIMON CREEK 46.0
END DESCRIPTION:
XS GIS Cut Line= 3
      2247122.75     13298691.12       2247172.9     13298507.22
      2246615.76     13297443.06
#Sta/Elev= 30
  4580.3  200.77  4619.6  199.79  4654.1  197.69  4693.9  196.55  4699.1  197.12
  4796.2  193.44  4850.3  190.05  4872.9  189.46  4878.8  188.31  4939.4  184.74
  4967.1     182  4989.2  181.94  4997.1  175.44  5002.6  175.29  5005.3  174.79
  5008.6  175.29  5011.2  176.51  5019.7  183.05  5022.8  182.99  5028.5  182.84
  5071.8  181.79  5099.5  183.04    5138  182.58    5189  184.11  5369.5  184.56
  5523.9  183.48  5551.6  184.63  5640.5  185.68  5832.9  187.12  5972.1  191.15
#Mann= 5 ,-1 , 0
  4580.3     .05       0  5002.6     .03       0  5008.6     .05       0
  5022.8      .1       0  5028.5     .05       0
Bank Sta=4989.2,5019.7
XS Rating Curve= 0 ,0
Exp/Cntr=0.3,0.1