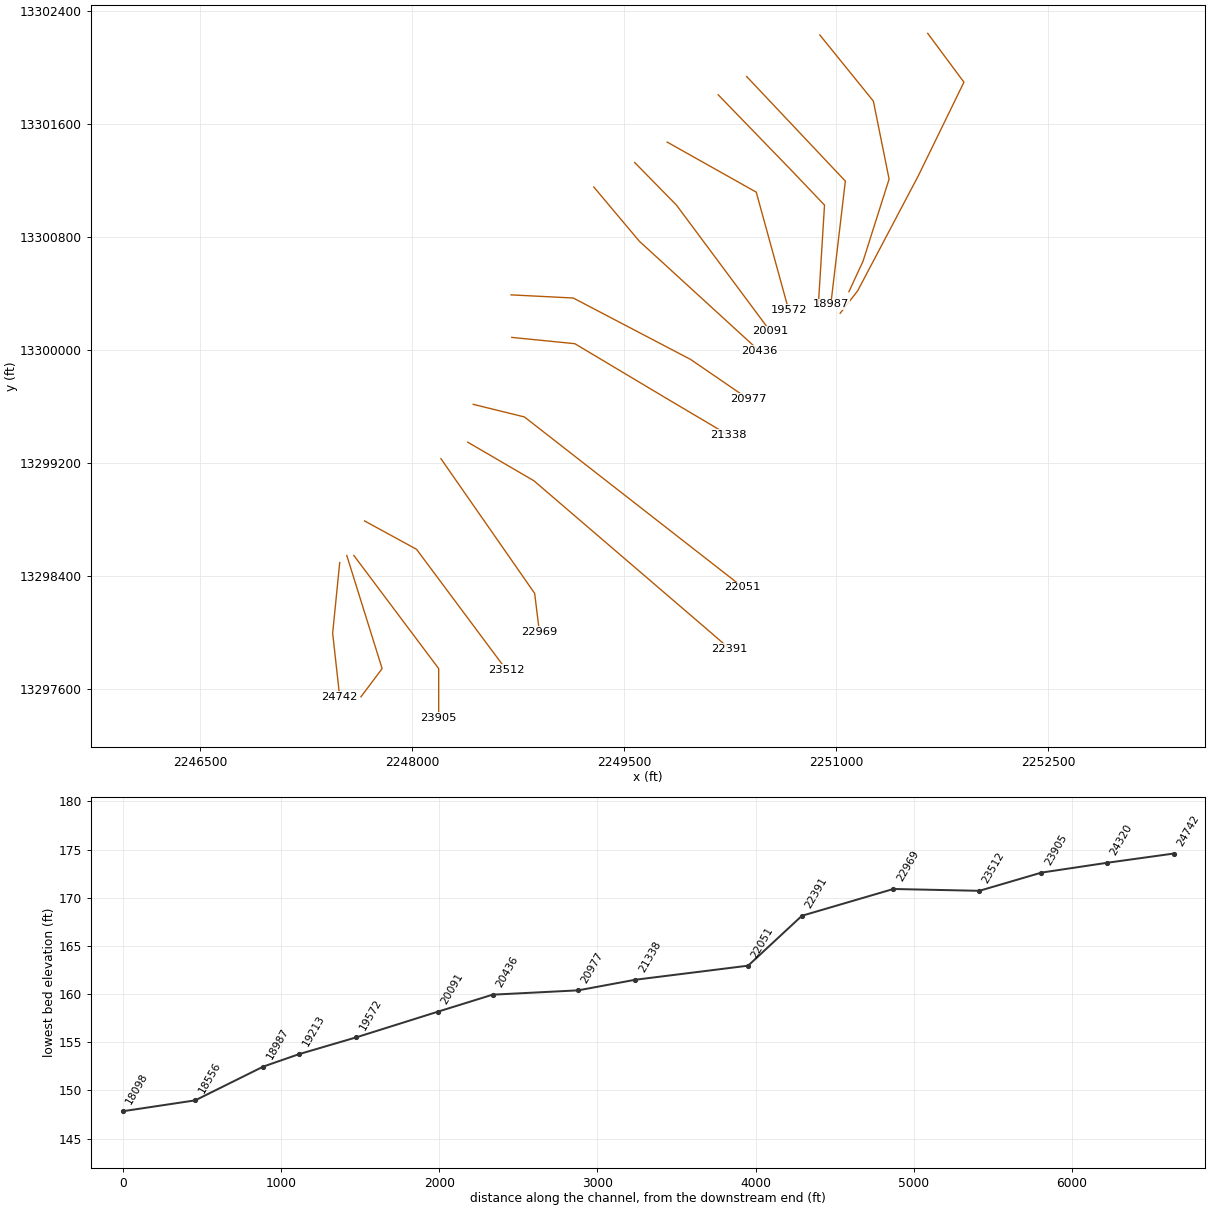
HEC-RAS study TIMON CREEK.prj: TIMON CREEK Base Level Engineering

--- TIMON CREEK.g01 (geometry) --- (continued)

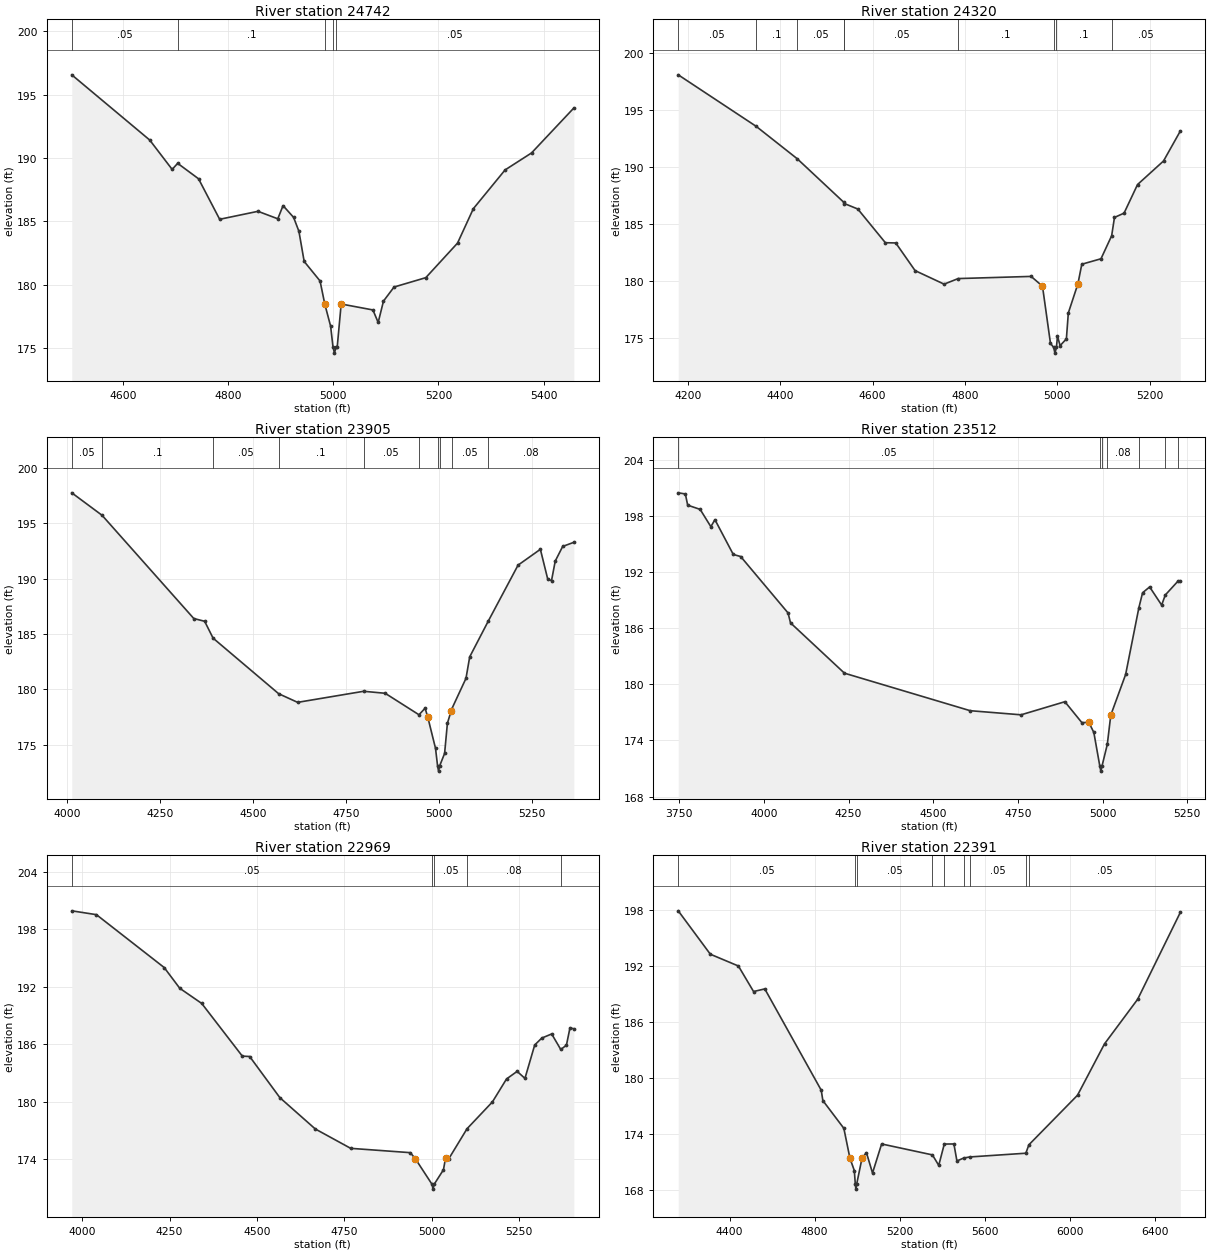
Type RM Length L Ch R = 1 ,24742   ,422,422,422
BEGIN DESCRIPTION:
TIMON CREEK 45.0
END DESCRIPTION:
XS GIS Cut Line= 3
      2247487.72      13298496.9      2247437.72     13297996.85
      2247487.72     13297546.86
#Sta/Elev= 30
  4502.4  196.57  4650.7  191.42  4693.4   189.1  4703.9  189.58  4743.6  188.36
  4783.8  185.16  4856.7  185.79  4894.4   185.2  4904.4  186.24  4924.5  185.31
  4934.6  184.21  4944.6  181.83  4974.8  180.29  4983.9  178.45  4994.9  176.72
  4999.4  175.09  5002.2  174.59  5005.4  175.09  5007.5  175.09    5015  178.47
  5075.4     178  5085.4  177.01  5095.5   178.7  5115.6  179.81    5176  180.55
  5236.4  183.28  5266.5     186  5326.9  189.06  5377.2   190.4  5457.7  193.95
#Mann= 5 ,-1 , 0
  4502.4     .05       0  4703.9      .1       0  4983.9     .05       0
  4999.4     .03       0  5005.4     .05       0
Bank Sta=4983.9,5015
XS Rating Curve= 0 ,0
Exp/Cntr=0.3,0.1

Type RM Length L Ch R = 1 ,24320   ,415,415,415
BEGIN DESCRIPTION:
TIMON CREEK 44.0
END DESCRIPTION:
XS GIS Cut Line= 3
      2247537.73     13298546.83      2247787.72     13297746.85
      2247637.73     13297546.87
#Sta/Elev= 30
  4178.6  198.08  4347.3  193.56  4436.4  190.71  4537.7  186.87  4538.8  186.77
  4567.8  186.29  4627.5  183.33    4650  183.31  4691.9  180.88  4754.8  179.69
  4785.3  180.18  4943.4  180.37    4968  179.51  4985.3  174.49  4992.2  174.13
    4995  173.63  4998.2  174.13  5000.5  175.12  5006.2  174.29  5019.8  174.88
    5024  177.16  5044.8  179.72  5053.2  181.44  5094.8  181.92  5117.9  183.94
    5124  185.55  5144.8  185.93    5174  188.44  5230.3  190.51  5266.7  193.14
#Mann= 9 ,-1 , 0
  4178.6     .05       0  4347.3      .1       0  4436.4     .05       0
  4537.7      .1       0  4538.8     .05       0  4785.3      .1       0
  4992.2     .07       0  4998.2      .1       0  5117.9     .05       0
Bank Sta=4968,5044.8
XS Rating Curve= 0 ,0
Exp/Cntr=0.3,0.1

Type RM Length L Ch R = 1 ,23905   ,393,393,393
BEGIN DESCRIPTION:
TIMON CREEK 43.0
END DESCRIPTION:
XS GIS Cut Line= 3
      2247587.71     13298546.87      2248187.72     13297746.85
      2248187.72     13297396.87
#Sta/Elev= 30
  4012.3  197.74  4093.8  195.71  4340.4  186.39  4369.6  186.14  4392.2  184.62
  4568.6   179.6  4619.6  178.82    4797  179.82    4855  179.64  4945.9   177.7
  4962.3  178.29  4969.6  177.48  4990.4  174.66  4995.8  173.11  4998.5  172.61
  5001.8  173.11  5014.8  174.21  5022.3  176.93  5032.3  178.04  5033.7   178.2
  5072.3  180.99  5082.3  182.93  5132.4  186.17  5212.3  191.21  5272.3  192.64
  5292.3  189.92  5302.3  189.82  5312.3  191.58  5332.3   192.9  5362.3  193.27
#Mann= 10 ,-1 , 0
  4012.3     .05       0  4093.8      .1       0  4392.2     .05       0
  4568.6      .1       0    4797     .05       0  4945.9      .1       0
  4995.8     .07       0  5001.8      .1       0  5033.7     .05       0
  5132.4     .08       0
Bank Sta=4969.6,5032.3
XS Rating Curve= 0 ,0
Exp/Cntr=0.3,0.1

Type RM Length L Ch R = 1 ,23512   ,543,543,543
BEGIN DESCRIPTION:
TIMON CREEK 42.0
END DESCRIPTION:
XS GIS Cut Line= 3
      2247663.22     13298791.34       2248030.9     13298590.79
      2248666.07     13297738.33
#Sta/Elev= 30
  3747.4  200.47  3768.4  200.35  3775.3  199.15  3812.1   198.7  3843.7  196.85
  3855.7   197.6  3909.9  193.88  3931.7  193.66  4071.5  187.63  4078.8  186.57
    4238  181.19  4609.1  177.18  4759.3  176.74  4888.6  178.14  4938.6  175.91
  4959.5  175.92  4974.1  174.85  4991.9  171.22  4994.7  170.72  4997.9  171.22
  5013.8  173.58  5024.1  176.71  5067.9  181.05    5107  188.19    5118  189.79
  5138.8  190.41  5174.2  188.47    5185  189.55  5222.2  191.02  5229.3  191.05
#Mann= 7 ,-1 , 0
  3747.4     .05       0  4991.9     .04       0  4997.9     .05       0
  5013.8     .08       0    5107      .1       0    5185     .08       0
  5222.2     .05       0
Bank Sta=4959.5,5024.1
XS Rating Curve= 0 ,0
Exp/Cntr=0.3,0.1

Type RM Length L Ch R = 1 ,22969   ,578,578,578
BEGIN DESCRIPTION:
TIMON CREEK 41.0
END DESCRIPTION:
XS GIS Cut Line= 3
      2248203.63     13299231.49      2248866.62     13298278.79
      2248900.04     13298005.82
#Sta/Elev= 30
  3970.2  199.91  4040.7  199.51  4234.5     194    4279  191.84  4341.8  190.26
  4457.9  184.77  4478.9  184.73  4565.3  180.44  4666.5  177.18  4767.8  175.16
  4938.3  174.71  4952.8  174.07  5000.4  171.41  5003.2  170.91  5006.4  171.41
  5033.1  172.93  5039.2  174.19    5048  174.06  5100.4   177.2  5173.1     180
  5213.4  182.39  5243.7  183.18  5266.1  182.45    5294  185.93  5314.2  186.65
  5342.5  187.08  5368.5  185.46  5384.7  185.91  5394.8  187.71  5405.9  187.62
#Mann= 5 ,-1 , 0
  3970.2     .05       0  5000.4     .03       0  5006.4     .05       0
  5100.4     .08       0  5368.5      .1       0
Bank Sta=4952.8,5039.2
XS Rating Curve= 0 ,0
Exp/Cntr=0.3,0.1

Type RM Length L Ch R = 1 ,22391   ,340,340,340
BEGIN DESCRIPTION:
TIMON CREEK 39.0
END DESCRIPTION:
XS GIS Cut Line= 4
      2248393.06     13299348.49      2248861.05      13299075.5
      2250114.62     13298000.22      2250242.71     13297888.83
#Sta/Elev= 30
  4158.1  197.89  4309.2  193.25  4441.3  191.99  4512.6  189.26  4565.5  189.54
  4831.1  178.71  4838.8   177.6  4937.6  174.63  4966.1  171.45  4986.9  170.11
  4991.6  168.63  4994.4  168.13  4997.6  168.63  5023.2  171.45    5044  172.03
  5072.5  169.85  5115.4  172.96  5354.5  171.79  5384.2  170.67  5410.3  172.95
  5455.6  172.96  5469.8  171.14    5501  171.45  5529.9  171.57  5794.1  171.97
  5808.5  172.87  6037.3  178.17  6164.6  183.67  6320.4  188.43  6521.2  197.72
#Mann= 9 ,-1 , 0
  4158.1     .05       0  4991.6     .03       0  4997.6     .05       0
  5354.5     .08       0  5410.3      .1       0    5501     .08       0
  5529.9     .05       0  5794.1     .08       0  5808.5     .05       0
#XS Ineff= 2 , 0
       0                 5128.41       0  172.84
Permanent Ineff=
       F       T
Bank Sta=4966.1,5023.2
XS Rating Curve= 0 ,0
Exp/Cntr=0.3,0.1

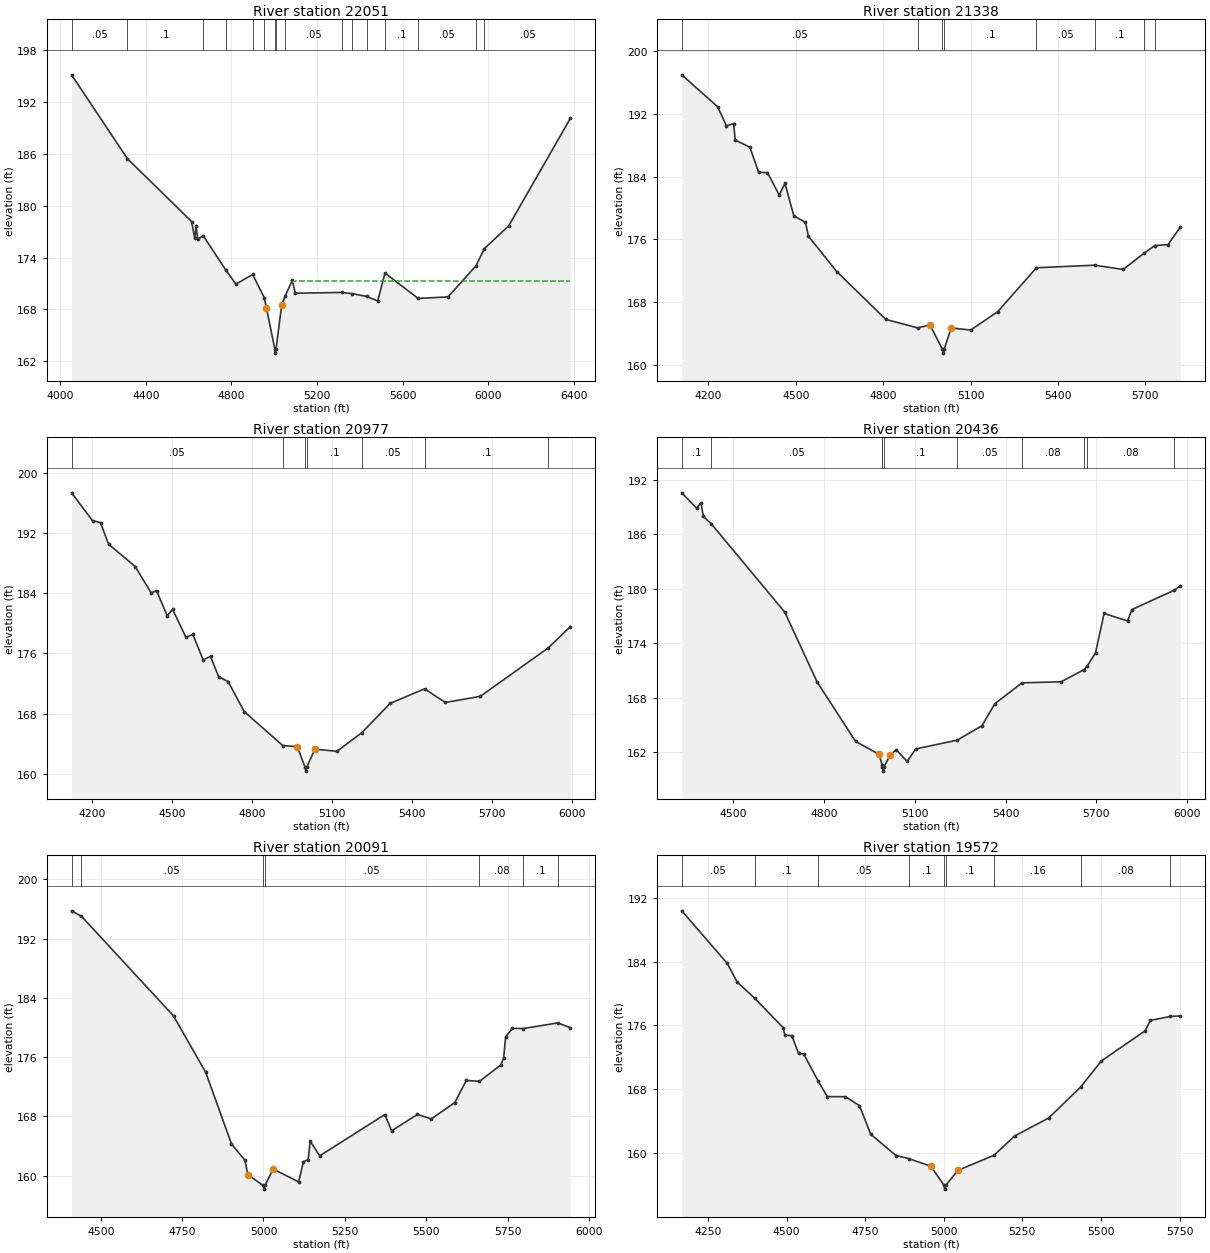
Type RM Length L Ch R = 1 ,22051   ,713,713,713
BEGIN DESCRIPTION:
TIMON CREEK 38.0
END DESCRIPTION:
XS GIS Cut Line= 3
      2248432.05     13299615.93      2248794.19     13299526.79
      2250337.49     13298323.35
#Sta/Elev= 30
  4053.8  195.14  4314.2  185.45  4614.4  178.17  4628.8  176.26  4635.2  177.63
  4643.3   176.1  4668.2  176.55  4775.1  172.53  4821.5  170.93  4899.6  172.05
  4954.6  169.33  4963.8  168.18  5003.1  163.45  5005.8  162.95  5009.1  163.45
    5035  168.47  5050.7   169.5  5084.8  171.38  5099.2  169.88  5315.4  169.97
  5363.5  169.84  5433.2   169.5  5483.7  168.98  5518.1  172.21  5672.7  169.28
  5812.1  169.45  5943.1  173.05    5982  175.03  6096.1  177.68  6383.8   190.1
#Mann= 16 ,-1 , 0
  4053.8     .05       0  4314.2      .1       0  4668.2     .05       0
  4775.1      .1       0  4899.6     .05       0  4954.6      .1       0
  5003.1     .07       0  5009.1      .1       0  5050.7     .05       0
  5315.4      .1       0  5363.5     .05       0  5433.2     .08       0
  5518.1      .1       0  5672.7     .05       0  5943.1     .08       0
    5982     .05       0
#XS Ineff= 2 , 0
                         5088.07           171.3
Permanent Ineff=
       F       F
Bank Sta=4963.8,5035
XS Rating Curve= 0 ,0
Exp/Cntr=0.3,0.1

Type RM Length L Ch R = 1 ,21338   ,361,361,361
BEGIN DESCRIPTION:
TIMON CREEK 37.0
END DESCRIPTION:
XS GIS Cut Line= 4
      2248705.02      13300089.5      2249150.76     13300044.93
      2249841.62     13299632.64       2250237.2     13299398.64
#Sta/Elev= 30
  4108.7  196.96    4232  192.89  4262.2  190.45  4286.7  190.75  4292.3  188.64
  4342.6  187.73  4372.7  184.53  4402.9   184.5  4443.1  181.66  4463.2  183.12
  4493.3     179  4533.5  178.15  4543.6  176.39  4640.6  171.89  4809.3  165.79
  4918.4  164.71  4960.7  165.08  5003.5  161.99  5006.2  161.49  5009.5  161.99
  5033.7   164.7  5100.5  164.43  5193.6  166.78  5326.3  172.37  5526.3   172.7
  5623.9  172.15  5695.6  174.22  5732.4   175.2    5778  175.32  5820.8  177.58
#Mann= 8 ,-1 , 0
  4108.7     .05       0  4918.4      .1       0  5003.5     .07       0
  5009.5      .1       0  5326.3     .05       0  5526.3      .1       0
  5695.6     .08       0  5732.4      .1       0
Bank Sta=4960.7,5033.7
XS Rating Curve= 0 ,0
Exp/Cntr=0.3,0.1

Type RM Length L Ch R = 1 ,20977   ,541,541,541
BEGIN DESCRIPTION:
TIMON CREEK 36.0
END DESCRIPTION:
XS GIS Cut Line= 4
      2248699.46     13300390.36      2249139.62     13300368.07
      2249969.76      13299933.5      2250376.48     13299654.93
#Sta/Elev= 30
  4123.6  197.32    4202  193.63    4232  193.37    4262  190.52  4362.2  187.54
  4422.2  184.03  4442.3  184.34  4482.3  180.99  4502.3  181.87  4552.4  178.15
  4578.4  178.53  4616.9  175.16  4644.6  175.61  4675.1  172.93  4710.8  172.27
  4771.4  168.28  4915.9  163.78    4970  163.65  4999.4  160.89  5002.1  160.39
  5005.4  160.89  5036.2  163.31  5118.8  163.02  5212.8  165.51  5318.4  169.38
  5447.5  171.31  5525.6   169.5  5656.4  170.31  5910.7  176.72  5994.3  179.56
#Mann= 7 ,-1 , 0
  4123.6     .05       0  4915.9      .1       0  4999.4     .07       0
  5005.4      .1       0  5212.8     .05       0  5447.5      .1       0
  5910.7     .08       0
Bank Sta=4970,5036.2
XS Rating Curve= 0 ,0
Exp/Cntr=0.3,0.1

Type RM Length L Ch R = 1 ,20436   ,345,345,345
BEGIN DESCRIPTION:
TIMON CREEK 35.0
END DESCRIPTION:
XS GIS Cut Line= 3
      2249284.45     13301153.67      2249607.62     13300769.22
      2250453.59      13299995.6
#Sta/Elev= 30
  4329.6  190.55  4378.9  188.86  4393.2  189.47    4401  187.96  4427.5  187.13
  4670.2  177.42  4776.9  169.76  4904.3   163.2    4982  161.79  4992.2   160.6
  4993.1  160.44  4995.9  159.94  4999.1  160.44  5017.7   161.7  5038.7   162.3
  5074.5     161  5102.8  162.38  5239.4  163.34  5321.8  164.93  5364.3  167.35
  5454.2  169.65  5583.9  169.77  5659.8  171.11  5669.1  171.45  5697.3  172.94
  5725.7  177.28  5803.4  176.46  5817.6  177.71  5958.3  179.85  5978.2  180.34
#Mann= 10 ,-1 , 0
  4329.6      .1       0  4427.5     .05       0  4992.2      .1       0
  4993.1     .07       0  4999.1      .1       0  5239.4     .05       0
  5454.2     .08       0  5659.8      .1       0  5669.1     .08       0
  5958.3      .1       0
Bank Sta=4982,5017.7
XS Rating Curve= 0 ,0
Exp/Cntr=0.3,0.1

Type RM Length L Ch R = 1 ,20091   ,519,519,519
BEGIN DESCRIPTION:
TIMON CREEK 34.0
END DESCRIPTION:
XS GIS Cut Line= 3
      2249574.21     13301326.34      2249869.48      13301025.5
      2250532.49     13300134.06
#Sta/Elev= 30
  4410.5  195.75  4440.9  195.01  4723.8  181.56  4822.8  173.93  4901.7  164.29
  4943.4  162.06  4951.8  160.15  4998.8  158.68  5001.6  158.18  5004.8  158.68
  5029.7  160.89  5108.2  159.16  5122.8  161.88  5137.4  162.16  5143.6  164.67
  5172.8  162.67  5373.1  168.25  5393.9  166.05  5473.2  168.27  5515.8  167.66
  5587.9  169.86  5623.4  172.86  5663.7  172.73  5729.7  174.95  5738.1  175.91
  5744.3  178.75  5765.2  179.88  5798.6  179.86  5904.5  180.62    5943  179.98
#Mann= 7 ,-1 , 0
  4410.5      .1       0  4440.9     .05       0  4998.8     .04       0
  5004.8     .05       0  5663.7     .08       0  5798.6      .1       0
  5904.5     .05       0
#XS Ineff= 2 , 0
                         5144.55          164.48
Permanent Ineff=
       F       F
Bank Sta=4951.8,5029.7
XS Rating Curve= 0 ,0
Exp/Cntr=0.3,0.1

Type RM Length L Ch R = 1 ,19572   ,359,359,359
BEGIN DESCRIPTION:
Mapping XS c0b1be34
END DESCRIPTION:
XS GIS Cut Line= 3
      2249803.82     13301471.01      2250434.02     13301116.86
      2250662.96     13300284.35
#Sta/Elev= 30
  4166.8  190.36  4311.3  183.79  4343.2  181.43  4398.8  179.41  4489.2  175.73
  4494.9  174.77  4516.6  174.74  4538.3  172.51  4554.2  172.45  4600.5  169.06
  4629.5  167.09  4687.5  167.08  4732.1  165.96  4767.8  162.38  4848.1  159.71
  4888.4  159.33  4958.7  158.37  5000.8     156  5003.5   155.5  5006.8     156
  5045.3  157.85  5160.2  159.75  5225.5  162.15  5333.9  164.41  5436.2  168.32
  5501.6  171.56  5640.3  175.32  5657.2  176.63  5720.7  177.13  5753.1   177.2
#Mann= 9 ,-1 , 0
  4166.8     .05       0  4398.8      .1       0  4600.5     .05       0
  4888.4      .1       0  5000.8     .07       0  5006.8      .1       0
  5160.2     .16       0  5436.2     .08       0  5720.7     .05       0
Bank Sta=4958.7,5045.3
XS Rating Curve= 0 ,0
Exp/Cntr=0.3,0.1

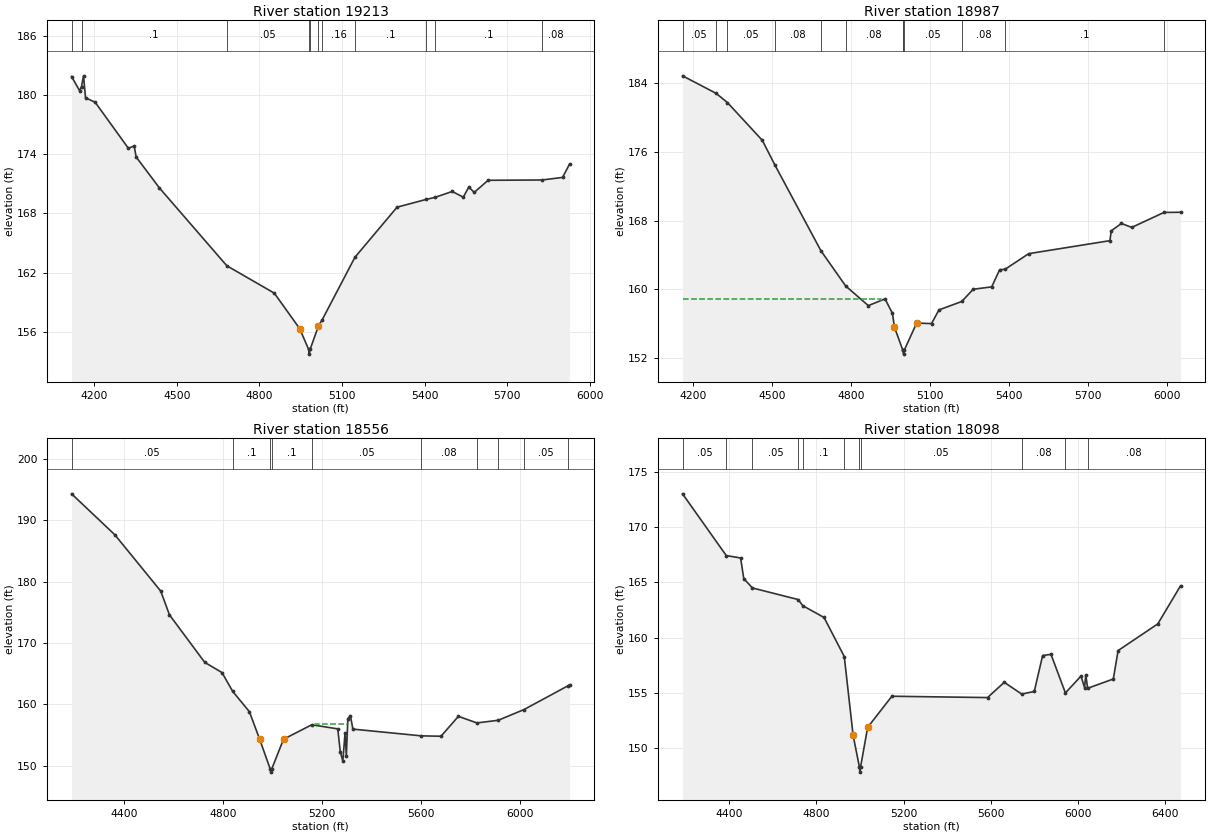
Type RM Length L Ch R = 1 ,19213   ,226,226,226
BEGIN DESCRIPTION:
Mapping XS 76b09119
END DESCRIPTION:
XS GIS Cut Line= 4
      2250164.78     13301805.49      2250688.48     13301265.07
       2250916.9      13301025.5      2250872.35     13300301.53
#Sta/Elev= 30
  4117.9  181.86  4147.2  180.42    4154  180.85  4161.4  181.93  4168.6  179.71
  4203.8  179.25  4324.2   174.6  4345.3  174.83  4352.5  173.72  4437.2  170.58
  4681.9  162.71  4854.4  159.94  4946.5  156.35  4978.7  154.27  4981.5  153.77
  4984.7  154.27  5014.6  156.61  5028.8  157.27  5147.2  163.57  5300.3  168.64
  5405.5  169.42  5437.9  169.63  5500.7  170.23  5540.7  169.65  5560.8  170.67
  5580.8  170.14  5630.9  171.36  5826.6  171.39  5901.4  171.65  5926.8     173
#Mann= 11 ,-1 , 0
  4117.9     .05       0    4154      .1       0  4681.9     .05       0
  4978.7     .03       0  4984.7     .05       0  5014.6      .1       0
  5028.8     .16       0  5147.2      .1       0  5405.5     .16       0
  5437.9      .1       0  5826.6     .08       0
Bank Sta=4946.5,5014.6
XS Rating Curve= 0 ,0
Exp/Cntr=0.3,0.1

Type RM Length L Ch R = 1 ,18987   ,431,431,431
BEGIN DESCRIPTION:
Mapping XS 514ebb0a
END DESCRIPTION:
XS GIS Cut Line= 3
      2250366.28     13301934.59      2251064.23     13301194.98
      2250961.47     13300323.45
#Sta/Elev= 30
  4158.8  184.83  4286.2   182.8  4329.7  181.72  4462.3  177.33  4510.6  174.44
  4685.6  164.48  4779.8  160.39  4865.7  158.12  4929.2   158.9  4957.5  157.21
  4964.8  155.63  4996.2  152.99    4997  152.98  4999.7  152.48    5003  152.98
  5049.4  156.09    5106  156.03  5134.3  157.62  5221.2   158.6  5264.5  160.02
    5335   160.3  5365.2  162.29  5385.6  162.34  5475.9  164.16  5784.7  165.67
  5789.8  166.81  5828.3  167.67  5867.7  167.21  5990.3  168.95  6053.3  168.97
#Mann= 12 ,-1 , 0
  4158.8     .05       0  4286.2     .08       0  4329.7     .05       0
  4510.6     .08       0  4685.6     .05       0  4779.8     .08       0
  4996.2     .05       0    4997     .03       0    5003     .05       0
  5221.2     .08       0  5385.6      .1       0  5990.3     .08       0
#XS Ineff= 2 , 0
         4911.93  158.92
Permanent Ineff=
       F       F
Bank Sta=4964.8,5049.4
XS Rating Curve= 0 ,0
Exp/Cntr=0.3,0.1

Type RM Length L Ch R = 1 ,18556   ,458,458,458
BEGIN DESCRIPTION:
Mapping XS a5f1c701
END DESCRIPTION:
XS GIS Cut Line= 5
      2250883.48     13302228.93      2251262.33     13301760.93
      2251373.76     13301209.36       2251189.9     13300629.93
       2251089.6      13300412.6
#Sta/Elev= 30
  4188.7  194.33  4363.7  187.65  4549.1  178.47  4584.3   174.6  4726.6  166.87
  4796.4   165.2    4840  162.12  4907.2  158.82  4948.7  154.33  4991.4  149.47
  4994.1  148.97  4997.4  149.47  5045.1  154.33  5159.2  156.69  5264.3  156.02
  5274.5  152.28  5284.7  150.78  5293.8  155.39  5298.9  151.64  5305.1   157.7
  5315.3  158.16  5325.5  155.98  5602.4  154.88  5681.4  154.82  5751.7  158.06
  5826.5  156.99  5912.6  157.42  6016.8  159.17  6193.9  163.03  6200.8   163.2
#Mann= 10 ,-1 , 0
  4188.7     .05       0    4840      .1       0  4991.4     .07       0
  4997.4      .1       0  5159.2     .05       0  5602.4     .08       0
  5826.5     .05       0  5912.6     .08       0  6016.8     .05       0
  6193.9     .08       0
#XS Ineff= 2 ,-1
 5171.33  5308.7  156.79 5315.06 5987.92  158.07
Permanent Ineff=
       T       F
Bank Sta=4948.7,5045.1
XS Rating Curve= 0 ,0
Exp/Cntr=0.3,0.1

Type RM Length L Ch R = 1 ,18098   ,359,359,359
BEGIN DESCRIPTION:
Mapping XS 7a30d583
END DESCRIPTION:
XS GIS Cut Line= 5
      2251646.78     13302240.05      2251903.05     13301894.64
       2251579.9     13301231.64       2251150.9     13300418.22
      2251027.77     13300260.33
#Sta/Elev= 30
  4184.7     173  4385.5  167.42  4451.4   167.2    4466  165.34  4505.8  164.49
  4716.3  163.44  4736.7  162.89  4834.8  161.82  4927.6  158.29  4968.3  151.17
  4996.8  148.34  4999.6  147.84  5002.8  148.34  5035.1  151.89  5146.3   154.7
  5585.8  154.58  5662.6  155.96  5742.4   154.9  5800.4  155.13  5838.8  158.38
  5877.2  158.49  5943.4     155    6015  156.52  6031.4  155.49    6037  156.64
  6045.6  155.42  6163.5  156.26  6185.5  158.83  6367.7  161.24  6472.2  164.68
#Mann= 11 ,-1 , 0
  4184.7     .05       0  4385.5     .08       0  4505.8     .05       0
  4716.3     .08       0  4736.7      .1       0  4927.6     .05       0
  4996.8     .03       0  5002.8     .05       0  5742.4     .08       0
  5943.4     .05       0  6045.6     .08       0
#XS Ineff= 2 , 0
                         5171.88          154.65
Permanent Ineff=
       F       F
Bank Sta=4968.3,5035.1
XS Rating Curve= 0 ,0
Exp/Cntr=0.3,0.1