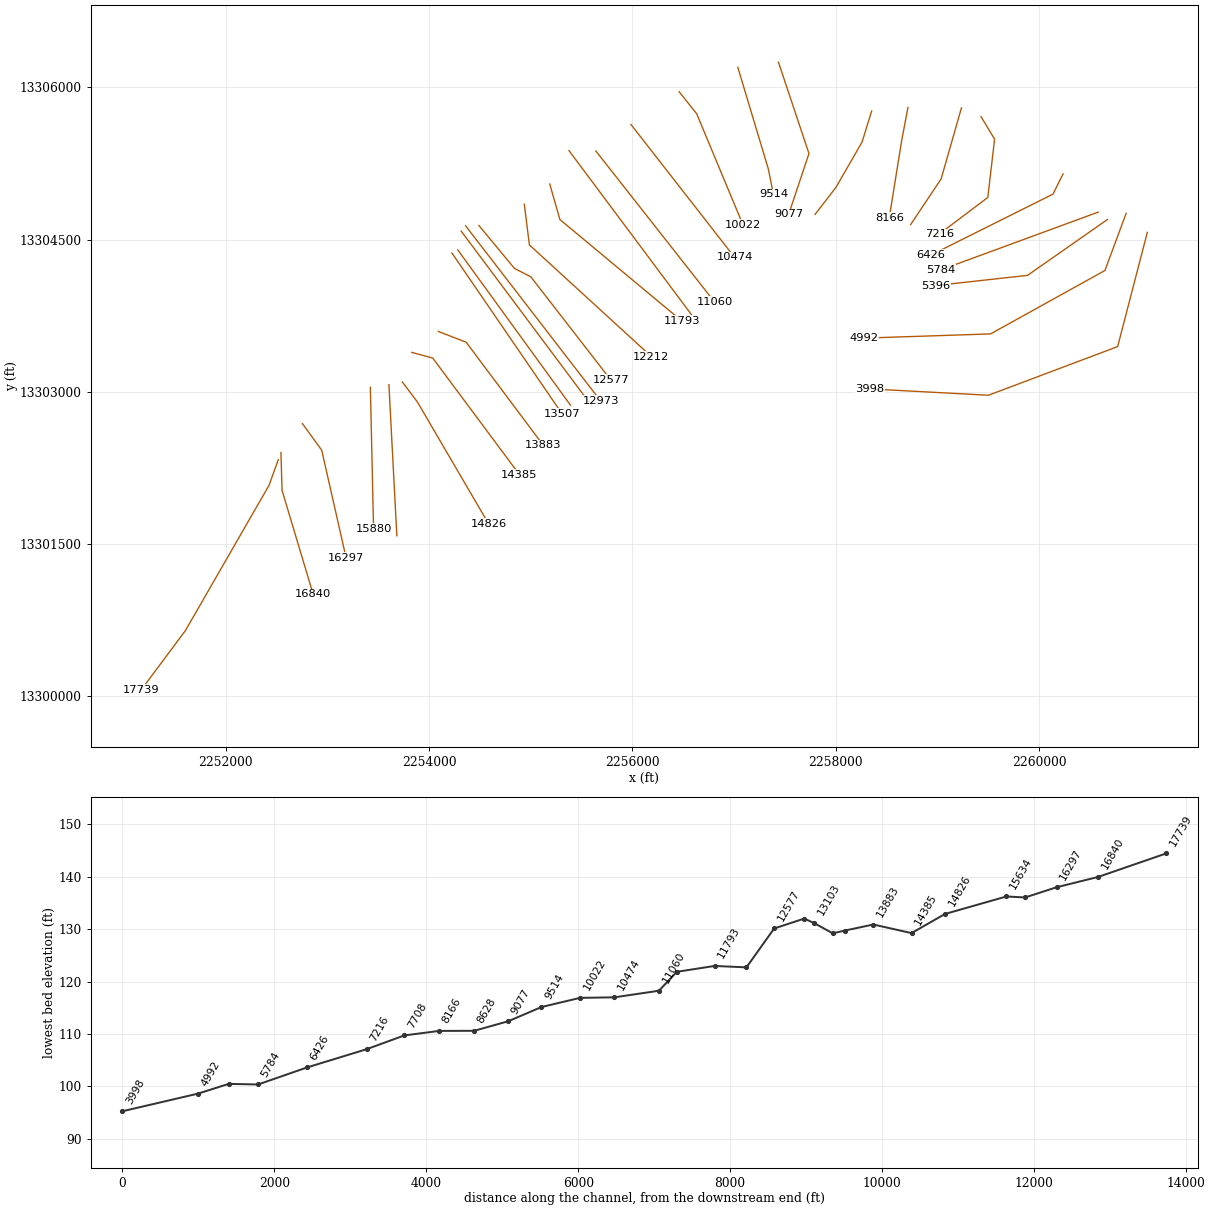
HEC-RAS study TIMON CREEK.prj: TIMON CREEK Base Level Engineering

--- TIMON CREEK.g01 (geometry) --- (continued)

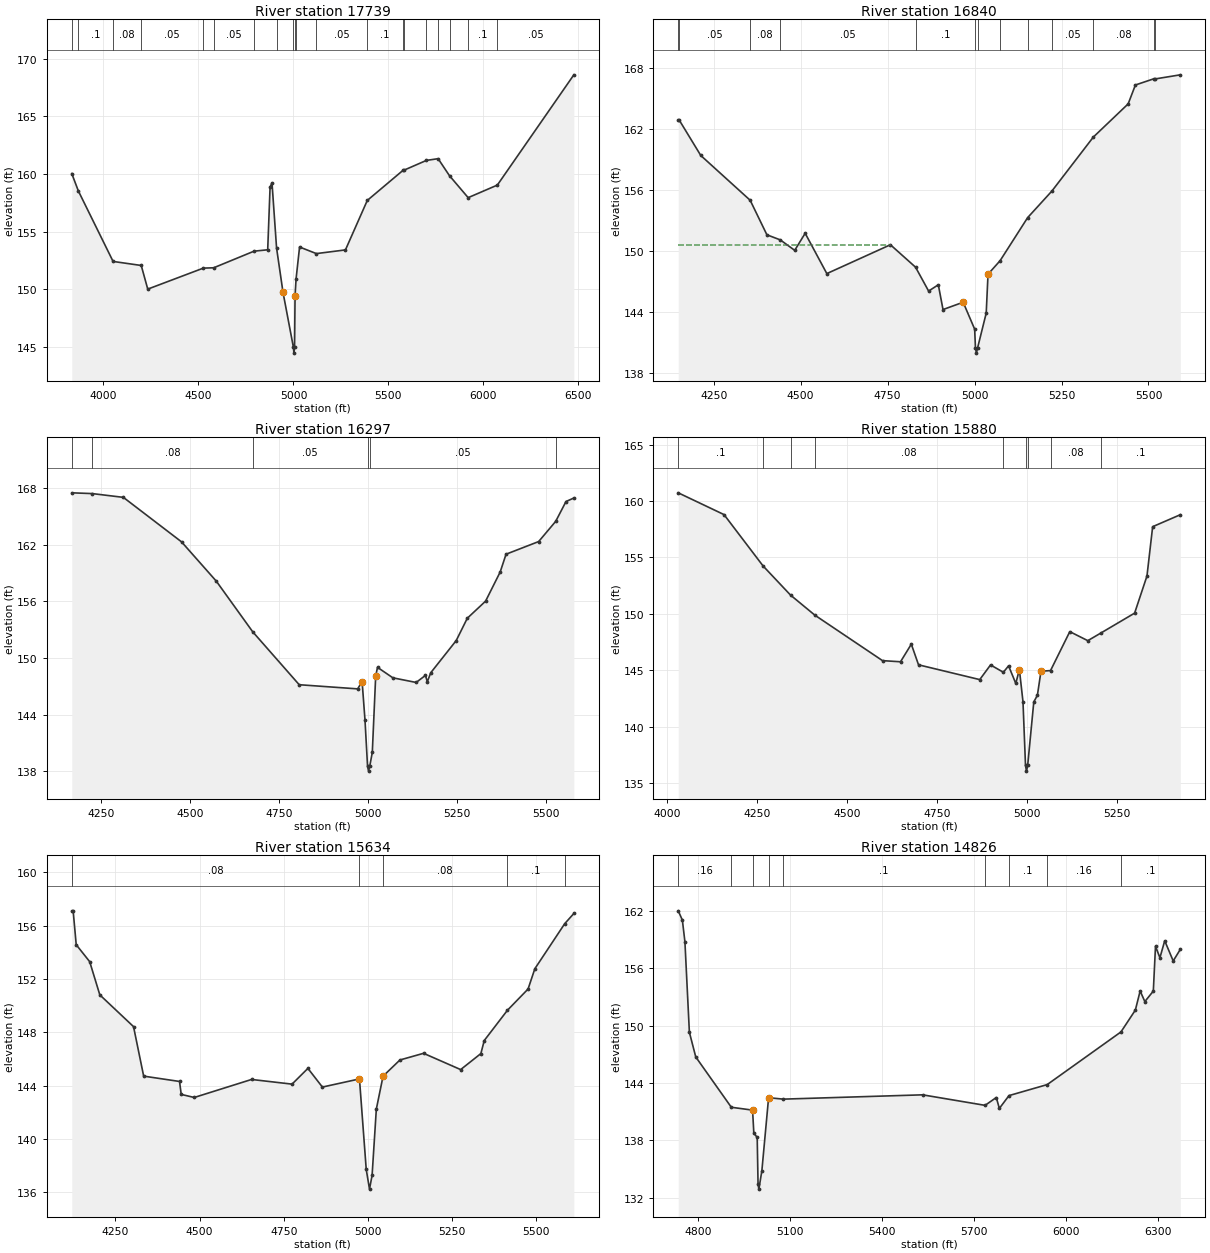
Type RM Length L Ch R = 1 ,17739   ,899,899,899
BEGIN DESCRIPTION:
Mapping XS 5484a227
END DESCRIPTION:
XS GIS Cut Line= 4
      2252517.53     13302331.05      2252426.89     13302078.56
      2251604.81       13300648.      2251171.89     13300066.47
#Sta/Elev= 30
    3833  160.04  3867.7  158.53  4050.5  152.42  4198.7  152.07    4233  150.02
  4525.6  151.84  4580.1  151.87  4792.6  153.31  4864.5  153.43    4877  158.86
  4887.1  159.24  4911.2  153.58  4945.2  149.73  4999.9  144.97  5002.6  144.47
  5005.9  144.97 5008.52  149.44    5014  150.93  5032.3  153.67  5120.7   153.1
  5273.8  153.42  5388.8  157.71  5576.2  160.31  5584.3  160.35  5700.1  161.18
  5761.7  161.33  5821.6  159.85  5919.8  157.95  6073.4  159.04  6476.2   168.6
#Mann= 20 ,-1 , 0
    3833     .08       0  3867.7      .1       0  4050.5     .08       0
  4198.7     .05       0  4525.6     .08       0  4580.1     .05       0
  4792.6     .08       0  4911.2     .05       0  4999.9     .04       0
  5005.9     .05       0    5014     .08       0  5120.7     .05       0
  5388.8      .1       0  5576.2     .08       0  5584.3      .1       0
  5700.1     .08       0  5761.7      .1       0  5821.6     .08       0
  5919.8      .1       0  6073.4     .05       0
#XS Ineff= 2 , 0
         4880.68  157.63
Permanent Ineff=
       F       F
Bank Sta=4945.2,5008.52
XS Rating Curve= 0 ,0
Exp/Cntr=0.3,0.1

Type RM Length L Ch R = 1 ,16840   ,543,543,543
BEGIN DESCRIPTION:
TIMON CREEK 29.0
END DESCRIPTION:
XS GIS Cut Line= 3
      2252543.76      13302401.6       2252554.9     13302028.36
      2252861.34     13301003.19
#Sta/Elev= 30
  4148.1  162.89  4151.4  162.89  4212.9  159.43  4354.9  155.02    4403  151.62
  4441.4  151.12    4483  150.09    4513  151.77  4575.3   147.8  4758.1  150.64
  4830.4  148.43  4867.9  146.08  4895.8   146.7  4909.3  144.26  4967.2  144.98
  5000.3  142.33  5002.6  140.47  5005.3  139.97  5008.6  140.47  5033.5  143.91
  5038.7  147.74  5073.4  149.07  5152.6  153.31  5222.4  155.93  5341.4  161.24
  5441.6  164.51  5462.4  166.37  5515.4  166.98  5519.9  166.97  5591.5  167.37
#Mann= 13 ,-1 , 0
  4148.1     .08       0  4151.4     .05       0  4354.9     .08       0
  4441.4     .05       0  4830.4      .1       0  5002.6     .07       0
  5008.6      .1       0  5073.4     .05       0  5152.6      .1       0
  5222.4     .05       0  5341.4     .08       0  5515.4      .1       0
  5519.9     .08       0
#XS Ineff= 2 , 0
            4760   150.6
Permanent Ineff=
       F       F
Bank Sta=4967.2,5038.7
XS Rating Curve= 0 ,0
Exp/Cntr=0.3,0.1

Type RM Length L Ch R = 1 ,16297   ,417,417,417
BEGIN DESCRIPTION:
TIMON CREEK 28.0
END DESCRIPTION:
XS GIS Cut Line= 3
      2252755.49     13302685.77       2252944.9     13302423.93
      2253184.47     13301365.37
#Sta/Elev= 30
  4168.8  167.49  4226.3  167.41  4313.5  167.01  4476.7   162.3  4574.4  158.13
  4676.5  152.77  4806.8  147.17  4970.9  146.73  4983.3  147.51  4991.4  143.43
  4998.6  138.52  5001.4  138.02  5004.6  138.52  5011.9     140  5021.4  148.08
  5026.5  149.01  5069.6   147.9  5134.9  147.41  5161.1  148.16  5166.2  147.48
  5175.9  148.44  5247.4  151.85  5278.4  154.21  5329.7  156.02  5370.7  159.11
  5387.1  160.99  5478.6  162.33  5526.4  164.47  5555.3  166.57  5577.3  166.94
#Mann= 6 ,-1 , 0
  4168.8      .1       0  4226.3     .08       0  4676.5     .05       0
  4998.6     .04       0  5004.6     .05       0  5526.4     .08       0
Bank Sta=4983.3,5021.4
XS Rating Curve= 0 ,0
Exp/Cntr=0.3,0.1

Type RM Length L Ch R = 1 ,15880   ,246,246,246
BEGIN DESCRIPTION:
Mapping XS 0cb6fb27
END DESCRIPTION:
XS GIS Cut Line= 2
       2253423.6     13303043.98      2253454.81     13301650.02
#Sta/Elev= 30
    4031  160.72  4158.2  158.79  4266.6  154.24  4342.8  151.66  4410.4  149.88
  4598.3  145.85  4648.3  145.75  4678.3  147.31  4698.3  145.48  4868.3  144.17
  4898.3  145.47  4933.9  144.82  4948.4  145.39  4968.4  143.83  4978.4  145.06
  4988.4  142.21  4995.4  136.56  4998.1  136.06  5001.4  136.56  5018.4  142.19
  5028.4  142.78  5038.4  144.91  5064.9  144.97  5118.4  148.42  5168.4  147.62
  5205.9  148.32  5298.4  150.06  5332.7  153.35  5348.5  157.72  5425.3  158.78
#Mann= 9 ,-1 , 0
    4031      .1       0  4266.6     .08       0  4342.8      .1       0
  4410.4     .08       0  4933.9      .1       0  4995.4     .07       0
  5001.4      .1       0  5064.9     .08       0  5205.9      .1       0
#XS Ineff= 2 , 0
       0 4678.18   147.3               0
Permanent Ineff=
       F       F
Bank Sta=4978.4,5038.4
XS Rating Curve= 0 ,0
Exp/Cntr=0.3,0.1

Type RM Length L Ch R = 1 ,15634   ,808,808,808
BEGIN DESCRIPTION:
Mapping XS 5a9147fa
END DESCRIPTION:
XS GIS Cut Line= 2
      2253605.89     13303070.03      2253683.98     13301581.17
#Sta/Elev= 30
  4120.6  157.11  4124.7  157.11  4133.8  154.57  4173.8   153.3  4203.9  150.81
    4304  148.43  4334.1  144.72  4440.6  144.32  4445.6  143.35  4484.3  143.12
  4654.5  144.47  4774.7  144.12  4821.8   145.3  4864.8   143.9  4974.9  144.51
    4995  137.73  5004.7  136.25  5012.4  137.28    5025  142.25    5045  144.72
  5095.1  145.93  5165.2  146.43  5275.4  145.21  5335.4  146.41  5345.5  147.39
  5414.4  149.66  5475.6  151.25  5495.7  152.77  5584.5  156.15  5611.5  156.91
#Mann= 5 ,-1 , 0
  4120.6     .08       0  4974.9    .035       0    5045     .08       0
  5414.4      .1       0  5584.5     .08       0
#XS Ineff= 2 , 0
         4818.18  145.04 5165.91           146.2
Permanent Ineff=
       F       F
Bank Sta=4974.9,5045
XS Rating Curve= 0 ,0
Exp/Cntr=0.3,0.1

Type RM Length L Ch R = 1 ,14826   ,441,441,441
BEGIN DESCRIPTION:
TIMON CREEK 25.0
END DESCRIPTION:
XS GIS Cut Line= 3
      2253737.75     13303096.82      2253887.72     13302896.85
      2254587.72     13301696.85
#Sta/Elev= 30
  4734.2  162.01  4747.7  161.04    4756  158.78  4770.6  149.31  4791.4  146.73
  4907.5  141.47  4976.9  141.17    4981  138.76    4992  138.32  4994.8  133.41
  4997.5  132.91  5007.3  134.85  5029.2  142.47  5077.2  142.32    5532  142.77
    5736  141.67  5772.6  142.49  5782.6  141.35  5814.1  142.69  5938.8  143.84
  6179.7  149.35  6226.6  151.63  6242.3  153.63  6257.6  152.52  6285.3  153.62
  6292.4  158.31  6306.8   157.1  6322.5  158.88  6350.2  156.77  6373.4  157.98
#Mann= 9 ,-1 , 0
  4734.2     .16       0  4907.5     .07       0  4976.9    .035       0
  5029.2     .07       0  5077.2      .1       0    5736     .08       0
  5814.1      .1       0  5938.8     .16       0  6179.7      .1       0
Bank Sta=4976.9,5029.2
XS Rating Curve= 0 ,0
Exp/Cntr=0.3,0.1

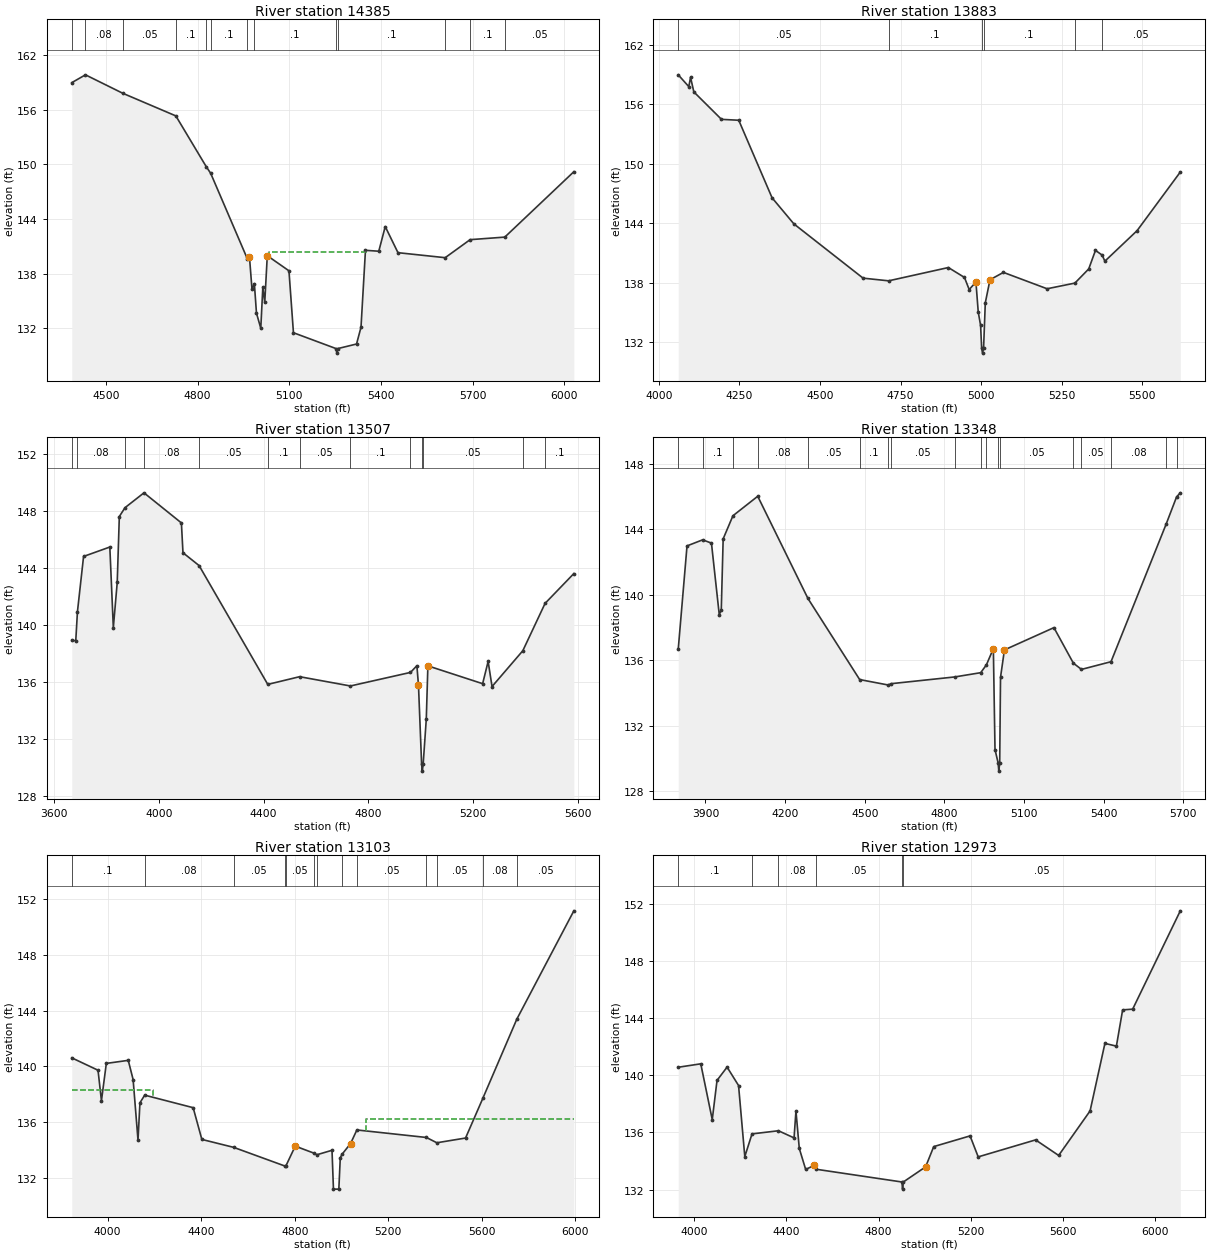
Type RM Length L Ch R = 1 ,14385   ,502,502,502
BEGIN DESCRIPTION:
TIMON CREEK 24.0
END DESCRIPTION:
XS GIS Cut Line= 3
      2253830.78     13303387.78       2254036.9     13303332.07
      2254889.35     13302184.33
#Sta/Elev= 30
  4388.2  158.96    4433  159.82  4555.4  157.79  4728.8  155.31  4828.4  149.73
  4842.8  149.01  4963.2  139.59  4969.7  139.85  4978.1  136.25  4985.8  136.89
  4992.7  133.65  5006.8  131.99  5013.5  136.51  5019.8  134.84  5028.1  139.96
    5099   138.3  5113.7   131.5    5253  129.76  5255.7  129.26    5259  129.76
  5320.2  130.26  5334.8   132.1  5349.4  140.55    5393  140.45  5414.1  143.16
  5455.8  140.29  5610.3  139.74  5691.9  141.72  5805.4     142  6031.4  149.18
#Mann= 13 ,-1 , 0
  4388.2      .1       0    4433     .08       0  4555.4     .05       0
  4728.8      .1       0  4828.4     .05       0  4842.8      .1       0
  4963.2     .12       0  4985.8      .1       0    5253     .07       0
    5259      .1       0  5610.3     .08       0  5691.9      .1       0
  5805.4     .05       0
#XS Ineff= 2 ,-1
 5035.21 5357.36  140.34 5418.14 5892.24  142.82
Permanent Ineff=
       T       F
Bank Sta=4969.7,5028.1
XS Rating Curve= 0 ,0
Exp/Cntr=0.3,0.1

Type RM Length L Ch R = 1 ,13883   ,376,376,376
BEGIN DESCRIPTION:
TIMON CREEK 23.0
END DESCRIPTION:
XS GIS Cut Line= 3
      2254092.63     13303593.92      2254365.62     13303488.07
      2255123.02     13302474.49
#Sta/Elev= 30
  4059.9  158.96  4092.7  157.77  4098.1  158.71  4108.3  157.24  4194.1  154.47
  4247.7  154.38  4351.1  146.56  4418.8  143.93  4633.5  138.46  4712.8  138.19
  4898.2  139.53  4948.2  138.53  4962.8  137.31  4983.7  138.07  4990.9  135.05
  4998.2   133.7  5001.5   131.4  5004.2   130.9  5007.5   131.4  5012.8  135.97
  5027.4   138.3  5069.1  139.04  5204.6  137.39  5290.8  137.96  5333.8  139.39
  5354.7  141.26  5375.6  140.78  5383.9  140.17  5483.9  143.25    5618  149.16
#Mann= 6 ,-1 , 0
  4059.9     .05       0  4712.8      .1       0  5001.5     .07       0
  5007.5      .1       0  5290.8     .08       0  5375.6     .05       0
Bank Sta=4983.7,5027.4
XS Rating Curve= 0 ,0
Exp/Cntr=0.3,0.1

Type RM Length L Ch R = 1 ,13507   ,159,159,159
BEGIN DESCRIPTION:
Mapping XS 7ead943d
END DESCRIPTION:
XS GIS Cut Line= 2
      2254225.71     13304366.82        2255309.     13302783.55
#Sta/Elev= 30
  3666.9   138.9  3682.2  138.89  3688.6  140.92    3712  144.79  3812.3  145.45
  3825.7   139.8  3840.6  142.97  3848.6  147.59  3870.4  148.21  3942.8  149.25
  4085.8  147.14  4091.8  145.05  4153.4  144.15  4415.8  135.82  4537.5  136.36
  4731.5  135.71  4961.1  136.66  4985.6  137.13  4991.7  135.75  5003.6  130.24
  5006.4  129.74  5009.6  130.24  5021.5  133.39  5027.6  137.12  5236.8  135.87
  5257.8  137.43  5272.7  135.67  5390.3  138.18  5475.4   141.5  5585.3  143.59
#Mann= 13 ,-1 , 0
  3666.9      .1       0  3688.6     .08       0  3870.4     .05       0
  3942.8     .08       0  4153.4     .05       0  4415.8      .1       0
  4537.5     .05       0  4731.5      .1       0  4961.1     .05       0
  5003.6    .035       0  5009.6     .05       0  5390.3     .08       0
  5475.4      .1       0
Bank Sta=4991.7,5027.6
XS Rating Curve= 0 ,0
Exp/Cntr=0.3,0.1

Type RM Length L Ch R = 1 ,13348   ,245,245,245
BEGIN DESCRIPTION:
Mapping XS c126a2e3
END DESCRIPTION:
XS GIS Cut Line= 2
      2254282.95     13304398.13      2255392.34     13302866.87
#Sta/Elev= 30
  3797.4  136.66  3830.5  142.97  3889.3  143.34  3922.5  143.14  3951.9  138.77
  3959.5  139.07  3966.6   143.4  4003.4  144.81  4096.8     146  4285.9  139.76
  4480.7  134.81  4587.5  134.48  4600.1  134.56  4838.8  134.97  4936.6  135.23
  4958.1  135.71  4984.2   136.7  4990.4  130.54  5002.1  129.72  5004.8  129.22
  5008.1  129.72  5011.2  134.95  5025.9  136.62  5212.3  137.98  5285.6  135.81
  5316.1  135.43  5427.3   135.9  5634.7  144.29  5674.2  145.96  5688.3  146.21
#Mann= 18 ,-1 , 0
  3797.4     .08       0  3889.3      .1       0  4003.4     .05       0
  4096.8     .08       0  4285.9     .05       0  4480.7      .1       0
  4587.5     .08       0  4600.1     .05       0  4838.8      .1       0
  4936.6     .08       0  4958.1     .05       0  5002.1    .035       0
  5008.1     .05       0  5285.6     .08       0  5316.1     .05       0
  5427.3     .08       0  5634.7     .05       0  5674.2      .1       0
#XS Ineff= 2 , 0
                         5193.18          137.63
Permanent Ineff=
       F       F
Bank Sta=4984.2,5025.9
XS Rating Curve= 0 ,0
Exp/Cntr=0.3,0.1

Type RM Length L Ch R = 1 ,13103   ,130,130,130
BEGIN DESCRIPTION:
Mapping XS e328bb86
END DESCRIPTION:
XS GIS Cut Line= 2
      2254316.39     13304583.01      2255600.58     13302861.79
#Sta/Elev= 30
  3846.4   140.6  3958.7  139.71  3973.3  137.52  3994.2   140.2    4088  140.42
  4108.8  139.04  4129.7  134.69    4138  137.37  4158.3  137.92  4365.6  137.02
  4402.8  134.74    4539  134.17  4756.3  132.84  4762.3  132.84  4802.3  134.26
  4881.3  133.76  4894.9  133.64  4959.5  133.96  4965.7  131.17  4988.7  131.17
  4994.9  133.42  5001.8  133.66  5038.7  134.44  5065.9  135.42  5363.3  134.88
  5407.9   134.5  5530.7  134.84  5604.3  137.68    5750  143.38  5993.9  151.16
#Mann= 13 ,-1 , 0
  3846.4      .1       0  4158.3     .08       0    4539     .05       0
  4756.3    .035       0  4762.3     .05       0  4881.3     .08       0
  4894.9     .05       0  5001.8     .08       0  5065.9     .05       0
  5363.3     .08       0  5407.9     .05       0  5604.3     .08       0
    5750     .05       0
#XS Ineff= 2 , 0
         4191.76  138.28 5106.53           136.2
Permanent Ineff=
       F       F
Bank Sta=4802.3,5038.7
XS Rating Curve= 0 ,0
Exp/Cntr=0.3,0.1

Type RM Length L Ch R = 1 ,12973   ,396,396,396
BEGIN DESCRIPTION:
Mapping XS d9e937cc
END DESCRIPTION:
XS GIS Cut Line= 2
      2254359.79      13304635.1      2255689.23     13302908.52
#Sta/Elev= 30
  3930.5  140.57  4028.3  140.81  4078.1   136.9  4098.9  139.65  4142.5  140.58
  4192.3  139.29  4219.4  134.31  4250.7   135.9  4365.4  136.12  4433.2  135.62
  4441.4   137.5  4455.9  134.88  4483.6  133.41  4520.3  133.69  4530.2  133.42
  4901.4  132.53  4904.1  132.03  4907.4  132.53  5004.1  133.59  5039.4  135.01
  5197.1  135.76  5232.4  134.29  5481.5  135.48  5581.6  134.39    5718  137.51
  5782.4  142.24  5832.2  142.05  5859.3  144.59  5902.8  144.64  6109.6  151.53
#Mann= 6 ,-1 , 0
  3930.5      .1       0  4250.7     .05       0  4365.4     .08       0
  4530.2     .05       0  4901.4    .035       0  4907.4     .05       0
#XS Ineff= 2 , 0
         4440.91  137.24 5158.52          135.48
Permanent Ineff=
       F       F
Bank Sta=4520.3,5004.1
XS Rating Curve= 0 ,0
Exp/Cntr=0.3,0.1

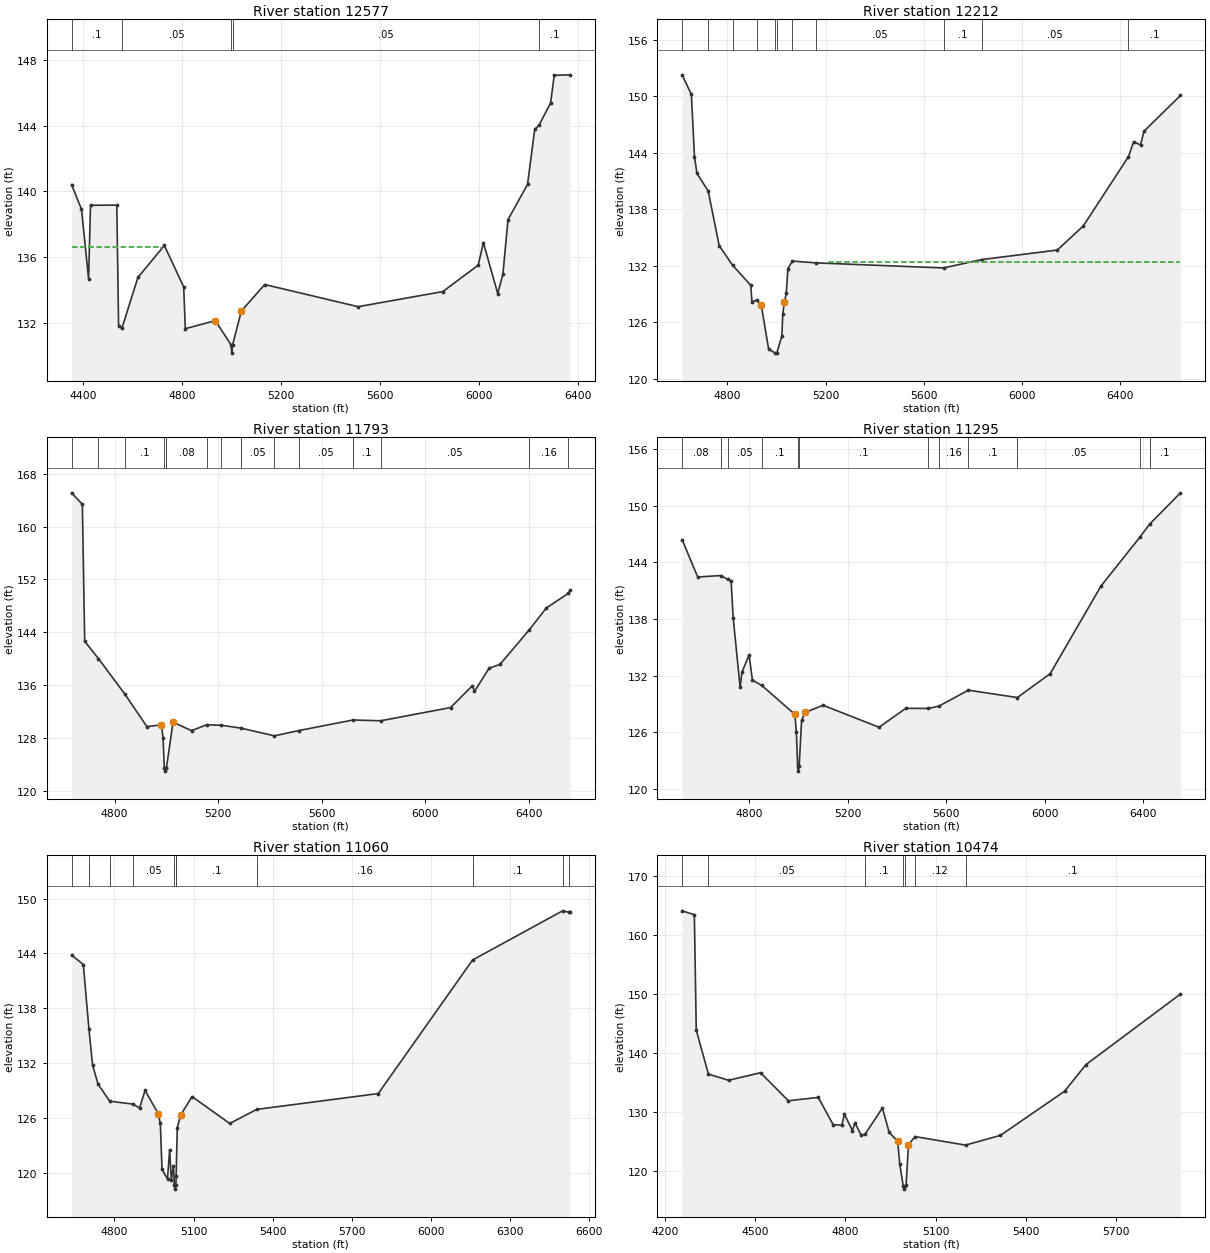
Type RM Length L Ch R = 1 ,12577   ,365,365,365
BEGIN DESCRIPTION:
Mapping XS 56346072
END DESCRIPTION:
XS GIS Cut Line= 4
      2254491.32     13304637.67      2254840.27     13304215.81
      2255001.73     13304132.48      2255788.19     13303116.85
#Sta/Elev= 30
  4354.9  140.41  4394.9  138.91  4423.6  134.67  4431.4  139.15  4537.6  139.16
  4544.8  131.81  4558.1  131.65  4622.9  134.75  4729.7   136.7  4807.9  134.17
  4814.4  131.63  4935.9  132.12  4999.3  130.64  5002.1  130.14  5005.3  130.64
    5041  132.71  5135.1  134.32  5512.6  132.97  5854.9  133.89  5997.9   135.5
  6018.7  136.88  6076.7  133.77  6097.5  134.94  6118.3  138.28  6197.1  140.42
  6226.1  143.77    6243  144.02  6290.4  145.39  6304.9  147.07  6368.6   147.1
#Mann= 5 ,-1 , 0
  4354.9      .1       0  4558.1     .05       0  4999.3     .03       0
  5005.3     .05       0    6243      .1       0
#XS Ineff= 2 , 0
       0 4717.33  136.59 5177.56       0  134.16
Permanent Ineff=
       F       T
Bank Sta=4935.9,5041
XS Rating Curve= 0 ,0
Exp/Cntr=0.3,0.1

Type RM Length L Ch R = 1 ,12212   ,419,419,419
BEGIN DESCRIPTION:
TIMON CREEK 19.0
END DESCRIPTION:
XS GIS Cut Line= 3
      2254937.72     13304846.88      2254987.72     13304446.85
      2256187.71     13303346.87
#Sta/Elev= 30
  4615.2  152.26    4653  150.18  4665.6  143.55  4675.7   141.8  4721.5  139.93
  4766.4  134.12  4820.6  132.06  4894.9  129.92  4899.9  128.17  4919.8  128.35
  4937.7  127.81  4967.9  123.14  4995.2  122.72  5001.2  122.72  5021.7  124.54
  5025.4  126.87  5032.2  128.17  5039.6  129.05  5046.4  131.68  5064.3  132.49
  5160.6   132.3  5680.4  131.76  5835.8  132.65    6144  133.66    6250  136.21
  6434.2  143.58  6455.4  145.15  6483.4  144.82  6497.3  146.27  6646.2  150.07
#Mann= 11 ,-1 , 0
  4615.2      .1       0  4721.5     .05       0  4820.6     .08       0
  4919.8      .1       0  4995.2     .07       0  5001.2      .1       0
  5064.3     .08       0  5160.6     .05       0  5680.4      .1       0
  5835.8     .05       0  6434.2      .1       0
#XS Ineff= 2 , 0
                         5213.07          132.43
Permanent Ineff=
       F       F
Bank Sta=4937.7,5032.2
XS Rating Curve= 0 ,0
Exp/Cntr=0.3,0.1

Type RM Length L Ch R = 1 ,11793   ,498,498,498
BEGIN DESCRIPTION:
TIMON CREEK 18.0
END DESCRIPTION:
XS GIS Cut Line= 3
      2255187.73     13305046.82      2255287.72     13304696.85
      2256487.71     13303696.87
#Sta/Elev= 30
  4633.6  165.11  4675.2  163.37  4684.3  142.64  4737.6  140.01  4839.4  134.65
  4924.8  129.72  4980.7     130  4987.2  127.99    4992  123.49  4994.7  122.99
    4998  123.49  5000.1  123.49  5025.6  130.39  5097.2  129.12  5155.5     130
  5212.9  129.93  5286.6  129.51  5417.6  128.33  5510.7  129.12  5721.2  130.73
  5827.7  130.61  6098.2  132.61  6182.8  135.93  6190.6  135.05  6247.2  138.57
  6289.5  139.15  6402.2  144.37  6467.8  147.67  6552.9  149.88  6559.6  150.35
#Mann= 15 ,-1 , 0
  4633.6      .1       0  4737.6     .05       0  4839.4      .1       0
    4992     .07       0    4998      .1       0  5000.1     .08       0
  5155.5     .05       0  5212.9      .1       0  5286.6     .05       0
  5417.6      .1       0  5510.7     .05       0  5721.2      .1       0
  5827.7     .05       0  6402.2     .16       0  6552.9      .1       0
Bank Sta=4980.7,5025.6
XS Rating Curve= 0 ,0
Exp/Cntr=0.3,0.1

Type RM Length L Ch R = 1 ,11295   ,235,235,235
BEGIN DESCRIPTION:
TIMON CREEK 17.0
END DESCRIPTION:
XS GIS Cut Line= 2
      2255377.14     13305375.57      2256585.91     13303754.03
#Sta/Elev= 30
  4528.2  146.41  4591.5  142.45    4684   142.6  4714.6  142.19    4727  142.04
  4735.4  138.15  4763.6  130.74  4770.8  132.35    4800  134.17  4813.5  131.52
  4851.7  130.95  4985.6  127.89  4991.8  126.07  4997.2  122.37  4999.9  121.87
  5003.2  122.37    5013  127.25  5027.3  128.09  5100.3  128.85  5327.5  126.52
    5436  128.53  5527.2  128.51  5570.2  128.76    5690  130.45  5888.7  129.67
  6021.9   132.2  6228.3   141.5    6385  146.64  6425.8  148.06  6550.7  151.37
#Mann= 12 ,-1 , 0
  4528.2     .08       0    4684      .1       0  4714.6     .05       0
  4851.7      .1       0  4997.2     .07       0  5003.2      .1       0
  5527.2     .05       0  5570.2     .16       0    5690      .1       0
  5888.7     .05       0    6385     .16       0  6425.8      .1       0
#XS Ineff= 2 , 0
                         5707.39          130.35
Permanent Ineff=
       F       F
Bank Sta=4985.6,5027.3
XS Rating Curve= 0 ,0
Exp/Cntr=0.3,0.1

Type RM Length L Ch R = 1 ,11060   ,586,586,586
BEGIN DESCRIPTION:
TIMON CREEK 16.0
END DESCRIPTION:
XS GIS Cut Line= 2
      2255641.51     13305372.03      2256808.14     13303885.96
#Sta/Elev= 30
  4637.6  143.83  4682.1  142.79  4703.4  135.71  4717.3   131.8  4738.1  129.72
    4782  127.87  4868.7  127.55  4895.4  127.13  4916.2  129.04  4965.9  126.51
    4974  125.45  4980.4  120.41  5001.2  119.38  5009.3  122.57  5015.6  119.28
  5023.7   120.8  5027.1  118.76  5029.8  118.26  5033.1  118.76  5033.9  119.73
  5038.2  124.94    5051  126.35  5094.3  128.37  5237.1  125.43  5339.6  126.97
  5800.2   128.7  6157.7  143.29  6499.1  148.66  6521.5  148.52  6526.9  148.56
#Mann= 11 ,-1 , 0
  4637.6      .1       0  4703.4     .05       0    4782      .1       0
  4868.7     .05       0  5027.1    .035       0  5033.1     .05       0
  5033.9      .1       0  5339.6     .16       0  6157.7      .1       0
  6499.1     .16       0  6521.5     .05       0
Bank Sta=4965.9,5051
XS Rating Curve= 0 ,0
Exp/Cntr=0.3,0.1

Type RM Length L Ch R = 1 ,10474   ,452,452,452
BEGIN DESCRIPTION:
TIMON CREEK 15.0
END DESCRIPTION:
XS GIS Cut Line= 2
      2255986.92     13305633.05      2257006.47      13304323.8
#Sta/Elev= 30
    4256  164.17  4296.8  163.51  4303.1  143.96  4343.6  136.49  4410.8  135.45
  4517.3  136.73  4609.8  131.98  4709.3  132.54  4759.1  127.91    4788  127.87
  4796.2  129.69  4823.3  126.93  4831.5  128.24  4852.3  126.12  4865.3  126.32
  4922.9  130.75  4945.5   126.6  4973.6  125.13  4980.8  121.22  4992.2   117.5
    4995     117  4998.2   117.5  5001.6  117.62  5009.7  124.51  5031.3  125.91
  5199.6  124.46  5315.8  126.11    5530  133.61  5600.5   138.1  5915.4  150.07
#Mann= 7 ,-1 , 0
    4256      .1       0  4343.6     .05       0  4865.3      .1       0
  4992.2     .07       0  4998.2      .1       0  5031.3     .12       0
  5199.6      .1       0
#XS Ineff= 2 , 0
         4916.93   130.1
Permanent Ineff=
       F       F
Bank Sta=4973.6,5009.7
XS Rating Curve= 0 ,0
Exp/Cntr=0.3,0.1

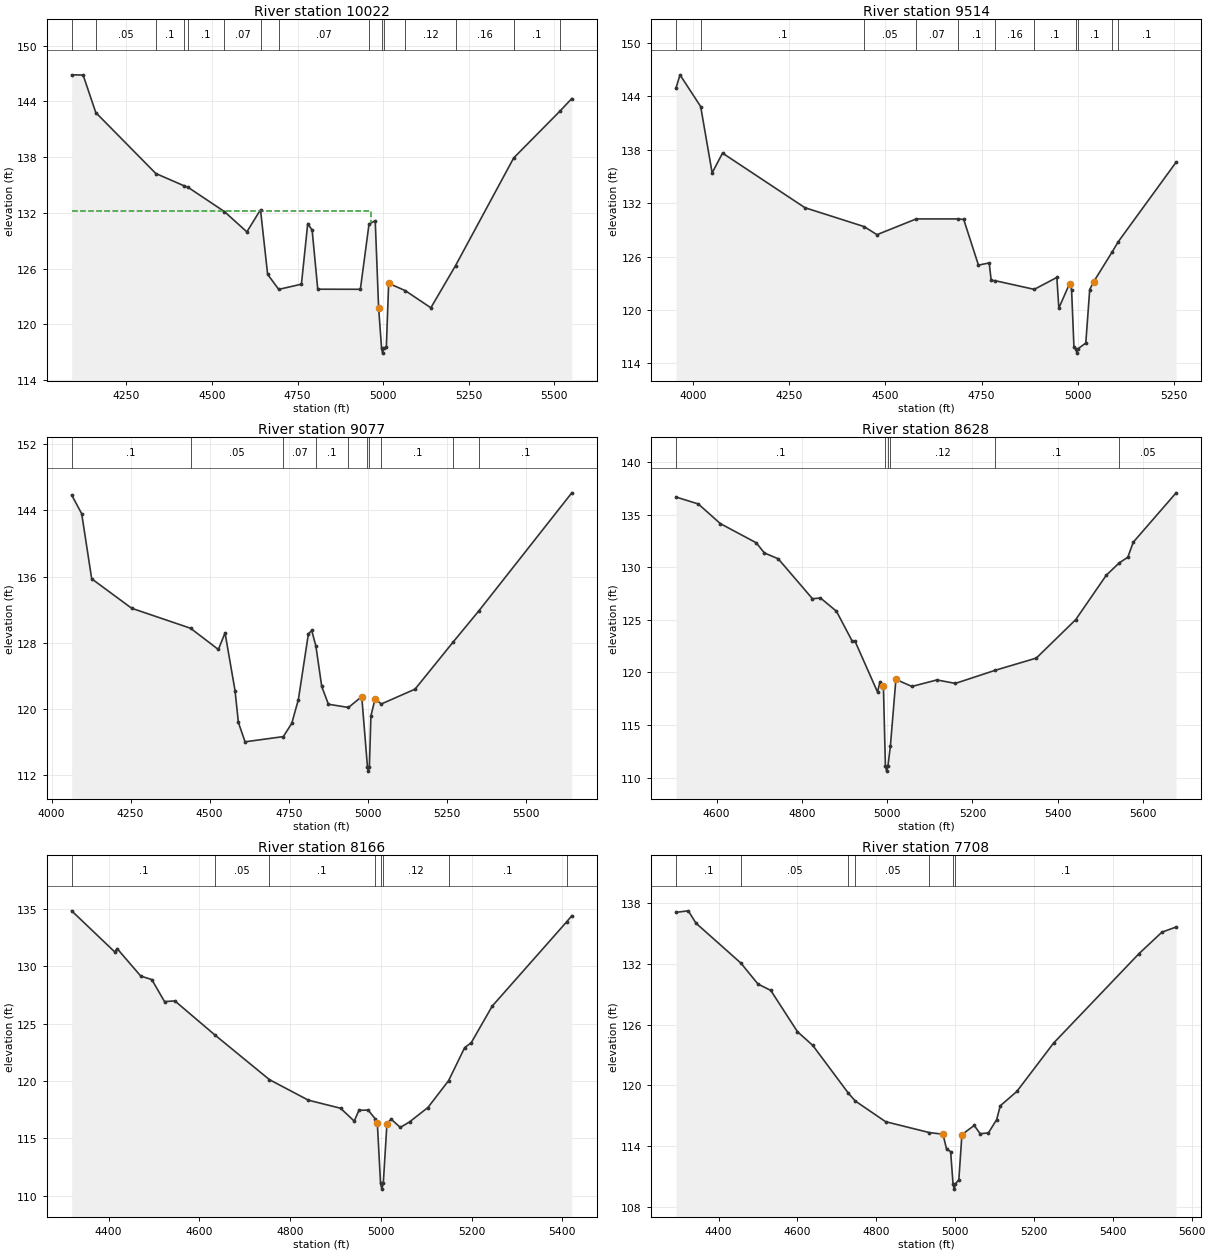
Type RM Length L Ch R = 1 ,10022   ,508,508,508
BEGIN DESCRIPTION:
TIMON CREEK 14.0
END DESCRIPTION:
XS GIS Cut Line= 3
      2256460.49     13305956.19      2256633.19     13305738.93
      2257087.71     13304646.88
#Sta/Elev= 30
  4090.4  146.85  4123.8  146.83  4160.8  142.79  4336.1  136.23  4419.8  134.89
  4430.5  134.74  4536.1  132.14    4602  129.95  4641.8  132.33  4662.6  125.38
    4695  123.76  4761.3  124.32  4779.7  130.84  4792.6  130.14    4809  123.78
  4933.4  123.77  4958.7  130.79  4976.8  131.15  4986.7  121.78  4995.4   117.4
  4998.2   116.9  5001.4   117.4  5009.2  117.51    5016  124.41  5064.3  123.63
  5139.2  121.78  5211.5  126.33  5381.2  137.91  5516.9  142.97  5550.8   144.3
#Mann= 15 ,-1 , 0
  4090.4     .08       0  4160.8     .05       0  4336.1      .1       0
  4419.8     .05       0  4430.5      .1       0  4536.1     .07       0
  4641.8      .1       0    4695     .07       0  4958.7     .05       0
  4995.4    .033       0  5001.4     .05       0  5064.3     .12       0
  5211.5     .16       0  5381.2      .1       0  5516.9     .16       0
#XS Ineff= 2 , 0
         4964.55  132.19
Permanent Ineff=
       F       F
Bank Sta=4986.7,5016
XS Rating Curve= 0 ,0
Exp/Cntr=0.3,0.1

Type RM Length L Ch R = 1 ,9514    ,437,437,437
BEGIN DESCRIPTION:
TIMON CREEK 13.0
END DESCRIPTION:
XS GIS Cut Line= 3
      2257037.73     13306196.84      2257337.72     13305196.85
      2257387.73     13304946.82
#Sta/Elev= 30
  3956.4  144.91  3966.8   146.4  4020.5  142.84  4050.3  135.39  4077.3  137.61
  4291.3  131.48    4445  129.36  4478.4  128.45  4580.4  130.22  4688.7  130.22
  4703.7  130.16    4742  125.03  4769.9  125.28  4775.1  123.31  4784.7  123.29
  4886.9  122.31  4945.6  123.65  4950.8   120.2  4978.7  122.96  4983.9  122.29
    4990  115.86  4994.8  115.65  4997.6  115.15  5000.8  115.65  5020.8  116.28
    5031  122.29  5041.2  123.16  5089.4  126.52  5105.1  127.66  5255.4  136.59
#Mann= 11 ,-1 , 0
  3956.4     .08       0  4020.5      .1       0    4445     .05       0
  4580.4     .07       0  4688.7      .1       0  4784.7     .16       0
  4886.9      .1       0  4994.8     .07       0  5000.8      .1       0
  5089.4     .16       0  5105.1      .1       0
#XS Ineff= 2 , 0
         4945.45  123.55
Permanent Ineff=
       F       F
Bank Sta=4978.7,5041.2
XS Rating Curve= 0 ,0
Exp/Cntr=0.3,0.1

Type RM Length L Ch R = 1 ,9077    ,449,449,449
BEGIN DESCRIPTION:
TIMON CREEK 12.0
END DESCRIPTION:
XS GIS Cut Line= 3
      2257437.71     13306246.88      2257737.72     13305346.85
      2257537.71     13304746.83
#Sta/Elev= 30
  4063.7  145.88  4095.4  143.61    4127  135.73  4253.5  132.16  4439.6  129.74
  4527.5  127.17  4548.6  129.18  4580.2  122.19  4590.8  118.33  4611.9  115.99
  4732.8  116.62  4759.4  118.21  4780.5  121.11  4812.1  129.06  4822.7  129.47
  4835.9  127.57  4854.3  122.69  4875.4  120.54  4938.9  120.15  4980.8  121.47
  4998.9  112.94  5001.6  112.44  5004.9  112.94  5009.8  119.13    5023   121.2
  5042.6  120.57  5149.4  122.37  5270.7  128.12  5351.3  131.86  5644.9  146.14
#Mann= 10 ,-1 , 0
  4063.7      .1       0  4439.6     .05       0  4732.8     .07       0
  4835.9      .1       0  4938.9     .16       0  4998.9     .07       0
  5004.9     .16       0  5042.6      .1       0  5270.7     .16       0
  5351.3      .1       0
#XS Ineff= 2 , 0
         4821.25  128.88
Permanent Ineff=
       F       F
Bank Sta=4980.8,5023
XS Rating Curve= 0 ,0
Exp/Cntr=0.3,0.1

Type RM Length L Ch R = 1 ,8628    ,462,462,462
BEGIN DESCRIPTION:
TIMON CREEK 11.0
END DESCRIPTION:
XS GIS Cut Line= 4
      2258354.78     13305766.83      2258260.05     13305460.36
      2258003.76     13305014.64      2257797.61      13304747.2
#Sta/Elev= 30
    4505   136.7  4557.3  136.04    4609  134.17  4693.4  132.34  4712.1  131.38
  4744.7  130.82    4825  127.02  4843.8  127.09  4881.2  125.83  4918.5  122.96
  4924.3  123.02  4977.5  118.14  4983.2   119.1  4991.3  118.73    4996  111.11
  4998.8  110.61    5002  111.11  5007.6  112.97  5020.6  119.34    5058  118.67
  5116.9  119.29    5160  118.96  5252.8   120.2  5349.8  121.37  5442.2  125.03
  5513.9  129.26  5544.5  130.44  5564.4  130.97  5577.1   132.4  5677.6   137.1
#Mann= 6 ,-1 , 0
    4505      .1       0    4996     .07       0    5002      .1       0
  5007.6     .12       0  5252.8      .1       0  5544.5     .05       0
Bank Sta=4991.3,5020.6
XS Rating Curve= 0 ,0
Exp/Cntr=0.3,0.1

Type RM Length L Ch R = 1 ,8166    ,458,458,458
BEGIN DESCRIPTION:
TIMON CREEK 10.0
END DESCRIPTION:
XS GIS Cut Line= 3
      2258711.34     13305800.26      2258650.05     13305477.07
      2258527.48      13304713.8
#Sta/Elev= 30
  4318.7  134.81  4413.7  131.23  4418.7  131.53    4471  129.13  4495.2  128.83
  4523.3  126.91  4546.1  126.97  4634.2  124.01  4754.4  120.12  4840.3  118.33
  4911.2  117.63  4941.3  116.51  4951.7  117.45    4972  117.47  4987.1  116.73
  4992.2  116.34  4999.3  111.09  5002.1  110.59  5005.3  111.09  5013.4  116.29
  5022.6  116.68  5042.9  115.96  5063.1  116.44  5103.6  117.69  5149.2  120.03
  5184.7  122.91  5199.1  123.33  5245.4  126.52  5409.1  133.84  5420.7  134.38
#Mann= 8 ,-1 , 0
  4318.7      .1       0  4634.2     .05       0  4754.4      .1       0
  4987.1     .12       0  4999.3     .07       0  5005.3     .12       0
  5149.2      .1       0  5409.1     .05       0
Bank Sta=4992.2,5013.4
XS Rating Curve= 0 ,0
Exp/Cntr=0.3,0.1

Type RM Length L Ch R = 1 ,7708    ,492,492,492
BEGIN DESCRIPTION:
TIMON CREEK 9.0
END DESCRIPTION:
XS GIS Cut Line= 3
      2259237.72     13305796.85      2259037.72     13305096.85
      2258737.74     13304646.89
#Sta/Elev= 30
  4291.8   137.1    4323  137.25  4342.5  136.03  4456.5  132.08  4499.8  130.01
  4532.3  129.38  4599.9   125.3  4638.9  123.94  4729.3  119.21  4746.5  118.45
  4823.5   116.4  4934.8  115.32  4969.1  115.16  4978.2  113.69  4988.6  113.44
  4994.7  110.23  4997.5  109.73  5000.7  110.23  5009.4  110.68  5017.2  115.12
  5048.4  116.03  5063.4  115.21  5084.4  115.29  5105.4  116.61  5114.5  117.97
  5156.5  119.39  5249.7  124.17    5466     133  5524.6  135.14  5560.6  135.65
#Mann= 7 ,-1 , 0
  4291.8      .1       0  4456.5     .05       0  4729.3      .1       0
  4746.5     .05       0  4934.8      .1       0  4994.7     .07       0
  5000.7      .1       0
Bank Sta=4969.1,5017.2
XS Rating Curve= 0 ,0
Exp/Cntr=0.3,0.1

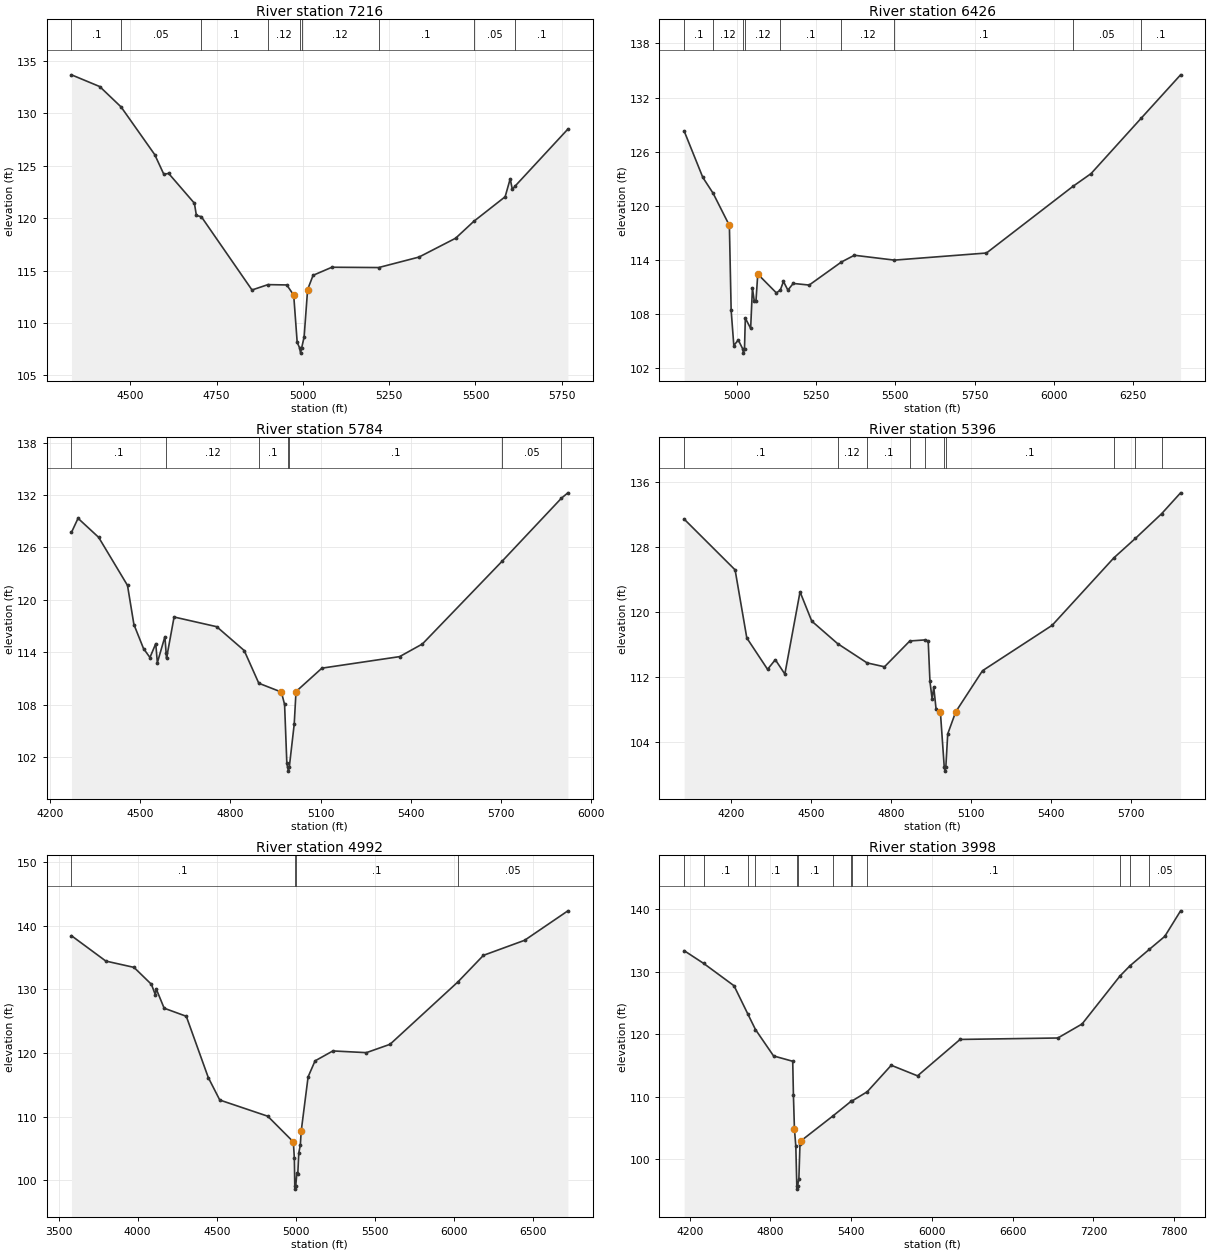
Type RM Length L Ch R = 1 ,7216    ,790,790,790
BEGIN DESCRIPTION:
TIMON CREEK 8.0
END DESCRIPTION:
XS GIS Cut Line= 4
      2259430.07     13305711.04      2259563.76     13305488.22
       2259496.9     13304914.36      2259017.76     13304552.21
#Sta/Elev= 30
  4329.6  133.69  4411.4  132.57  4473.4  130.62  4570.8  126.07  4597.2  124.19
    4611  124.28  4685.7  121.43  4691.5  120.26  4705.7  120.15  4852.6  113.15
  4898.9  113.66  4953.3  113.63  4973.4  112.66  4983.5  108.15  4990.5  107.62
  4993.3  107.12  4996.5  107.62  5003.6  108.67  5013.7  113.19  5029.6  114.55
  5084.1  115.32  5219.5  115.29  5336.3  116.29  5442.5  118.09  5495.1   119.7
    5586  122.05  5600.6  123.76  5606.9  122.75  5615.5  123.09  5767.8  128.51
#Mann= 9 ,-1 , 0
  4329.6      .1       0  4473.4     .05       0  4705.7      .1       0
  4898.9     .12       0  4990.5     .07       0  4996.5     .12       0
  5219.5      .1       0  5495.1     .05       0  5615.5      .1       0
Bank Sta=4973.4,5013.7
XS Rating Curve= 0 ,0
Exp/Cntr=0.3,0.1

Type RM Length L Ch R = 1 ,6426    ,642,642,642
BEGIN DESCRIPTION:
TIMON CREEK 7.0
END DESCRIPTION:
XS GIS Cut Line= 3
      2260237.71     13305146.83      2260137.72     13304946.85
      2258937.74     13304346.86
#Sta/Elev= 30
  4834.3  128.27    4893  123.13  4925.6  121.36  4976.8  117.79  4982.4  108.37
  4990.8  104.45  5004.8  105.07  5018.5  104.11  5021.3  103.61  5024.5  104.11
  5027.1  107.49  5043.9  106.36  5049.5  110.85  5055.1  109.42  5060.7  109.42
  5066.3  112.39    5125   110.3  5137.3  110.61  5147.3  111.57  5161.3  110.61
  5178.1  111.35  5228.4  111.17    5330  113.73  5370.9  114.48    5497  113.94
  5787.4  114.73  6059.6  122.12  6117.2  123.55    6276  129.73  6399.5  134.52
#Mann= 9 ,-1 , 0
  4834.3      .1       0  4925.6     .12       0  5018.5     .07       0
  5024.5     .12       0  5137.3      .1       0    5330     .12       0
    5497      .1       0  6059.6     .05       0    6276      .1       0
Bank Sta=4976.8,5066.3
XS Rating Curve= 0 ,0
Exp/Cntr=0.3,0.1

Type RM Length L Ch R = 1 ,5784    ,388,388,388
BEGIN DESCRIPTION:
TIMON CREEK 6.0
END DESCRIPTION:
XS GIS Cut Line= 2
      2260582.49     13304769.65      2259033.87      13304200.2
#Sta/Elev= 30
  4271.8  127.73  4293.6  129.34  4362.1  127.16    4458  121.65  4479.3  117.17
  4511.3  114.41  4532.6  113.39  4551.9  114.98  4557.2  112.79  4582.3  115.78
  4586.3  113.94  4587.7   113.3  4612.8  118.03  4754.5  116.92  4845.9  114.19
  4894.4  110.44  4969.4  109.43  4980.1  108.01  4987.6  101.28  4989.9  100.87
  4992.7  100.37  4995.9  100.87  5012.1  105.75  5018.1  109.49  5104.2  112.17
  5362.4  113.49  5438.2  114.94  5702.5   124.4  5900.4  131.65  5921.8  132.26
#Mann= 7 ,-1 , 0
  4271.8      .1       0  4586.3     .12       0  4894.4      .1       0
  4989.9     .07       0  4995.9      .1       0  5702.5     .05       0
  5900.4      .1       0
Bank Sta=4969.4,5018.1
XS Rating Curve= 0 ,0
Exp/Cntr=0.3,0.1

Type RM Length L Ch R = 1 ,5396    ,404,404,404
BEGIN DESCRIPTION:
TIMON CREEK 5.0
END DESCRIPTION:
XS GIS Cut Line= 3
      2260674.49     13304697.59      2259887.72     13304146.85
      2258987.73     13304046.86
#Sta/Elev= 30
  4022.2  131.42  4213.6  125.19  4257.6  116.83  4335.6  112.98  4364.8  114.16
  4400.6   112.4  4457.7  122.49  4501.7   118.9  4598.7  116.14  4709.6  113.77
  4775.1  113.29  4870.3  116.46  4927.2  116.59  4939.4  116.47    4946  111.49
  4954.2  109.33  4960.3   110.8  4969.1  108.07  4985.1   107.8  4999.7  100.98
  5002.4  100.48  5005.7  100.98  5012.8  105.05  5042.9  107.76  5143.6  112.81
  5405.2  118.38  5637.4  126.67  5718.4  129.06  5816.9  132.09  5888.1  134.65
#Mann= 10 ,-1 , 0
  4022.2      .1       0  4598.7     .12       0  4709.6      .1       0
  4870.3     .12       0  4927.2      .1       0  4999.7     .07       0
  5005.7      .1       0  5637.4     .05       0  5718.4      .1       0
  5816.9     .05       0
Bank Sta=4985.1,5042.9
XS Rating Curve= 0 ,0
Exp/Cntr=0.3,0.1

Type RM Length L Ch R = 1 ,4992    ,994,994,994
BEGIN DESCRIPTION:
TIMON CREEK 4.0
END DESCRIPTION:
XS GIS Cut Line= 4
      2260857.49     13304757.37      2260649.17     13304194.91
      2259524.17     13303569.91      2258274.12     13303528.24
#Sta/Elev= 30
  3581.9  138.41  3799.1  134.43    3977  133.44    4087  130.78  4112.1  129.13
  4117.4  130.06  4167.6  127.03  4307.5  125.76  4446.5  116.14  4519.1  112.61
  4822.3  110.07  4984.1  106.04  4990.5  103.49  4993.2   99.12  4995.9   98.62
  4999.2   99.12  5006.5  101.17  5012.2  101.01  5018.5  104.31  5028.2  105.51
  5033.9  107.75  5077.4  116.25  5121.4  118.76  5234.1  120.32  5445.7  120.05
  5595.2  121.36  6024.7  131.17  6185.5  135.33  6445.6  137.69  6719.4  142.32
#Mann= 4 ,-1 , 0
  3581.9      .1       0  4993.2     .07       0  4999.2      .1       0
  6024.7     .05       0
Bank Sta=4984.1,5033.9
XS Rating Curve= 0 ,0
Exp/Cntr=0.3,0.1

Type RM Length L Ch R = 1 ,3998    ,0,0,0
BEGIN DESCRIPTION:
TIMON CREEK 1.0
END DESCRIPTION:
XS GIS Cut Line= 4
      2261065.84     13304569.92      2260774.17     13303444.91
      2259503.33     13302965.74      2258336.68     13303028.24
#Sta/Elev= 30
  4159.4  133.38  4304.3  131.34  4529.9  127.77  4632.1  123.27  4689.2  120.77
  4823.7  116.55    4966   115.7  4971.1   110.3  4978.7  104.89    4989   102.1
  4996.3   95.76  4999.1   95.26  5002.3   95.76  5011.7   96.95    5020  102.54
  5030.3  103.03    5263  106.93  5397.8  109.27  5407.4  109.36  5519.7  110.83
    5698  115.06  5893.4  113.37  6209.6  119.19  6935.8  119.42    7116  121.66
  7398.1  129.34  7471.3  130.95  7614.6  133.57  7730.3  135.66  7848.1  139.75
#Mann= 13 ,-1 , 0
  4159.4     .16       0  4304.3      .1       0  4632.1     .16       0
  4689.2      .1       0  4996.3     .07       0  5002.3      .1       0
    5263     .05       0  5397.8      .1       0  5407.4     .05       0
  5519.7      .1       0  7398.1     .05       0  7471.3      .1       0
  7614.6     .05       0
Bank Sta=4978.7,5030.3
XS Rating Curve= 0 ,0
Exp/Cntr=0.3,0.1

Chan Stop Cuts=-1
Use User Specified Reach Order=0
Composite Channel Slope=5