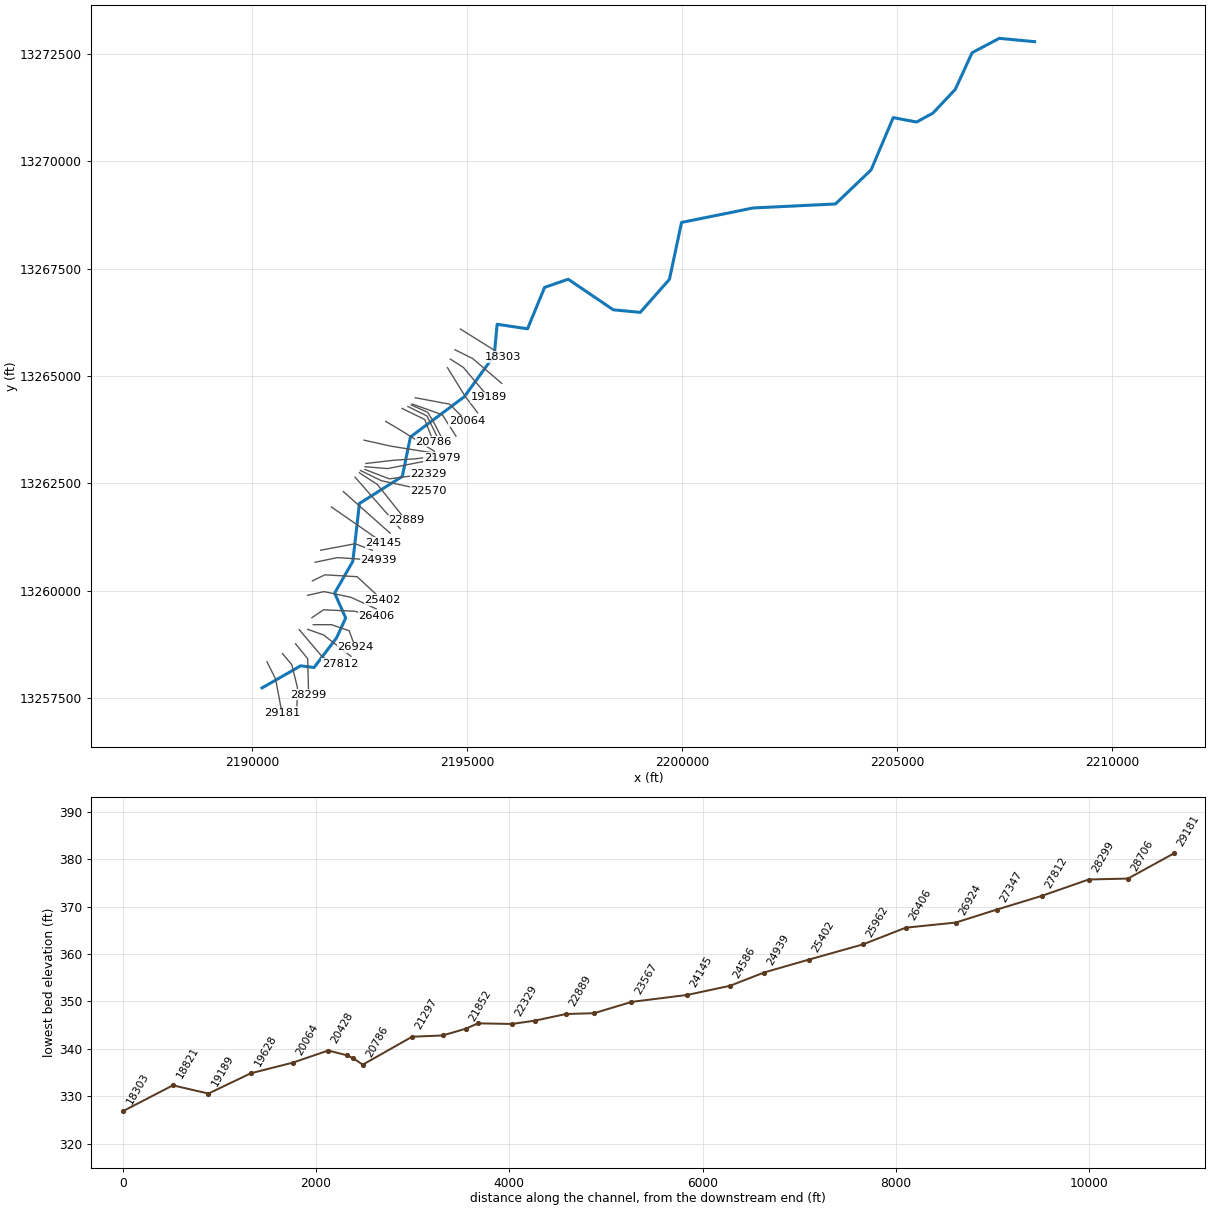
--- UNT001 IN SPCR.prj (project) ---

Proj Title=UNT001 IN SPCR Base Level Engineering
Current Plan=p01
Default Exp/Contr=0.3,0.1
English Units
Geom File=g01
Flow File=f01
Plan File=p01
Y Axis Title=Elevation
X Axis Title(PF)=Main Channel Distance
X Axis Title(XS)=Station
BEGIN DESCRIPTION:
UNT001 IN SPCR
END DESCRIPTION:
DSS Export Rating Curves= 0
DSS Export Rating Curve Sorted= 0
DSS Export Volume Flow Curves= 0
DXF OffsetX= 0
DXF OffsetY= 0
DXF ScaleX= 1
DXF ScaleY= 10

--- UNT001 IN SPCR.p01 (plan) ---

Plan Title=Multiple Run
Short Identifier=Multiple
Geom File=g01
Flow File=f01
Subcritical Flow
K Sum by GR= 0
Std Step Tol= 0.01
Critical Tol= 0.01
Num of Std Step Trials= 20
Max Error Tol= 0.3
Flow Tol Ratio= 0.001
Split Flow NTrial= 30
Split Flow Tol= 0.02
Split Flow Ratio= 0.02
Log Output Level= 0
Friction Slope Method= 1
Unsteady Friction Slope Method= 2
Unsteady Bridges Friction Slope Method= 1
Parabolic Critical Depth
Global Vel Dist=  1 , 1 , 1
Global Log Level= 0
CheckData=True
Encroach Param= -1, 0, 0, 0
BEGIN DESCRIPTION:
Multiple Run
END DESCRIPTION:

--- UNT001 IN SPCR.f01 (steady flow) ---

Flow Title=Multiple
Program Version=4.10
Number of Profiles= 7
Profile Names=10-year,25-year,50-year,1pct_min,100-year,1pct_plu,500-year
River Rch & RM=UNT001 IN SPCR,Reach-1         ,29181
     326     467     587     543     735     993    1170
River Rch & RM=UNT001 IN SPCR,Reach-1         ,24145
     460     668     850     794    1074    1452    1743
River Rch & RM=UNT001 IN SPCR,Reach-1         ,23567
     460     668     850     794    1074    1452    1743
River Rch & RM=UNT001 IN SPCR,Reach-1         ,21979
     543     795    1015     952    1287    1741    2103
River Rch & RM=UNT001 IN SPCR,Reach-1         ,19189
     567     828    1055     987    1335    1805    2171
River Rch & RM=UNT001 IN SPCR,Reach-1         ,14064
     778    1150    1478    1393    1883    2547    3109
River Rch & RM=UNT001 IN SPCR,Reach-1         ,13204
     778    1150    1478    1393    1883    2547    3109
River Rch & RM=UNT001 IN SPCR,Reach-1         ,11065
    1024    1528    1974    1870    2529    3420    4218
River Rch & RM=UNT001 IN SPCR,Reach-1         ,10644
    1024    1528    1974    1870    2529    3420    4218
River Rch & RM=UNT001 IN SPCR,Reach-1         ,5834
    1037    1542    1990    1881    2544    3441    4226
Boundary for River Rch & Prof#=UNT001 IN SPCR,Reach-1         , 1
Up Type= 0
Dn Type= 3
Dn Slope=0.005
Boundary for River Rch & Prof#=UNT001 IN SPCR,Reach-1         , 2
Up Type= 0
Dn Type= 3
Dn Slope=0.005
Boundary for River Rch & Prof#=UNT001 IN SPCR,Reach-1         , 3
Up Type= 0
Dn Type= 3
Dn Slope=0.005
Boundary for River Rch & Prof#=UNT001 IN SPCR,Reach-1         , 4
Up Type= 0
Dn Type= 3
Dn Slope=0.005
Boundary for River Rch & Prof#=UNT001 IN SPCR,Reach-1         , 5
Up Type= 0
Dn Type= 3
Dn Slope=0.005
Boundary for River Rch & Prof#=UNT001 IN SPCR,Reach-1         , 6
Up Type= 0
Dn Type= 3
Dn Slope=0.005
Boundary for River Rch & Prof#=UNT001 IN SPCR,Reach-1         , 7
Up Type= 0
Dn Type= 3
Dn Slope=0.005
DSS Import GetInterval= 0
DSS Import GetPeak= 0
DSS Import FillOption= 0

--- UNT001 IN SPCR.g01 (geometry) ---

Geom Title=Existing Conditions
Program Version=4.10

River Reach=UNT001 IN SPCR  ,Reach-1
Reach XY= 30
      2190222.29     13257739.59        2191119.     13258253.96
      2191433.67     13258216.04      2191957.42     13258907.21
      2192168.66     13259369.77      2191911.41     13259946.26
      2192334.78     13260688.07      2192488.96      13262035.2
      2193485.74     13262664.35      2193675.39     13263583.23
      2194929.49     13264520.76      2195625.73     13265482.68
      2195693.28     13266207.68      2196400.29     13266102.18
      2196797.72     13267066.85      2197346.76     13267256.63
      2198396.89     13266544.38      2199023.45     13266485.02
      2199702.97     13267254.11      2199984.79     13268578.81
      2201648.19     13268915.72      2203566.73     13269009.25
      2204395.52     13269801.88      2204911.39     13271020.18
      2205452.41     13270917.31       2205834.2      13271124.4
      2206355.23     13271677.88      2206746.18     13272530.92
      2207378.26     13272866.05      2208202.05      13272788.2

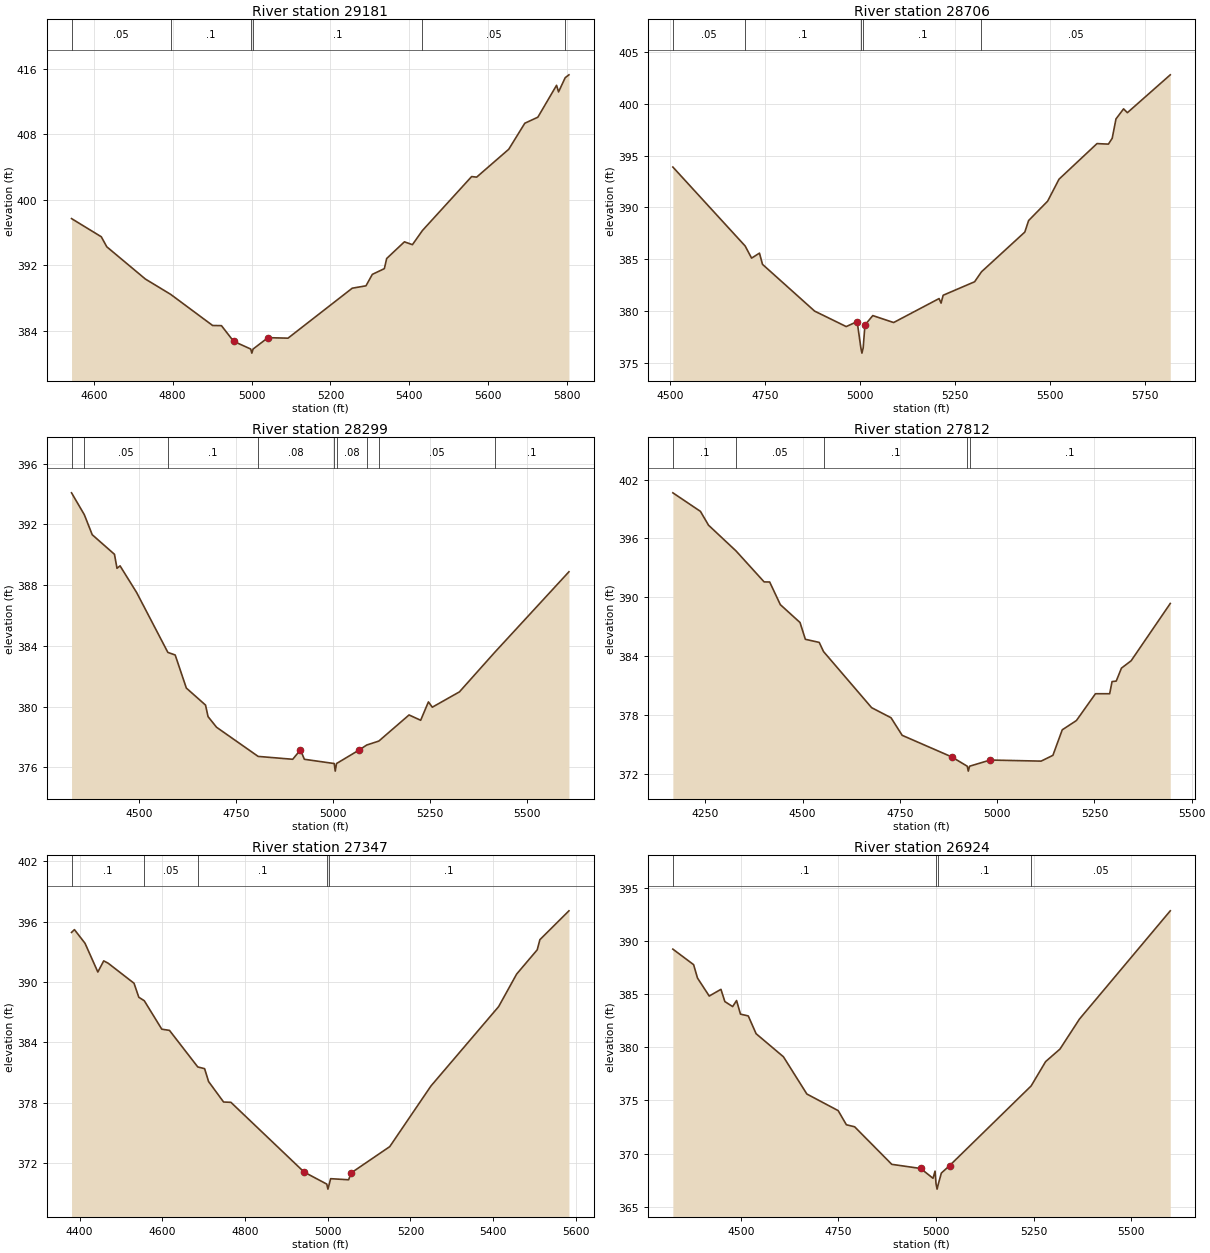
Type RM Length L Ch R = 1 ,29181   ,475,475,475
BEGIN DESCRIPTION:
UNT001 IN SPCR 55.0
END DESCRIPTION:
XS GIS Cut Line= 3
      2190337.74     13258346.81      2190537.72     13257946.85
      2190687.72     13257146.86
#Sta/Elev= 30
  4543.7  397.71  4619.1  395.49  4633.1  394.26  4730.9  390.32  4795.2  388.44
  4901.4  384.64  4923.8  384.62  4954.5  382.71    4998  381.76  5000.8  381.26
    5004  381.76  5041.7  383.15  5092.6  383.09  5255.4   389.2  5290.2  389.49
  5306.3  390.89  5336.8  391.59  5342.7  392.83  5387.7  394.87    5408  394.52
  5433.3  396.25  5558.1  402.85  5570.8  402.78  5652.2  406.19  5692.9  409.37
    5726  410.11  5773.4  414.01  5778.5   413.2  5795.3  414.94  5804.8  415.29
#Mann= 6 ,-1 , 0
  4543.7     .05       0  4795.2      .1       0    4998     .07       0
    5004      .1       0  5433.3     .05       0  5795.3      .1       0
Bank Sta=4954.5,5041.7
XS Rating Curve= 0 ,0
Exp/Cntr=0.3,0.1

Type RM Length L Ch R = 1 ,28706   ,407,407,407
BEGIN DESCRIPTION:
UNT001 IN SPCR 54.0
END DESCRIPTION:
XS GIS Cut Line= 4
      2190698.48      13258539.3      2190915.47     13258278.92
      2191045.68     13257747.24      2191034.83     13257324.02
#Sta/Elev= 30
  4506.8  393.89  4697.1  386.28  4714.1  385.11  4734.9  385.59  4742.8  384.51
  4880.1     380  4963.3  378.51    4992  378.99  5001.9  376.45  5004.6  375.95
  5007.9  376.45  5012.6  378.66  5033.2  379.57  5088.1   378.9  5207.8  381.21
    5213  380.77  5218.5  381.53  5301.3  382.83  5319.4  383.79  5433.5  387.62
  5443.5  388.73  5493.6   390.6  5523.6  392.72  5623.6  396.15  5653.6   396.1
  5663.6  396.66  5673.6  398.53  5693.6   399.5  5703.6  399.13  5816.5  402.78
#Mann= 5 ,-1 , 0
  4506.8     .05       0  4697.1      .1       0  5001.9     .07       0
  5007.9      .1       0  5319.4     .05       0
Bank Sta=4992,5012.6
XS Rating Curve= 0 ,0
Exp/Cntr=0.3,0.1

Type RM Length L Ch R = 1 ,28299   ,487,487,487
BEGIN DESCRIPTION:
UNT001 IN SPCR 53.0
END DESCRIPTION:
XS GIS Cut Line= 3
      2191002.27     13258767.21      2191284.39     13258419.98
       2191306.1     13257584.45
#Sta/Elev= 30
  4325.3  394.08  4358.3  392.64  4378.7  391.32  4436.1  390.03  4442.6  389.11
  4450.5  389.27  4493.3  387.51  4573.8  383.57  4592.7   383.4  4621.5  381.22
    4671   380.1  4677.5  379.34  4699.4  378.64  4806.7  376.72  4895.9  376.53
  4915.9  377.15  4925.9  376.53  5002.9  376.25  5005.6  375.75  5008.9  376.25
  5065.9  377.12  5086.9  377.47  5118.1  377.73    5196  379.45    5226   379.1
    5246  380.31    5256  379.96    5326  380.97  5416.9  383.57  5608.5  388.88
#Mann= 9 ,-1 , 0
  4325.3      .1       0  4358.3     .05       0  4573.8      .1       0
  4806.7     .08       0  5002.9     .07       0  5008.9     .08       0
  5086.9      .1       0  5118.1     .05       0  5416.9      .1       0
Bank Sta=4915.9,5065.9
XS Rating Curve= 0 ,0
Exp/Cntr=0.3,0.1

Type RM Length L Ch R = 1 ,27812   ,465,465,465
BEGIN DESCRIPTION:
UNT001 IN SPCR 52.0
END DESCRIPTION:
XS GIS Cut Line= 3
      2191087.72     13259096.85      2191637.72     13258446.85
      2192037.75     13258296.84
#Sta/Elev= 30
  4166.3  400.65  4237.2  398.76    4258  397.35  4328.6  394.73  4400.9  391.57
  4415.2  391.56  4442.6  389.25  4493.2  387.43  4506.9  385.72  4542.6   385.4
  4553.6  384.47  4677.2  378.75  4727.2  377.72  4755.8  375.93  4883.2  373.73
  4923.1  372.78  4925.8  372.28  4929.1  372.78    4982  373.41    5113   373.3
  5143.3  373.89  5167.3  376.49  5203.8  377.44  5252.7  380.17  5289.2  380.17
  5295.4  381.41  5306.1  381.46  5319.5  382.78  5344.4  383.53    5445  389.37
#Mann= 5 ,-1 , 0
  4166.3      .1       0  4328.6     .05       0  4553.6      .1       0
  4923.1     .07       0  4929.1      .1       0
Bank Sta=4883.2,4982
XS Rating Curve= 0 ,0
Exp/Cntr=0.3,0.1

Type RM Length L Ch R = 1 ,27347   ,423,423,423
BEGIN DESCRIPTION:
UNT001 IN SPCR 51.0
END DESCRIPTION:
XS GIS Cut Line= 3
      2191284.38     13259103.58      2191653.32     13258973.37
       2192293.1     13258474.55
#Sta/Elev= 30
  4380.7  394.94  4387.7  395.22  4413.3  393.86  4444.3     391  4458.5  392.11
  4469.1  391.88  4531.8  389.88  4543.3  388.49  4556.6  388.14  4598.9  385.31
  4617.5  385.19  4685.9  381.55  4702.4  381.38    4712   380.1  4748.3  378.06
    4766  378.03  4942.9  371.09  4997.8  369.89  5000.5  369.39  5003.8  369.89
  5007.1  370.43  5050.5  370.32  5056.9  371.01    5150  373.62  5249.5  379.65
  5413.3  387.56  5456.7  390.79  5506.5  393.21    5513  394.22  5583.2  397.09
#Mann= 5 ,-1 , 0
  4380.7      .1       0  4556.6     .05       0  4685.9      .1       0
  4997.8     .07       0  5003.8      .1       0
Bank Sta=4942.9,5056.9
XS Rating Curve= 0 ,0
Exp/Cntr=0.3,0.1

Type RM Length L Ch R = 1 ,26924   ,518,518,518
BEGIN DESCRIPTION:
UNT001 IN SPCR 50.0
END DESCRIPTION:
XS GIS Cut Line= 4
      2191414.59     13259212.08      2191837.78     13259212.08
      2192250.11     13259071.02       2192390.9     13258681.14
#Sta/Elev= 30
  4326.2  389.22  4379.3  387.76  4389.3   386.5  4419.3  384.81  4449.3  385.44
  4459.3  384.29  4479.3  383.82  4489.3  384.39  4499.3  383.11  4519.3  382.94
  4539.3  381.27  4609.3   379.1  4669.3   375.6  4749.4  374.04  4770.5  372.71
  4791.6  372.52  4886.7  368.99  4960.7   368.6  4992.2  367.68  4997.5  368.35
    5000  367.16  5002.7  366.66    5006  367.16  5013.6  368.17  5034.7  368.87
  5243.5  376.36  5280.6  378.65  5317.2  379.82  5367.3  382.65  5599.7  392.82
#Mann= 4 ,-1 , 0
  4326.2      .1       0    5000     .07       0    5006      .1       0
  5243.5     .05       0
Bank Sta=4960.7,5034.7
XS Rating Curve= 0 ,0
Exp/Cntr=0.3,0.1

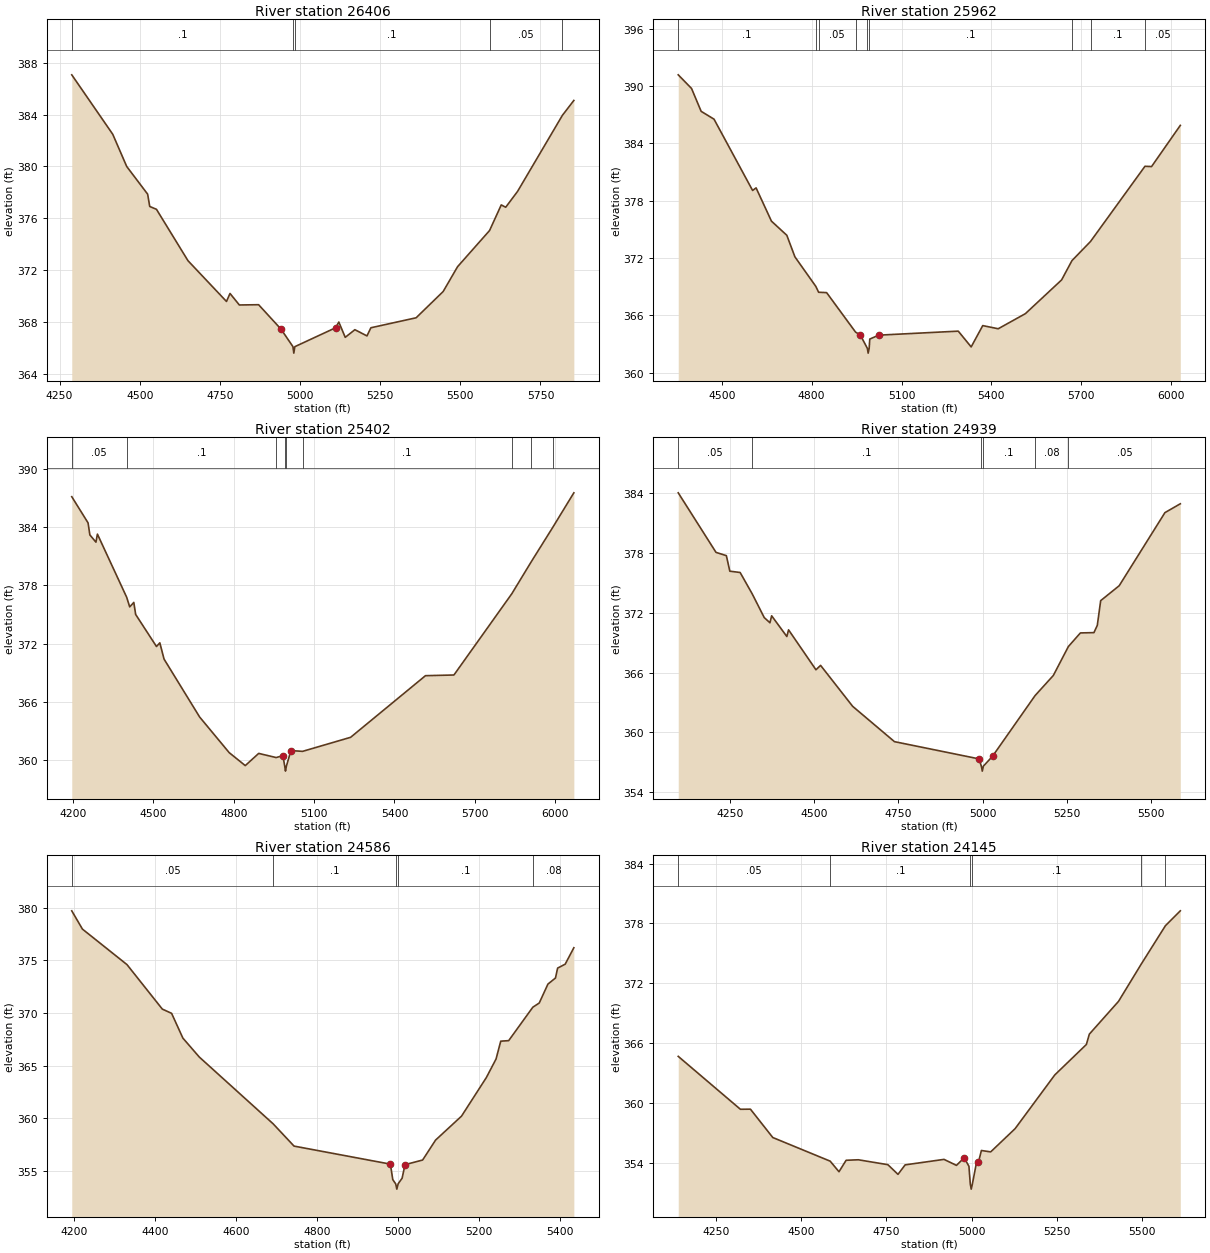
Type RM Length L Ch R = 1 ,26406   ,444,444,444
BEGIN DESCRIPTION:
UNT001 IN SPCR 49.0
END DESCRIPTION:
XS GIS Cut Line= 4
      2191382.02     13259374.82      2191653.32      13259559.3
      2192358.61     13259526.75       2192879.4     13259418.25
#Sta/Elev= 30
  4288.1  387.08  4415.9  382.49  4459.5     380  4524.8  377.86  4531.3  376.91
  4552.3  376.69  4650.6  372.72  4770.7  369.57  4781.7  370.19  4810.8   369.3
  4870.9  369.32  4940.9  367.43    4978  366.08  4980.7  365.58    4984  366.08
  5111.1  367.54  5121.1  367.98  5141.1   366.8  5171.2  367.39  5208.9  366.91
  5221.2  367.54  5362.2  368.31  5446.6  370.34  5491.6  372.26  5591.3  375.05
  5627.8  377.03  5641.7  376.85  5678.8  378.08  5818.5  383.95  5854.2   385.1
#Mann= 5 ,-1 , 0
  4288.1      .1       0    4978     .07       0    4984      .1       0
  5591.3     .05       0  5818.5      .1       0
Bank Sta=4940.9,5111.1
XS Rating Curve= 0 ,0
Exp/Cntr=0.3,0.1

Type RM Length L Ch R = 1 ,25962   ,560,560,560
BEGIN DESCRIPTION:
UNT001 IN SPCR 48.0
END DESCRIPTION:
XS GIS Cut Line= 4
      2191284.36     13259895.67      2191664.17     13259982.48
      2192282.66     13259852.27      2192878.54     13259581.42
#Sta/Elev= 30
  4354.6  391.16  4399.1  389.73  4431.1  387.34  4474.1  386.52  4602.9  379.06
  4614.5  379.33  4665.8  375.85  4717.1  374.37  4744.2  372.11  4813.8  369.03
  4823.3  368.41    4850  368.37  4946.6  364.24  4962.4  363.94    4986  362.54
  4988.7  362.04    4992  362.54  4994.1  363.51  5023.8  363.92  5289.5  364.34
  5332.6  362.69  5371.2  364.92  5422.9  364.59  5513.6  366.17  5634.5   369.7
  5669.1  371.72    5731  373.72  5912.8  381.59  5934.8  381.56  6030.8  385.87
#Mann= 9 ,-1 , 0
  4354.6      .1       0  4813.8     .08       0  4823.3     .05       0
  4946.6      .1       0    4986     .07       0    4992      .1       0
  5669.1     .05       0    5731      .1       0  5912.8     .05       0
Bank Sta=4962.4,5023.8
XS Rating Curve= 0 ,0
Exp/Cntr=0.3,0.1

Type RM Length L Ch R = 1 ,25402   ,463,463,463
BEGIN DESCRIPTION:
UNT001 IN SPCR 47.0
END DESCRIPTION:
XS GIS Cut Line= 4
      2191392.91     13260232.05      2191685.87     13260373.11
      2192434.57      13260329.7      2193020.47      13259787.2
#Sta/Elev= 30
  4195.7  387.15  4256.5  384.45  4263.2  383.21  4285.9  382.46  4291.4  383.29
  4400.5  376.78  4411.9  375.78  4427.2  376.24  4434.1     375  4511.8  371.69
  4524.3  372.07  4540.1  370.39    4673  364.41  4783.1  360.74  4843.2   359.4
  4893.3  360.66  4958.5  360.23  4983.5  360.43  4990.5  359.33  4993.2  358.83
  4996.5  359.33  5013.5  360.95    5057  360.87  5236.3  362.32  5515.7  368.68
  5621.8  368.75  5837.9  377.14  5910.9  380.46  5989.8  383.95  6069.3  387.55
#Mann= 9 ,-1 , 0
  4195.7     .05       0  4400.5      .1       0  4958.5     .05       0
  4990.5     .04       0  4996.5     .05       0    5057      .1       0
  5837.9     .05       0  5910.9      .1       0  5989.8     .05       0
Bank Sta=4983.5,5013.5
XS Rating Curve= 0 ,0
Exp/Cntr=0.3,0.1

Type RM Length L Ch R = 1 ,24939   ,353,353,353
BEGIN DESCRIPTION:
UNT001 IN SPCR 46.0
END DESCRIPTION:
XS GIS Cut Line= 3
      2191458.04     13260666.08      2191978.84     13260774.58
      2192933.25     13260709.51
#Sta/Elev= 30
  4097.5  384.06  4209.5  378.08  4240.2  377.75  4250.4  376.19    4281  376.06
  4316.9  373.91  4352.5  371.53  4369.4  371.01  4374.5  371.71  4419.5  369.63
  4424.6   370.3  4505.8  366.29  4519.6  366.73  4614.6  362.62  4738.6  359.07
  4989.2  357.34  4996.2  356.61    4999  356.11  5002.2  356.61  5029.3   357.6
  5155.6   363.7  5209.7  365.72  5254.2  368.62  5289.9  369.99    5330  370.02
    5340  370.75    5350  373.23  5404.9  374.73  5540.5  382.07  5586.1  382.96
#Mann= 6 ,-1 , 0
  4097.5     .05       0  4316.9      .1       0  4996.2     .07       0
  5002.2      .1       0  5155.6     .08       0  5254.2     .05       0
Bank Sta=4989.2,5029.3
XS Rating Curve= 0 ,0
Exp/Cntr=0.3,0.1

Type RM Length L Ch R = 1 ,24586   ,441,441,441
BEGIN DESCRIPTION:
UNT001 IN SPCR 45.0
END DESCRIPTION:
XS GIS Cut Line= 3
      2191587.68     13260946.85      2192387.72     13261096.85
      2192787.73     13260946.85
#Sta/Elev= 30
  4193.7  379.69    4220  377.96  4330.2  374.59  4417.6  370.37  4440.5  369.97
  4468.4  367.62  4509.1  365.82  4691.6  359.49  4743.2  357.38  4981.4  355.67
  4987.3   354.2  4994.5   353.8  4997.3   353.3  5000.5   353.8  5010.4  354.34
  5017.5  355.62  5061.1  356.06  5093.1  357.95  5157.2  360.22  5218.6  363.88
  5242.6  365.64  5254.2  367.33  5273.8  367.38  5333.5  370.55  5349.4  370.95
  5370.8  372.74  5389.5  373.32  5394.8  374.26  5413.5  374.63  5434.9  376.19
#Mann= 5 ,-1 , 0
  4193.7     .05       0  4691.6      .1       0  4994.5     .07       0
  5000.5      .1       0  5333.5     .08       0
Bank Sta=4981.4,5017.5
XS Rating Curve= 0 ,0
Exp/Cntr=0.3,0.1

Type RM Length L Ch R = 1 ,24145   ,578,578,578
BEGIN DESCRIPTION:
UNT001 IN SPCR 44.0
END DESCRIPTION:
XS GIS Cut Line= 2
      2191838.11     13261951.86      2193046.45     13261113.31
#Sta/Elev= 30
  4140.4  364.68  4322.5  359.38  4351.9  359.39  4417.4  356.55  4585.6  354.18
  4611.3  353.12  4632.2  354.27    4668  354.32  4754.5  353.83  4784.2  352.86
  4805.1  353.81  4918.9  354.36  4955.5  353.76    4978  354.52    4992  353.67
    4996  351.88  4998.7  351.38    5002  351.88  5013.8  353.98  5019.9  354.08
  5028.5  355.25  5055.7  355.11  5127.3  357.44  5243.5  362.82    5336  365.87
  5344.8  366.91  5430.2  370.19  5496.5  373.91  5567.6  377.77  5611.2  379.26
#Mann= 6 ,-1 , 0
  4140.4     .05       0  4585.6      .1       0    4996     .07       0
    5002      .1       0  5496.5     .08       0  5567.6      .1       0
#XS Ineff= 1 ,-1
 4562.05 4662.74  354.31
Permanent Ineff=
       F
Bank Sta=4978,5019.9
XS Rating Curve= 0 ,0
Exp/Cntr=0.3,0.1

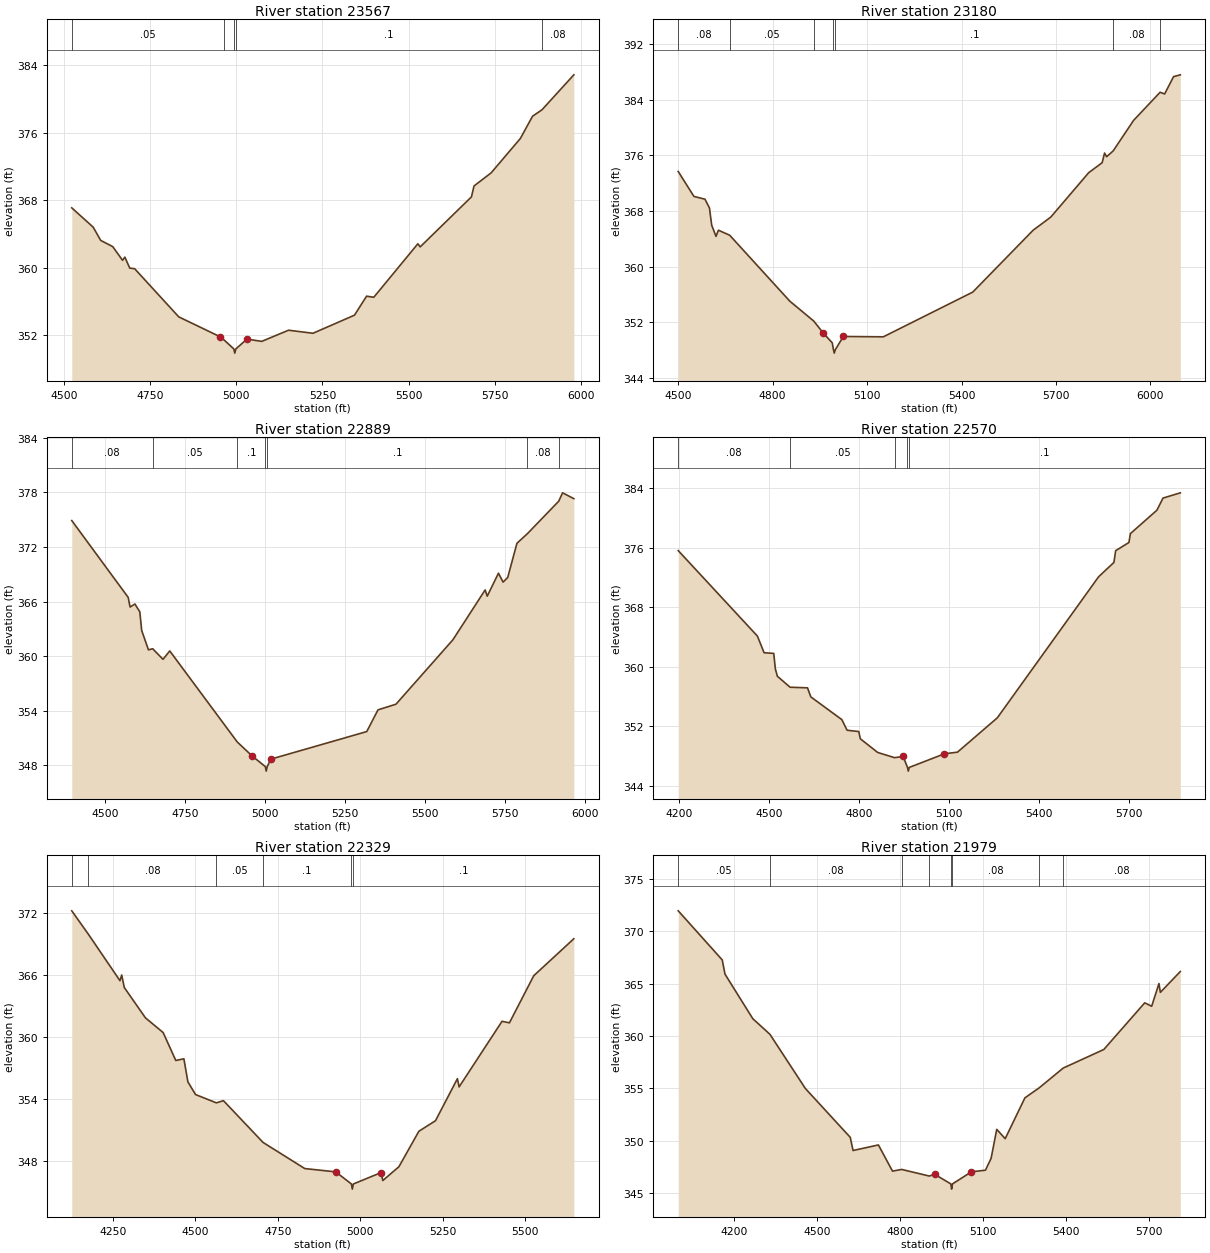
Type RM Length L Ch R = 1 ,23567   ,387,387,387
BEGIN DESCRIPTION:
UNT001 IN SPCR 43.0
END DESCRIPTION:
XS GIS Cut Line= 2
      2192114.14     13262311.24      2193202.69     13261342.48
#Sta/Elev= 30
  4522.3  367.09  4584.4  364.81  4606.2  363.24  4641.3   362.5  4669.7  360.88
  4676.4  361.26  4690.6  359.96  4704.8  359.89  4832.8  354.19  4953.2  351.83
    4963  351.51  4992.6   350.4  4995.4   349.9  4998.6   350.4  5030.9  351.56
  5073.6  351.29  5151.4  352.61  5222.4  352.25  5342.8  354.39    5378  356.64
  5398.9  356.51  5526.8  362.84  5533.5  362.47  5682.3  368.39  5689.8  369.68
  5739.2  371.22  5824.5  375.31  5859.6  377.93    5887  378.69  5979.5  382.83
#Mann= 5 ,-1 , 0
  4522.3     .05       0    4963      .1       0  4992.6     .07       0
  4998.6      .1       0    5887     .08       0
Bank Sta=4953.2,5030.9
XS Rating Curve= 0 ,0
Exp/Cntr=0.3,0.1

Type RM Length L Ch R = 1 ,23180   ,291,291,291
BEGIN DESCRIPTION:
UNT001 IN SPCR 42.0
END DESCRIPTION:
XS GIS Cut Line= 3
      2192387.74     13262646.83      2192737.72     13262246.85
      2193437.72     13261446.85
#Sta/Elev= 30
  4500.3  373.69  4550.1   370.1  4585.2   369.7  4599.5  368.43  4606.6  365.95
  4620.3  364.34  4627.9  365.23  4663.7  364.51  4854.8     355  4930.7  352.14
  4961.1   350.4  4989.5     349  4993.2  348.02  4995.9  347.52  4999.2  348.02
  5024.7  349.92  5151.8  349.87  5435.6  356.31  5627.4  365.23  5683.4  367.12
  5803.9  373.52  5846.6  374.96  5854.2  376.35  5860.8  375.82  5881.6  376.66
  5946.3  381.05  6030.7  385.11    6045  384.86  6073.4  387.36  6094.8  387.62
#Mann= 7 ,-1 , 0
  4500.3     .08       0  4663.7     .05       0  4930.7      .1       0
  4993.2     .07       0  4999.2      .1       0  5881.6     .08       0
  6030.7      .1       0
Bank Sta=4961.1,5024.7
XS Rating Curve= 0 ,0
Exp/Cntr=0.3,0.1

Type RM Length L Ch R = 1 ,22889   ,319,319,319
BEGIN DESCRIPTION:
Mapping XS a9a7feac
END DESCRIPTION:
XS GIS Cut Line= 3
      2192486.83     13262749.05      2192905.96     13262477.49
      2193571.84     13261640.72
#Sta/Elev= 30
  4396.3  374.91  4572.6  366.46  4578.5   365.4  4593.7  365.73  4608.9  364.87
  4614.8  362.82  4635.9  360.69  4649.1  360.81  4681.4  359.65  4702.5  360.57
  4913.5  350.55  4960.8  348.99    5001  347.85  5003.8  347.35    5007  347.85
  5018.5  348.67    5318   351.7  5353.2  354.09  5409.3  354.71  5587.1  361.79
    5688  367.28  5694.4  366.59  5729.6  369.12    5744  368.14  5758.5  368.65
  5787.3  372.41  5820.1  373.47  5917.9  377.04  5929.9  377.96  5965.1  377.32
#Mann= 7 ,-1 , 0
  4396.3     .08       0  4649.1     .05       0  4913.5      .1       0
    5001     .07       0    5007      .1       0  5820.1     .08       0
  5917.9      .1       0
Bank Sta=4960.8,5018.5
XS Rating Curve= 0 ,0
Exp/Cntr=0.3,0.1

Type RM Length L Ch R = 1 ,22570   ,241,241,241
BEGIN DESCRIPTION:
Mapping XS 5dfc348b
END DESCRIPTION:
XS GIS Cut Line= 3
      2192510.55     13262803.65       2192998.8     13262564.95
       2194104.1     13262326.55
#Sta/Elev= 30
  4197.5   375.6  4461.5  364.11  4483.8  361.87    4516  361.78  4521.5  359.66
  4528.3   358.7  4570.5  357.23  4628.5  357.15  4639.7  355.93    4743  352.88
  4760.5  351.45  4799.6  351.27  4804.7   350.3  4862.6  348.46  4918.9  347.76
  4947.5  347.92  4961.9  346.45  4964.7  345.95  4967.9  346.45  5085.1  348.28
  5128.6   348.5  5261.6  353.12  5599.2  372.08  5650.3  374.01  5656.1  375.59
  5700.3  376.69  5705.4  377.89  5793.6  381.03    5814  382.66  5871.7  383.37
#Mann= 5 ,-1 , 0
  4197.5     .08       0  4570.5     .05       0  4918.9      .1       0
  4961.9     .07       0  4967.9      .1       0
Bank Sta=4947.5,5085.1
XS Rating Curve= 0 ,0
Exp/Cntr=0.3,0.1

Type RM Length L Ch R = 1 ,22329   ,350,350,350
BEGIN DESCRIPTION:
Mapping XS 47fca5ed
END DESCRIPTION:
XS GIS Cut Line= 3
      2192618.99     13262825.38      2193183.27     13262608.35
      2194093.72     13262727.57
#Sta/Elev= 30
    4125  372.18  4175.7   369.9  4271.2  365.42  4276.5  365.97  4284.3  364.76
  4348.6  361.82  4402.2   360.4  4440.5   357.7  4465.1  357.86  4477.2  355.63
  4500.5   354.4  4563.5   353.6  4585.1  353.81  4705.1  349.77  4831.7  347.24
  4925.7  346.92  4973.1  345.75  4975.9  345.25  4979.1  345.75  5063.2  346.85
  5068.3  346.08  5117.3  347.42  5177.8  350.85  5228.2  351.87  5294.7  355.94
  5299.8  355.14    5430  361.49  5452.4  361.34  5526.2   365.9  5647.8  369.48
#Mann= 6 ,-1 , 0
    4125     .05       0  4175.7     .08       0  4563.5     .05       0
  4705.1      .1       0  4973.1     .07       0  4979.1      .1       0
Bank Sta=4925.7,5063.2
XS Rating Curve= 0 ,0
Exp/Cntr=0.3,0.1

Type RM Length L Ch R = 1 ,21979   ,127,127,127
BEGIN DESCRIPTION:
Mapping XS 6edfa7e2
END DESCRIPTION:
XS GIS Cut Line= 3
      2192619.07     13262890.46      2193139.86     13262847.06
      2194409.37     13263096.62
#Sta/Elev= 30
  3998.4  371.97  4157.6  367.28  4167.6  365.92    4268  361.67  4330.2  360.17
  4458.5  354.99  4620.7  350.33  4630.9  349.07  4722.6   349.6  4773.6   347.1
    4807  347.26  4906.5  346.63  4926.5  346.79  4984.6  345.88  4987.4  345.38
  4990.6  345.88    5059  347.03  5109.9  347.19  5130.3  348.32  5150.7  351.09
  5181.3   350.2  5252.6   354.1  5304.4  355.06  5391.4  356.95    5538  358.72
  5686.1  363.18  5711.2  362.85  5737.5  365.02  5742.6  364.18  5814.8  366.17
#Mann= 8 ,-1 , 0
  3998.4     .05       0  4330.2     .08       0    4807      .1       0
  4906.5     .08       0  4984.6     .07       0  4990.6     .08       0
  5304.4      .1       0  5391.4     .08       0
Bank Sta=4926.5,5059
XS Rating Curve= 0 ,0
Exp/Cntr=0.3,0.1

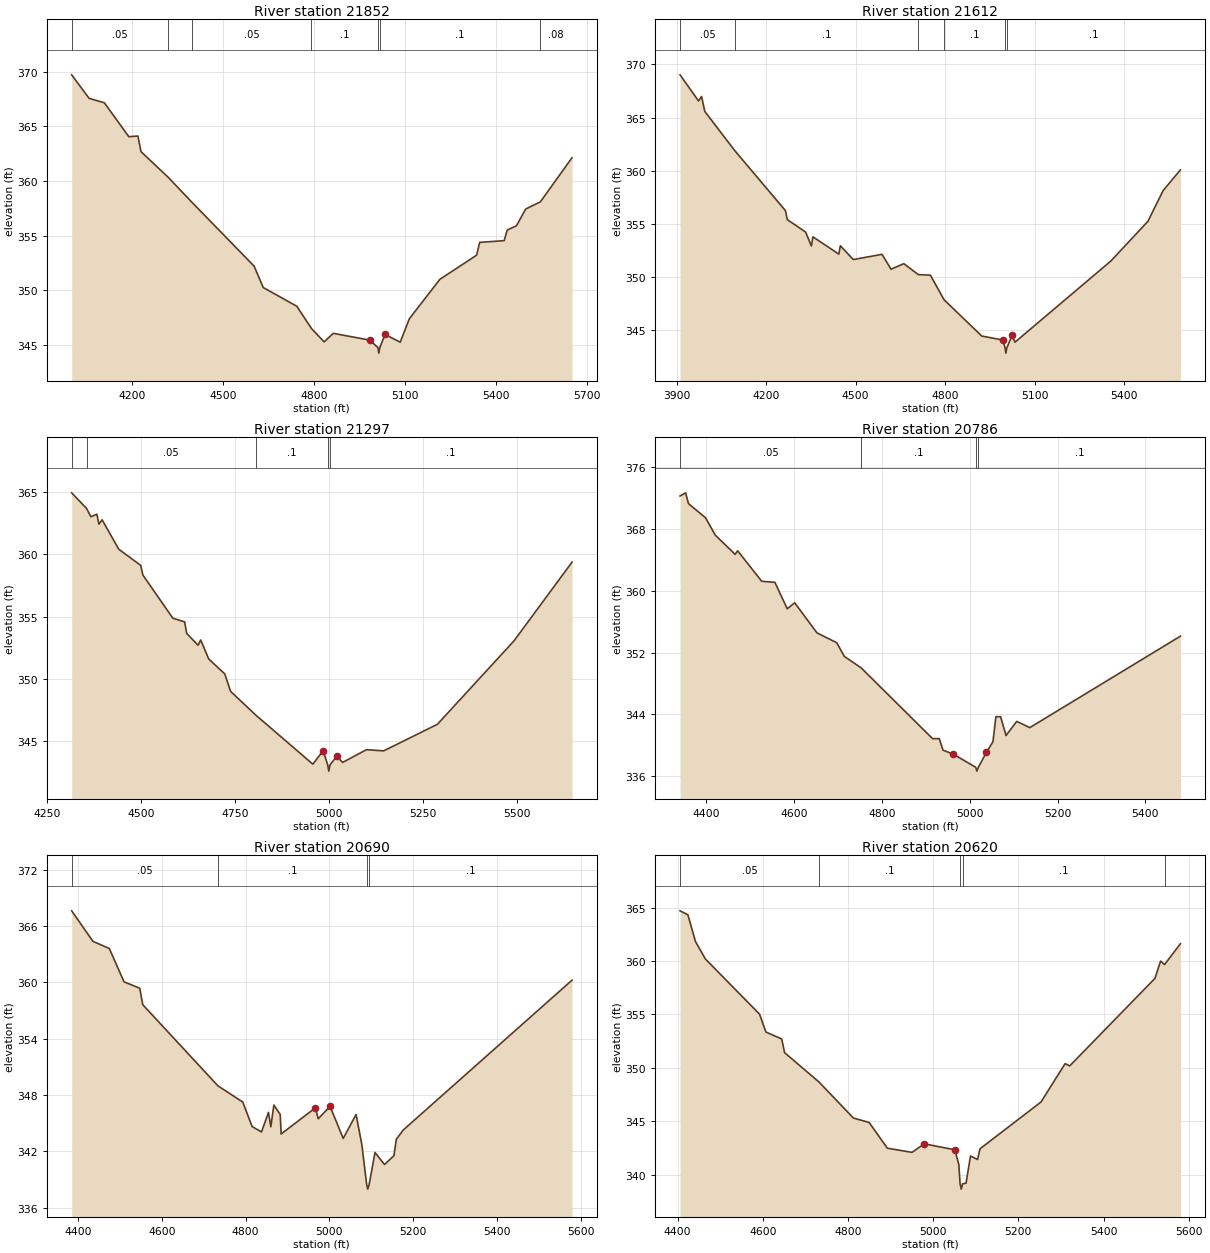
Type RM Length L Ch R = 1 ,21852   ,240,240,240
BEGIN DESCRIPTION:
Mapping XS df2068ec
END DESCRIPTION:
XS GIS Cut Line= 4
      2192640.77     13262966.43      2193302.62     13263042.38
      2193801.75     13263074.93      2194279.14     13263140.03
#Sta/Elev= 30
  4002.3   369.7  4059.6  367.55    4110  367.14  4190.5  364.04  4220.5   364.1
  4230.7  362.67  4319.7  360.34  4398.1  358.05  4603.2   352.2  4633.4  350.24
  4743.8  348.53  4792.2  346.49  4833.9  345.27    4864  346.05  4984.3  345.43
  5011.3  344.74  5014.1  344.24  5017.3  344.74  5034.4  345.95  5084.5  345.24
  5114.5  347.38    5215  350.99  5336.2   353.2  5346.3  354.37    5427  354.53
    5437   355.5  5467.4  355.89  5497.7  357.42  5546.2  358.08  5650.5  362.12
#Mann= 7 ,-1 , 0
  4002.3     .05       0  4319.7      .1       0  4398.1     .05       0
  4792.2      .1       0  5011.3     .07       0  5017.3      .1       0
  5546.2     .08       0
Bank Sta=4984.3,5034.4
XS Rating Curve= 0 ,0
Exp/Cntr=0.3,0.1

Type RM Length L Ch R = 1 ,21612   ,315,315,315
BEGIN DESCRIPTION:
Mapping XS a23436fc
END DESCRIPTION:
XS GIS Cut Line= 3
      2192597.36     13263508.95      2193226.67      13263367.9
      2194244.67     13263205.45
#Sta/Elev= 30
  3911.8  369.02  3973.7  366.56  3983.9  366.98  3994.6  365.58  4095.5  361.87
    4265  356.23  4270.9  355.39  4332.3  354.22  4351.7  352.91  4356.8  353.77
  4443.6  352.14  4448.7  352.93    4492  351.63  4588.2  352.12  4618.5  350.72
  4661.3  351.24  4710.1  350.21  4750.2  350.16  4796.2  347.84  4922.3  344.43
  4993.2  344.05  5000.4  343.32  5003.1  342.82  5006.4  343.32  5023.6  344.49
  5033.7  343.85  5354.6  351.49  5478.9  355.23  5529.9  358.13  5587.6  360.07
#Mann= 6 ,-1 , 0
  3911.8     .05       0  4095.5      .1       0  4710.1     .05       0
  4796.2      .1       0  5000.4     .07       0  5006.4      .1       0
Bank Sta=4993.2,5023.6
XS Rating Curve= 0 ,0
Exp/Cntr=0.3,0.1

Type RM Length L Ch R = 1 ,21297   ,511,511,511
BEGIN DESCRIPTION:
UNT001 IN SPCR 38.0
END DESCRIPTION:
XS GIS Cut Line= 3
      2193098.02     13263947.63      2193429.48     13263751.21
      2194233.63     13263249.89
#Sta/Elev= 30
  4314.8  364.96  4354.4   363.7  4366.1  363.03  4381.7  363.24  4387.5  362.44
  4395.8  362.79  4440.2  360.42  4498.6  359.12  4504.5  358.34  4584.4  354.86
  4615.6  354.57  4621.4  353.63  4651.5  352.69  4658.5  353.11  4679.9  351.58
  4722.6  350.38    4738  348.98  4805.3  347.06  4957.3  343.11  4984.6   344.2
  4996.9  343.05  4999.7  342.55  5002.9  343.05  5021.1  343.75  5036.5  343.25
  5100.2  344.28  5145.8  344.18    5289  346.32  5493.1  353.04  5647.7  359.38
#Mann= 5 ,-1 , 0
  4314.8      .1       0  4354.4     .05       0  4805.3      .1       0
  4996.9     .07       0  5002.9      .1       0
Bank Sta=4984.6,5021.1
XS Rating Curve= 0 ,0
Exp/Cntr=0.3,0.1

Type RM Length L Ch R = 1 ,20786   ,96,96,96
BEGIN DESCRIPTION:
Mapping XS 5b483869
END DESCRIPTION:
XS GIS Cut Line= 3
      2193480.45     13264247.01       2194006.5      13263991.8
      2194209.63     13263476.15
#Sta/Elev= 30
  4340.7  372.27  4353.4  372.68  4359.9  371.28  4398.6  369.46  4421.1  367.19
  4466.3  364.71  4471.8  365.18  4526.6  361.23  4556.6  361.09  4584.7  357.67
  4601.7  358.44  4652.4  354.55  4697.5  353.27  4714.5  351.51  4753.1  350.01
  4915.6  340.85  4930.7  340.86  4939.2  339.37  4962.9  338.84  5013.7  337.15
  5016.4  336.65  5019.7  337.15  5038.2  339.09  5052.9  340.45  5059.7   343.7
  5070.4  343.69  5082.7  341.26  5107.1  343.09  5136.8  342.28  5479.6  354.12
#Mann= 4 ,-1 , 0
  4340.7     .05       0  4753.1      .1       0  5013.7     .07       0
  5019.7      .1       0
Bank Sta=4962.9,5038.2
XS Rating Curve= 0 ,0
Exp/Cntr=0.3,0.1

Type RM Length L Ch R = 1 ,20690   ,70,70,70
BEGIN DESCRIPTION:
Mapping XS 9ccab76c
END DESCRIPTION:
XS GIS Cut Line= 3
      2193615.91     13264293.87      2194063.79     13264069.93
      2194365.86     13263444.95
#Sta/Elev= 30
  4384.5   367.6  4435.3  364.35  4474.4  363.59  4509.5  360.04  4547.1  359.36
  4554.2  357.61  4733.7  348.97  4793.1  347.24  4815.4  344.63  4837.8  344.06
  4854.5  346.14  4860.1  344.61  4867.3  346.92  4882.5  345.92  4884.7  343.84
  4966.4  346.62  4973.3  345.46  5001.5  346.78    5033  343.37  5063.7  345.92
  5077.5  342.69  5088.9  338.47  5091.6  337.97  5094.9  338.47  5108.9  341.87
  5131.5  340.59  5154.1  341.53  5159.7  343.27  5176.7  344.28  5579.4  360.22
#Mann= 4 ,-1 , 0
  4384.5     .05       0  4733.7      .1       0  5088.9     .07       0
  5094.9      .1       0
Bank Sta=4966.4,5001.5
XS Rating Curve= 0 ,0
Exp/Cntr=0.3,0.1

Type RM Length L Ch R = 1 ,20620   ,192,192,192
BEGIN DESCRIPTION:
Mapping XS fb8ab67f
END DESCRIPTION:
XS GIS Cut Line= 4
      2193693.44     13264328.21      2194076.06     13264158.39
      2194209.06     13263943.54      2194438.23     13263495.43
#Sta/Elev= 30
  4405.9  364.69  4424.3  364.32  4442.1  361.82  4465.3  360.19  4592.6  355.02
  4607.5  353.35  4644.6   352.7  4651.3  351.42  4731.9  348.68  4812.9   345.3
  4849.8  344.89  4892.6  342.48  4950.5  342.09  4979.2  342.89  5050.9  342.33
  5060.4  340.95  5063.3  339.15    5066  338.65  5069.3  339.15  5077.2   339.2
  5087.8  341.75  5104.4  341.42    5110  342.42  5253.2   346.8  5309.9  350.39
  5320.6  350.18  5520.8  358.37    5534  359.99  5543.3  359.66  5580.5  361.61
#Mann= 5 ,-1 , 0
  4405.9     .05       0  4731.9      .1       0  5063.3     .07       0
  5069.3      .1       0  5543.3     .05       0
Bank Sta=4979.2,5050.9
XS Rating Curve= 0 ,0
Exp/Cntr=0.3,0.1

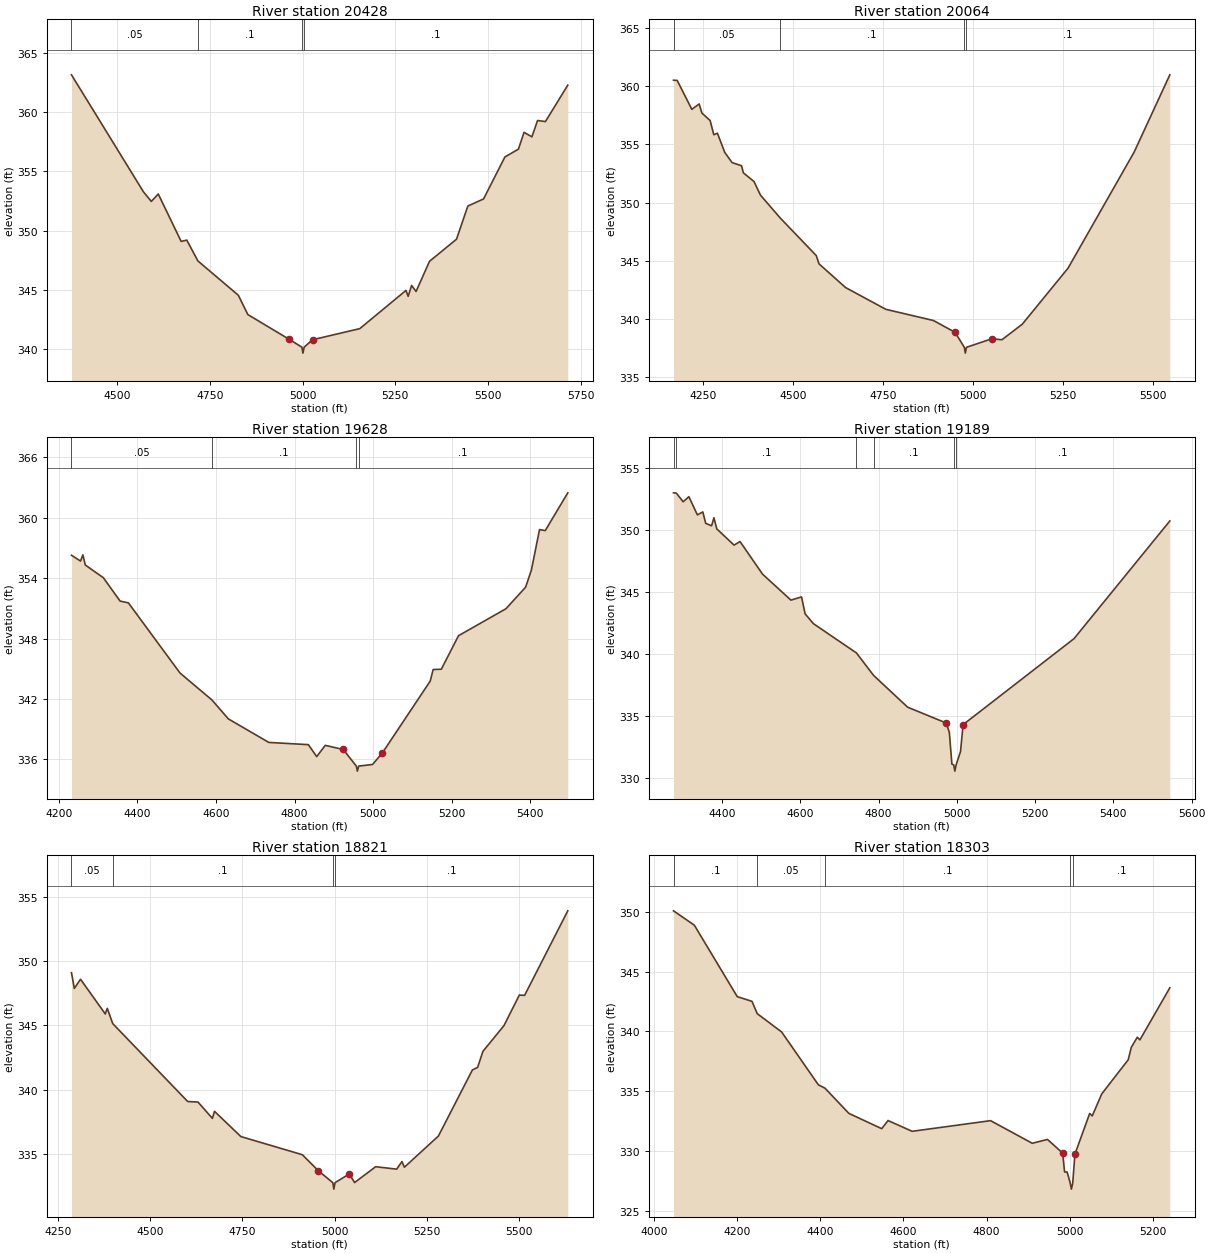
Type RM Length L Ch R = 1 ,20428   ,364,364,364
BEGIN DESCRIPTION:
Mapping XS 3680476f
END DESCRIPTION:
XS GIS Cut Line= 3
      2193714.83     13264351.18      2194417.96     13264101.18
      2194735.42     13263601.56
#Sta/Elev= 30
  4376.9  363.16    4571  353.27  4592.2  352.46  4610.9  353.09  4672.6  349.08
  4687.8  349.19  4717.8  347.43  4826.8  344.53  4852.4   342.9  4963.7  340.81
  4998.3  340.14    5001  339.64  5004.3  340.14  5026.8  340.77  5154.3  341.71
  5278.8  344.94  5284.7  344.44    5294  345.36    5306  344.85  5342.3   347.4
  5415.1  349.27  5445.6  352.07    5488  352.67  5545.6  356.22    5582  356.88
  5597.2   358.3  5618.4  357.92  5633.6   359.3  5654.8  359.21  5715.1  362.29
#Mann= 4 ,-1 , 0
  4376.9     .05       0  4717.8      .1       0  4998.3     .07       0
  5004.3      .1       0
Bank Sta=4963.7,5026.8
XS Rating Curve= 0 ,0
Exp/Cntr=0.3,0.1

Type RM Length L Ch R = 1 ,20064   ,436,436,436
BEGIN DESCRIPTION:
UNT001 IN SPCR 35.0
END DESCRIPTION:
XS GIS Cut Line= 3
      2193787.68     13264496.86      2194587.72     13264346.85
      2194987.74     13263946.83
#Sta/Elev= 30
  4168.2  360.51  4178.4  360.49  4219.1  358.01  4239.5  358.47  4247.1  357.69
    4270  357.05  4280.2  355.83  4290.3  355.96  4310.7  354.31    4331  353.44
  4357.3  353.17  4362.4  352.56  4392.1  351.81  4409.9  350.65  4464.7  348.69
    4565  345.46  4572.7  344.75  4646.4  342.72  4758.3  340.85  4890.6  339.89
  4950.8  338.88  4976.6  337.59  4979.4  337.09  4982.6  337.59  5052.9  338.32
  5081.2  338.24  5137.7  339.57    5265  344.38  5448.9  354.35  5547.9  360.97
#Mann= 4 ,-1 , 0
  4168.2     .05       0  4464.7      .1       0  4976.6     .07       0
  4982.6      .1       0
Bank Sta=4950.8,5052.9
XS Rating Curve= 0 ,0
Exp/Cntr=0.3,0.1

Type RM Length L Ch R = 1 ,19628   ,439,439,439
BEGIN DESCRIPTION:
UNT001 IN SPCR 34.0
END DESCRIPTION:
XS GIS Cut Line= 3
      2194537.72     13265196.86      2194937.72     13264546.85
      2195237.71     13264146.87
#Sta/Elev= 30
  4232.3  356.28  4255.4   355.7  4261.3  356.32  4267.5  355.31  4313.4  354.05
    4356  351.73  4377.2  351.55  4508.6  344.58    4590   341.9  4631.5  340.03
  4734.6  337.69  4835.2  337.47  4856.5  336.28  4878.1   337.4    4924  336.99
  4957.3  335.34    4960  334.84  4963.3  335.34  4998.6   335.5  5023.6  336.65
  5145.5  343.79  5152.8  344.93  5173.6  344.96  5217.4  348.29  5338.2  350.97
  5388.2  353.11  5402.8   354.8  5423.6  358.83  5438.2  358.73  5495.5  362.48
#Mann= 4 ,-1 , 0
  4232.3     .05       0    4590      .1       0  4957.3     .07       0
  4963.3      .1       0
Bank Sta=4924,5023.6
XS Rating Curve= 0 ,0
Exp/Cntr=0.3,0.1

Type RM Length L Ch R = 1 ,19189   ,368,368,368
BEGIN DESCRIPTION:
UNT001 IN SPCR 33.0
END DESCRIPTION:
XS GIS Cut Line= 3
       2194604.7     13265396.98      2194908.53     13265201.66
      2195493.62     13264508.21
#Sta/Elev= 30
  4275.7  353.01  4282.8  352.99  4300.4  352.29    4315   352.7  4336.7  351.23
  4350.6  351.47  4357.9  350.55    4373  350.35    4379     351  4386.3   350.1
  4430.5  348.79  4445.7  349.08  4503.2  346.45  4575.8  344.35  4602.9  344.61
  4612.1  343.24  4633.3  342.45  4743.2  340.09  4786.9  338.28  4874.1  335.71
  4972.9  334.43  4980.7  333.67  4987.2  331.12    4992  331.05  4994.7  330.55
    4998  331.05  5009.3  332.14  5015.8   334.3  5299.3  341.24  5544.2  350.74
#Mann= 6 ,-1 , 0
  4275.7     .05       0  4282.8      .1       0  4743.2     .05       0
  4786.9      .1       0    4992     .07       0    4998      .1       0
Bank Sta=4972.9,5015.8
XS Rating Curve= 0 ,0
Exp/Cntr=0.3,0.1

Type RM Length L Ch R = 1 ,18821   ,518,518,518
BEGIN DESCRIPTION:
UNT001 IN SPCR 32.0
END DESCRIPTION:
XS GIS Cut Line= 3
      2194713.21     13265613.99      2195125.54     13265407.83
      2195798.25     13264832.77
#Sta/Elev= 30
  4286.2  349.09  4293.9  347.87  4310.7  348.58  4377.8  345.89  4383.4  346.32
    4398  345.14  4601.4  339.09  4629.3  339.05  4668.4  337.78    4674  338.33
  4745.6  336.37  4912.4  334.96  4955.2  333.73    4995  332.79  4997.8  332.29
    5001  332.79  5039.7  333.47    5054   332.8  5111.1  334.03  5168.2  333.84
  5182.5  334.43    5189  333.99  5281.3  336.41  5373.5  341.54  5387.7  341.74
    5402  342.98  5459.1  344.98  5500.8  347.35  5515.1  347.33  5632.2  353.89
#Mann= 4 ,-1 , 0
  4286.2     .05       0    4398      .1       0    4995     .07       0
    5001      .1       0
Bank Sta=4955.2,5039.7
XS Rating Curve= 0 ,0
Exp/Cntr=0.3,0.1

Type RM Length L Ch R = 1 ,18303   ,465,465,465
BEGIN DESCRIPTION:
UNT001 IN SPCR 31.0
END DESCRIPTION:
XS GIS Cut Line= 3
      2194837.74     13266096.84      2195637.72     13265596.85
      2195837.74     13265446.84
#Sta/Elev= 30
  4047.4  350.07  4097.5  348.87  4200.7   342.9  4236.1  342.51  4248.7  341.48
  4307.4  339.95  4395.8  335.53  4411.4  335.26    4469  333.15    4548  331.87
  4563.3  332.55  4621.1  331.65  4809.8  332.54    4910  330.65  4946.6  330.97
  4983.1  329.83  4987.8  328.25  4993.9  328.25  5001.3  327.32  5004.1  326.82
  5007.3  327.32  5012.6  329.74  5048.1  333.14  5054.3  332.94  5077.2  334.78
  5140.8  337.63  5148.1  338.66  5162.6  339.51  5168.9  339.29  5240.8  343.64
#Mann= 5 ,-1 , 0
  4047.4      .1       0  4248.7     .05       0  4411.4      .1       0
  5001.3     .07       0  5007.3      .1       0
Bank Sta=4983.1,5012.6
XS Rating Curve= 0 ,0
Exp/Cntr=0.3,0.1