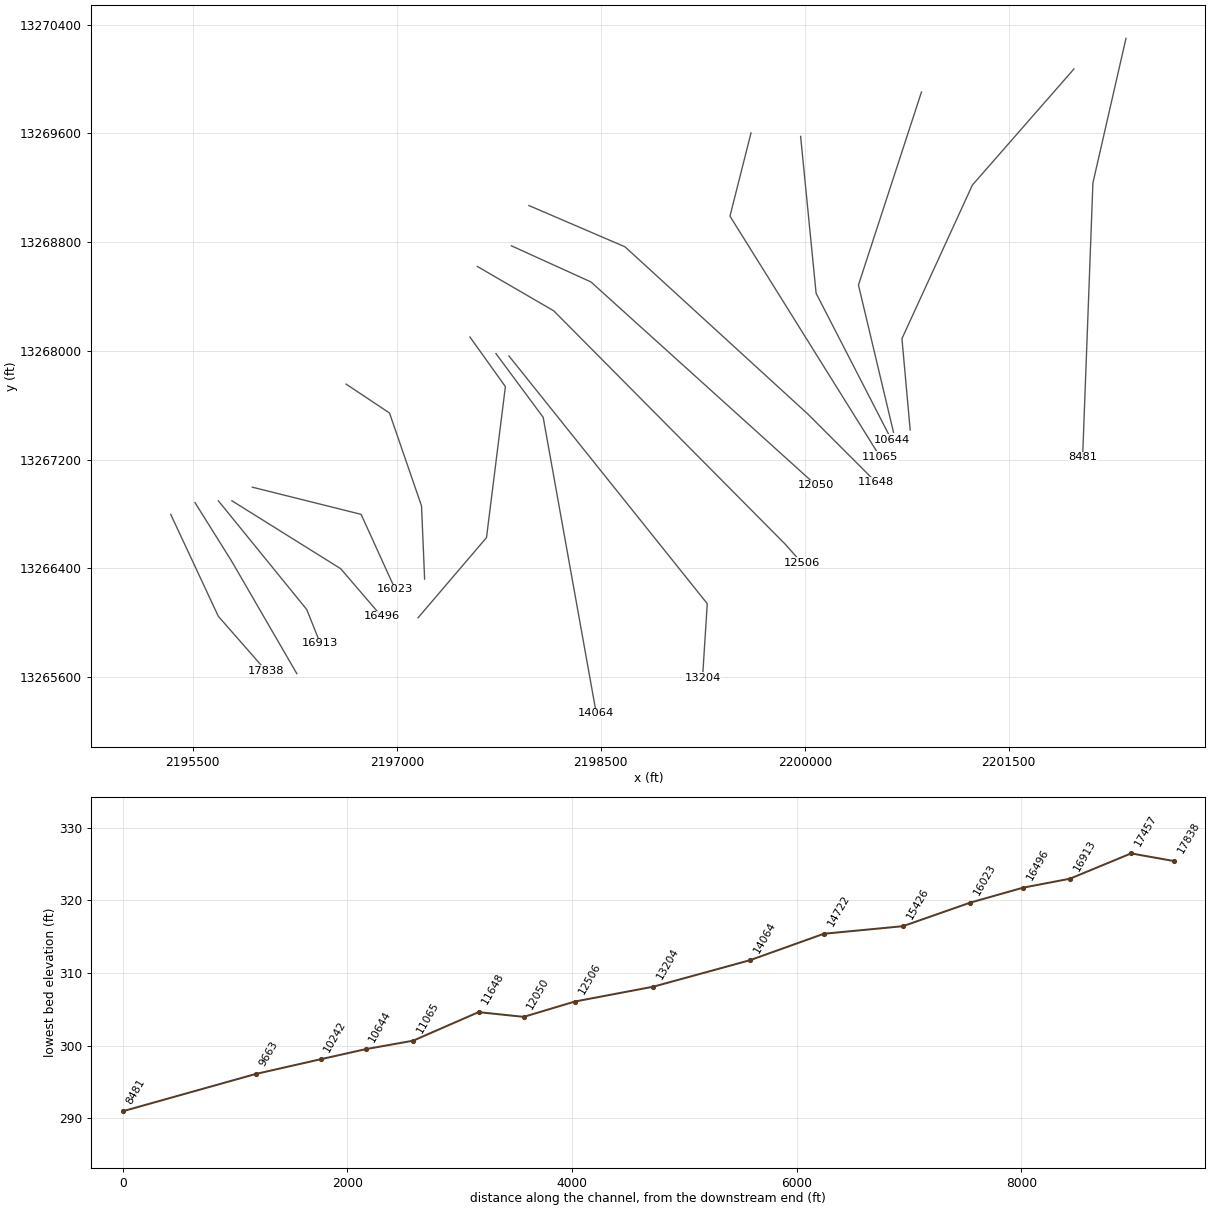
HEC-RAS study UNT001 IN SPCR.prj: UNT001 IN SPCR Base Level Engineering

--- UNT001 IN SPCR.g01 (geometry) --- (continued)

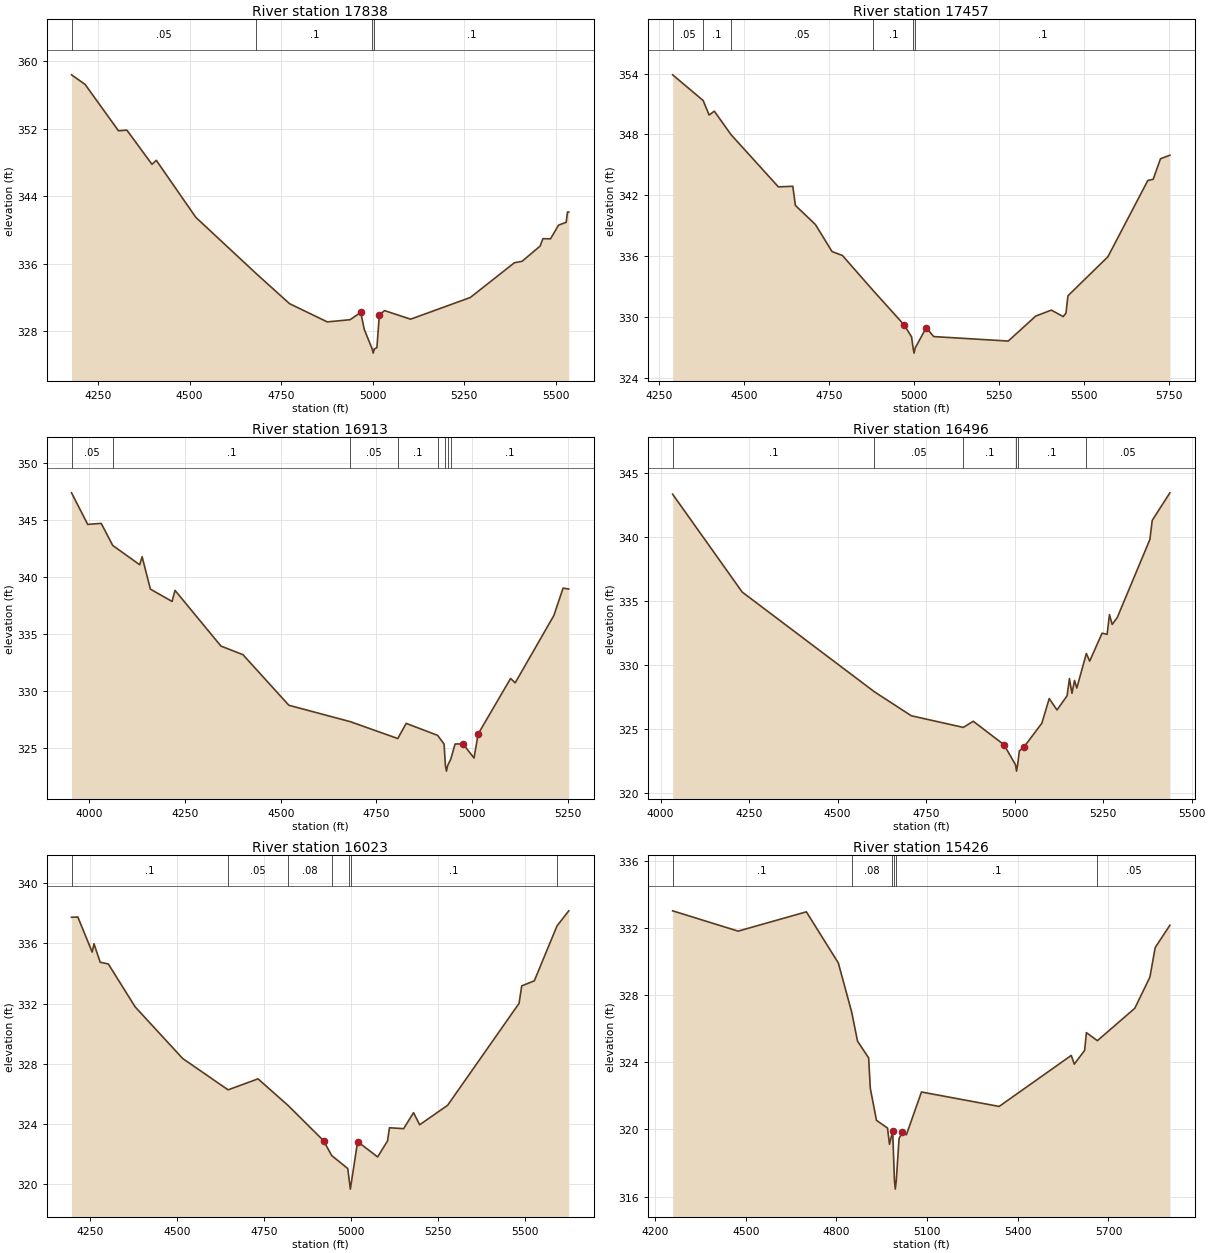
Type RM Length L Ch R = 1 ,17838   ,381,381,381
BEGIN DESCRIPTION:
UNT001 IN SPCR 30.0
END DESCRIPTION:
XS GIS Cut Line= 3
      2195337.74     13266796.82      2195687.72     13266046.85
      2196037.71     13265646.87
#Sta/Elev= 30
  4177.1  358.37  4214.1  357.24  4305.5  351.74  4328.4  351.82    4397  347.77
  4408.8  348.24  4516.8  341.49  4682.2  334.81    4773  331.26  4876.2   329.1
  4938.5  329.36  4967.7  330.23  4977.1  328.23  4998.9   325.9  5001.7   325.4
  5004.9   325.9  5011.8  326.05  5018.5  329.92  5032.7  330.44  5103.9  329.42
  5267.1  331.99  5387.7  336.11  5408.6  336.28  5457.9  338.08  5465.5  338.96
  5486.4  338.94  5508.2  340.56  5529.1   340.9  5532.9  342.12  5536.2  342.12
#Mann= 4 ,-1 , 0
  4177.1     .05       0  4682.2      .1       0  4998.9     .07       0
  5004.9      .1       0
Bank Sta=4967.7,5018.5
XS Rating Curve= 0 ,0
Exp/Cntr=0.3,0.1

Type RM Length L Ch R = 1 ,17457   ,544,544,544
BEGIN DESCRIPTION:
UNT001 IN SPCR 29.0
END DESCRIPTION:
XS GIS Cut Line= 3
      2195516.17     13266883.52      2195787.43     13266449.49
      2196264.86     13265624.85
#Sta/Elev= 30
    4289  353.87  4378.8  351.34  4396.4  349.91  4411.7  350.29  4461.1  347.97
  4600.4  342.83  4642.9  342.89  4650.6     341  4709.6  339.12  4758.4  336.46
  4789.1  336.07  4880.6  332.58  4971.2  329.22  4992.8  328.05  4997.3  326.95
  5000.1  326.45  5003.3  326.95  5035.8  328.95  5058.1  328.08  5277.6  327.64
  5358.5   330.1  5404.5  330.69  5439.4  330.05  5447.6  330.39  5453.4   332.1
    5571  335.94  5688.7  343.46  5704.5  343.58    5726   345.6  5753.7  345.95
#Mann= 6 ,-1 , 0
    4289     .05       0  4378.8      .1       0  4461.1     .05       0
  4880.6      .1       0  4997.3     .07       0  5003.3      .1       0
Bank Sta=4971.2,5035.8
XS Rating Curve= 0 ,0
Exp/Cntr=0.3,0.1

Type RM Length L Ch R = 1 ,16913   ,417,417,417
BEGIN DESCRIPTION:
UNT001 IN SPCR 28.0
END DESCRIPTION:
XS GIS Cut Line= 3
      2195687.72     13266896.86      2196337.72     13266096.85
      2196437.71     13265846.89
#Sta/Elev= 30
  3953.1  347.39  3995.5  344.62  4030.7  344.71  4060.9  342.77  4131.3  341.08
  4137.7  341.78  4159.3  338.94    4216  337.86  4223.7  338.83  4343.9  333.94
  4401.3  333.19  4521.3  328.75  4681.9  327.31  4806.1  325.83    4828  327.16
  4910.2  326.11  4927.1  325.35  4930.6  323.47  4933.3  322.97  4936.6  323.47
  4944.5  324.01  4955.9  325.35  4976.7  325.36  5005.4  324.12  5016.2  326.23
    5101   331.1  5113.1  330.72  5214.1  336.62  5238.3  339.03  5253.1  338.95
#Mann= 8 ,-1 , 0
  3953.1     .05       0  4060.9      .1       0  4681.9     .05       0
  4806.1      .1       0  4910.2     .05       0  4930.6     .07       0
  4936.6     .05       0  4944.5      .1       0
Bank Sta=4976.7,5016.2
XS Rating Curve= 0 ,0
Exp/Cntr=0.3,0.1

Type RM Length L Ch R = 1 ,16496   ,473,473,473
BEGIN DESCRIPTION:
UNT001 IN SPCR 27.0
END DESCRIPTION:
XS GIS Cut Line= 3
      2195787.69     13266896.87      2196587.72     13266396.85
      2196887.71     13266046.86
#Sta/Elev= 30
  4034.1  343.34  4230.5  335.71  4603.9  327.93  4708.1  326.06  4854.9  325.15
  4883.2  325.63  4969.9   323.8  5002.5  322.24  5005.3  321.74  5008.5  322.24
  5013.2  323.31  5027.5  323.66  5076.9  325.48  5097.7   327.4  5119.7  326.51
  5148.2  327.62  5154.8  328.96  5161.9  327.81  5169.1  328.81  5175.6  328.22
  5202.6  330.92  5211.9  330.32    5247   332.5  5261.3  332.41  5267.8  333.95
  5275.5  333.18  5289.8  333.72    5382  339.81  5388.6   341.3  5438.5  343.45
#Mann= 6 ,-1 , 0
  4034.1      .1       0  4603.9     .05       0  4854.9      .1       0
  5002.5     .07       0  5008.5      .1       0  5202.6     .05       0
Bank Sta=4969.9,5027.5
XS Rating Curve= 0 ,0
Exp/Cntr=0.3,0.1

Type RM Length L Ch R = 1 ,16023   ,597,597,597
BEGIN DESCRIPTION:
UNT001 IN SPCR 26.0
END DESCRIPTION:
XS GIS Cut Line= 3
      2195937.69     13266996.86      2196737.72     13266796.85
      2196987.72     13266246.86
#Sta/Elev= 30
  4196.1  337.74  4214.2  337.76  4255.4  335.43  4260.6  335.98  4278.6  334.75
  4301.8  334.64  4379.1  331.78  4515.7  328.35    4646  326.27  4732.1     327
  4818.9  325.22  4920.3  322.89  4943.8   321.9  4989.8  321.04  4994.6  320.17
  4997.3  319.67  5000.6  320.17  5018.2  322.83  5075.7  321.81  5104.2  322.88
  5109.7  323.75  5150.4  323.69  5178.9  324.75  5196.5  323.95  5276.7  325.24
  5482.1  332.02  5489.8  333.18    5526  333.52    5591  337.16  5624.9  338.17
#Mann= 7 ,-1 , 0
  4196.1      .1       0    4646     .05       0  4818.9     .08       0
  4943.8      .1       0  4994.6     .07       0  5000.6      .1       0
    5591     .05       0
Bank Sta=4920.3,5018.2
XS Rating Curve= 0 ,0
Exp/Cntr=0.3,0.1

Type RM Length L Ch R = 1 ,15426   ,704,704,704
BEGIN DESCRIPTION:
UNT001 IN SPCR 24.0
END DESCRIPTION:
XS GIS Cut Line= 4
      2196627.47     13267755.34      2196946.47     13267542.67
      2197181.93      13266859.1      2197204.67     13266320.86
#Sta/Elev= 30
  4258.2  333.03  4474.8  331.82  4700.6  332.97  4806.4  329.92  4850.4     327
  4869.9  325.26  4906.6  324.26  4912.2  322.44  4932.6  320.54  4969.1  320.08
  4975.6  319.11  4985.1  319.83  4986.2  319.91    4992  316.94  4994.8  316.44
    4998  316.94  5007.3  319.46  5017.9  319.82  5031.5  319.68  5081.4  322.23
  5338.4  321.37    5577  324.41    5587  323.89  5621.2  324.71  5627.1  325.77
  5663.4  325.29  5787.2  327.22  5837.2  329.08  5854.7  330.84  5903.3  332.17
#Mann= 6 ,-1 , 0
  4258.2      .1       0  4850.4     .08       0  4985.1      .1       0
    4992     .07       0    4998      .1       0  5663.4     .05       0
Bank Sta=4986.2,5017.9
XS Rating Curve= 0 ,0
Exp/Cntr=0.3,0.1

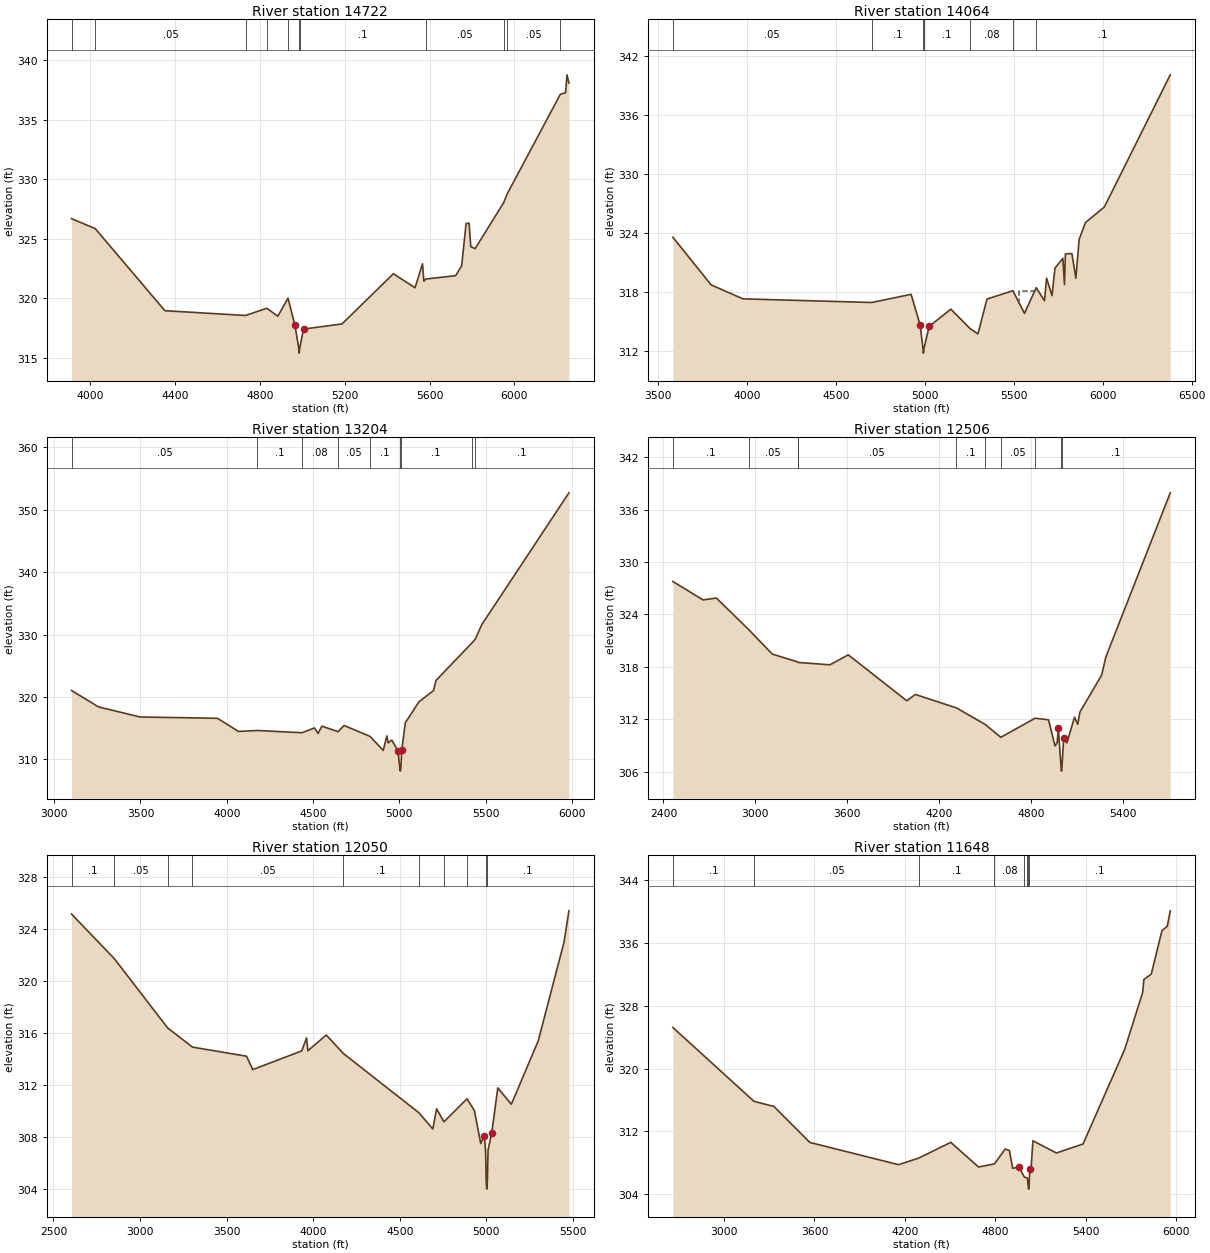
Type RM Length L Ch R = 1 ,14722   ,658,658,658
BEGIN DESCRIPTION:
Mapping XS e9afc3c6
END DESCRIPTION:
XS GIS Cut Line= 4
      2197538.15     13268101.46      2197798.56     13267736.88
      2197659.67     13266625.77      2197156.21      13266035.5
#Sta/Elev= 30
  3913.4  326.69  4025.1  325.85  4353.4  318.96  4733.6  318.56  4833.5  319.17
  4885.5   318.5  4933.4  320.01  4966.1  317.73  4983.3   315.9    4986   315.4
  4989.3   315.9  5006.4  317.42  5187.8  317.85  5429.7  322.06  5531.9  320.89
  5567.1   322.9  5573.6  321.44  5582.6  321.62    5723   321.9  5751.5  322.73
  5772.4  326.28  5786.7   326.3  5794.4  324.34  5815.2  324.17    5950  328.05
    5966  328.76  6216.5  337.13  6241.2  337.25  6247.8  338.76    6257  338.08
#Mann= 11 ,-1 , 0
  3913.4      .1       0  4025.1     .05       0  4733.6     .08       0
  4833.5     .05       0  4933.4      .1       0  4983.3     .07       0
  4989.3      .1       0  5582.6     .05       0    5950      .1       0
    5966     .05       0  6216.5      .1       0
Bank Sta=4966.1,5006.4
XS Rating Curve= 0 ,0
Exp/Cntr=0.3,0.1

Type RM Length L Ch R = 1 ,14064   ,860,860,860
BEGIN DESCRIPTION:
Mapping XS 34e0ca9e
END DESCRIPTION:
XS GIS Cut Line= 3
       2197729.1     13267979.96      2198076.34     13267511.19
      2198466.96      13265332.4
#Sta/Elev= 30
  3582.8  323.57  3798.2  318.71    3977  317.29  4700.5  316.92  4922.4  317.75
  4973.2  314.63  4989.1  312.26  4991.8  311.76  4995.1  312.26    5024  314.48
  5145.9  316.24    5255  314.25  5298.3  313.72  5349.1  317.27  5494.6  318.12
  5559.9  315.81  5625.8  318.43  5672.4   317.1  5684.3   319.4  5714.8  317.62
  5731.2  320.42  5775.8  321.42  5784.9  318.75    5790  321.87  5826.6  321.91
  5848.8   319.4  5867.2  323.33  5902.6  325.06  6009.4  326.66  6379.7  340.12
#Mann= 7 ,-1 , 0
  3582.8     .05       0  4700.5      .1       0  4989.1     .07       0
  4995.1      .1       0    5255     .08       0  5494.6     .05       0
  5625.8      .1       0
#XS Ineff= 1 ,-1
 5531.91 5622.28   318.1
Permanent Ineff=
       F
Bank Sta=4973.2,5024
XS Rating Curve= 0 ,0
Exp/Cntr=0.3,0.1

Type RM Length L Ch R = 1 ,13204   ,698,698,698
BEGIN DESCRIPTION:
Mapping XS 138de81a
END DESCRIPTION:
XS GIS Cut Line= 3
      2197824.62     13267962.55      2199282.93     13266139.66
      2199248.21      13265592.8
#Sta/Elev= 30
  3100.8  321.04  3256.6  318.41  3498.3  316.79  3946.5  316.58  4068.2  314.48
  4177.5  314.63  4436.9  314.27  4508.4  315.04  4529.6  314.16  4551.6  315.32
  4645.7  314.44  4679.7  315.43  4830.3  313.69    4907  311.44  4927.8  313.75
  4935.8  312.64  4956.6  313.09  4991.8  311.42  5003.3  308.62    5006  308.12
  5009.3  308.62  5014.3  311.44  5035.1  315.87  5113.5   319.2  5198.4  321.02
  5212.8  322.64  5418.9  328.59  5440.6  329.26  5478.1  331.58  5983.2  352.69
#Mann= 9 ,-1 , 0
  3100.8     .05       0  4177.5      .1       0  4436.9     .08       0
  4645.7     .05       0  4830.3      .1       0  5003.3     .07       0
  5009.3      .1       0  5418.9     .05       0  5440.6      .1       0
Bank Sta=4991.8,5014.3
XS Rating Curve= 0 ,0
Exp/Cntr=0.3,0.1

Type RM Length L Ch R = 1 ,12506   ,456,456,456
BEGIN DESCRIPTION:
UNT001 IN SPCR 21.0
END DESCRIPTION:
XS GIS Cut Line= 4
      2197592.03     13268621.22      2198154.12      13268294.6
      2199855.45     13266578.08      2199976.76     13266441.61
#Sta/Elev= 30
  2461.4  327.77    2659  325.66  2745.6  325.88  2956.3  322.28  3110.7  319.47
  3276.4  318.57  3279.7  318.51  3487.2  318.24  3607.4  319.38  3989.3  314.13
  4045.8  314.85  4313.9  313.31  4501.9  311.42  4603.7  309.95  4827.9  312.13
  4915.6  311.95    4958  308.96  4972.1  309.35  4979.3  310.99  4997.4  306.58
  5000.2  306.08  5003.4  306.58  5014.6  309.85  5035.8  309.32  5085.3  312.25
  5106.5  311.44  5120.7  312.84  5262.1  317.04  5290.4  319.15  5710.9  337.91
#Mann= 10 ,-1 , 0
  2461.4      .1       0  2956.3     .05       0  3276.4      .1       0
  3279.7     .05       0  4313.9      .1       0  4501.9     .08       0
  4603.7     .05       0  4827.9      .1       0  4997.4     .07       0
  5003.4      .1       0
Bank Sta=4979.3,5014.6
XS Rating Curve= 0 ,0
Exp/Cntr=0.3,0.1

Type RM Length L Ch R = 1 ,12050   ,402,402,402
BEGIN DESCRIPTION:
UNT001 IN SPCR 20.0
END DESCRIPTION:
XS GIS Cut Line= 3
      2197842.68     13268773.12      2198427.54     13268507.27
      2200082.55     13267011.69
#Sta/Elev= 30
  2604.5  325.14  2851.6  321.71  3159.5  316.38  3303.1   314.9  3615.4   314.2
  3651.3  313.17  3934.5  314.61  3962.1  315.61  3969.6  314.62  4075.7  315.83
  4174.8  314.41  4610.8  309.85  4691.5   308.6  4713.1  310.15  4755.5  309.15
  4888.7  310.92  4932.1     310    4968  307.48  4988.9  308.09  4996.3  306.82
  5000.1  304.47  5002.8  303.97  5006.1  304.47  5010.5  306.98  5031.5  308.29
  5066.7  311.76    5145   310.5  5300.5  315.39  5449.2  322.98  5477.6  325.39
#Mann= 10 ,-1 , 0
  2604.5      .1       0  2851.6     .05       0  3159.5      .1       0
  3303.1     .05       0  4174.8      .1       0  4610.8     .08       0
  4755.5     .05       0  4888.7      .1       0  5000.1     .07       0
  5006.1      .1       0
Bank Sta=4988.9,5031.5
XS Rating Curve= 0 ,0
Exp/Cntr=0.3,0.1

Type RM Length L Ch R = 1 ,11648   ,583,583,583
BEGIN DESCRIPTION:
UNT001 IN SPCR 19.0
END DESCRIPTION:
XS GIS Cut Line= 4
      2197971.81     13269069.32      2198678.19     13268765.51
      2200022.54     13267535.08      2200523.27     13267034.35
#Sta/Elev= 30
  2660.7  325.24  3198.7  315.82  3331.2  315.16  3569.8  310.57  4157.5  307.74
    4292  308.58  4504.1  310.59  4688.5  307.44  4794.1  307.84  4865.5  309.74
  4893.2  309.54  4914.8  307.28  4957.3  307.43  4992.3  306.15    5012  306.05
  5017.9  305.12  5020.6  304.62  5023.9  305.12  5028.3  307.19    5035  306.73
  5049.2  310.79  5204.9  309.23  5381.8  310.38  5657.5  322.42  5777.7  329.75
  5784.8  331.35  5834.3  332.06    5905  337.58  5940.4  338.16  5960.2  340.12
#Mann= 8 ,-1 , 0
  2660.7      .1       0  3198.7     .05       0    4292      .1       0
  4794.1     .08       0  4992.3     .05       0    5012      .1       0
  5017.9     .03       0  5023.9      .1       0
Bank Sta=4957.3,5028.3
XS Rating Curve= 0 ,0
Exp/Cntr=0.3,0.1

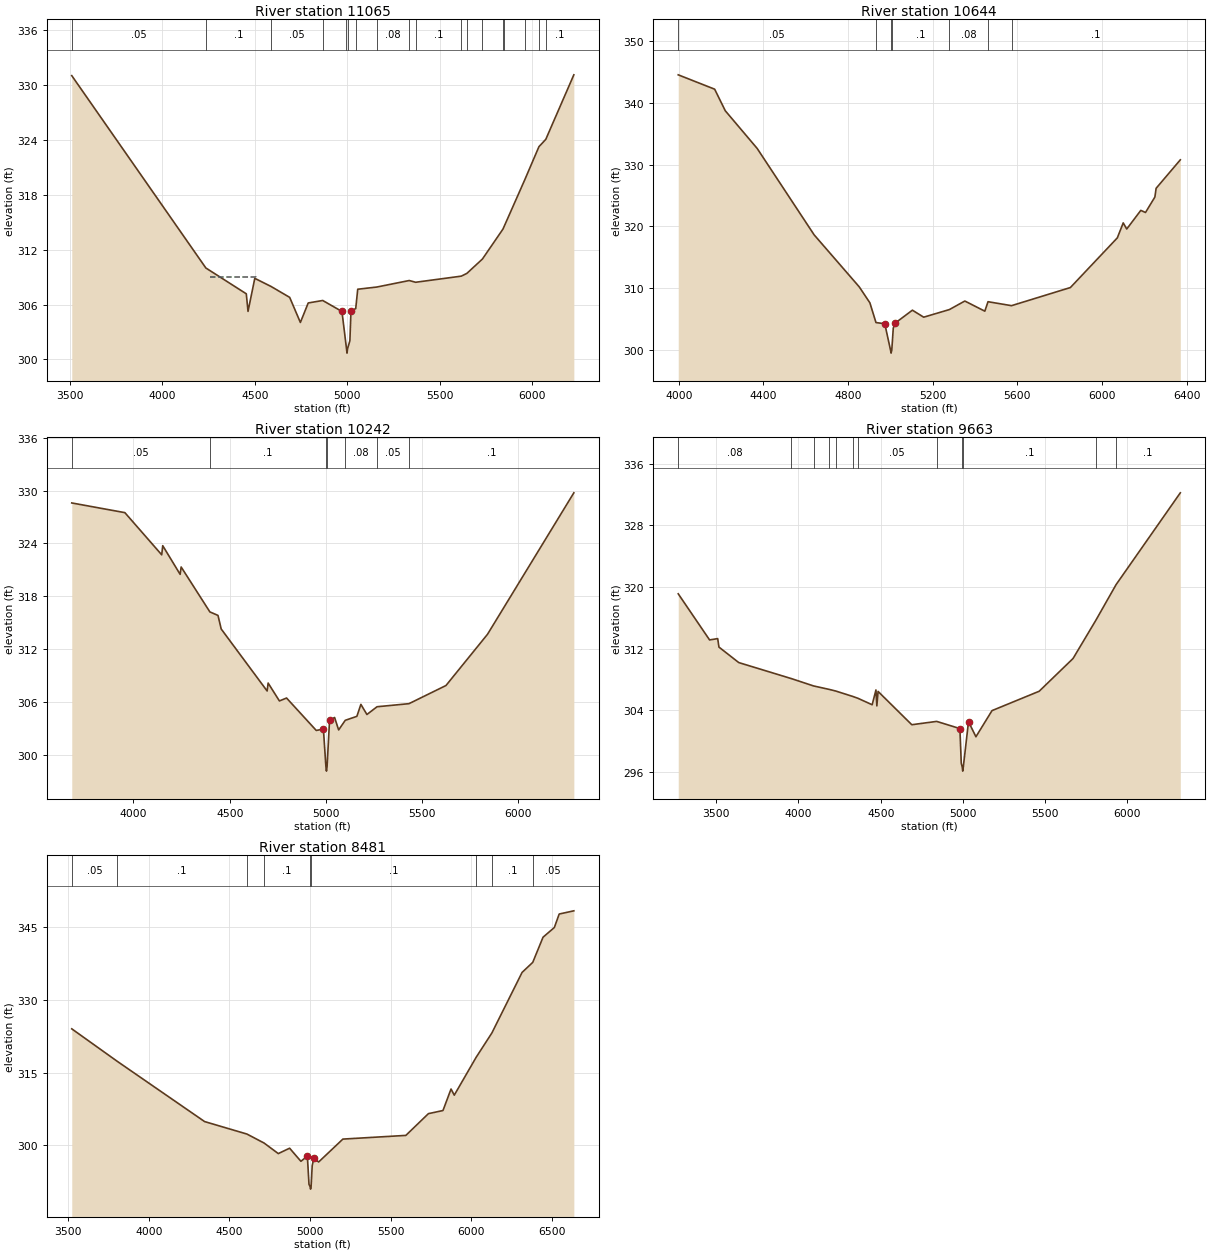
Type RM Length L Ch R = 1 ,11065   ,421,421,421
BEGIN DESCRIPTION:
Mapping XS be6f6079
END DESCRIPTION:
XS GIS Cut Line= 3
      2199604.64      13269603.5      2199449.91     13268991.33
      2200552.92     13267222.48
#Sta/Elev= 30
  3509.7     331  4235.1  309.99  4453.8  307.17  4463.2  305.25  4499.8  308.86
  4588.8  307.96  4688.5  306.78  4746.4  304.04  4788.8  306.17  4867.3  306.44
  4971.3  305.24  4995.8  301.19  4998.6  300.69  5001.8  301.19  5014.2  302.04
  5020.1  305.31  5045.7  305.55  5056.7  307.67    5160  307.91  5335.2  308.62
    5370  308.43  5616.9   309.1  5647.1   309.4  5731.2  310.97    5842  314.23
  5845.4  314.38  5959.7   319.6  6036.9  323.24  6073.9  324.04  6225.7  331.09
#Mann= 18 ,-1 , 0
  3509.7     .05       0  4235.1      .1       0  4588.8     .05       0
  4867.3      .1       0  4995.8     .07       0  5001.8      .1       0
  5045.7     .05       0    5160     .08       0  5335.2     .05       0
    5370      .1       0  5616.9     .08       0  5647.1      .1       0
  5731.2     .08       0    5842      .1       0  5845.4     .08       0
  5959.7      .1       0  6036.9     .08       0  6073.9      .1       0
#XS Ineff= 1 ,-1
 4255.13 4503.76  308.96
Permanent Ineff=
       F
Bank Sta=4971.3,5020.1
XS Rating Curve= 0 ,0
Exp/Cntr=0.3,0.1

Type RM Length L Ch R = 1 ,10644   ,402,402,402
BEGIN DESCRIPTION:
Mapping XS 3bfd9063
END DESCRIPTION:
XS GIS Cut Line= 3
      2199969.38     13269578.15      2200083.31     13268423.72
      2200637.74     13267345.23
#Sta/Elev= 30
  3997.4  344.51  4169.5  342.19  4219.8   338.7  4370.5  332.61  4639.6  318.65
  4852.8  310.24  4903.1  307.66  4931.9  304.47  4973.4  304.28  5000.6  300.03
  5003.3  299.53  5006.6  300.03  5013.6  303.57  5023.7  304.41    5104  306.47
  5157.4  305.34  5278.8  306.57  5351.8  307.95  5446.3  306.31  5461.3  307.84
  5572.4   307.2  5850.7  310.13  6072.5  318.16  6100.3  320.58  6116.9  319.59
  6183.4   322.6  6205.6  322.26    6250  324.76  6255.8  326.17  6370.1  330.77
#Mann= 7 ,-1 , 0
  3997.4     .05       0  4931.9      .1       0  5000.6     .07       0
  5006.6      .1       0  5278.8     .08       0  5461.3     .05       0
  5572.4      .1       0
Bank Sta=4973.4,5023.7
XS Rating Curve= 0 ,0
Exp/Cntr=0.3,0.1

Type RM Length L Ch R = 1 ,10242   ,579,579,579
BEGIN DESCRIPTION:
Mapping XS e9569f0f
END DESCRIPTION:
XS GIS Cut Line= 3
      2200858.03     13269904.83      2200394.71     13268484.48
      2200652.42      13267400.6
#Sta/Elev= 30
  3679.5  328.59  3955.4  327.49  4146.8   322.7    4152  323.74  4242.5  320.48
  4247.7  321.32  4396.9  316.22  4439.1  315.82  4455.7  314.28  4694.3  307.24
  4699.6  308.14  4758.1  306.11  4795.3  306.44  4949.5  302.76  4986.7  302.91
  4999.7  298.64  5002.5  298.14  5005.7  298.64  5018.6  303.92  5044.8  304.23
  5065.8  302.82  5100.2  303.91  5160.5  304.36  5181.3  305.72  5212.7  304.57
  5265.3  305.45  5431.2   305.8  5623.3  307.86  5839.2  313.68  6287.6  329.74
#Mann= 7 ,-1 , 0
  3679.5     .05       0  4396.9      .1       0  4999.7     .07       0
  5005.7      .1       0  5100.2     .08       0  5265.3     .05       0
  5431.2      .1       0
Bank Sta=4986.7,5018.6
XS Rating Curve= 0 ,0
Exp/Cntr=0.3,0.1

Type RM Length L Ch R = 1 ,9663    ,1182,1182,1182
BEGIN DESCRIPTION:
Mapping XS 7d00d375
END DESCRIPTION:
XS GIS Cut Line= 4
      2201979.12      13270074.3      2201232.49     13269220.03
      2200714.53     13268089.95      2200775.07     13267417.26
#Sta/Elev= 30
  3268.8  319.11  3459.4  313.13  3508.8   313.3  3516.4   312.2  3636.9  310.19
    3957  308.11  4091.8  307.16  4187.1  306.71  4226.5   306.5  4331.3  305.79
  4361.3  305.56  4448.1  304.72  4471.1  306.64  4476.6  304.57  4483.9  306.45
  4689.1  302.13  4840.2  302.56  4981.6  301.63  4989.9  297.14  4996.1  296.61
  4998.8  296.11  5002.1  296.61  5033.9  302.52  5079.1  300.57  5176.9  303.96
  5463.6  306.47  5669.7  310.72  5807.8  315.66  5931.3   320.3  6321.9  332.21
#Mann= 12 ,-1 , 0
  3268.8     .08       0    3957      .1       0  4091.8     .05       0
  4187.1      .1       0  4226.5     .05       0  4331.3      .1       0
  4361.3     .05       0  4840.2      .1       0  4996.1     .07       0
  5002.1      .1       0  5807.8     .05       0  5931.3      .1       0
Bank Sta=4981.6,5033.9
XS Rating Curve= 0 ,0
Exp/Cntr=0.3,0.1

Type RM Length L Ch R = 1 ,8481    ,784,784,784
BEGIN DESCRIPTION:
Mapping XS 3cef75ba
END DESCRIPTION:
XS GIS Cut Line= 3
      2202361.88     13270299.75      2202118.83     13269236.41
      2202042.88      13267216.1
#Sta/Elev= 30
  3522.4  324.05  3803.9  317.36    4346  304.92  4608.2  302.35  4714.4   300.5
  4802.8  298.32  4872.9  299.43  4942.9  296.73    4983   297.8    4993  291.98
    5000  291.49  5002.7  290.99    5006  291.49    5013  295.85    5023  297.32
    5053  296.59  5203.1  301.31  5593.4  302.07  5733.5  306.56  5823.6   307.2
  5873.6  311.64  5893.6  310.37  6029.1  318.17    6127  323.21  6313.9  335.68
  6380.2  337.76    6444  342.95  6514.1  344.95  6544.1  347.73  6634.9  348.39
#Mann= 9 ,-1 , 0
  3522.4     .05       0  3803.9      .1       0  4608.2     .05       0
  4714.4      .1       0    5000     .07       0    5006      .1       0
  6029.1     .05       0    6127      .1       0  6380.2     .05       0
Bank Sta=4983,5023
XS Rating Curve= 0 ,0
Exp/Cntr=0.3,0.1