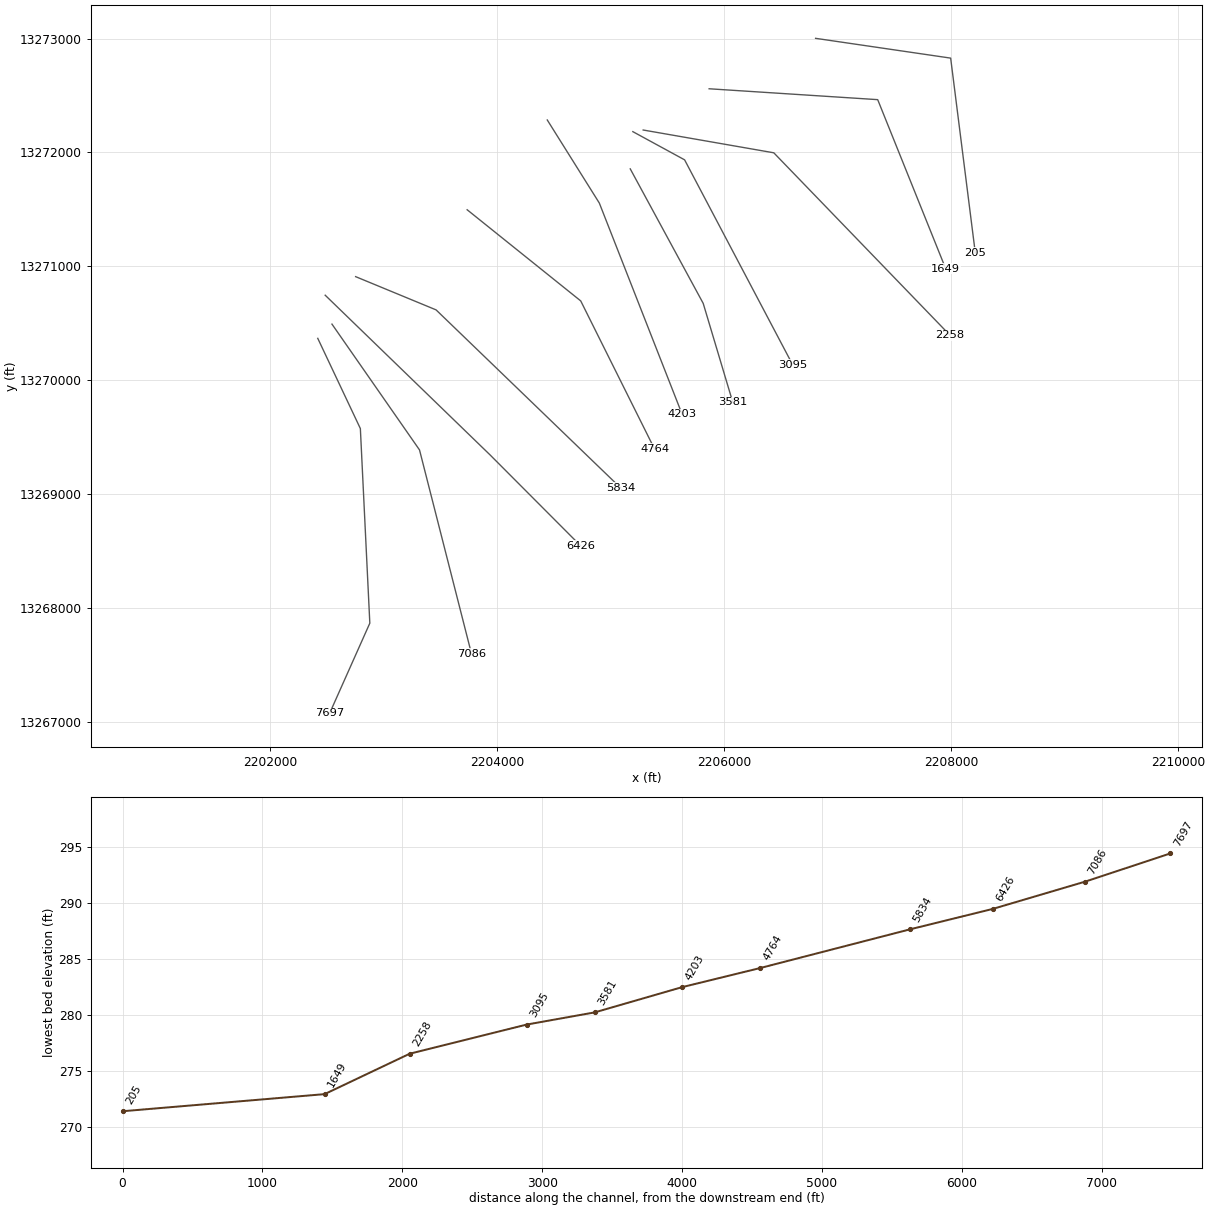
HEC-RAS study UNT001 IN SPCR.prj: UNT001 IN SPCR Base Level Engineering

--- UNT001 IN SPCR.g01 (geometry) --- (continued)

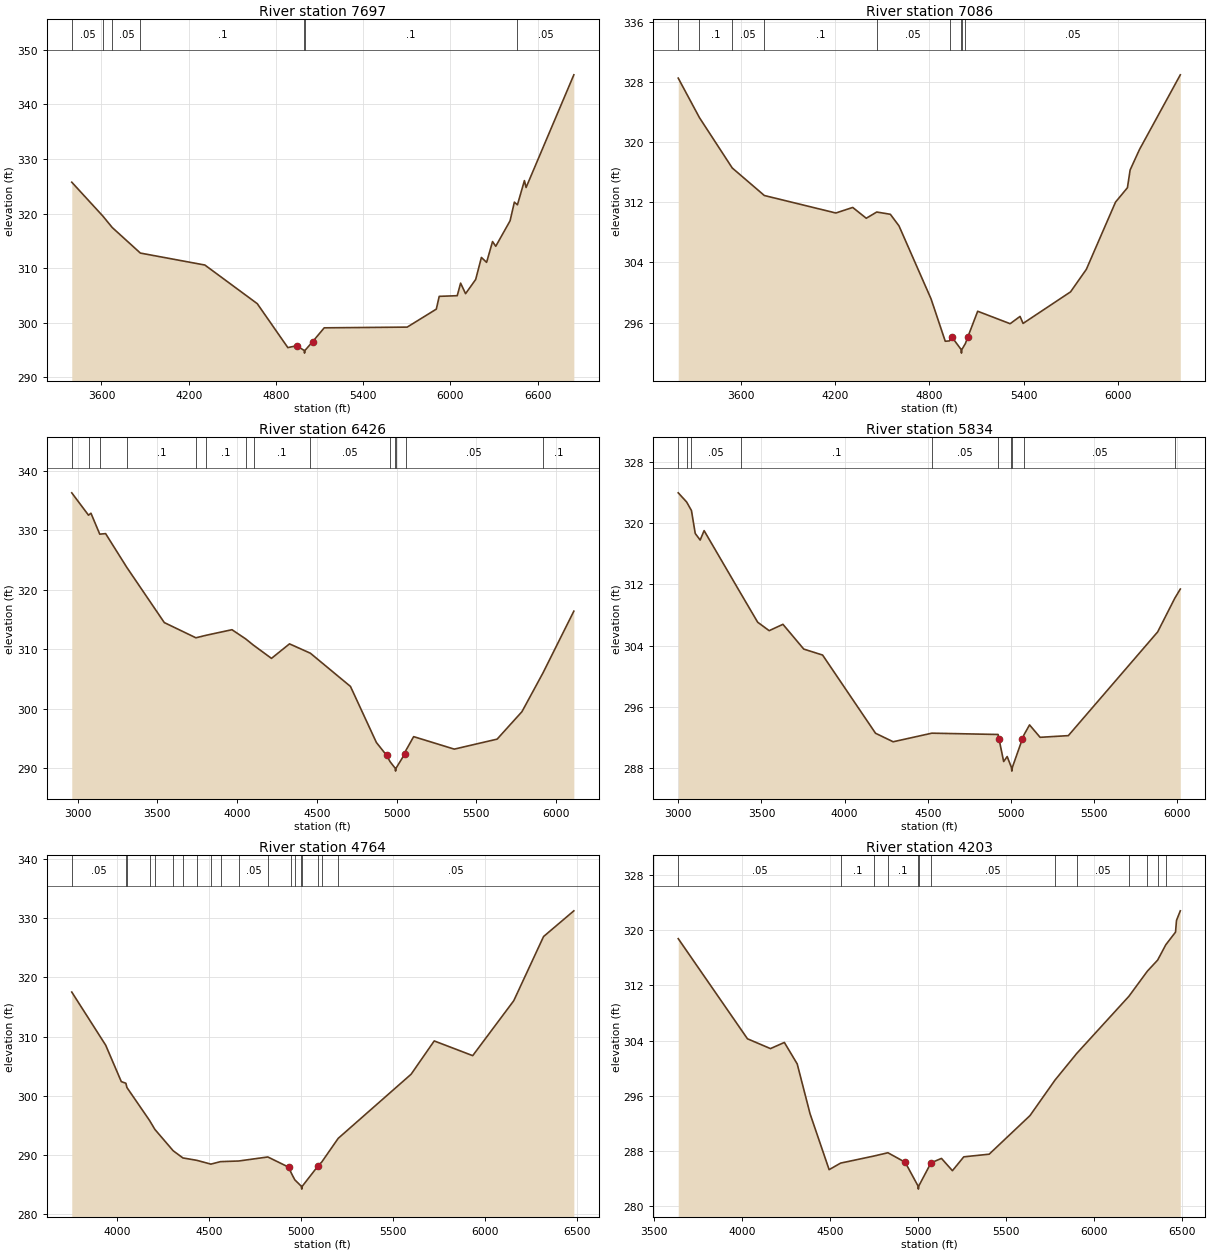
Type RM Length L Ch R = 1 ,7697    ,611,611,611
BEGIN DESCRIPTION:
UNT001 IN SPCR 12.0
END DESCRIPTION:
XS GIS Cut Line= 4
      2202422.38     13270368.14      2202797.38     13269576.48
      2202880.71     13267868.15      2202526.55     13267076.51
#Sta/Elev= 30
  3395.8  325.73  3610.3  319.51  3674.4  317.43  3867.7  312.76  4311.5  310.57
  4671.9   303.5  4882.1  295.46  4942.2   295.8  4994.2  294.95    4997  294.45
  5000.2  294.95  5052.3  296.54  5132.4  299.08  5703.1  299.21  5903.3   302.5
  5923.4  304.84  6047.3  304.96  6070.5  307.26  6104.6  305.33  6174.2  307.93
  6213.6  311.96  6249.3  311.06  6290.2  314.87  6312.2     314  6410.8  318.67
  6440.3  322.08  6461.4  321.59  6509.4  326.02  6520.9  324.76  6849.4  345.38
#Mann= 7 ,-1 , 0
  3395.8     .05       0  3610.3      .1       0  3674.4     .05       0
  3867.7      .1       0  4994.2     .07       0  5000.2      .1       0
  6461.4     .05       0
Bank Sta=4942.2,5052.3
XS Rating Curve= 0 ,0
Exp/Cntr=0.3,0.1

Type RM Length L Ch R = 1 ,7086    ,660,660,660
BEGIN DESCRIPTION:
UNT001 IN SPCR 11.0
END DESCRIPTION:
XS GIS Cut Line= 3
      2202547.36     13270493.18      2203318.21     13269388.98
      2203776.54     13267597.32
#Sta/Elev= 30
  3202.2  328.56  3337.4  323.29    3546  316.59  3750.4  312.92  4205.6  310.59
  4312.9  311.33  4399.2  309.89  4465.6  310.72  4552.5  310.42  4607.6  308.87
  4811.7  299.14    4902   293.5  4929.1  293.55  4943.3  294.09  5002.2  292.42
    5005  291.92  5008.2  292.42  5030.2   293.2  5046.3  294.11  5108.4   297.5
  5314.9  295.84    5378  296.81  5397.4  295.88  5699.4  300.08    5800  303.08
  5985.8  312.04  6061.6  313.96  6078.7  316.32  6138.1  319.04  6398.2     329
#Mann= 9 ,-1 , 0
  3202.2     .05       0  3337.4      .1       0    3546     .05       0
  3750.4      .1       0  4465.6     .05       0  4929.1      .1       0
  5002.2     .07       0  5008.2      .1       0  5030.2     .05       0
Bank Sta=4943.3,5046.3
XS Rating Curve= 0 ,0
Exp/Cntr=0.3,0.1

Type RM Length L Ch R = 1 ,6426    ,592,592,592
BEGIN DESCRIPTION:
UNT001 IN SPCR 10.0
END DESCRIPTION:
XS GIS Cut Line= 3
      2202487.72     13270746.85      2203937.72     13269346.85
       2204737.7     13268546.88
#Sta/Elev= 30
  2963.8  336.28  3068.8  332.52  3084.1  332.85  3139.2  329.33  3175.9  329.42
  3308.9  323.74  3543.8  314.46    3742   311.9    3805  312.32    3968  313.26
  4053.1  311.73  4103.2  310.65  4215.5  308.44  4328.6  310.88  4459.3  309.31
  4710.7  303.72  4873.2  294.29    4937  292.14  4958.6  291.08  4990.5  289.98
  4993.3  289.48  4996.5  289.98  5050.1  292.33  5056.8   292.9  5106.6  295.28
  5361.2  293.18  5629.9  294.86  5785.5  299.48  5916.6  305.96  6110.7  316.38
#Mann= 14 ,-1 , 0
  2963.8     .05       0  3068.8     .08       0  3139.2     .05       0
  3308.9      .1       0    3742     .05       0    3805      .1       0
  4053.1     .05       0  4103.2      .1       0  4459.3     .05       0
  4958.6      .1       0  4990.5     .07       0  4996.5      .1       0
  5056.8     .05       0  5916.6      .1       0
Bank Sta=4937,5050.1
XS Rating Curve= 0 ,0
Exp/Cntr=0.3,0.1

Type RM Length L Ch R = 1 ,5834    ,1070,1070,1070
BEGIN DESCRIPTION:
UNT001 IN SPCR 9.0
END DESCRIPTION:
XS GIS Cut Line= 3
      2202755.75      13270909.8      2203464.04     13270618.15
      2205089.02     13269055.67
#Sta/Elev= 30
  2999.2  323.95  3049.6  322.76  3078.7  321.64  3101.5  318.65  3131.1  317.79
  3154.8  319.02  3376.6  310.78  3477.2  307.07  3546.4  305.97  3629.1   306.8
  3754.2  303.57  3867.6  302.79  4186.1  292.59  4292.1  291.48  4524.9   292.6
  4923.3  292.43  4928.6  291.87  4956.9   288.9    4978  289.55  5003.3  288.15
    5006  287.65  5009.3  288.15  5070.1  291.89  5079.3  292.39  5112.5  293.68
  5176.1  292.06  5345.9  292.28  5883.3  305.81    5986  310.19  6019.5   311.4
#Mann= 10 ,-1 , 0
  2999.2     .05       0  3049.6     .08       0  3078.7     .05       0
  3376.6      .1       0  4524.9     .05       0  4923.3      .1       0
  5003.3     .07       0  5009.3      .1       0  5079.3     .05       0
    5986      .1       0
Bank Sta=4928.6,5070.1
XS Rating Curve= 0 ,0
Exp/Cntr=0.3,0.1

Type RM Length L Ch R = 1 ,4764    ,561,561,561
BEGIN DESCRIPTION:
UNT001 IN SPCR 7.0
END DESCRIPTION:
XS GIS Cut Line= 3
      2203737.73     13271496.85      2204737.72     13270696.85
      2205387.74     13269396.82
#Sta/Elev= 30
  3751.3  317.53  3936.2  308.53    4021  302.38    4046   302.1  4051.7  301.38
  4174.8  295.81    4204  294.29  4303.6  290.68  4356.3  289.47  4432.5  289.06
  4508.7  288.42  4561.3  288.84    4661  288.95    4819  289.63  4931.9  287.91
  4947.8  286.84  4965.7  285.77  5000.9  284.69  5003.7  284.19  5006.9  284.69
  5090.6  288.04  5093.4  288.16  5112.9  288.79  5202.2  292.78  5599.3  303.63
  5725.1  309.26  5934.7  306.77  6158.3  316.07  6320.5  326.92  6485.4  331.27
#Mann= 19 ,-1 , 0
  3751.3     .05       0    4046     .08       0  4051.7     .05       0
  4174.8     .08       0    4204     .05       0  4303.6     .08       0
  4356.3     .05       0  4432.5     .08       0  4508.7     .05       0
  4561.3     .08       0    4661     .05       0    4819     .08       0
  4947.8     .05       0  4965.7     .08       0  5000.9     .07       0
  5006.9     .08       0  5093.4     .05       0  5112.9     .08       0
  5202.2     .05       0
Bank Sta=4931.9,5090.6
XS Rating Curve= 0 ,0
Exp/Cntr=0.3,0.1

Type RM Length L Ch R = 1 ,4203    ,622,622,622
BEGIN DESCRIPTION:
UNT001 IN SPCR 6.0
END DESCRIPTION:
XS GIS Cut Line= 3
      2204443.19     13272284.84      2204901.54     13271555.65
      2205630.65     13269701.64
#Sta/Elev= 30
  3636.4  318.76  4029.9  304.25  4160.6  302.83  4239.6  303.72  4312.6  300.61
  4385.6  293.39    4494  285.29  4559.2  286.24  4749.4  287.27  4828.2  287.74
  4926.2  286.36  4998.4  282.97  5001.2  282.47  5004.4  282.97  5070.3  286.15
    5073  286.28  5132.5  286.92  5194.8  285.14  5259.3  287.15  5403.5  287.53
  5635.4  293.12  5778.1  298.28  5901.3  302.13  6197.8  310.41  6302.7  314.05
    6361  315.65  6407.6  317.88  6462.8  319.71  6468.2   321.4  6489.9  322.79
#Mann= 13 ,-1 , 0
  3636.4     .05       0  4559.2      .1       0  4749.4     .05       0
  4828.2      .1       0  4998.4     .07       0  5004.4      .1       0
  5070.3     .05       0  5778.1     .08       0  5901.3     .05       0
  6197.8     .08       0  6302.7     .05       0    6361     .08       0
  6407.6     .05       0
Bank Sta=4926.2,5073
XS Rating Curve= 0 ,0
Exp/Cntr=0.3,0.1

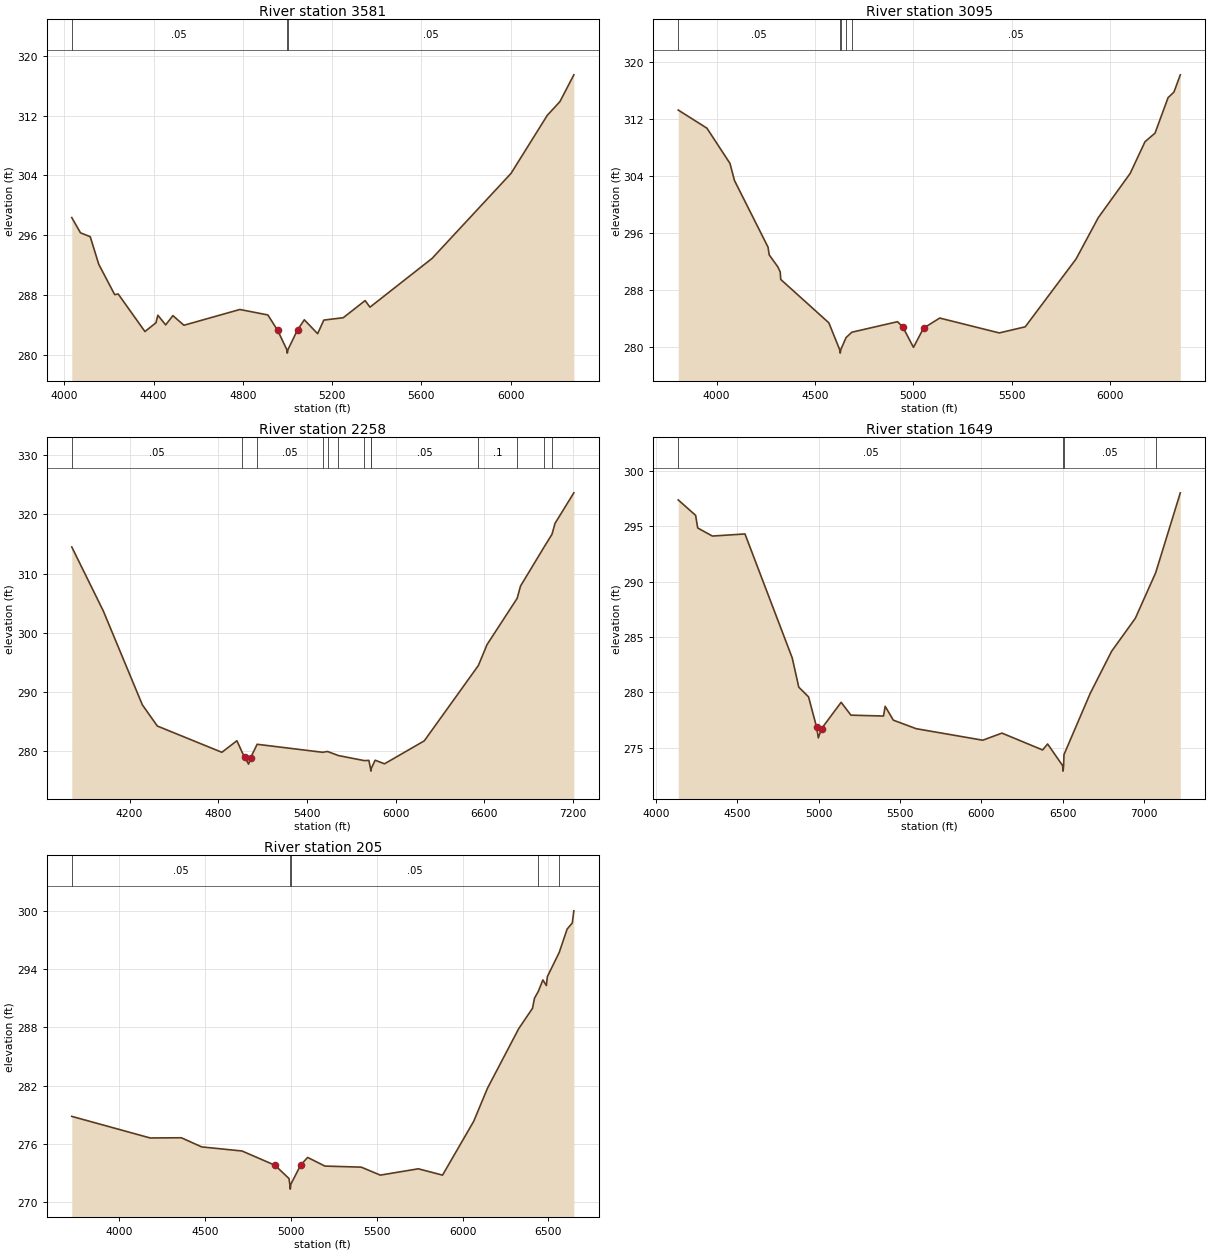
Type RM Length L Ch R = 1 ,3581    ,486,486,486
BEGIN DESCRIPTION:
UNT001 IN SPCR 5.0
END DESCRIPTION:
XS GIS Cut Line= 3
      2205173.79     13271855.77      2205816.18     13270675.18
      2206076.59     13269807.14
#Sta/Elev= 30
  4033.1  298.36  4072.2  296.32  4115.9   295.8  4153.9  292.12  4225.4  288.05
  4241.3  288.13    4361  283.11  4410.4  284.28  4418.9  285.29    4454     284
  4486.4  285.24  4535.7  283.95  4786.5  286.06  4911.9  285.33  4955.6  283.28
  4996.5  280.72  4999.3  280.22  5002.5  280.72  5045.1  283.33  5075.3  284.68
  5135.1  282.82  5162.7  284.64    5250  284.96  5347.9  287.25  5369.7  286.37
  5647.8  292.89  6001.8  304.27  6164.6  312.05  6221.1  313.88  6283.4  317.46
#Mann= 3 ,-1 , 0
  4033.1     .05       0  4996.5     .03       0  5002.5     .05       0
Bank Sta=4955.6,5045.1
XS Rating Curve= 0 ,0
Exp/Cntr=0.3,0.1

Type RM Length L Ch R = 1 ,3095    ,837,837,837
BEGIN DESCRIPTION:
UNT001 IN SPCR 4.0
END DESCRIPTION:
XS GIS Cut Line= 3
      2205196.63     13272182.49      2205652.33     13271935.11
       2206602.8     13270138.33
#Sta/Elev= 30
  3805.2   313.3    3951  310.75  4068.1   305.8  4090.9   303.4  4261.6  294.02
  4267.5  292.94  4311.2  291.26  4323.7  290.52    4326  289.49  4570.6  283.39
  4625.4  279.63  4628.2  279.13  4631.4  279.63  4657.8  281.31  4687.3  282.07
  4919.5  283.55  4947.2  282.76  5000.5  279.94  5051.6  282.64  5133.9  284.06
  5436.3  281.97  5568.4  282.83  5826.8  292.37  5939.5  298.17  6101.6  304.39
  6177.1  308.85  6227.9  310.05    6294  315.03  6324.1  315.83  6356.4  318.25
#Mann= 5 ,-1 , 0
  3805.2     .05       0  4625.4     .03       0  4631.4     .05       0
  4657.8      .1       0  4687.3     .05       0
Bank Sta=4947.2,5051.6
XS Rating Curve= 0 ,0
Exp/Cntr=0.3,0.1

Type RM Length L Ch R = 1 ,2258    ,609,609,609
BEGIN DESCRIPTION:
UNT001 IN SPCR 2.0
END DESCRIPTION:
XS GIS Cut Line= 3
      2205287.71     13272196.86      2206437.72     13271996.85
      2207987.69     13270396.89
#Sta/Elev= 30
  3809.6   314.5  4022.8  303.66  4286.7  287.76  4388.2  284.16  4824.6  279.71
  4926.1  281.67  4963.9   279.6  4980.4  278.85  5005.1   277.7  5019.2   278.8
    5063  281.07  5506.2  279.71  5538.9  279.85  5612.1  279.16  5787.9   278.3
  5818.4  278.34  5829.6  277.02  5832.3  276.52  5835.6  277.02  5860.9  278.37
  5924.4  277.76  6193.2  281.65  6558.5   294.4  6617.6  297.96  6821.1  305.79
  6843.8  307.87  7005.4  314.57  7056.6  316.64  7077.3   318.5  7204.5  323.67
#Mann= 13 ,-1 , 0
  3809.6     .05       0  4963.9      .1       0    5063     .05       0
  5506.2      .1       0  5538.9     .05       0  5612.1      .1       0
  5787.9     .05       0  5829.6     .07       0  5835.6     .05       0
  6558.5      .1       0  6821.1     .05       0  7005.4      .1       0
  7056.6     .05       0
Bank Sta=4980.4,5019.2
XS Rating Curve= 0 ,0
Exp/Cntr=0.3,0.1

Type RM Length L Ch R = 1 ,1649    ,1444,1444,1444
BEGIN DESCRIPTION:
Mapping XS e70d90c6
END DESCRIPTION:
XS GIS Cut Line= 3
      2205868.29     13272558.86      2207352.63     13272463.37
        2207951.     13270980.46
#Sta/Elev= 30
  4135.9  297.37  4242.8  295.98  4255.6  294.84  4345.8  294.11  4546.2   294.3
  4836.8  283.11  4876.9  280.48    4937   279.6  4987.1  276.84  4997.1   275.9
  5017.2  276.74  5137.4  279.11  5197.5  277.95  5397.9  277.87    5408  278.75
  5458.1   277.5  5598.4  276.73  6007.8  275.69  6126.1  276.33  6375.8  274.81
  6406.7  275.35  6498.9   273.4  6501.7   272.9  6504.9   273.4  6507.3  274.39
  6668.4  279.91  6799.9  283.71  6945.9  286.69    7071   290.8  7222.4  298.01
#Mann= 4 ,-1 , 0
  4135.9     .05       0  6498.9     .03       0  6504.9     .05       0
    7071      .1       0
Bank Sta=4987.1,5017.2
XS Rating Curve= 0 ,0
Exp/Cntr=0.3,0.1

Type RM Length L Ch R = 1 ,205     ,0,0,0
BEGIN DESCRIPTION:
UNT001 IN SPCR 1.0
END DESCRIPTION:
XS GIS Cut Line= 3
      2206805.78     13273001.56        2207995.     13272827.95
      2208212.01     13271117.89
#Sta/Elev= 30
  3723.2  278.85  4179.9  276.63  4361.8  276.65  4480.4  275.71  4715.5  275.29
  4907.6  273.82    4989  272.46  4993.7  271.87  4996.4  271.37  4999.7  271.87
  5057.2  273.85  5097.5  274.63  5198.3  273.74    5410  273.63  5520.9  272.81
  5742.6  273.46  5883.7  272.81  6065.2  278.34  6145.8  281.75  6327.3  287.86
  6407.9  289.96  6419.6     291  6442.1  291.71  6468.4  292.88  6488.6   292.3
  6494.6  293.22  6563.8  295.71  6609.5   298.1  6639.8  298.73  6648.8  299.98
#Mann= 5 ,-1 , 0
  3723.2     .05       0  4993.7     .03       0  4999.7     .05       0
  6442.1      .1       0  6563.8     .05       0
Bank Sta=4907.6,5057.2
XS Rating Curve= 0 ,0
Exp/Cntr=0.3,0.1

Chan Stop Cuts=-1
Use User Specified Reach Order=0
Composite Channel Slope=5