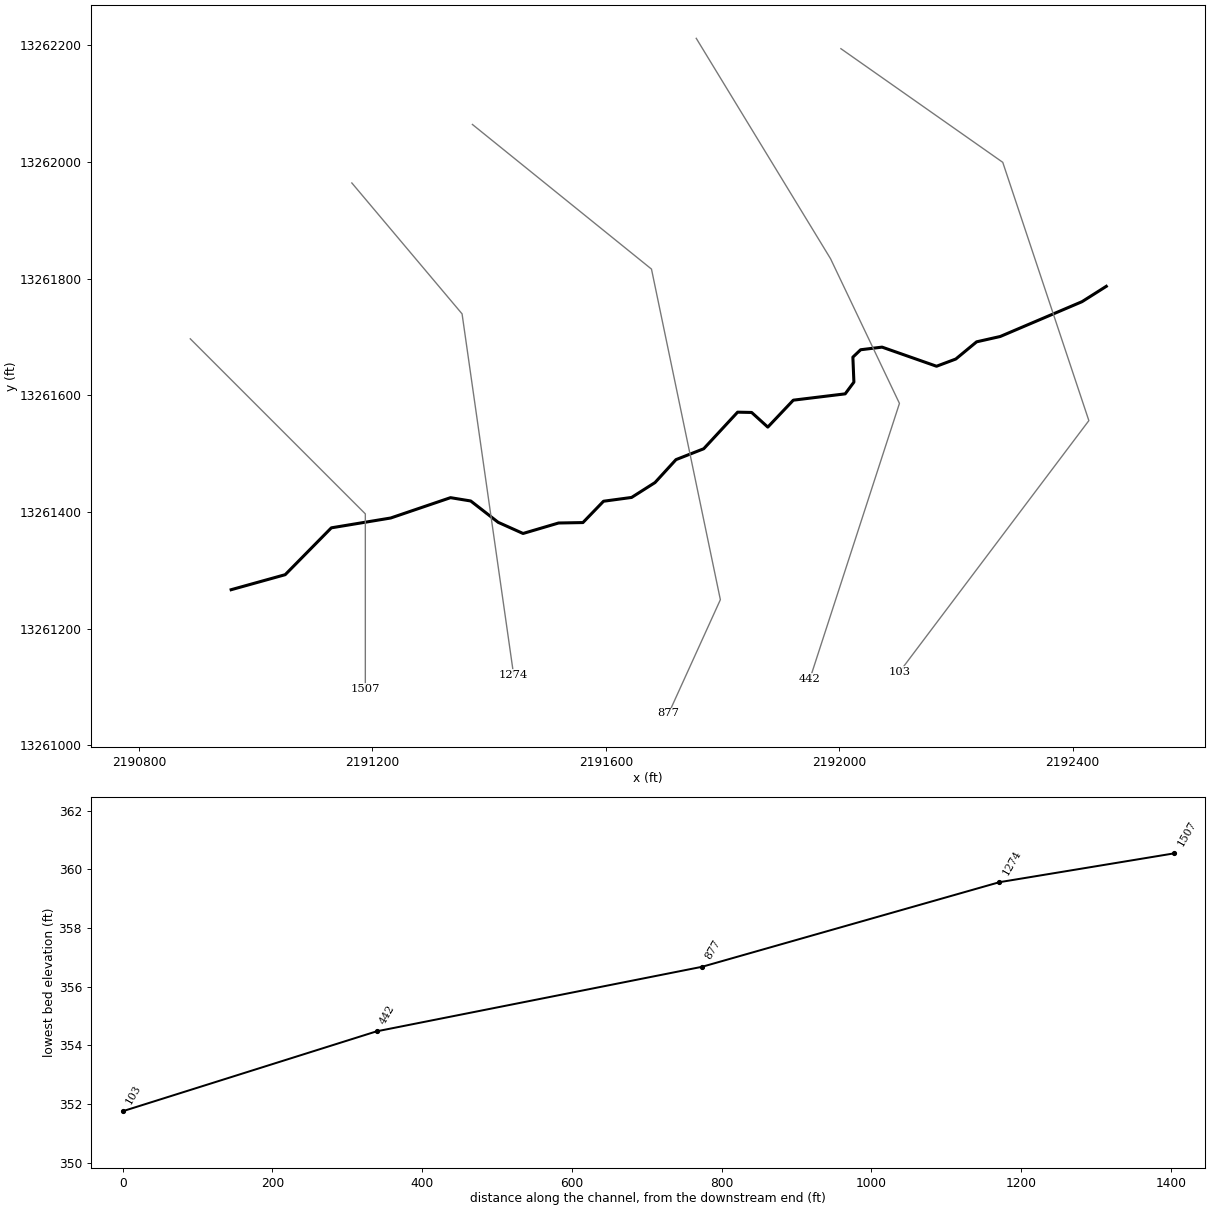
--- UNT002 IN SPCR.prj (project) ---

Proj Title=UNT002 IN SPCR Base Level Engineering
Current Plan=p01
Default Exp/Contr=0.3,0.1
English Units
Geom File=g01
Flow File=f01
Plan File=p01
BEGIN DESCRIPTION:
UNT002 IN SPCR
END DESCRIPTION:

--- UNT002 IN SPCR.p01 (plan) ---

Plan Title=Multiple Run
Short Identifier=Multiple
Geom File=g01
Flow File=f01
Subcritical Flow
K Sum by GR= 0
Std Step Tol= 0.01
Critical Tol= 0.01
Num of Std Step Trials= 20
Max Error Tol= 0.3
Flow Tol Ratio= 0.001
Split Flow NTrial= 30
Split Flow Tol= 0.02
Split Flow Ratio= 0.02
Log Output Level= 0
Friction Slope Method= 1
Unsteady Friction Slope Method= 2
Unsteady Bridges Friction Slope Method= 1
Parabolic Critical Depth
Global Vel Dist=  1 , 1 , 1
Global Log Level= 0
CheckData=True
Encroach Param= -1, 0, 0, 0
BEGIN DESCRIPTION:
Multiple Run
END DESCRIPTION:

--- UNT002 IN SPCR.f01 (steady flow) ---

Flow Title=Multiple
Number of Profiles=7
Profile Names=10-year,25-year,50-year,1pct_min,100-year,1pct_plu,500-year
River Rch & RM= UNT002 IN SPCR,Reach-1,1507
     233     329     409     376     508     688     796
Boundary for River Rch & Prof#=UNT002 IN SPCR,Reach-1,1
Up Type=0
Dn Type=3
Dn Slope=0.005
Boundary for River Rch & Prof#=UNT002 IN SPCR,Reach-1,2
Up Type=0
Dn Type=3
Dn Slope=0.005
Boundary for River Rch & Prof#=UNT002 IN SPCR,Reach-1,3
Up Type=0
Dn Type=3
Dn Slope=0.005
Boundary for River Rch & Prof#=UNT002 IN SPCR,Reach-1,4
Up Type=0
Dn Type=3
Dn Slope=0.005
Boundary for River Rch & Prof#=UNT002 IN SPCR,Reach-1,5
Up Type=0
Dn Type=3
Dn Slope=0.005
Boundary for River Rch & Prof#=UNT002 IN SPCR,Reach-1,6
Up Type=0
Dn Type=3
Dn Slope=0.005
Boundary for River Rch & Prof#=UNT002 IN SPCR,Reach-1,7
Up Type=0
Dn Type=3
Dn Slope=0.005

--- UNT002 IN SPCR.g01 (geometry) ---

Geom Title=Existing Conditions

River Reach=UNT002 IN SPCR,Reach-1
Reach XY= 30
      2190957.72     13261266.85      2191050.39     13261292.61
      2191129.46     13261372.90      2191231.22     13261389.75
      2191333.74     13261424.61      2191368.36     13261418.93
      2191415.41     13261382.34      2191458.06     13261363.23
      2191518.93     13261381.18      2191560.68     13261381.93
      2191596.01     13261418.50      2191644.09     13261424.99
      2191684.23     13261450.51      2191720.18     13261489.81
      2191767.72     13261508.45      2191825.79     13261571.15
      2191849.87     13261570.66      2191877.54     13261545.53
      2191921.25     13261591.71      2192010.19     13261602.55
      2192025.12     13261622.64      2192023.36     13261665.45
      2192036.67     13261678.14      2192073.40     13261682.63
      2192166.75     13261649.87      2192199.79     13261662.25
      2192235.45     13261691.72      2192275.98     13261700.87
      2192416.18     13261760.56      2192457.72     13261786.85

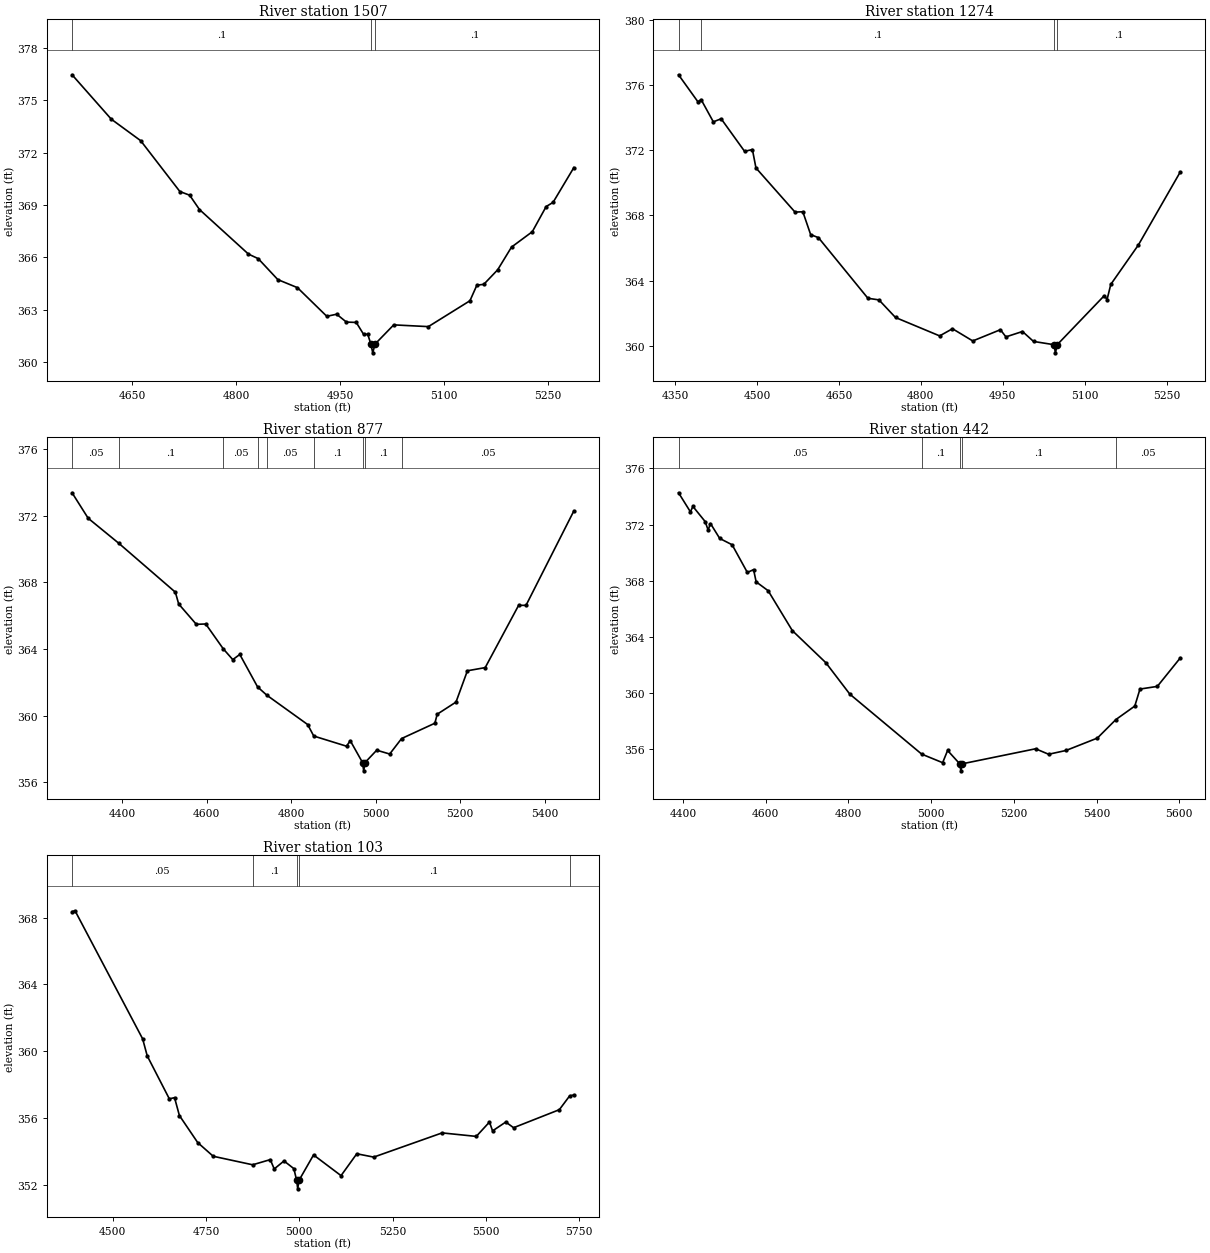
Type RM Length L Ch R = 1,1507,233,233,233
BEGIN DESCRIPTION:
UNT002 IN SPCR 3.0
END DESCRIPTION:
XS GIS Cut Line= 3
      2190887.70     13261696.87      2191187.72     13261396.85
      2191187.72     13261096.85
#Sta/Elev= 30
  4563.3  376.45  4619.9  373.91  4662.3  372.68  4718.9  369.77  4733.0  369.56
  4747.2  368.74  4817.9  366.19  4832.0  365.93  4860.3  364.73  4888.6  364.27
  4931.0  362.63  4945.2  362.75  4959.3  362.30  4973.5  362.28  4984.1  361.60
  4990.1  361.60  4994.6  361.04  4997.3  360.54  5000.6  361.04  5027.6  362.14
  5077.6  362.04  5137.6  363.52  5147.6  364.41  5157.6  364.46  5177.6  365.29
  5197.6  366.59  5227.6  367.47  5247.6  368.91  5257.6  369.15  5287.6  371.14
#Mann=3,-1,0
  4563.3     0.1       0  4994.6    0.07       0  5000.6     0.1       0
Bank Sta=4994.6,5000.6
Exp/Cntr=0.3,0.1

Type RM Length L Ch R = 1,1274,397,397,397
BEGIN DESCRIPTION:
Mapping XS 3a71195e
END DESCRIPTION:
XS GIS Cut Line= 3
      2191164.61     13261963.99      2191353.53     13261739.65
      2191441.93     13261120.82
#Sta/Elev= 30
  4356.5  376.63  4392.0  374.97  4397.8  375.11  4420.2  373.74  4434.5  373.93
  4477.4  371.93  4491.7  372.04  4498.2  370.91  4569.7  368.20  4584.0  368.22
  4598.3  366.82  4612.6  366.63  4703.1  362.91  4723.3  362.81  4753.6  361.73
  4834.4  360.60  4857.9  361.04  4895.0  360.29  4945.6  360.98  4955.7  360.54
  4986.0  360.87  5006.2  360.26  5043.6  360.06  5046.3  359.56  5049.6  360.06
  5135.7  363.07  5140.8  362.83  5147.6  363.76  5198.1  366.18  5274.9  370.67
#Mann=4,-1,0
  4356.5    0.05       0  4397.8     0.1       0  5043.6    0.07       0
  5049.6     0.1       0
Bank Sta=5043.6,5049.6
Exp/Cntr=0.3,0.1

Type RM Length L Ch R = 1,877,435,435,435
BEGIN DESCRIPTION:
UNT002 IN SPCR 2.0
END DESCRIPTION:
XS GIS Cut Line= 4
      2191371.24     13262064.30      2191678.18     13261816.38
      2191796.24     13261249.72      2191707.68     13261054.89
#Sta/Elev= 30
  4281.5  373.38  4319.6  371.85  4392.4  370.34  4525.9  367.41  4533.8  366.70
  4575.5  365.48  4597.8  365.50  4639.2  364.01  4661.8  363.36  4678.4  363.67
  4720.5  361.72  4742.5  361.22  4839.0  359.46  4853.4  358.77  4930.9  358.16
  4939.8  358.49  4968.8  357.18  4971.6  356.68  4974.8  357.18  5002.4  357.92
  5033.1  357.69  5061.3  358.62  5140.0  359.54  5145.5  360.08  5190.0  360.81
  5217.0  362.69  5259.1  362.88  5338.2  366.62  5355.7  366.62  5468.9  372.29
#Mann=9,-1,0
  4281.5    0.05       0  4392.4     0.1       0  4639.2    0.05       0
  4720.5     0.1       0  4742.5    0.05       0  4853.4     0.1       0
  4968.8    0.07       0  4974.8     0.1       0  5061.3    0.05       0
Bank Sta=4968.8,4974.8
Exp/Cntr=0.3,0.1

Type RM Length L Ch R = 1,442,339,339,339
BEGIN DESCRIPTION:
Mapping XS 31cb2cde
END DESCRIPTION:
XS GIS Cut Line= 4
      2191754.91     13262211.89      2191985.13     13261834.09
      2192103.18     13261586.18      2191949.72     13261113.99
#Sta/Elev= 30
  4389.2  374.27  4418.0  372.91  4423.9  373.30  4453.6  372.22  4460.7  371.62
  4466.5  372.08  4488.8  371.02  4518.8  370.57  4555.6  368.60  4570.7  368.80
  4576.9  367.93  4605.9  367.30  4664.4  364.46  4745.3  362.18  4803.4  359.94
  4977.2  355.67  5027.9  355.06  5039.9  355.93  5069.2  354.98  5072.0  354.48
  5075.2  354.98  5252.7  356.05  5284.2  355.66  5326.3  355.93  5402.0  356.81
  5446.9  358.13  5492.6  359.09  5505.1  360.30  5547.1  360.49  5602.7  362.52
#Mann=5,-1,0
  4389.2    0.05       0  4977.2     0.1       0  5069.2    0.07       0
  5075.2     0.1       0  5446.9    0.05       0
Bank Sta=5069.2,5075.2
Exp/Cntr=0.3,0.1

Type RM Length L Ch R = 1,103,0,0,0
BEGIN DESCRIPTION:
UNT002 IN SPCR 1.0
END DESCRIPTION:
XS GIS Cut Line= 4
      2192002.87     13262194.13      2192280.26     13261999.37
      2192427.83     13261556.66      2192103.19     13261125.77
#Sta/Elev= 30
  4390.9  368.36  4398.9  368.41  4580.1  360.74  4592.4  359.72  4651.6  357.15
  4665.6  357.22  4678.6  356.15  4727.7  354.53  4769.3  353.71  4875.0  353.20
  4922.2  353.51  4932.8  352.95  4959.0  353.43  4985.4  352.97  4993.0  352.26
  4995.8  351.76  4999.0  352.26  5038.2  353.79  5111.9  352.55  5154.1  353.86
  5199.5  353.66  5382.8  355.11  5474.4  354.90  5509.8  355.76  5518.1  355.23
  5553.5  355.76  5574.4  355.42  5697.1  356.50  5724.5  357.32  5736.0  357.38
#Mann=5,-1,0
  4390.9    0.05       0  4875.0     0.1       0  4993.0    0.07       0
  4999.0     0.1       0  5724.5    0.05       0
Bank Sta=4993,4999
Exp/Cntr=0.3,0.1

Chan Stop Cuts=-1