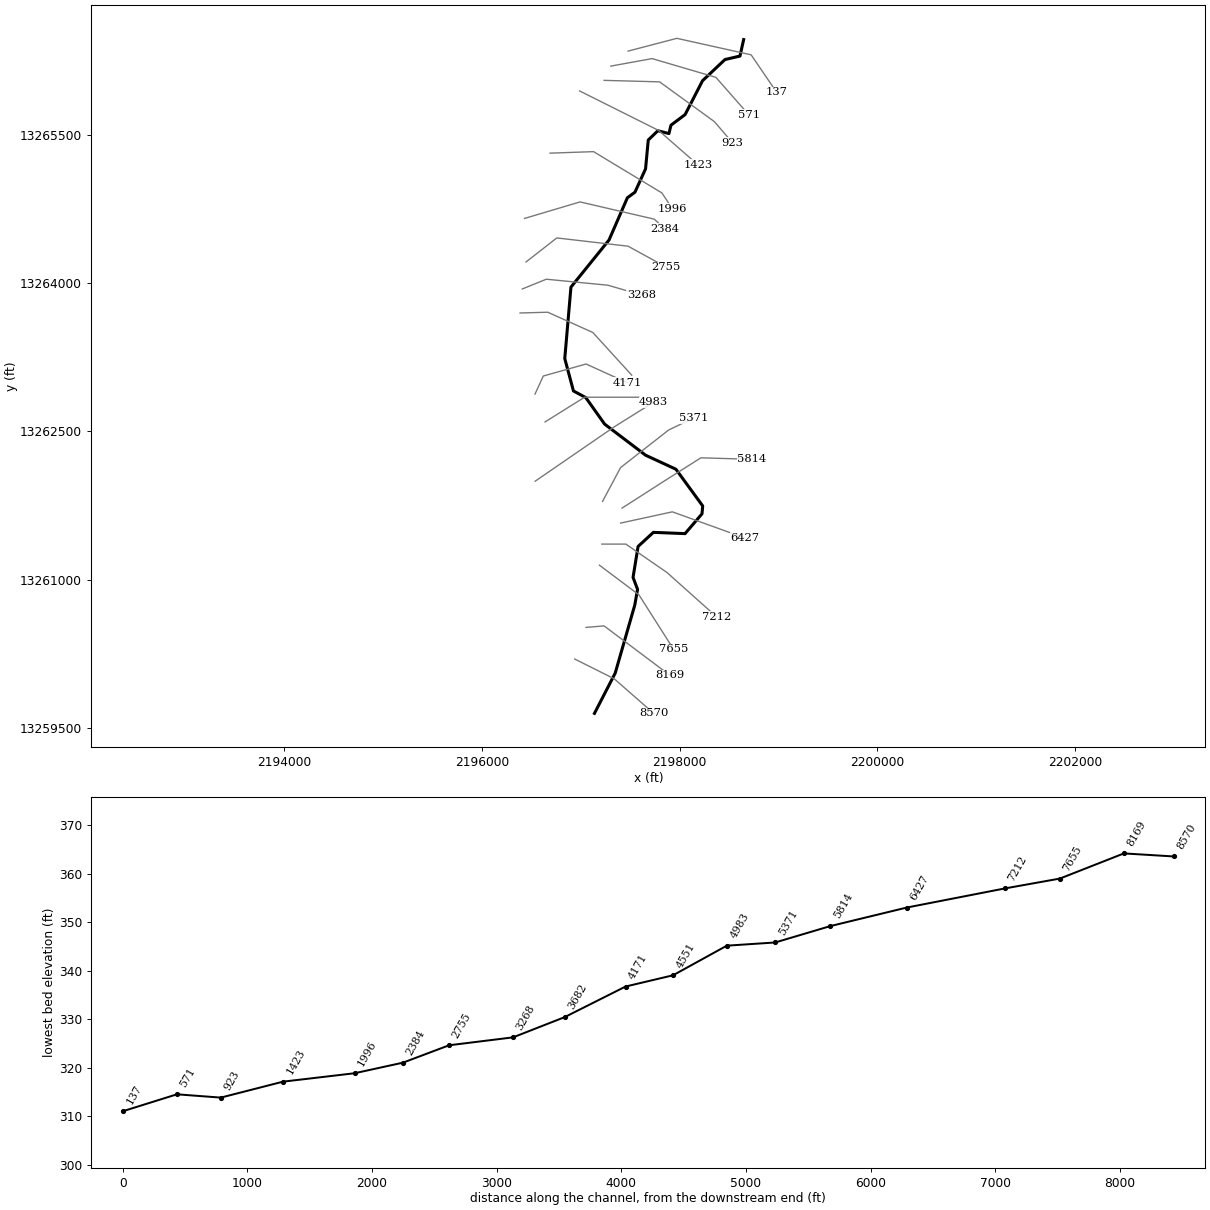
--- UNT003 IN SPCR.prj (project) ---

Proj Title=UNT003 IN SPCR Base Level Engineering
Current Plan=p01
Default Exp/Contr=0.3,0.1
English Units
Geom File=g01
Flow File=f01
Plan File=p01
BEGIN DESCRIPTION:
UNT003 IN SPCR
END DESCRIPTION:

--- UNT003 IN SPCR.p01 (plan) ---

Plan Title=Multiple Run
Short Identifier=Multiple
Geom File=g01
Flow File=f01
Subcritical Flow
K Sum by GR= 0
Std Step Tol= 0.01
Critical Tol= 0.01
Num of Std Step Trials= 20
Max Error Tol= 0.3
Flow Tol Ratio= 0.001
Split Flow NTrial= 30
Split Flow Tol= 0.02
Split Flow Ratio= 0.02
Log Output Level= 0
Friction Slope Method= 1
Unsteady Friction Slope Method= 2
Unsteady Bridges Friction Slope Method= 1
Parabolic Critical Depth
Global Vel Dist=  1 , 1 , 1
Global Log Level= 0
CheckData=True
Encroach Param= -1, 0, 0, 0
BEGIN DESCRIPTION:
Multiple Run
END DESCRIPTION:

--- UNT003 IN SPCR.f01 (steady flow) ---

Flow Title=Multiple
Number of Profiles=7
Profile Names=10-year,25-year,50-year,1pct_min,100-year,1pct_plu,500-year
River Rch & RM= UNT003 IN SPCR,Reach-1,8570
     352     504     633     585     791    1070    1257
Boundary for River Rch & Prof#=UNT003 IN SPCR,Reach-1,1
Up Type=0
Dn Type=3
Dn Slope=0.005
Boundary for River Rch & Prof#=UNT003 IN SPCR,Reach-1,2
Up Type=0
Dn Type=3
Dn Slope=0.005
Boundary for River Rch & Prof#=UNT003 IN SPCR,Reach-1,3
Up Type=0
Dn Type=3
Dn Slope=0.005
Boundary for River Rch & Prof#=UNT003 IN SPCR,Reach-1,4
Up Type=0
Dn Type=3
Dn Slope=0.005
Boundary for River Rch & Prof#=UNT003 IN SPCR,Reach-1,5
Up Type=0
Dn Type=3
Dn Slope=0.005
Boundary for River Rch & Prof#=UNT003 IN SPCR,Reach-1,6
Up Type=0
Dn Type=3
Dn Slope=0.005
Boundary for River Rch & Prof#=UNT003 IN SPCR,Reach-1,7
Up Type=0
Dn Type=3
Dn Slope=0.005

--- UNT003 IN SPCR.g01 (geometry) ---

Geom Title=Existing Conditions

River Reach=UNT003 IN SPCR,Reach-1
Reach XY= 30
      2197137.72     13259646.85      2197347.68     13260054.40
      2197545.69     13260742.64      2197574.03     13260902.00
      2197528.26     13261023.14      2197579.23     13261336.27
      2197734.18     13261479.08      2198054.56     13261466.15
      2198226.24     13261666.67      2198233.33     13261746.36
      2197962.28     13262118.03      2197656.00     13262259.47
      2197240.74     13262574.54      2197050.02     13262842.96
      2196925.00     13262910.33      2196837.19     13263238.23
      2196899.73     13263961.34      2197285.04     13264438.05
      2197470.87     13264865.47      2197547.47     13264921.73
      2197654.90     13265158.16      2197682.11     13265449.81
      2197779.27     13265544.01      2197891.60     13265515.46
      2197911.91     13265600.06      2198055.24     13265707.72
      2198231.77     13266050.55      2198458.69     13266264.66
      2198610.55     13266299.93      2198647.72     13266466.86

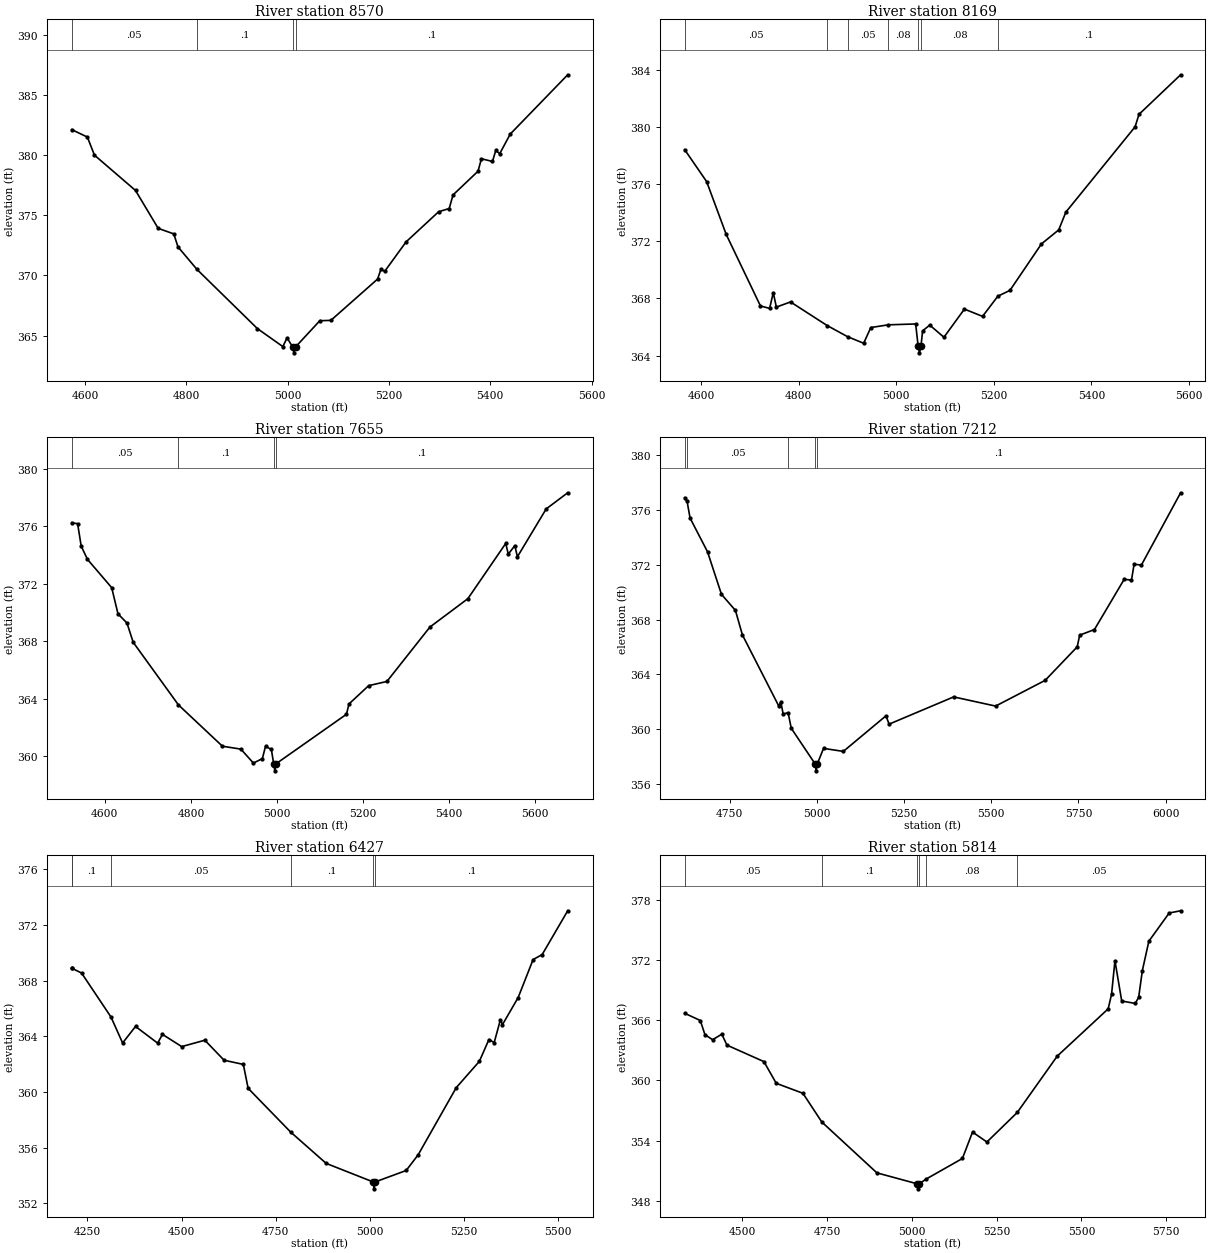
Type RM Length L Ch R = 1,8570,401,401,401
BEGIN DESCRIPTION:
UNT003 IN SPCR 18.0
END DESCRIPTION:
XS GIS Cut Line= 3
      2196937.71     13260196.86      2197337.72     13259996.85
      2197737.70     13259646.87
#Sta/Elev= 30
  4574.1  382.12  4604.9  381.50  4618.8  380.00  4699.9  377.06  4744.6  373.91
  4775.4  373.45  4783.7  372.37  4821.1  370.50  4940.3  365.58  4990.6  364.08
  4999.0  364.80  5009.9  364.06  5012.7  363.56  5015.9  364.06  5063.6  366.23
  5085.4  366.26  5177.5  369.69  5184.1  370.49  5191.7  370.34  5233.9  372.79
  5298.0  375.29  5318.9  375.56  5326.5  376.69  5375.8  378.66  5382.5  379.70
  5404.3  379.47  5410.9  380.40  5418.5  380.11  5439.4  381.75  5552.8  386.68
#Mann=4,-1,0
  4574.1    0.05       0  4821.1     0.1       0  5009.9    0.07       0
  5015.9     0.1       0
Bank Sta=5009.9,5015.9
Exp/Cntr=0.3,0.1

Type RM Length L Ch R = 1,8169,514,514,514
BEGIN DESCRIPTION:
UNT003 IN SPCR 17.0
END DESCRIPTION:
XS GIS Cut Line= 3
      2197052.85     13260517.08      2197235.09     13260532.27
      2197902.48     13260031.73
#Sta/Elev= 30
  4565.9  378.40  4610.9  376.17  4651.1  372.47  4721.3  367.47  4740.1  367.30
  4747.6  368.40  4753.9  367.39  4783.0  367.75  4858.1  366.10  4900.0  365.32
  4933.0  364.86  4947.6  365.96  4983.7  366.15  5039.6  366.21  5044.6  364.69
  5047.4  364.19  5050.6  364.69  5053.9  365.73  5068.5  366.13  5097.6  365.28
  5139.6  367.25  5176.8  366.74  5208.1  368.15  5233.0  368.56  5297.6  371.81
  5333.0  372.79  5347.6  374.03  5489.6  380.00  5497.6  380.87  5583.0  383.64
#Mann=7,-1,0
  4565.9    0.05       0  4858.1    0.08       0  4900.0    0.05       0
  4983.7    0.08       0  5044.6    0.07       0  5050.6    0.08       0
  5208.1     0.1       0
Bank Sta=5044.6,5050.6
Exp/Cntr=0.3,0.1

Type RM Length L Ch R = 1,7655,443,443,443
BEGIN DESCRIPTION:
UNT003 IN SPCR 16.0
END DESCRIPTION:
XS GIS Cut Line= 3
      2197187.69     13261146.88      2197587.72     13260846.85
      2197937.74     13260296.82
#Sta/Elev= 30
  4523.2  376.24  4536.8  376.17  4545.1  374.61  4559.7  373.69  4615.9  371.73
  4630.5  369.91  4651.4  369.27  4665.9  367.93  4771.0  363.58  4873.2  360.71
  4915.9  360.51  4945.1  359.54  4965.9  359.85  4973.2  360.70  4986.8  360.49
  4992.1  359.50  4994.9  359.00  4998.1  359.50  5161.2  362.93  5167.2  363.65
  5212.9  364.92  5255.2  365.21  5355.1  368.99  5443.2  370.96  5531.2  374.80
  5537.2  374.06  5552.4  374.65  5558.3  373.87  5625.2  377.20  5675.2  378.32
#Mann=4,-1,0
  4523.2    0.05       0  4771.0     0.1       0  4992.1    0.07       0
  4998.1     0.1       0
Bank Sta=4992.1,4998.1
Exp/Cntr=0.3,0.1

Type RM Length L Ch R = 1,7212,785,785,785
BEGIN DESCRIPTION:
UNT003 IN SPCR 15.0
END DESCRIPTION:
XS GIS Cut Line= 4
      2197212.26     13261360.15      2197455.35     13261360.15
      2197873.09     13261071.53      2198373.54     13260624.16
#Sta/Elev= 30
  4620.8  376.91  4627.6  376.66  4636.3  375.42  4686.3  372.96  4726.3  369.85
  4766.3  368.68  4786.3  366.89  4890.5  361.70  4896.6  361.98  4903.2  361.11
  4917.4  361.21  4926.4  360.07  4995.0  357.46  4997.8  356.96  5001.0  357.46
  5019.0  358.60  5075.7  358.38  5198.1  360.98  5206.9  360.37  5392.1  362.36
  5512.4  361.69  5654.5  363.57  5746.5  366.02  5753.4  366.87  5795.8  367.28
  5881.1  370.95  5902.0  370.89  5909.5  372.05  5930.4  371.99  6042.9  377.27
#Mann=5,-1,0
  4620.8     0.1       0  4627.6    0.05       0  4917.4     0.1       0
  4995.0    0.07       0  5001.0     0.1       0
Bank Sta=4995,5001
Exp/Cntr=0.3,0.1

Type RM Length L Ch R = 1,6427,613,613,613
BEGIN DESCRIPTION:
UNT003 IN SPCR 14.0
END DESCRIPTION:
XS GIS Cut Line= 3
      2197402.20     13261572.82      2197926.26     13261686.74
      2198661.56     13261421.43
#Sta/Elev= 30
  4208.3  368.91  4209.1  368.89  4234.4  368.55  4312.5  365.39  4343.4  363.52
  4377.7  364.71  4436.5  363.51  4449.3  364.14  4500.5  363.26  4561.9  363.72
  4613.1  362.28  4664.2  361.98  4677.0  360.26  4790.1  357.11  4884.4  354.86
  5008.9  353.53  5011.7  353.03  5014.9  353.53  5097.0  354.35  5128.9  355.48
  5230.1  360.31  5291.5  362.20  5316.9  363.77  5330.9  363.55  5347.5  365.20
  5352.9  364.84  5394.6  366.79  5434.3  369.52  5458.4  369.88  5526.3  373.03
#Mann=6,-1,0
  4208.3    0.05       0  4209.1     0.1       0  4312.5    0.05       0
  4790.1     0.1       0  5008.9    0.07       0  5014.9     0.1       0
Bank Sta=5008.9,5014.9
Exp/Cntr=0.3,0.1

Type RM Length L Ch R = 1,5814,443,443,443
BEGIN DESCRIPTION:
UNT003 IN SPCR 13.0
END DESCRIPTION:
XS GIS Cut Line= 4
      2197417.42     13261724.75      2197819.93     13261982.96
      2198214.88     13262233.60      2198731.37     13262218.41
#Sta/Elev= 30
  4329.9  366.68  4376.0  365.96  4389.7  364.55  4412.3  364.05  4439.4  364.60
  4454.6  363.51  4563.6  361.87  4600.0  359.71  4678.6  358.72  4734.4  355.86
  4896.8  350.80  5015.7  349.71  5018.4  349.21  5021.7  349.71  5042.9  350.20
  5149.0  352.23  5178.9  354.86  5221.3  353.87  5310.8  356.81  5428.8  362.42
  5578.9  367.12  5588.9  368.57  5598.9  371.91  5618.9  367.90  5658.9  367.66
  5668.9  368.28  5679.7  370.92  5698.9  373.85  5758.9  376.66  5792.6  376.88
#Mann=6,-1,0
  4329.9    0.05       0  4734.4     0.1       0  5015.7    0.07       0
  5021.7     0.1       0  5042.9    0.08       0  5310.8    0.05       0
Bank Sta=5015.7,5021.7
Exp/Cntr=0.3,0.1

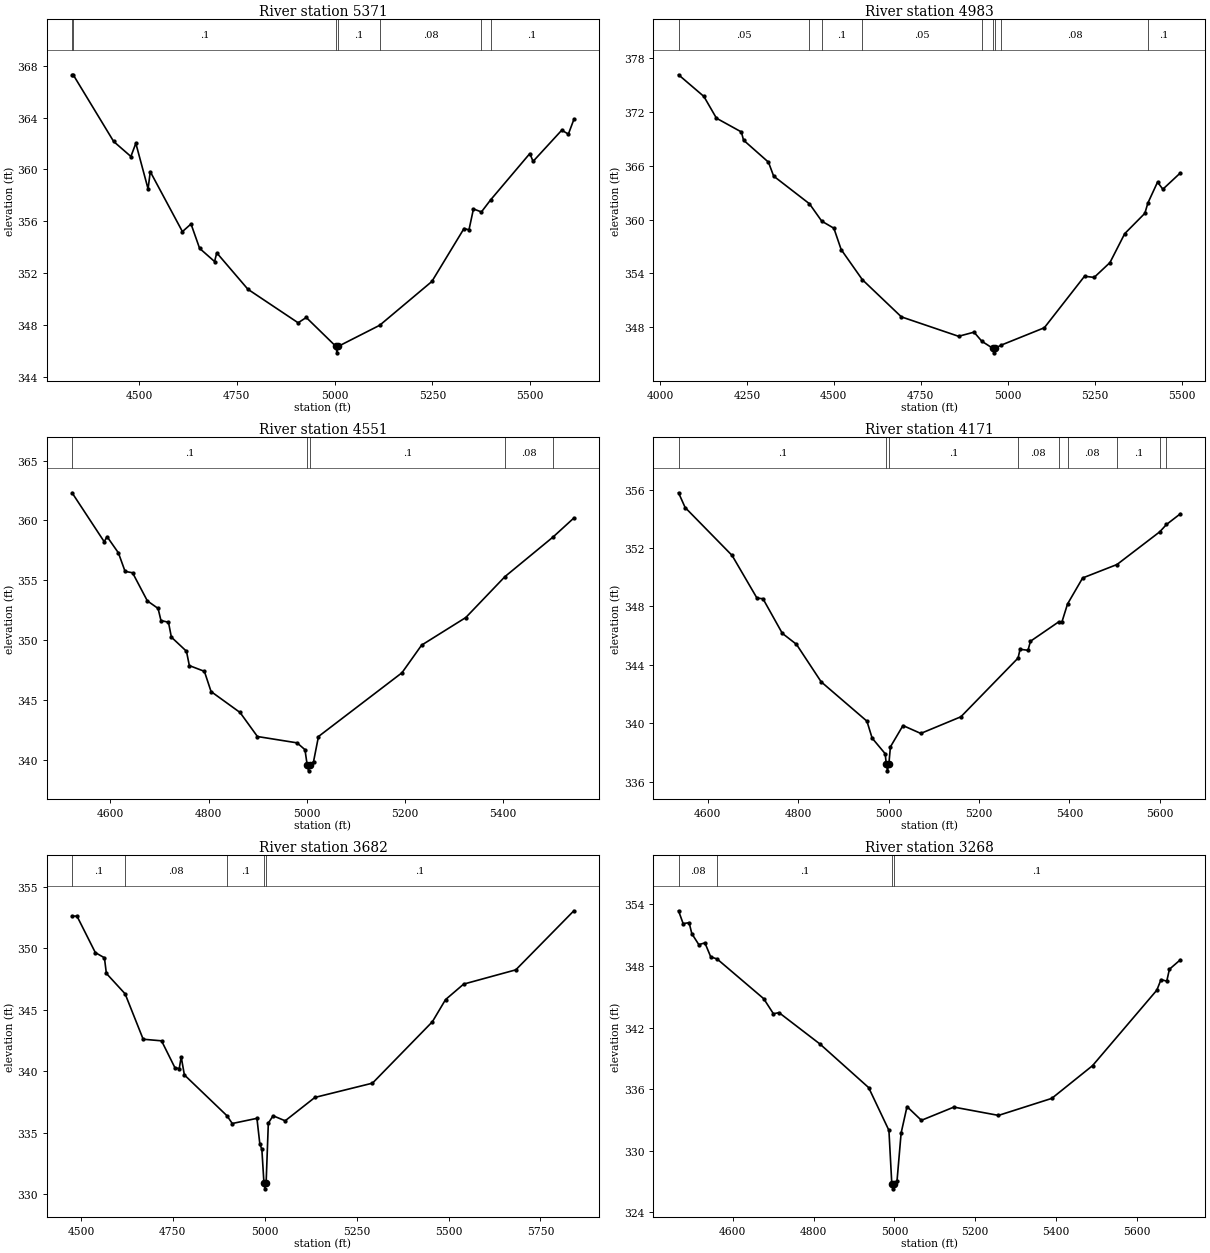
Type RM Length L Ch R = 1,5371,388,388,388
BEGIN DESCRIPTION:
UNT003 IN SPCR 12.0
END DESCRIPTION:
XS GIS Cut Line= 4
      2197219.90     13261793.07      2197402.19     13262134.86
      2197888.28     13262514.63      2198138.95     13262636.16
#Sta/Elev= 30
  4329.0  367.30  4332.1  367.29  4435.3  362.15  4479.4  360.99  4492.0  362.01
  4523.3  358.49  4528.9  359.82  4611.1  355.19  4633.1  355.78  4655.0  353.90
  4693.3  352.88  4698.9  353.55  4778.5  350.74  4906.9  348.15  4927.7  348.56
  5003.4  346.33  5006.1  345.83  5009.4  346.33  5115.5  347.96  5248.8  351.34
  5331.0  355.43  5343.7  355.33  5355.1  356.94  5375.5  356.71  5399.0  357.64
  5499.3  361.22  5507.5  360.61  5580.8  363.02  5597.8  362.72  5611.8  363.85
#Mann=7,-1,0
  4329.0    0.05       0  4332.1     0.1       0  5003.4    0.07       0
  5009.4     0.1       0  5115.5    0.08       0  5375.5    0.05       0
  5399.0     0.1       0
Bank Sta=5003.4,5009.4
Exp/Cntr=0.3,0.1

Type RM Length L Ch R = 1,4983,432,432,432
BEGIN DESCRIPTION:
UNT003 IN SPCR 11.0
END DESCRIPTION:
XS GIS Cut Line= 3
      2196537.69     13261996.83      2197337.72     13262546.85
      2197737.75     13262796.87
#Sta/Elev= 30
  4053.6  376.10  4126.5  373.69  4162.6  371.27  4234.3  369.74  4240.4  368.83
  4312.1  366.38  4327.0  364.83  4430.0  361.75  4465.3  359.82  4500.2  359.03
  4521.1  356.66  4582.0  353.31  4694.3  349.17  4858.7  347.01  4903.1  347.47
  4925.5  346.46  4957.2  345.67  4960.0  345.17  4963.2  345.67  4982.0  346.04
  5105.2  347.96  5220.8  353.69  5248.5  353.56  5293.9  355.21  5336.4  358.43
  5394.2  360.69  5403.0  361.84  5430.7  364.16  5446.0  363.37  5496.2  365.18
#Mann=9,-1,0
  4053.6    0.05       0  4430.0    0.08       0  4465.3     0.1       0
  4582.0    0.05       0  4925.5     0.1       0  4957.2    0.07       0
  4963.2     0.1       0  4982.0    0.08       0  5403.0     0.1       0
Bank Sta=4957.2,4963.2
Exp/Cntr=0.3,0.1

Type RM Length L Ch R = 1,4551,380,380,380
BEGIN DESCRIPTION:
UNT003 IN SPCR 10.0
END DESCRIPTION:
XS GIS Cut Line= 3
      2196637.73     13262596.86      2197037.72     13262846.85
      2197587.73     13262846.85
#Sta/Elev= 30
  4522.2  362.31  4587.6  358.22  4593.5  358.64  4616.5  357.29  4630.1  355.74
  4645.4  355.62  4675.5  353.27  4697.3  352.64  4703.2  351.63  4718.5  351.48
  4724.4  350.24  4755.1  349.06  4761.0  347.86  4791.6  347.38  4805.2  345.69
  4864.2  343.94  4899.6  341.93  4980.3  341.40  4996.4  340.83  5000.9  339.56
  5003.6  339.06  5006.9  339.56  5013.9  339.84  5023.9  341.93  5193.9  347.26
  5233.9  349.57  5323.9  351.88  5403.6  355.30  5501.8  358.62  5543.9  360.20
#Mann=5,-1,0
  4522.2     0.1       0  5000.9    0.07       0  5006.9     0.1       0
  5403.6    0.08       0  5501.8     0.1       0
Bank Sta=5000.9,5006.9
Exp/Cntr=0.3,0.1

Type RM Length L Ch R = 1,4171,489,489,489
BEGIN DESCRIPTION:
UNT003 IN SPCR 9.0
END DESCRIPTION:
XS GIS Cut Line= 4
      2196536.33     13262879.19      2196619.88     13263061.48
      2197052.81     13263183.01      2197470.58     13262993.11
#Sta/Elev= 30
  4535.9  355.78  4550.5  354.77  4654.3  351.49  4709.3  348.57  4722.5  348.53
  4765.3  346.16  4796.5  345.41  4851.2  342.84  4952.3  340.15  4963.8  338.99
  4992.7  337.92  4994.9  337.25  4997.7  336.75  5000.9  337.25  5004.2  338.39
  5032.0  339.85  5071.3  339.31  5160.0  340.45  5286.4  344.47  5290.7  345.07
  5308.3  345.00  5313.8  345.62  5375.9  346.94  5383.0  346.91  5395.7  348.17
  5429.1  349.95  5505.0  350.87  5599.6  353.11  5614.4  353.61  5645.0  354.34
#Mann=9,-1,0
  4535.9     0.1       0  4994.9    0.07       0  5000.9     0.1       0
  5286.4    0.08       0  5375.9     0.1       0  5395.7    0.08       0
  5505.0     0.1       0  5599.6    0.08       0  5614.4     0.1       0
Bank Sta=4994.9,5000.9
Exp/Cntr=0.3,0.1

Type RM Length L Ch R = 1,3682,414,414,414
BEGIN DESCRIPTION:
UNT003 IN SPCR 8.0
END DESCRIPTION:
XS GIS Cut Line= 4
      2196384.44     13263699.48      2196665.45     13263707.08
      2197121.16     13263502.01      2197514.86     13263070.45
#Sta/Elev= 30
  4475.9  352.60  4489.2  352.61  4539.2  349.64  4563.9  349.22  4569.2  347.95
  4620.2  346.29  4669.3  342.60  4719.3  342.47  4755.6  340.29  4767.4  340.21
  4772.8  341.16  4781.4  339.70  4897.3  336.38  4911.7  335.75  4978.8  336.17
  4986.7  334.08  4992.2  333.65  4997.8  330.94  5000.5  330.44  5003.8  330.94
  5009.8  335.78  5022.7  336.38  5055.6  335.97  5136.5  337.87  5293.1  339.03
  5456.0  344.02  5491.8  345.82  5541.1  347.08  5683.0  348.24  5840.9  353.04
#Mann=5,-1,0
  4475.9     0.1       0  4620.2    0.08       0  4897.3     0.1       0
  4997.8    0.07       0  5003.8     0.1       0
Bank Sta=4997.8,5003.8
Exp/Cntr=0.3,0.1

Type RM Length L Ch R = 1,3268,513,513,513
BEGIN DESCRIPTION:
UNT003 IN SPCR 7.0
END DESCRIPTION:
XS GIS Cut Line= 4
      2196407.20     13263942.53      2196650.26     13264041.27
      2197273.07     13263980.51      2197613.63     13263882.12
#Sta/Elev= 30
  4465.5  353.38  4476.9  352.13  4491.7  352.22  4498.4  351.15  4515.7  350.08
  4530.8  350.25  4545.2  348.89  4561.0  348.68  4676.4  344.81  4700.5  343.34
  4714.3  343.45  4815.7  340.39  4936.3  336.14  4986.5  331.97  4993.6  326.77
  4996.3  326.27  4999.6  326.77  5006.6  327.07  5016.7  331.71  5031.3  334.29
  5066.9  332.95  5147.3  334.24  5257.8  333.43  5389.8  335.09  5490.7  338.28
  5649.9  345.64  5660.3  346.67  5674.5  346.52  5681.1  347.68  5708.1  348.60
#Mann=4,-1,0
  4465.5    0.08       0  4561.0     0.1       0  4993.6    0.07       0
  4999.6     0.1       0
Bank Sta=4993.6,4999.6
Exp/Cntr=0.3,0.1

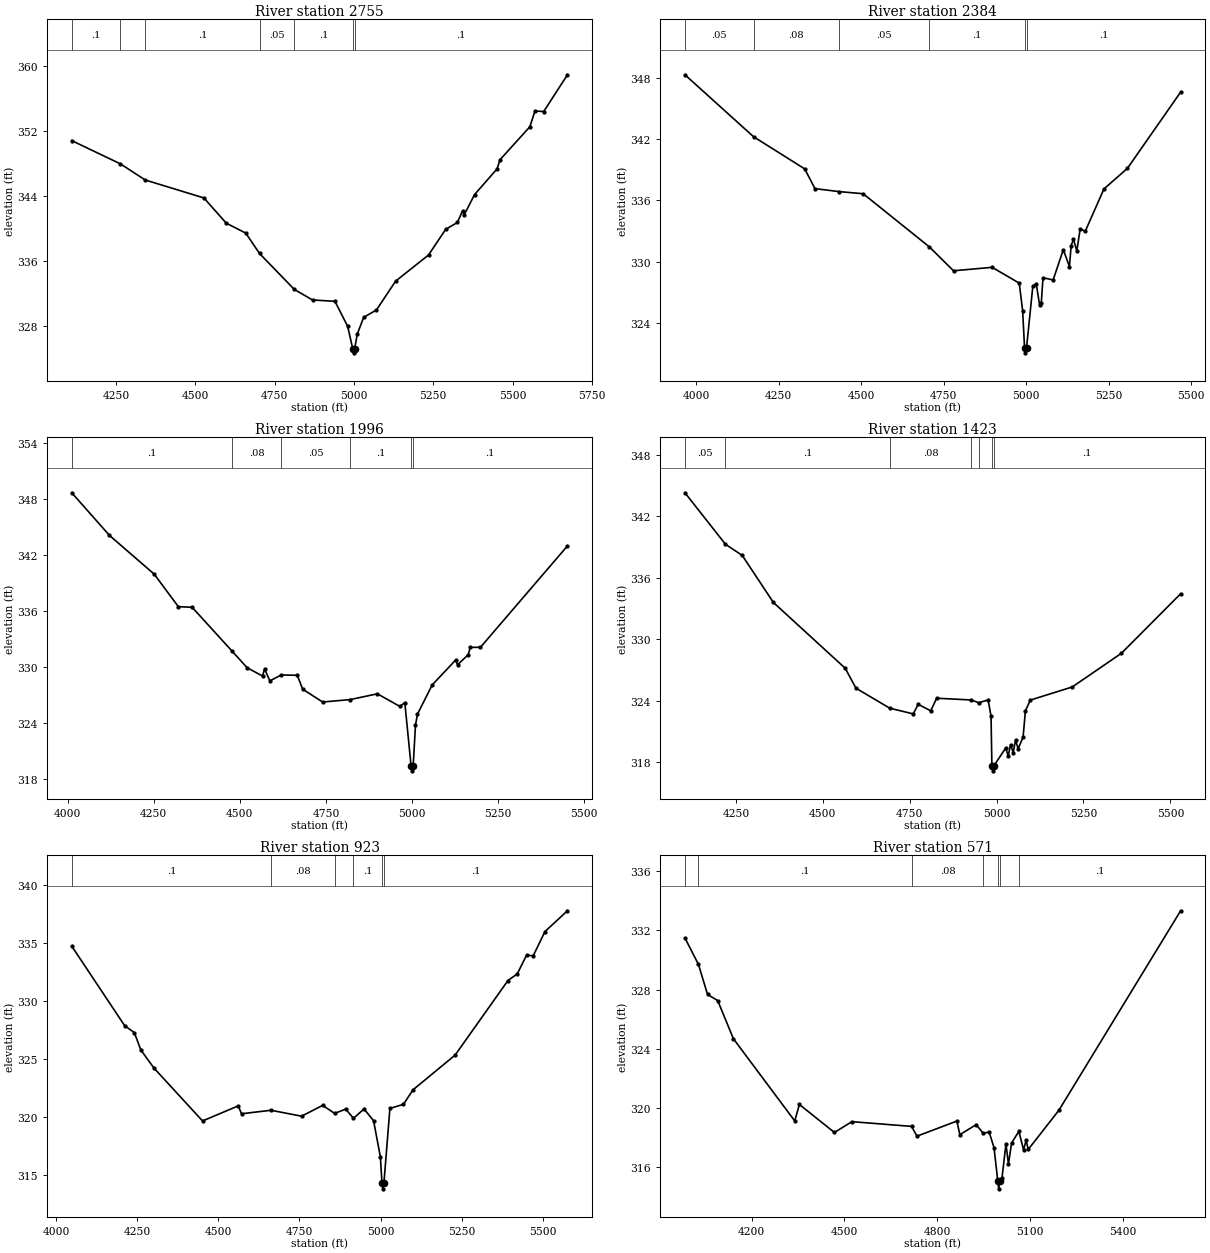
Type RM Length L Ch R = 1,2755,371,371,371
BEGIN DESCRIPTION:
UNT003 IN SPCR 6.0
END DESCRIPTION:
XS GIS Cut Line= 4
      2196445.16     13264215.93      2196756.59     13264459.01
      2197478.14     13264375.46      2197864.07     13264163.58
#Sta/Elev= 30
  4111.2  350.78  4264.3  347.92  4342.7  345.93  4527.5  343.72  4598.0  340.61
  4659.4  339.39  4702.7  336.88  4812.4  332.45  4869.8  331.15  4940.3  330.99
  4980.5  327.90  4996.4  325.14  4999.1  324.64  5002.4  325.14  5010.7  326.95
  5030.9  329.01  5071.1  329.92  5131.5  333.47  5235.2  336.69  5289.2  339.85
  5326.2  340.70  5342.3  342.12  5348.0  341.67  5380.2  344.13  5451.3  347.31
  5460.3  348.42  5554.5  352.49  5570.6  354.43  5598.1  354.36  5672.9  358.89
#Mann=7,-1,0
  4111.2     0.1       0  4264.3    0.05       0  4342.7     0.1       0
  4702.7    0.05       0  4812.4     0.1       0  4996.4    0.07       0
  5002.4     0.1       0
Bank Sta=4996.4,5002.4
Exp/Cntr=0.3,0.1

Type RM Length L Ch R = 1,2384,388,388,388
BEGIN DESCRIPTION:
UNT003 IN SPCR 5.0
END DESCRIPTION:
XS GIS Cut Line= 4
      2196429.98     13264656.48      2196992.04     13264823.58
      2197743.97     13264648.89      2197849.40     13264550.99
#Sta/Elev= 30
  3965.7  348.33  4173.7  342.25  4328.5  339.10  4359.8  337.16  4432.4  336.87
  4505.8  336.66  4706.6  331.44  4779.6  329.10  4896.7  329.44  4978.8  327.89
  4989.1  325.19  4994.9  321.55  4997.7  321.05  5000.9  321.55  5019.9  327.56
  5030.2  327.84  5040.4  325.76  5045.7  325.97  5050.8  328.42  5081.5  328.20
  5112.3  331.17  5130.9  329.51  5136.1  331.57  5143.1  332.19  5153.3  331.06
  5163.6  333.23  5178.7  332.97  5235.5  337.13  5306.6  339.15  5467.9  346.63
#Mann=6,-1,0
  3965.7    0.05       0  4173.7    0.08       0  4432.4    0.05       0
  4706.6     0.1       0  4994.9    0.07       0  5000.9     0.1       0
Bank Sta=4994.9,5000.9
Exp/Cntr=0.3,0.1

Type RM Length L Ch R = 1,1996,573,573,573
BEGIN DESCRIPTION:
UNT003 IN SPCR 4.0
END DESCRIPTION:
XS GIS Cut Line= 4
      2196688.26     13265317.27      2197128.76     13265332.46
      2197819.93     13264914.72      2197926.28     13264755.19
#Sta/Elev= 30
  4011.7  348.69  4121.2  344.12  4251.3  339.96  4321.3  336.48  4361.4  336.41
  4478.4  331.67  4521.4  329.92  4565.9  329.04  4571.8  329.79  4587.3  328.52
  4620.5  329.15  4666.9  329.12  4682.4  327.63  4740.6  326.25  4820.2  326.51
  4899.7  327.13  4965.4  325.77  4979.3  326.19  4997.6  319.37  5000.4  318.87
  5003.6  319.37  5010.3  323.77  5016.1  324.95  5058.8  328.08  5126.7  330.74
  5132.5  330.25  5163.6  331.32  5169.4  332.11  5199.1  332.12  5451.8  342.99
#Mann=6,-1,0
  4011.7     0.1       0  4478.4    0.08       0  4620.5    0.05       0
  4820.2     0.1       0  4997.6    0.07       0  5003.6     0.1       0
Bank Sta=4997.6,5003.6
Exp/Cntr=0.3,0.1

Type RM Length L Ch R = 1,1423,500,500,500
BEGIN DESCRIPTION:
UNT003 IN SPCR 3.0
END DESCRIPTION:
XS GIS Cut Line= 3
      2196987.72     13265946.86      2197787.72     13265546.85
      2198187.69     13265196.88
#Sta/Elev= 30
  4103.6  344.29  4220.2  339.26  4268.5  338.17  4358.0  333.58  4564.8  327.15
  4595.5  325.21  4692.6  323.26  4760.4  322.70  4774.4  323.64  4810.8  323.00
  4827.5  324.23  4927.7  324.06  4948.3  323.79  4975.7  324.06  4984.1  322.49
  4986.6  317.64  4989.4  317.14  4992.6  317.64  5026.0  319.36  5033.6  318.60
  5040.3  319.70  5047.9  318.92  5054.5  320.13  5062.1  319.30  5076.3  320.43
  5083.0  323.00  5097.2  324.05  5217.8  325.33  5359.2  328.62  5529.5  334.43
#Mann=7,-1,0
  4103.6    0.05       0  4220.2     0.1       0  4692.6    0.08       0
  4927.7    0.05       0  4948.3     0.1       0  4986.6    0.07       0
  4992.6     0.1       0
Bank Sta=4986.6,4992.6
Exp/Cntr=0.3,0.1

Type RM Length L Ch R = 1,923,352,352,352
BEGIN DESCRIPTION:
UNT003 IN SPCR 2.0
END DESCRIPTION:
XS GIS Cut Line= 4
      2197235.10     13266054.01      2197797.14     13266038.82
      2198351.59     13265636.27      2198533.28     13265424.30
#Sta/Elev= 30
  4048.7  334.76  4211.4  327.92  4241.4  327.31  4261.4  325.82  4301.4  324.27
  4451.5  319.70  4561.5  321.00  4571.5  320.32  4662.4  320.62  4756.4  320.11
  4821.3  321.04  4858.3  320.35  4892.4  320.72  4916.3  319.93  4948.8  320.73
  4978.2  319.72  4999.1  316.62  5004.1  314.35  5006.9  313.85  5010.1  314.35
  5028.5  320.78  5070.2  321.13  5099.6  322.38  5229.5  325.38  5392.1  331.80
  5420.6  332.37  5449.2  333.97  5470.0  333.94  5506.1  336.02  5575.3  337.81
#Mann=6,-1,0
  4048.7     0.1       0  4662.4    0.08       0  4858.3    0.05       0
  4916.3     0.1       0  5004.1    0.07       0  5010.1     0.1       0
Bank Sta=5004.1,5010.1
Exp/Cntr=0.3,0.1

Type RM Length L Ch R = 1,571,434,434,434
BEGIN DESCRIPTION:
Mapping XS ddeb3123
END DESCRIPTION:
XS GIS Cut Line= 4
      2197303.46     13266198.32      2197721.19     13266274.27
      2198366.78     13266084.39      2198700.98     13265704.62
#Sta/Elev= 30
  3984.0  331.48  4027.8  329.69  4057.0  327.67  4090.0  327.25  4140.8  324.67
  4339.1  319.12  4354.2  320.23  4467.5  318.34  4524.1  319.07  4716.9  318.75
  4734.7  318.09  4863.6  319.11  4873.3  318.19  4926.1  318.87  4949.2  318.27
  4967.8  318.38  4983.8  317.31  4996.1  315.03  4998.9  314.53  5002.1  315.03
  5009.5  315.26  5022.4  317.57  5030.4  316.21  5040.8  317.64  5064.1  318.41
  5079.4  317.16  5087.7  317.82  5094.4  317.19  5194.0  319.85  5587.4  333.32
#Mann=7,-1,0
  3984.0    0.05       0  4027.8     0.1       0  4716.9    0.08       0
  4949.2    0.05       0  4996.1    0.03       0  5002.1    0.05       0
  5064.1     0.1       0
Bank Sta=4996.1,5002.1
Exp/Cntr=0.3,0.1

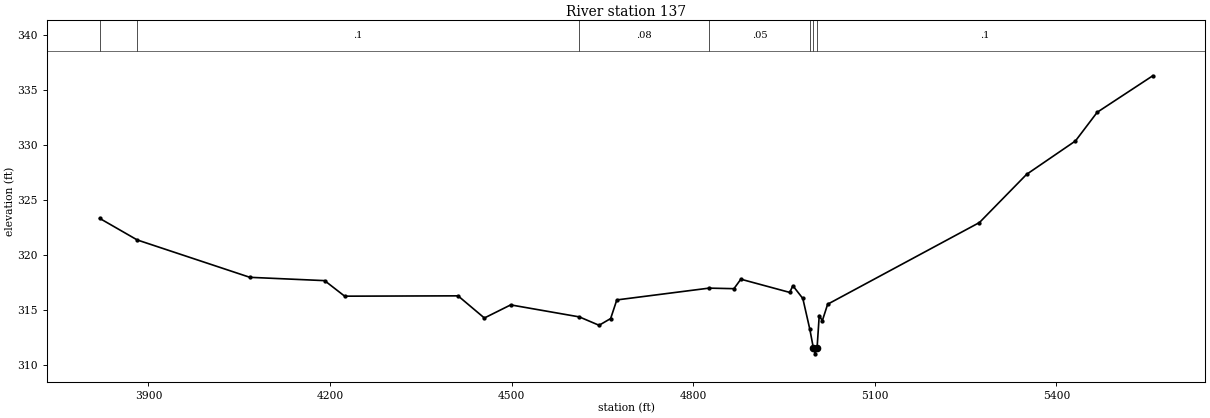
Type RM Length L Ch R = 1,137,0,0,0
BEGIN DESCRIPTION:
UNT003 IN SPCR 1.0
END DESCRIPTION:
XS GIS Cut Line= 4
      2197478.11     13266350.21      2197971.83     13266479.34
      2198723.76     13266312.24      2198981.97     13265932.52
#Sta/Elev= 30
  3819.4  323.33  3881.5  321.37  4067.6  317.98  4191.1  317.68  4224.2  316.27
  4411.5  316.30  4455.0  314.29  4498.5  315.48  4611.9  314.39  4644.5  313.63
  4663.6  314.24  4673.8  315.93  4826.2  317.00  4867.3  316.95  4878.7  317.81
  4959.5  316.61  4964.6  317.22  4981.1  316.06  4992.7  313.26  4998.6  311.54
  5001.4  311.04  5004.6  311.54  5008.2  314.51  5013.3  314.04  5022.1  315.54
  5272.9  322.95  5350.8  327.32  5431.5  330.35  5467.4  332.95  5559.2  336.26
#Mann=7,-1,0
  3819.4    0.05       0  3881.5     0.1       0  4611.9    0.08       0
  4826.2    0.05       0  4992.7     0.1       0  4998.6    0.07       0
  5004.6     0.1       0
Bank Sta=4998.6,5004.6
Exp/Cntr=0.3,0.1

Chan Stop Cuts=-1