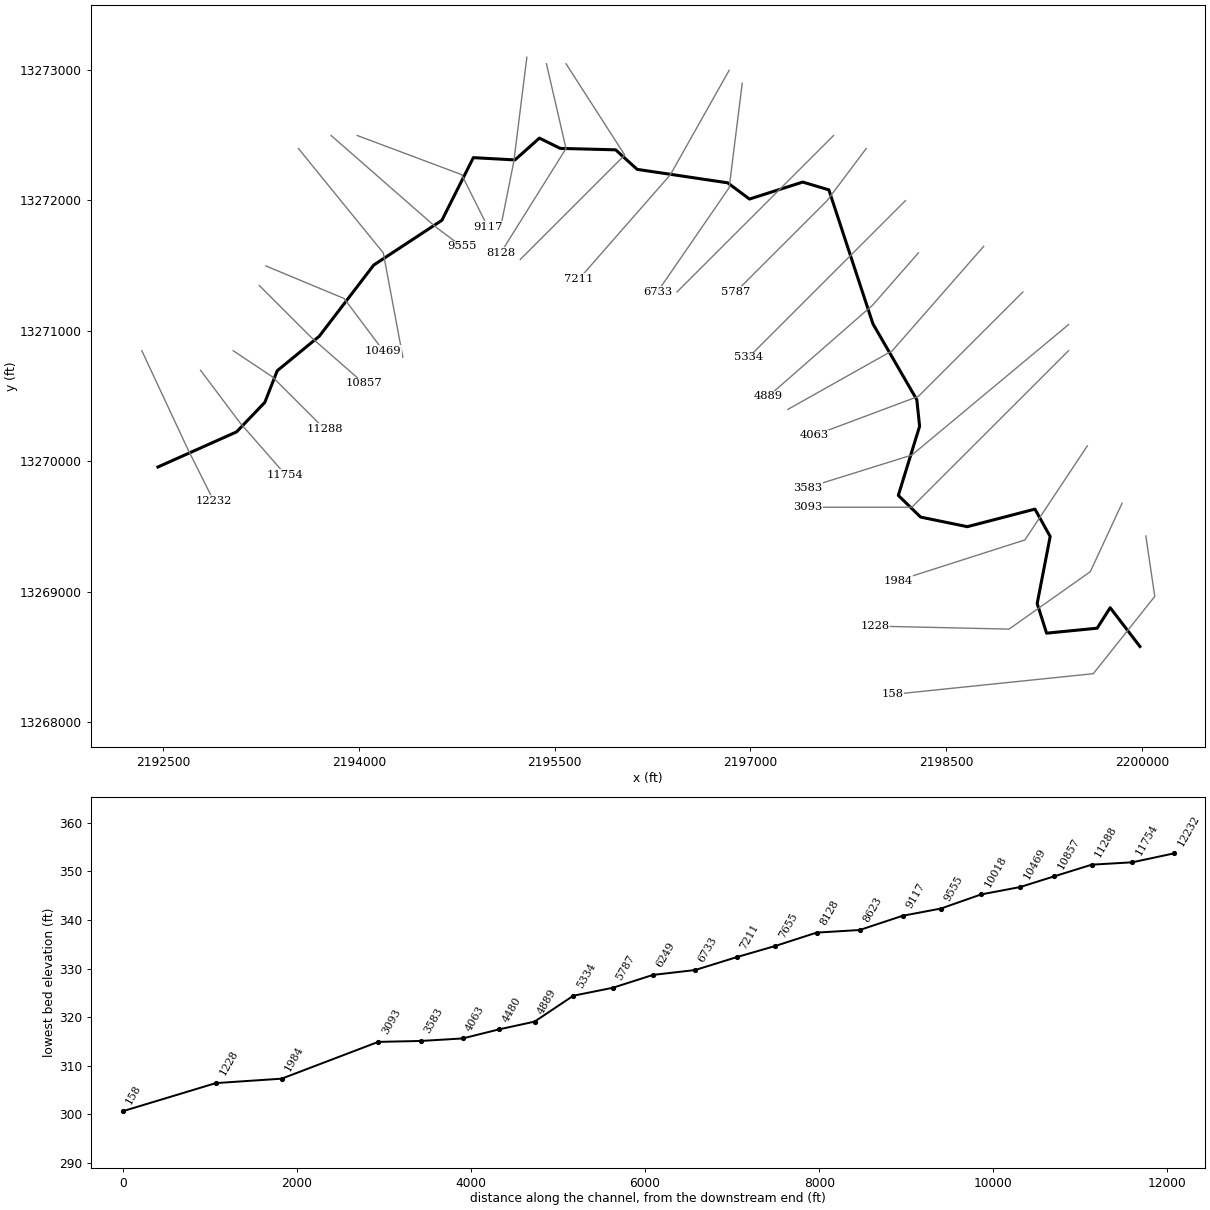
--- UNT004 IN SPCR.prj (project) ---

Proj Title=UNT004 IN SPCR Base Level Engineering
Current Plan=p01
Default Exp/Contr=0.3,0.1
English Units
Geom File=g01
Flow File=f01
Plan File=p01
BEGIN DESCRIPTION:
UNT004 IN SPCR
END DESCRIPTION:

--- UNT004 IN SPCR.p01 (plan) ---

Plan Title=Multiple Run
Short Identifier=Multiple
Geom File=g01
Flow File=f01
Subcritical Flow
K Sum by GR= 0
Std Step Tol= 0.01
Critical Tol= 0.01
Num of Std Step Trials= 20
Max Error Tol= 0.3
Flow Tol Ratio= 0.001
Split Flow NTrial= 30
Split Flow Tol= 0.02
Split Flow Ratio= 0.02
Log Output Level= 0
Friction Slope Method= 1
Unsteady Friction Slope Method= 2
Unsteady Bridges Friction Slope Method= 1
Parabolic Critical Depth
Global Vel Dist=  1 , 1 , 1
Global Log Level= 0
CheckData=True
Encroach Param= -1, 0, 0, 0
BEGIN DESCRIPTION:
Multiple Run
END DESCRIPTION:

--- UNT004 IN SPCR.f01 (steady flow) ---

Flow Title=Multiple
Number of Profiles=7
Profile Names=10-year,25-year,50-year,1pct_min,100-year,1pct_plu,500-year
River Rch & RM= UNT004 IN SPCR,Reach-1,12232
     370     532     671     623     843    1140    1349
River Rch & RM= UNT004 IN SPCR,Reach-1,6733
     443     639     809     752    1017    1375    1633
Boundary for River Rch & Prof#=UNT004 IN SPCR,Reach-1,1
Up Type=0
Dn Type=3
Dn Slope=0.005
Boundary for River Rch & Prof#=UNT004 IN SPCR,Reach-1,2
Up Type=0
Dn Type=3
Dn Slope=0.005
Boundary for River Rch & Prof#=UNT004 IN SPCR,Reach-1,3
Up Type=0
Dn Type=3
Dn Slope=0.005
Boundary for River Rch & Prof#=UNT004 IN SPCR,Reach-1,4
Up Type=0
Dn Type=3
Dn Slope=0.005
Boundary for River Rch & Prof#=UNT004 IN SPCR,Reach-1,5
Up Type=0
Dn Type=3
Dn Slope=0.005
Boundary for River Rch & Prof#=UNT004 IN SPCR,Reach-1,6
Up Type=0
Dn Type=3
Dn Slope=0.005
Boundary for River Rch & Prof#=UNT004 IN SPCR,Reach-1,7
Up Type=0
Dn Type=3
Dn Slope=0.005

--- UNT004 IN SPCR.g01 (geometry) ---

Geom Title=Existing Conditions

River Reach=UNT004 IN SPCR,Reach-1
Reach XY= 30
      2192461.14     13269955.22      2193063.75     13270224.41
      2193279.92     13270450.50      2193375.35     13270693.23
      2193696.94     13270957.26      2194114.56     13271503.47
      2194636.81     13271846.67      2194877.72     13272326.86
      2195196.51     13272309.53      2195383.82     13272476.59
      2195543.15     13272397.99      2195968.15     13272386.83
      2196132.61     13272237.14      2196826.43     13272133.87
      2196993.35     13272009.50      2197401.51     13272139.62
      2197601.60     13272079.99      2197939.08     13271052.98
      2198275.52     13270470.60      2198296.82     13270267.44
      2198133.68     13269737.38      2198304.70     13269571.02
      2198662.38     13269497.58      2199180.49     13269632.26
      2199297.16     13269422.24      2199197.58     13268908.13
      2199269.62     13268681.14      2199657.06     13268719.37
      2199757.01     13268876.26      2199984.79     13268578.81

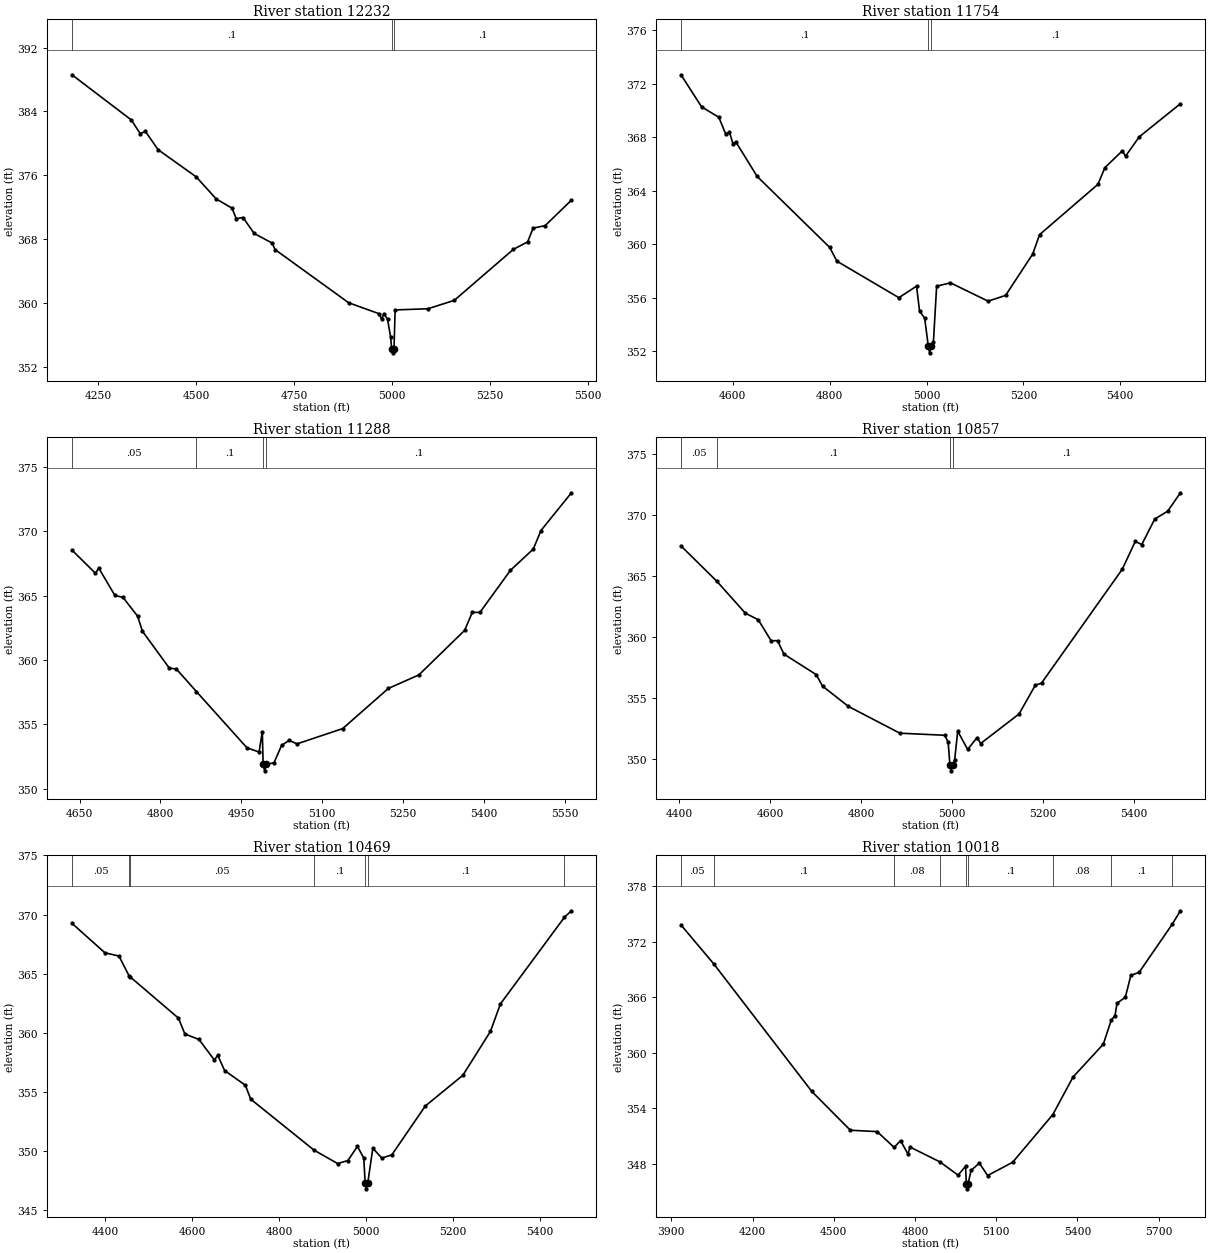
Type RM Length L Ch R = 1,12232,478,478,478
BEGIN DESCRIPTION:
UNT004 IN SPCR 22.0
END DESCRIPTION:
XS GIS Cut Line= 3
      2192337.70     13270846.90      2192687.72     13270096.85
      2192887.72     13269696.86
#Sta/Elev= 30
  4183.5  388.59  4334.9  382.93  4357.7  381.22  4371.1  381.48  4403.5  379.19
  4500.4  375.80  4551.7  373.02  4591.9  371.87  4602.9  370.55  4620.2  370.69
  4648.6  368.69  4694.3  367.49  4702.2  366.66  4889.8  360.00  4967.1  358.63
  4974.1  357.93  4979.7  358.65  4989.1  357.91  4997.0  355.66  4999.5  354.22
  5002.3  353.72  5005.5  354.22  5008.4  359.10  5092.2  359.25  5159.3  360.30
  5310.3  366.70  5346.6  367.63  5360.6  369.36  5391.3  369.67  5458.4  372.87
#Mann=3,-1,0
  4183.5     0.1       0  4999.5    0.07       0  5005.5     0.1       0
Bank Sta=4999.5,5005.5
Exp/Cntr=0.3,0.1

Type RM Length L Ch R = 1,11754,466,466,466
BEGIN DESCRIPTION:
UNT004 IN SPCR 21.0
END DESCRIPTION:
XS GIS Cut Line= 3
      2192787.71     13270696.87      2193087.72     13270296.85
      2193437.71     13269896.87
#Sta/Elev= 30
  4492.8  372.66  4535.5  370.26  4570.9  369.49  4585.5  368.21  4592.8  368.39
  4600.1  367.52  4606.4  367.63  4650.1  365.07  4800.1  359.76  4814.7  358.74
  4942.8  356.01  4979.3  356.87  4985.5  355.02  4996.1  354.47  5003.6  352.39
  5006.3  351.89  5009.6  352.39  5014.2  352.72  5020.8  356.87  5049.3  357.12
  5127.1  355.75  5163.2  356.18  5219.2  359.27  5233.4  360.72  5354.0  364.48
  5368.2  365.72  5404.3  366.98  5410.9  366.58  5439.4  368.03  5524.3  370.50
#Mann=3,-1,0
  4492.8     0.1       0  5003.6    0.07       0  5009.6     0.1       0
Bank Sta=5003.6,5009.6
Exp/Cntr=0.3,0.1

Type RM Length L Ch R = 1,11288,431,431,431
BEGIN DESCRIPTION:
UNT004 IN SPCR 20.0
END DESCRIPTION:
XS GIS Cut Line= 3
      2193037.73     13270846.85      2193337.72     13270646.85
      2193737.70     13270246.87
#Sta/Elev= 30
  4636.0  368.54  4679.6  366.74  4685.6  367.15  4715.6  365.02  4730.6  364.87
  4757.7  363.41  4766.7  362.24  4816.3  359.39  4829.8  359.30  4866.7  357.56
  4960.5  353.19  4983.0  352.86  4989.0  354.45  4990.5  351.90  4993.3  351.40
  4996.5  351.90  5010.7  352.03  5024.8  353.38  5039.0  353.77  5053.1  353.49
  5138.0  354.68  5222.8  357.80  5279.4  358.85  5364.2  362.31  5378.4  363.71
  5392.5  363.70  5449.1  366.97  5491.5  368.62  5505.7  370.06  5562.2  372.99
#Mann=4,-1,0
  4636.0    0.05       0  4866.7     0.1       0  4990.5    0.07       0
  4996.5     0.1       0
Bank Sta=4990.5,4996.5
Exp/Cntr=0.3,0.1

Type RM Length L Ch R = 1,10857,388,388,388
BEGIN DESCRIPTION:
UNT004 IN SPCR 19.0
END DESCRIPTION:
XS GIS Cut Line= 3
      2193237.74     13271346.83      2193637.72     13270946.85
      2194037.75     13270596.83
#Sta/Elev= 30
  4404.2  367.46  4483.0  364.56  4545.6  361.94  4573.9  361.40  4602.2  359.68
  4616.3  359.68  4630.4  358.58  4701.2  356.90  4715.3  355.95  4771.9  354.29
  4885.0  352.09  4983.6  351.92  4991.2  351.35  4994.9  349.50  4997.6  349.00
  5000.9  349.50  5005.4  349.88  5012.1  352.26  5033.9  350.76  5054.8  351.73
  5062.4  351.24  5146.9  353.67  5182.5  356.02  5196.2  356.20  5373.7  365.55
  5402.2  367.83  5416.4  367.57  5444.9  369.66  5473.4  370.31  5501.4  371.82
#Mann=4,-1,0
  4404.2    0.05       0  4483.0     0.1       0  4994.9    0.07       0
  5000.9     0.1       0
Bank Sta=4994.9,5000.9
Exp/Cntr=0.3,0.1

Type RM Length L Ch R = 1,10469,451,451,451
BEGIN DESCRIPTION:
UNT004 IN SPCR 18.0
END DESCRIPTION:
XS GIS Cut Line= 3
      2193287.76     13271496.84      2193887.72     13271246.85
      2194187.75     13270846.82
#Sta/Elev= 30
  4322.9  369.26  4398.7  366.77  4431.2  366.49  4454.7  364.80  4456.0  364.76
  4568.2  361.24  4582.9  359.90  4615.4  359.44  4650.6  357.71  4658.7  358.09
  4674.4  356.81  4722.1  355.57  4734.5  354.39  4880.0  350.09  4934.4  348.95
  4958.2  349.20  4980.2  350.40  4994.7  349.42  4998.0  347.31  5000.7  346.81
  5004.0  347.31  5015.6  350.24  5036.4  349.41  5059.3  349.68  5136.4  353.81
  5222.9  356.41  5286.4  360.12  5309.3  362.44  5456.8  369.77  5472.9  370.32
#Mann=7,-1,0
  4322.9    0.05       0  4454.7     0.1       0  4456.0    0.05       0
  4880.0     0.1       0  4998.0    0.07       0  5004.0     0.1       0
  5456.8    0.05       0
Bank Sta=4998,5004
Exp/Cntr=0.3,0.1

Type RM Length L Ch R = 1,10018,463,463,463
BEGIN DESCRIPTION:
UNT004 IN SPCR 17.0
END DESCRIPTION:
XS GIS Cut Line= 3
      2193537.74     13272396.83      2194187.72     13271596.85
      2194337.72     13270796.84
#Sta/Elev= 30
  3935.6  373.83  4056.6  369.62  4419.0  355.81  4561.2  351.62  4660.3  351.47
  4723.0  349.76  4746.6  350.50  4773.8  349.05  4781.7  349.80  4892.3  348.19
  4959.2  346.76  4986.7  347.73  4989.6  345.78  4992.4  345.28  4995.6  345.78
  5007.0  347.27  5037.6  348.07  5068.1  346.72  5160.5  348.15  5308.9  353.31
  5383.5  357.37  5495.4  360.93  5524.8  363.53  5538.6  364.03  5546.3  365.36
  5576.8  366.01  5597.1  368.37  5627.7  368.70  5750.1  373.91  5780.3  375.36
#Mann=9,-1,0
  3935.6    0.05       0  4056.6     0.1       0  4723.0    0.08       0
  4892.3     0.1       0  4989.6    0.07       0  4995.6     0.1       0
  5308.9    0.08       0  5524.8     0.1       0  5750.1    0.05       0
Bank Sta=4989.6,4995.6
Exp/Cntr=0.3,0.1

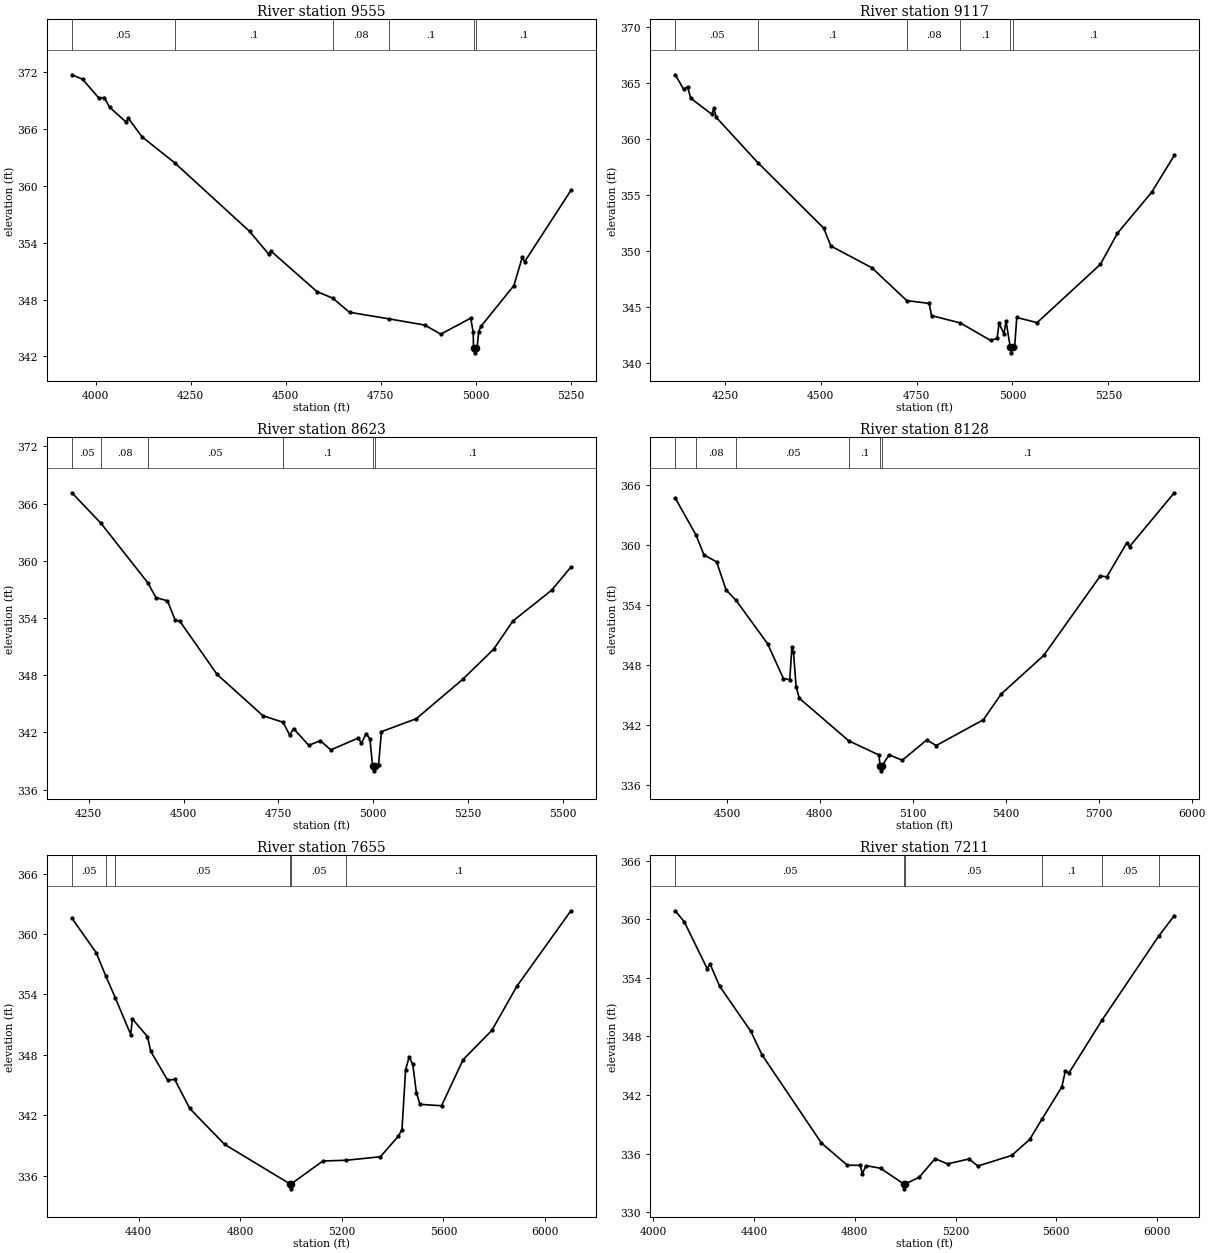
Type RM Length L Ch R = 1,9555,438,438,438
BEGIN DESCRIPTION:
UNT004 IN SPCR 16.0
END DESCRIPTION:
XS GIS Cut Line= 3
      2193787.70     13272496.87      2194587.72     13271796.85
      2194787.69     13271646.88
#Sta/Elev= 30
  3937.8  371.72  3965.8  371.25  4008.5  369.27  4022.8  369.32  4037.0  368.29
  4079.7  366.75  4086.4  367.11  4122.4  365.17  4207.8  362.44  4405.3  355.19
  4455.6  352.79  4462.2  353.09  4582.7  348.83  4623.8  348.15  4668.2  346.65
  4771.6  345.96  4866.5  345.30  4908.3  344.34  4987.1  346.03  4993.7  344.54
  4994.5  342.87  4997.3  342.37  5000.5  342.87  5004.0  342.87  5008.1  344.62
  5014.4  345.18  5100.8  349.47  5122.7  352.44  5129.0  351.98  5250.8  359.52
#Mann=6,-1,0
  3937.8    0.05       0  4207.8     0.1       0  4623.8    0.08       0
  4771.6     0.1       0  4994.5    0.07       0  5000.5     0.1       0
Bank Sta=4994.5,5000.5
Exp/Cntr=0.3,0.1

Type RM Length L Ch R = 1,9117,494,494,494
BEGIN DESCRIPTION:
UNT004 IN SPCR 15.0
END DESCRIPTION:
XS GIS Cut Line= 3
      2193987.72     13272496.86      2194787.72     13272196.85
      2194987.71     13271796.87
#Sta/Elev= 30
  4120.4  365.75  4141.8  364.47  4152.4  364.67  4160.5  363.66  4215.6  362.22
  4221.0  362.75  4227.2  361.94  4336.1  357.88  4507.6  352.04  4526.2  350.44
  4633.0  348.50  4724.3  345.56  4782.6  345.31  4788.8  344.22  4864.1  343.56
  4942.8  342.00  4959.7  342.18  4965.0  343.52  4977.6  342.60  4983.2  343.71
  4994.2  341.39  4996.9  340.89  5000.2  341.39  5005.6  341.41  5011.1  344.05
  5064.2  343.59  5229.2  348.80  5273.9  351.59  5363.3  355.26  5422.0  358.54
#Mann=6,-1,0
  4120.4    0.05       0  4336.1     0.1       0  4724.3    0.08       0
  4864.1     0.1       0  4994.2    0.07       0  5000.2     0.1       0
Bank Sta=4994.2,5000.2
Exp/Cntr=0.3,0.1

Type RM Length L Ch R = 1,8623,495,495,495
BEGIN DESCRIPTION:
UNT004 IN SPCR 14.0
END DESCRIPTION:
XS GIS Cut Line= 3
      2195287.72     13273096.82      2195187.72     13272296.85
      2195087.72     13271796.85
#Sta/Elev= 30
  4205.6  367.14  4282.4  363.93  4405.5  357.71  4427.3  356.14  4457.5  355.80
  4477.7  353.80  4490.3  353.66  4588.5  348.08  4709.5  343.74  4762.4  343.06
  4780.0  341.71  4790.1  342.40  4830.4  340.63  4860.6  341.13  4888.3  340.16
  4961.4  341.41  4969.0  340.84  4981.6  341.85  4991.6  341.32  4998.7  338.46
  5001.5  337.96  5004.7  338.46  5014.3  338.57  5022.0  342.07  5113.8  343.43
  5236.2  347.56  5317.7  350.71  5368.7  353.68  5470.7  356.91  5521.7  359.34
#Mann=6,-1,0
  4205.6    0.05       0  4282.4    0.08       0  4405.5    0.05       0
  4762.4     0.1       0  4998.7    0.07       0  5004.7     0.1       0
Bank Sta=4998.7,5004.7
Exp/Cntr=0.3,0.1

Type RM Length L Ch R = 1,8128,473,473,473
BEGIN DESCRIPTION:
UNT004 IN SPCR 13.0
END DESCRIPTION:
XS GIS Cut Line= 3
      2195437.72     13273046.86      2195587.72     13272396.85
      2195087.71     13271596.85
#Sta/Elev= 30
  4333.4  364.66  4400.9  360.93  4425.8  358.99  4466.8  358.29  4497.6  355.47
  4529.2  354.46  4631.0  350.13  4682.3  346.64  4702.9  346.53  4709.7  349.75
  4714.8  349.29  4723.4  345.81  4733.7  344.67  4893.5  340.41  4990.2  339.01
  4994.9  337.92  4997.7  337.42  5000.9  337.92  5023.5  339.02  5065.9  338.48
  5144.9  340.50  5175.6  339.95  5327.7  342.52  5385.5  345.10  5522.3  348.94
  5705.1  356.88  5726.3  356.80  5790.6  360.19  5799.4  359.81  5943.9  365.19
#Mann=6,-1,0
  4333.4    0.05       0  4400.9    0.08       0  4529.2    0.05       0
  4893.5     0.1       0  4994.9    0.07       0  5000.9     0.1       0
Bank Sta=4994.9,5000.9
Exp/Cntr=0.3,0.1

Type RM Length L Ch R = 1,7655,444,444,444
BEGIN DESCRIPTION:
UNT004 IN SPCR 12.0
END DESCRIPTION:
XS GIS Cut Line= 3
      2195587.73     13273046.85      2196037.72     13272346.85
      2195237.74     13271546.87
#Sta/Elev= 30
  4137.9  361.58  4233.0  358.17  4271.7  355.81  4308.9  353.65  4369.4  350.01
  4375.7  351.58  4435.1  349.81  4448.0  348.35  4514.7  345.47  4542.1  345.56
  4601.5  342.67  4738.6  339.10  4995.3  335.18  4998.1  334.68  5001.3  335.18
  5125.6  337.45  5217.0  337.52  5351.9  337.87  5422.6  339.92  5436.7  340.57
  5450.9  346.52  5465.0  347.80  5479.2  347.04  5493.3  344.25  5507.5  343.08
  5592.3  342.94  5677.2  347.52  5790.3  350.43  5889.3  354.84  6101.4  362.32
#Mann=6,-1,0
  4137.9    0.05       0  4271.7    0.08       0  4308.9    0.05       0
  4995.3    0.03       0  5001.3    0.05       0  5217.0     0.1       0
Bank Sta=4995.3,5001.3
Exp/Cntr=0.3,0.1

Type RM Length L Ch R = 1,7211,478,478,478
BEGIN DESCRIPTION:
UNT004 IN SPCR 11.0
END DESCRIPTION:
XS GIS Cut Line= 3
      2196837.74     13272996.89      2196387.72     13272196.85
      2195687.75     13271396.88
#Sta/Elev= 30
  4087.2  360.89  4122.6  359.77  4213.5  354.97  4225.2  355.44  4262.9  353.17
  4387.1  348.53  4431.4  346.12  4667.6  337.07  4770.2  334.80  4821.5  334.79
  4829.5  333.92  4844.5  334.76  4901.9  334.49  4994.2  332.88  4996.9  332.38
  5000.2  332.88  5055.0  333.56  5118.5  335.47  5167.9  334.94  5253.3  335.44
  5288.4  334.72  5423.2  335.81  5494.4  337.45  5542.2  339.50  5621.6  342.82
  5635.8  344.48  5650.1  344.26  5780.6  349.65  6006.6  358.31  6068.1  360.39
#Mann=6,-1,0
  4087.2    0.05       0  4994.2    0.03       0  5000.2    0.05       0
  5542.2     0.1       0  5780.6    0.05       0  6006.6     0.1       0
Bank Sta=4994.2,5000.2
Exp/Cntr=0.3,0.1

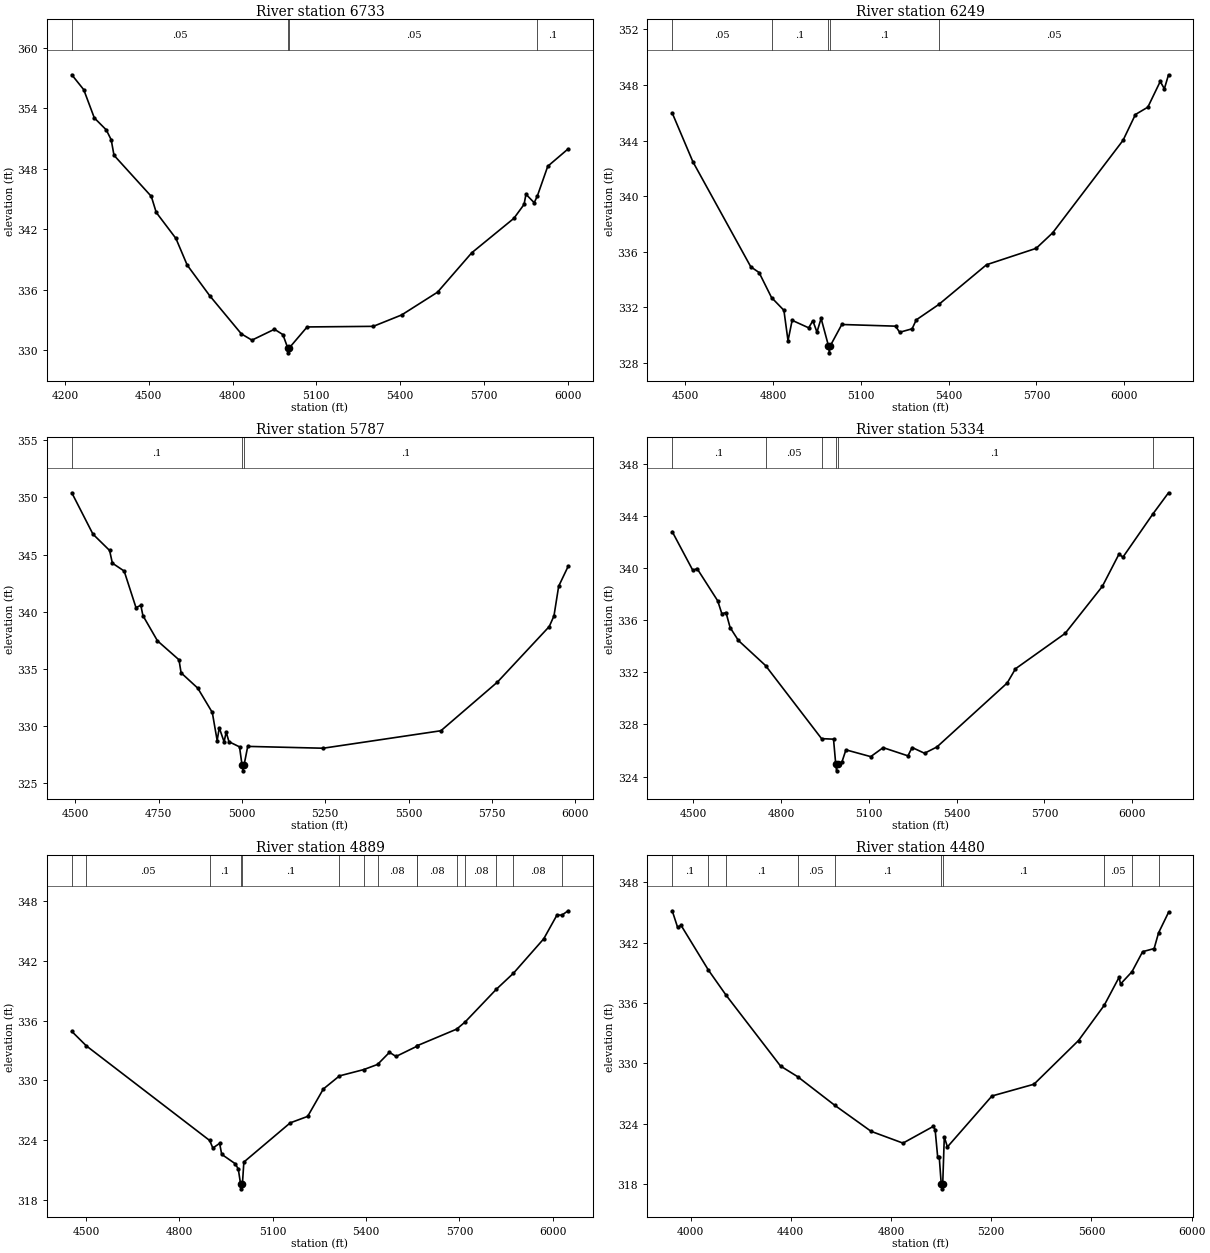
Type RM Length L Ch R = 1,6733,484,484,484
BEGIN DESCRIPTION:
UNT004 IN SPCR 10.0
END DESCRIPTION:
XS GIS Cut Line= 3
      2196937.72     13272896.83      2196837.72     13272096.85
      2196287.74     13271296.88
#Sta/Elev= 30
  4224.5  357.32  4267.3  355.84  4305.1  353.04  4347.9  351.85  4365.6  350.87
  4375.6  349.33  4509.2  345.25  4526.8  343.66  4597.4  341.07  4637.7  338.43
  4718.3  335.39  4831.7  331.60  4869.5  330.98  4950.1  332.06  4980.3  331.53
  4997.5  330.22  5000.2  329.72  5003.5  330.22  5067.1  332.29  5304.0  332.35
  5405.5  333.48  5534.0  335.74  5656.5  339.65  5807.4  343.07  5843.8  344.45
  5850.7  345.46  5880.2  344.62  5891.7  345.31  5928.7  348.24  6001.5  349.96
#Mann=4,-1,0
  4224.5    0.05       0  4997.5    0.03       0  5003.5    0.05       0
  5891.7     0.1       0
Bank Sta=4997.5,5003.5
Exp/Cntr=0.3,0.1

Type RM Length L Ch R = 1,6249,462,462,462
BEGIN DESCRIPTION:
UNT004 IN SPCR 9.0
END DESCRIPTION:
XS GIS Cut Line= 3
      2197637.74     13272496.87      2197237.72     13272096.85
      2196437.71     13271296.84
#Sta/Elev= 30
  4454.7  345.98  4525.4  342.47  4723.4  334.91  4751.7  334.50  4794.3  332.70
  4836.6  331.78  4850.7  329.59  4864.8  331.06  4921.4  330.52  4935.6  331.03
  4949.7  330.21  4963.8  331.20  4989.1  329.22  4991.9  328.72  4995.1  329.22
  5034.6  330.76  5218.4  330.64  5232.5  330.20  5275.0  330.45  5289.1  331.09
  5366.2  332.20  5529.5  335.06  5699.2  336.24  5755.8  337.36  5996.2  344.01
  6038.6  345.87  6081.1  346.40  6123.5  348.25  6137.6  347.72  6151.8  348.73
#Mann=5,-1,0
  4454.7    0.05       0  4794.3     0.1       0  4989.1    0.07       0
  4995.1     0.1       0  5366.2    0.05       0
Bank Sta=4989.1,4995.1
Exp/Cntr=0.3,0.1

Type RM Length L Ch R = 1,5787,453,453,453
BEGIN DESCRIPTION:
UNT004 IN SPCR 8.0
END DESCRIPTION:
XS GIS Cut Line= 3
      2197887.69     13272396.82      2197587.72     13271996.85
      2196887.72     13271296.85
#Sta/Elev= 30
  4489.1  350.41  4552.6  346.79  4602.6  345.36  4610.9  344.25  4646.3  343.56
  4681.8  340.36  4696.3  340.56  4702.6  339.66  4746.3  337.45  4810.9  335.79
  4817.2  334.65  4867.2  333.31  4910.9  331.18  4925.5  328.72  4931.8  329.84
  4946.3  328.61  4952.6  329.46  4960.9  328.62  4992.6  328.17  5000.2  326.57
  5002.9  326.07  5006.2  326.57  5017.3  328.21  5243.6  328.05  5597.2  329.58
  5766.9  333.84  5922.4  338.70  5936.6  339.63  5950.7  342.23  5979.0  343.96
#Mann=3,-1,0
  4489.1     0.1       0  5000.2    0.07       0  5006.2     0.1       0
Bank Sta=5000.2,5006.2
Exp/Cntr=0.3,0.1

Type RM Length L Ch R = 1,5334,445,445,445
BEGIN DESCRIPTION:
UNT004 IN SPCR 7.0
END DESCRIPTION:
XS GIS Cut Line= 3
      2198187.74     13271996.87      2197787.72     13271596.85
      2196987.71     13270796.84
#Sta/Elev= 30
  4427.3  342.79  4498.0  339.81  4512.2  339.96  4582.9  337.48  4597.0  336.49
  4611.2  336.58  4625.3  335.43  4653.6  334.44  4746.3  332.52  4938.0  326.91
  4978.9  326.87  4986.5  324.94  4989.2  324.44  4992.5  324.94  5007.2  325.09
  5021.3  326.05  5106.1  325.53  5148.6  326.22  5233.4  325.59  5247.6  326.23
  5290.0  325.79  5332.4  326.27  5572.8  331.18  5601.1  332.27  5770.8  334.98
  5898.1  338.59  5954.7  341.05  5968.8  340.84  6071.4  344.16  6124.4  345.77
#Mann=6,-1,0
  4427.3     0.1       0  4746.3    0.05       0  4938.0     0.1       0
  4986.5    0.07       0  4992.5     0.1       0  6071.4    0.05       0
Bank Sta=4986.5,4992.5
Exp/Cntr=0.3,0.1

Type RM Length L Ch R = 1,4889,409,409,409
BEGIN DESCRIPTION:
UNT004 IN SPCR 6.0
END DESCRIPTION:
XS GIS Cut Line= 3
      2198287.69     13271596.82      2197937.72     13271196.85
      2197137.70     13270496.84
#Sta/Elev= 30
  4454.7  334.93  4501.7  333.47  4897.6  323.97  4907.9  323.21  4929.7  323.68
  4936.3  322.58  4979.0  321.65  4989.5  321.12  4996.9  319.61  4999.7  319.11
  5002.9  319.61  5007.5  321.80  5156.5  325.74  5212.5  326.39  5262.8  329.14
  5314.7  330.46  5392.4  331.09  5437.1  331.61  5475.4  332.83  5496.3  332.41
  5563.1  333.43  5564.2  333.49  5691.3  335.16  5718.5  335.88  5818.5  339.16
  5873.8  340.78  5970.9  344.23  6013.6  346.63  6029.2  346.61  6049.2  347.05
#Mann=15,-1,0
  4454.7     0.1       0  4501.7    0.05       0  4897.6     0.1       0
  4996.9    0.07       0  5002.9     0.1       0  5314.7    0.08       0
  5392.4     0.1       0  5437.1    0.08       0  5563.1     0.1       0
  5564.2    0.08       0  5691.3     0.1       0  5718.5    0.08       0
  5818.5     0.1       0  5873.8    0.08       0  6029.2    0.05       0
Bank Sta=4996.9,5002.9
Exp/Cntr=0.3,0.1

Type RM Length L Ch R = 1,4480,417,417,417
BEGIN DESCRIPTION:
UNT004 IN SPCR 5.0
END DESCRIPTION:
XS GIS Cut Line= 3
      2198787.73     13271646.87      2198087.72     13270846.85
      2197287.73     13270396.86
#Sta/Elev= 30
  3926.7  345.18  3948.1  343.54  3962.3  343.72  4071.1  339.28  4142.0  336.77
  4359.0  329.73  4427.4  328.67  4576.2  325.81  4720.7  323.23  4847.8  322.06
  4968.4  323.72  4976.0  323.41  4986.4  320.64  4992.6  320.64  5000.4  318.01
  5003.2  317.51  5006.4  318.01  5012.7  322.68  5025.1  321.68  5202.9  326.75
  5370.6  327.92  5548.4  332.27  5650.9  335.77  5710.3  338.56  5716.1  337.89
  5761.6  339.11  5804.3  341.11  5850.2  341.42  5867.8  342.98  5907.6  345.02
#Mann=10,-1,0
  3926.7     0.1       0  4071.1    0.05       0  4142.0     0.1       0
  4427.4    0.05       0  4576.2     0.1       0  5000.4    0.07       0
  5006.4     0.1       0  5650.9    0.05       0  5761.6    0.08       0
  5867.8    0.05       0
Bank Sta=5000.4,5006.4
Exp/Cntr=0.3,0.1

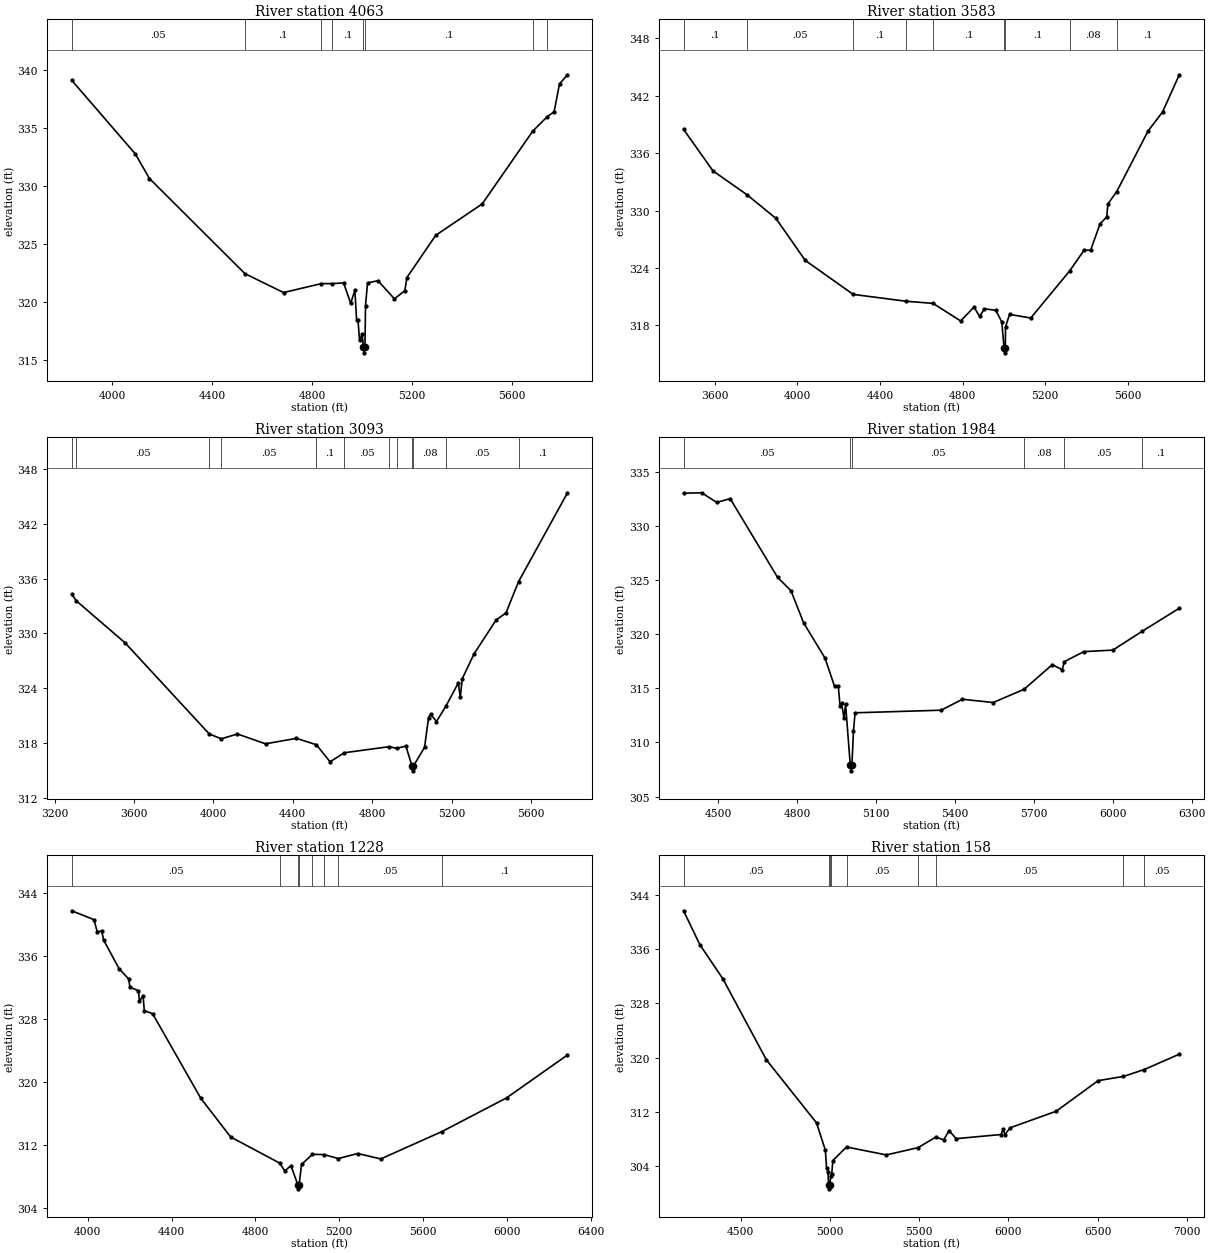
Type RM Length L Ch R = 1,4063,480,480,480
BEGIN DESCRIPTION:
UNT004 IN SPCR 4.0
END DESCRIPTION:
XS GIS Cut Line= 3
      2199087.69     13271296.82      2198287.72     13270496.85
      2197487.75     13270196.86
#Sta/Elev= 30
  3837.3  339.11  4091.8  332.78  4148.4  330.66  4530.8  322.47  4685.8  320.84
  4836.6  321.61  4881.0  321.61  4926.2  321.67  4954.5  319.92  4971.3  321.03
  4978.4  318.46  4983.8  318.47  4990.0  316.73  5000.7  317.25  5005.7  316.15
  5008.4  315.65  5011.7  316.15  5014.0  319.72  5022.0  321.67  5063.9  321.86
  5129.7  320.30  5171.5  321.00  5179.6  322.13  5295.3  325.77  5481.3  328.47
  5683.9  334.74  5739.4  335.93  5769.6  336.42  5791.0  338.81  5823.0  339.59
#Mann=8,-1,0
  3837.3    0.05       0  4530.8     0.1       0  4836.6    0.05       0
  4881.0     0.1       0  5005.7    0.07       0  5011.7     0.1       0
  5683.9    0.08       0  5739.4    0.05       0
Bank Sta=5005.7,5011.7
Exp/Cntr=0.3,0.1

Type RM Length L Ch R = 1,3583,490,490,490
BEGIN DESCRIPTION:
UNT004 IN SPCR 3.0
END DESCRIPTION:
XS GIS Cut Line= 3
      2199437.75     13271046.88      2198237.72     13270046.85
      2197437.76     13269796.87
#Sta/Elev= 30
  3448.9  338.48  3591.5  334.14  3754.9  331.67  3896.1  329.18  4038.0  324.79
  4269.9  321.24  4527.1  320.52  4656.8  320.30  4790.4  318.46  4854.8  319.91
  4882.8  318.93  4904.9  319.74  4960.9  319.57  4989.5  318.37  5000.8  315.63
  5003.6  315.13  5006.8  315.63  5007.7  317.85  5027.2  319.15  5129.9  318.77
  5318.5  323.70  5388.2  325.86  5419.6  325.85  5465.2  328.60  5497.6  329.33
  5503.4  330.69  5546.1  331.98  5697.8  338.31  5767.9  340.30  5849.1  344.19
#Mann=9,-1,0
  3448.9     0.1       0  3754.9    0.05       0  4269.9     0.1       0
  4527.1    0.05       0  4656.8     0.1       0  5000.8    0.07       0
  5006.8     0.1       0  5318.5    0.08       0  5546.1     0.1       0
Bank Sta=5000.8,5006.8
Exp/Cntr=0.3,0.1

Type RM Length L Ch R = 1,3093,1109,1109,1109
BEGIN DESCRIPTION:
UNT004 IN SPCR 2.0
END DESCRIPTION:
XS GIS Cut Line= 3
      2199437.75     13270846.89      2198237.72     13269646.85
      2197437.72     13269646.85
#Sta/Elev= 30
  3286.6  334.27  3310.1  333.55  3555.3  328.96  3979.2  318.98  4040.2  318.45
  4121.0  318.98  4262.5  317.90  4418.0  318.50  4518.8  317.80  4587.7  315.93
  4659.1  316.92  4886.3  317.59  4922.9  317.40  4969.6  317.66  5000.7  315.44
  5003.5  314.94  5006.7  315.44  5063.7  317.51  5083.7  320.75  5093.7  321.16
  5123.7  320.34  5171.5  322.04  5233.7  324.56  5243.7  323.02  5253.7  325.04
  5313.7  327.78  5423.7  331.45  5473.7  332.24  5537.1  335.66  5783.7  345.40
#Mann=12,-1,0
  3286.6     0.1       0  3310.1    0.05       0  3979.2     0.1       0
  4040.2    0.05       0  4518.8     0.1       0  4659.1    0.05       0
  4886.3     0.1       0  4922.9    0.08       0  5000.7    0.07       0
  5006.7    0.08       0  5171.5    0.05       0  5537.1     0.1       0
Bank Sta=5000.7,5006.7
Exp/Cntr=0.3,0.1

Type RM Length L Ch R = 1,1984,756,756,756
BEGIN DESCRIPTION:
Mapping XS 5942baaf
END DESCRIPTION:
XS GIS Cut Line= 3
      2199582.00     13270117.43      2199103.52     13269395.91
      2198132.00     13269084.72
#Sta/Elev= 30
  4367.2  333.01  4436.1  333.05  4493.2  332.16  4544.4  332.51  4724.8  325.24
  4775.9  324.00  4824.0  321.03  4905.3  317.78  4941.4  315.18  4955.8  315.18
  4962.4  313.39  4968.4  313.59  4977.5  312.24  4983.5  313.52  5001.5  307.87
  5004.3  307.37  5007.5  307.87  5013.6  311.05  5019.6  312.73  5346.9  312.97
  5428.1  313.98  5545.1  313.68  5662.5  314.90  5770.0  317.18  5807.4  316.71
  5816.1  317.46  5890.1  318.38  6000.3  318.52  6112.5  320.27  6253.1  322.39
#Mann=6,-1,0
  4367.2    0.05       0  5001.5    0.03       0  5007.5    0.05       0
  5662.5    0.08       0  5816.1    0.05       0  6112.5     0.1       0
Bank Sta=5001.5,5007.5
Exp/Cntr=0.3,0.1

Type RM Length L Ch R = 1,1228,1070,1070,1070
BEGIN DESCRIPTION:
Mapping XS e4453c8a
END DESCRIPTION:
XS GIS Cut Line= 4
      2199847.85     13269676.92      2199604.81     13269152.86
      2198982.00     13268712.34      2197956.68     13268735.12
#Sta/Elev= 30
  3923.6  341.79  4029.6  340.66  4044.9  339.14  4067.0  339.20  4075.4  338.08
  4149.7  334.42  4195.5  333.12  4201.0  332.08  4241.3  331.64  4246.8  330.33
  4264.2  330.96  4269.7  329.11  4309.5  328.71  4539.1  317.98  4681.9  313.05
  4916.0  309.73  4940.4  308.74  4969.9  309.41  5002.6  306.96  5005.4  306.46
  5008.6  306.96  5020.4  309.57  5072.3  310.84  5127.9  310.81  5196.3  310.31
  5288.4  310.95  5398.4  310.26  5690.6  313.74  5998.6  318.01  6289.7  323.47
#Mann=8,-1,0
  3923.6    0.05       0  4916.0     0.1       0  5002.6    0.07       0
  5008.6     0.1       0  5072.3    0.05       0  5127.9    0.08       0
  5196.3    0.05       0  5690.6     0.1       0
Bank Sta=5002.6,5008.6
Exp/Cntr=0.3,0.1

Type RM Length L Ch R = 1,158,0,0,0
BEGIN DESCRIPTION:
UNT004 IN SPCR 1.0
END DESCRIPTION:
XS GIS Cut Line= 4
      2200030.14     13269426.26      2200098.50     13268962.98
      2199627.59     13268370.55      2198085.80     13268211.06
#Sta/Elev= 30
  4181.3  341.66  4272.1  336.68  4401.3  331.63  4645.1  319.68  4925.7  310.39
  4975.3  306.34  4981.7  303.74  4989.6  303.21  4993.2  301.17  4995.9  300.67
  4999.2  301.17  5005.7  302.58  5010.6  302.83  5017.0  304.84  5093.4  306.84
  5316.5  305.67  5494.4  306.75  5592.8  308.29  5637.5  307.89  5667.6  309.24
  5707.8  308.07  5959.2  308.68  5969.2  309.43  5980.6  308.67  6009.4  309.67
  6267.1  312.11  6502.1  316.62  6643.7  317.24  6759.5  318.25  6956.4  320.52
#Mann=9,-1,0
  4181.3    0.05       0  4993.2    0.03       0  4999.2    0.05       0
  5005.7     0.1       0  5093.4    0.05       0  5494.4    0.08       0
  5592.8    0.05       0  6643.7     0.1       0  6759.5    0.05       0
Bank Sta=4993.2,4999.2
Exp/Cntr=0.3,0.1

Chan Stop Cuts=-1