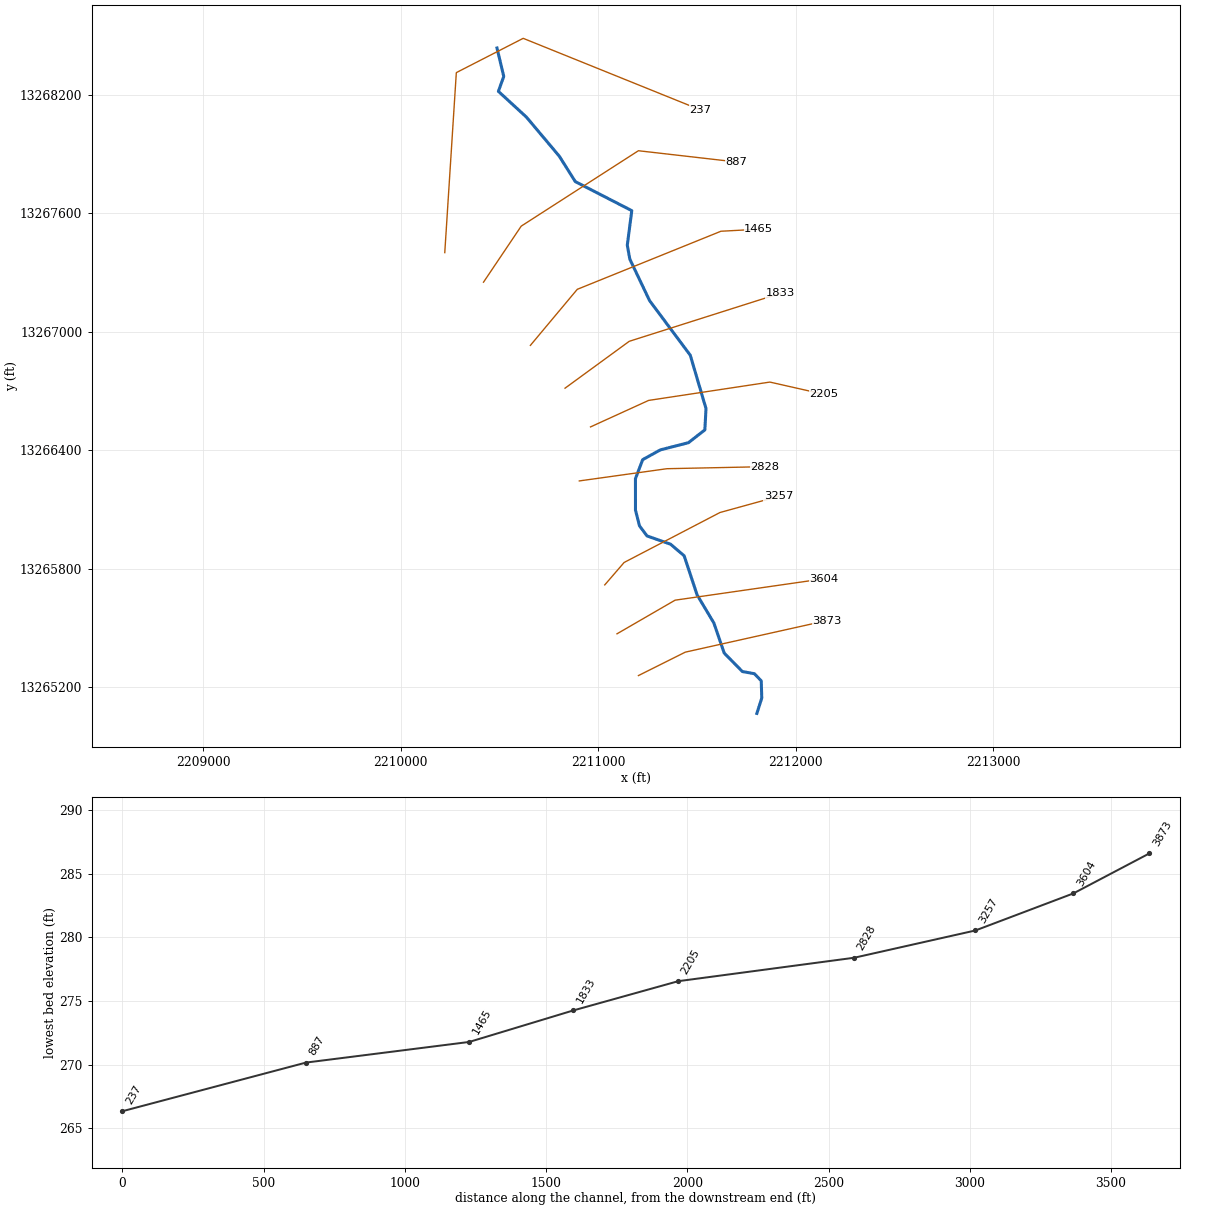
--- UNT007 IN SPCR.prj (project) ---

Proj Title=UNT007 IN SPCR Base Level Engineering
Current Plan=p01
Default Exp/Contr=0.3,0.1
English Units
Geom File=g01
Flow File=f01
Plan File=p01
Y Axis Title=Elevation
X Axis Title(PF)=Main Channel Distance
X Axis Title(XS)=Station
BEGIN DESCRIPTION:
UNT007 IN SPCR
END DESCRIPTION:
DSS Export Rating Curves= 0
DSS Export Rating Curve Sorted= 0
DSS Export Volume Flow Curves= 0
DXF OffsetX= 0
DXF OffsetY= 0
DXF ScaleX= 1
DXF ScaleY= 10

--- UNT007 IN SPCR.p01 (plan) ---

Plan Title=Multiple Run
Short Identifier=Multiple
Geom File=g01
Flow File=f01
Subcritical Flow
K Sum by GR= 0
Std Step Tol= 0.01
Critical Tol= 0.01
Num of Std Step Trials= 20
Max Error Tol= 0.3
Flow Tol Ratio= 0.001
Split Flow NTrial= 30
Split Flow Tol= 0.02
Split Flow Ratio= 0.02
Log Output Level= 0
Friction Slope Method= 1
Unsteady Friction Slope Method= 2
Unsteady Bridges Friction Slope Method= 1
Parabolic Critical Depth
Global Vel Dist=  1 , 1 , 1
Global Log Level= 0
CheckData=True
Encroach Param= -1, 0, 0, 0
BEGIN DESCRIPTION:
Multiple Run
END DESCRIPTION:

--- UNT007 IN SPCR.f01 (steady flow) ---

Flow Title=Multiple
Program Version=4.10
Number of Profiles= 7
Profile Names=10-year,25-year,50-year,1pct_min,100-year,1pct_plu,500-year
River Rch & RM=UNT007 IN SPCR,Reach-1         ,3873
     273     387     483     444     601     813     945
Boundary for River Rch & Prof#=UNT007 IN SPCR,Reach-1         , 1
Up Type= 0
Dn Type= 3
Dn Slope=0.00183
Boundary for River Rch & Prof#=UNT007 IN SPCR,Reach-1         , 2
Up Type= 0
Dn Type= 3
Dn Slope=0.00183
Boundary for River Rch & Prof#=UNT007 IN SPCR,Reach-1         , 3
Up Type= 0
Dn Type= 3
Dn Slope=0.00183
Boundary for River Rch & Prof#=UNT007 IN SPCR,Reach-1         , 4
Up Type= 0
Dn Type= 3
Dn Slope=0.00183
Boundary for River Rch & Prof#=UNT007 IN SPCR,Reach-1         , 5
Up Type= 0
Dn Type= 3
Dn Slope=0.00183
Boundary for River Rch & Prof#=UNT007 IN SPCR,Reach-1         , 6
Up Type= 0
Dn Type= 3
Dn Slope=0.00183
Boundary for River Rch & Prof#=UNT007 IN SPCR,Reach-1         , 7
Up Type= 0
Dn Type= 3
Dn Slope=0.00183
DSS Import GetInterval= 0
DSS Import GetPeak= 0
DSS Import FillOption= 0

--- UNT007 IN SPCR.g01 (geometry) ---

Geom Title=Existing Conditions
Program Version=4.10

River Reach=UNT007 IN SPCR  ,Reach-1
Reach XY= 30
      2211803.42     13265068.16      2211828.34     13265145.71
      2211825.57     13265232.95      2211790.95     13265268.96
      2211730.02     13265280.03      2211638.14     13265373.52
      2211585.76     13265525.86      2211500.87     13265668.16
      2211435.35     13265866.01      2211366.82     13265924.57
      2211247.35     13265966.49      2211209.29     13266017.43
      2211188.84     13266097.05      2211188.78      13266256.7
      2211225.41     13266352.78      2211314.92     13266402.21
      2211457.06     13266438.56      2211540.16     13266503.43
      2211545.96     13266611.33      2211466.36     13266881.37
      2211260.21     13267157.89      2211160.22     13267367.93
      2211147.46     13267438.76      2211170.18     13267613.39
       2210884.3     13267760.35      2210802.84     13267889.56
      2210636.81     13268086.92      2210494.79     13268217.49
      2210522.02     13268292.96      2210487.72     13268436.86

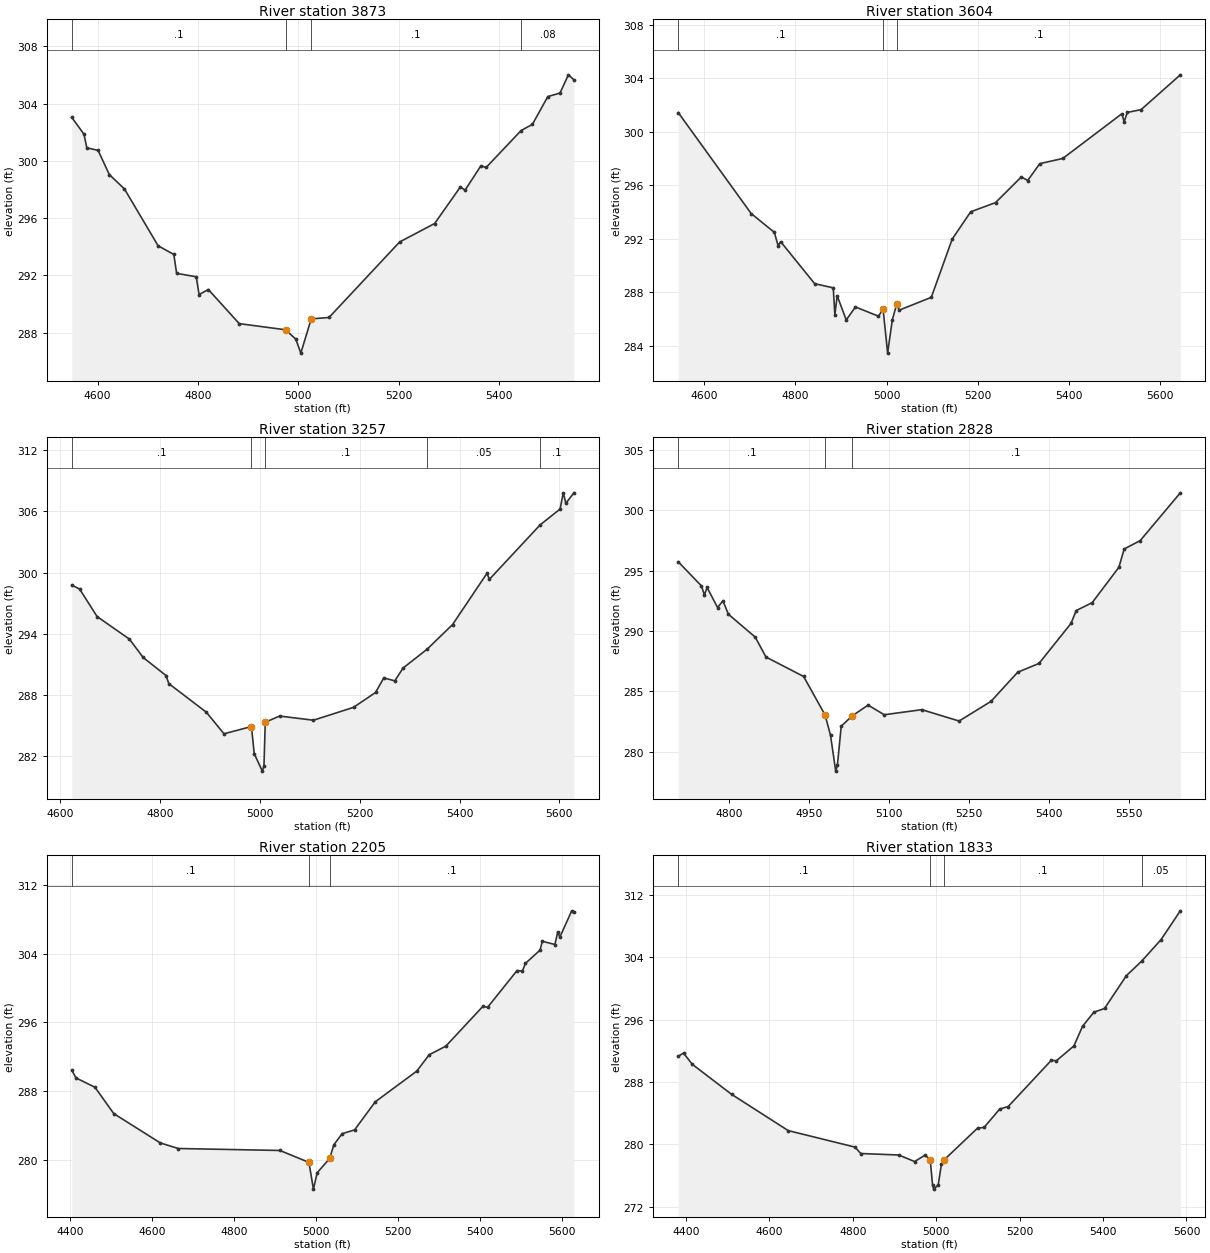
Type RM Length L Ch R = 1 ,3873    ,269,269,269
BEGIN DESCRIPTION:
UNT007 IN SPCR 9.0
END DESCRIPTION:
XS GIS Cut Line= 3
      2211203.79      13265259.5       2211441.1     13265378.15
      2212158.35     13265538.12
#Sta/Elev= 30
  4548.6  303.04    4573  301.86  4578.6  300.91    4601  300.74  4623.3  299.05
  4653.6  298.04  4720.7  294.07  4751.9  293.47  4757.5  292.15  4796.6  291.91
  4802.2  290.67  4820.7  291.02  4882.2  288.64  4974.4  288.21  4994.9  287.56
  5004.9  286.58  5025.6  288.97  5061.1  289.07  5201.7  294.34  5271.5  295.63
  5322.7  298.18  5332.1  297.96  5363.7  299.66    5374  299.54  5443.7  302.12
  5466.2  302.55  5496.9  304.49  5521.3  304.74  5537.9  306.01  5548.8  305.67
#Mann= 4 ,-1 , 0
  4548.6      .1       0  4974.4     .07       0  5025.6      .1       0
  5443.7     .08       0
Bank Sta=4974.4,5025.6
XS Rating Curve= 0 ,0
Exp/Cntr=0.3,0.1

Type RM Length L Ch R = 1 ,3604    ,347,347,347
BEGIN DESCRIPTION:
UNT007 IN SPCR 8.0
END DESCRIPTION:
XS GIS Cut Line= 3
      2211095.37     13265471.01       2211389.5      13265641.3
      2212142.78     13265749.65
#Sta/Elev= 30
  4543.3  301.42  4703.3  293.87    4754  292.47  4762.2  291.48  4767.9  291.77
  4842.5  288.63  4883.2  288.32  4886.7  286.31  4891.8  287.73  4911.7  285.92
  4931.9  286.89  4982.4   286.2  4992.5  286.73  5002.4  283.44  5012.7  285.93
  5022.7  287.14  5027.7  286.65  5098.2  287.61    5144  291.96  5184.5     294
  5239.1  294.69  5295.6  296.61  5309.6  296.34    5336   297.6  5386.5  297.99
    5516  301.33  5521.1  300.74    5528  301.43  5558.3  301.64  5644.2  304.24
#Mann= 3 , 0 , 0
  4543.3      .1       0  4992.5     .07       0  5022.7      .1       0
Bank Sta=4992.5,5022.7
XS Rating Curve= 0 ,0
Exp/Cntr=0.3,0.1

Type RM Length L Ch R = 1 ,3257    ,429,429,429
BEGIN DESCRIPTION:
UNT007 IN SPCR 7.0
END DESCRIPTION:
XS GIS Cut Line= 4
       2211033.5     13265718.73      2211131.51     13265832.21
      2211616.53     13266085.04       2211914.3     13266167.18
#Sta/Elev= 30
  4623.1  298.76  4638.8  298.38  4673.9  295.68  4738.6  293.47  4766.1  291.67
  4811.9   289.9  4817.5  289.11  4892.8   286.3    4928  284.19    4983   284.9
  4988.6  282.25  5004.8  280.53  5008.1  281.03  5010.7  285.32  5039.4  285.93
  5107.1  285.52  5187.5  286.78  5231.7  288.24  5248.1  289.67  5270.2  289.38
  5286.7  290.63  5334.9  292.48    5386   294.9  5454.7  299.91  5459.9  299.34
  5561.4  304.67  5601.3  306.22  5607.7  307.81  5612.9  306.78  5628.9  307.81
#Mann= 5 ,-1 , 0
  4623.1      .1       0    4983     .07       0  5010.7      .1       0
  5334.9     .05       0  5561.4      .1       0
Bank Sta=4983,5010.7
XS Rating Curve= 0 ,0
Exp/Cntr=0.3,0.1

Type RM Length L Ch R = 1 ,2828    ,623,623,623
BEGIN DESCRIPTION:
UNT007 IN SPCR 6.0
END DESCRIPTION:
XS GIS Cut Line= 3
      2210904.51       13266245.      2211348.22     13266306.91
      2211843.11     13266317.22
#Sta/Elev= 30
  4703.9  295.73  4747.5  293.73    4753  292.98  4758.1   293.6  4777.8  291.94
  4787.9   292.5    4798  291.39  4848.5  289.49  4868.7  287.84  4939.4  286.23
  4979.8  283.03  4989.9  281.36  4999.7  278.39  5002.9  278.89    5010  282.11
  5030.2  282.95  5060.5  283.86  5090.8  283.06  5161.4  283.48  5231.4  282.54
  5291.4  284.17  5341.4  286.58  5381.5  287.31  5441.5  290.62  5451.5  291.69
  5481.5  292.35  5531.5  295.27  5541.5  296.79  5571.5  297.48  5646.9  301.44
#Mann= 3 , 0 , 0
  4703.9      .1       0  4979.8     .07       0  5030.2      .1       0
Bank Sta=4979.8,5030.2
XS Rating Curve= 0 ,0
Exp/Cntr=0.3,0.1

Type RM Length L Ch R = 1 ,2205    ,372,372,372
BEGIN DESCRIPTION:
UNT007 IN SPCR 5.0
END DESCRIPTION:
XS GIS Cut Line= 4
      2210961.24     13266518.46      2211255.35     13266652.62
      2211869.36     13266745.49      2212142.79     13266683.58
#Sta/Elev= 30
  4404.1  290.43  4414.5  289.52  4460.6  288.44  4506.6  285.36  4620.1  281.94
    4664  281.29  4911.8  281.06  4982.6  279.67  4993.5  276.55  5002.8  278.47
  5033.2  280.13  5043.3  281.72  5063.5  283.02  5093.8  283.46  5144.4  286.74
  5245.6  290.32  5275.9  292.23  5316.4  293.23  5406.6  297.86  5418.4  297.77
  5490.2  302.05  5503.1  301.99  5510.7  302.89  5546.3  304.44  5551.7  305.47
  5582.5  305.09  5589.4  306.54  5594.6  305.95  5623.5  309.02  5628.7  308.87
#Mann= 3 , 0 , 0
  4404.1      .1       0  4982.6     .07       0  5033.2      .1       0
Bank Sta=4982.6,5033.2
XS Rating Curve= 0 ,0
Exp/Cntr=0.3,0.1

Type RM Length L Ch R = 1 ,1833    ,368,368,368
BEGIN DESCRIPTION:
UNT007 IN SPCR 4.0
END DESCRIPTION:
XS GIS Cut Line= 3
      2210832.24     13266714.53      2211157.31     13266951.88
      2211920.93     13267194.38
#Sta/Elev= 30
  4381.6   291.3  4394.3  291.71  4415.2  290.27  4509.4  286.42  4645.3  281.76
  4805.5  279.64  4819.2  278.82  4910.4  278.63  4948.2  277.79  4973.4  278.61
  4985.7  278.03  4991.4  274.75  4994.1  274.25  5004.9  274.79  5012.7  277.51
  5017.9  277.95  5099.3  282.08  5114.7  282.16  5152.2  284.52  5172.7  284.85
    5276  290.78  5288.2  290.72  5330.1  292.62  5351.1  295.16    5378  296.95
  5403.6  297.43    5456  301.64  5492.6   303.5  5539.3  306.28  5585.3  309.96
#Mann= 4 ,-1 , 0
  4381.6      .1       0  4985.7     .07       0  5017.9      .1       0
  5492.6     .05       0
Bank Sta=4985.7,5017.9
XS Rating Curve= 0 ,0
Exp/Cntr=0.3,0.1

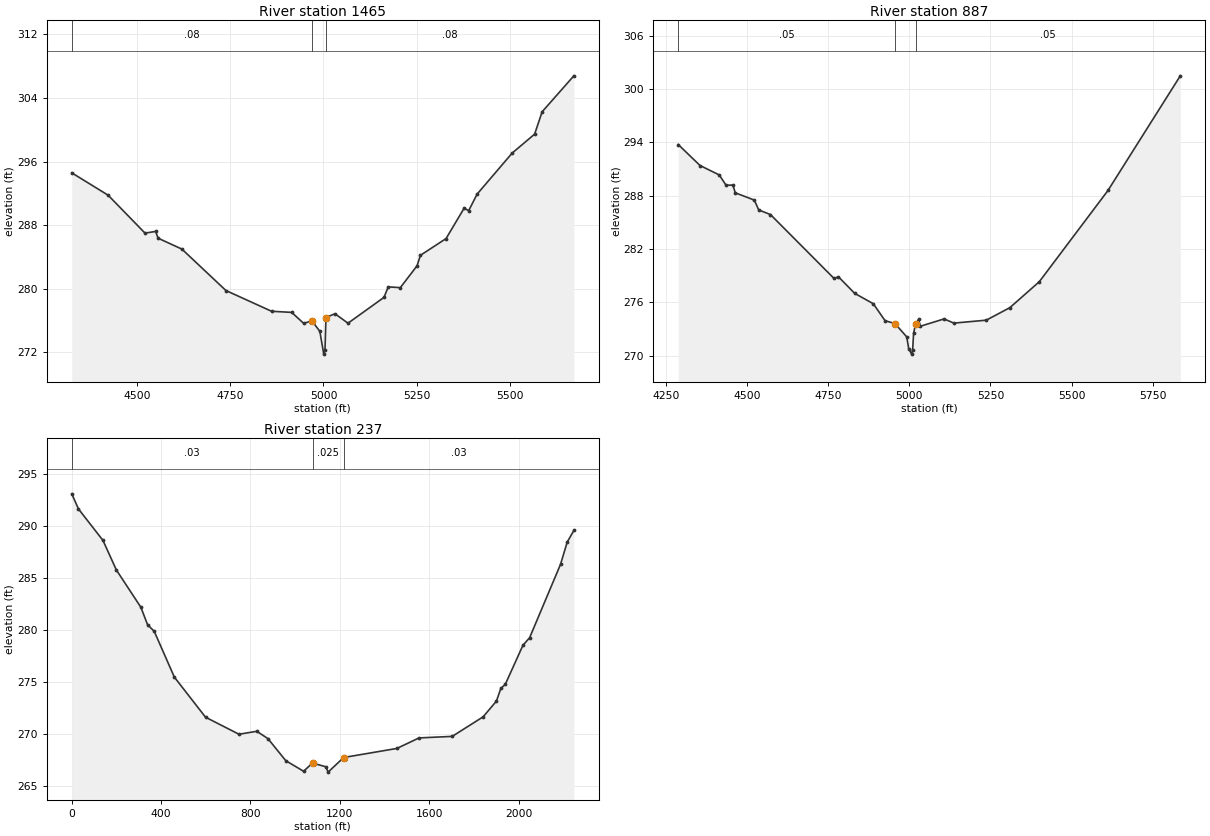
Type RM Length L Ch R = 1 ,1465    ,578,578,578
BEGIN DESCRIPTION:
UNT007 IN SPCR 3.0
END DESCRIPTION:
XS GIS Cut Line= 4
      2210656.82     13266931.25      2210894.16     13267215.03
      2211621.69     13267509.14      2211812.64     13267519.46
#Sta/Elev= 30
  4325.3  294.58  4422.7  291.77  4521.6     287  4550.2  287.21  4556.7  286.36
  4620.5  284.99  4738.5  279.78  4860.9  277.17  4914.8  277.03  4947.2  275.64
  4968.7  275.98  4990.3  274.65  5000.8  271.78  5004.1  272.28  5006.7  276.38
  5030.8  276.86  5065.8  275.67  5162.3  278.92  5173.7  280.24    5206  280.14
  5250.8  282.88    5260  284.21  5328.6  286.31  5376.9  290.12  5389.4  289.83
  5411.8   291.9    5506  297.07  5566.1  299.45  5586.2  302.26  5671.2  306.78
#Mann= 3 , 0 , 0
  4325.3     .08       0  4968.7     .05       0  5006.7     .08       0
Bank Sta=4968.7,5006.7
XS Rating Curve= 0 ,0
Exp/Cntr=0.3,0.1

Type RM Length L Ch R = 1 ,887     ,650,650,650
BEGIN DESCRIPTION:
UNT007 IN SPCR 2.0
END DESCRIPTION:
XS GIS Cut Line= 4
      2210419.47     13267251.16      2210610.37     13267534.94
      2211203.75     13267916.76      2211699.09       13267860.
#Sta/Elev= 30
  4288.7  293.74  4355.8  291.38    4415  290.32    4436  289.16    4457  289.18
  4464.3  288.31    4523  287.49  4536.6  286.38  4572.8  285.86  4768.6  278.67
  4782.1  278.86    4832     277  4889.4  275.83  4925.7  273.92  4956.1   273.6
  4992.4   272.1  4998.4  270.78  5007.4  270.16  5010.6  270.66  5013.6  272.54
    5020   273.6  5028.8  274.06  5034.7   273.3  5107.3  274.12  5137.7  273.65
  5237.4  273.98    5310  275.39  5400.7  278.31  5612.1  288.57  5834.9  301.47
#Mann= 3 , 0 , 0
  4288.7     .05       0  4956.1     .03       0    5020     .05       0
Bank Sta=4956.1,5020
XS Rating Curve= 0 ,0
Exp/Cntr=0.3,0.1

Type RM Length L Ch R = 1 ,237     ,0,0,0
BEGIN DESCRIPTION:
UNT007 IN SPCR 1.0
END DESCRIPTION:
XS GIS Cut Line= 4
     2210223.392    13267400.782     2210281.874    13268312.183
     2210620.416    13268485.794     2211518.494     13268123.15
#Sta/Elev= 30
       0293.133229.93602291.6808139.7014 288.646199.5734 285.804309.3388 282.213
339.2748280.5319369.2108279.8939459.0189275.4926598.7203271.6282748.4004269.9891
828.2297270.2703878.1231269.5667957.9167267.44431037.689 266.4241077.575267.2198
1137.404266.85351147.376266.34081217.176267.74821455.294268.62131554.304269.6338
1702.819269.78111841.433271.66641900.839273.17881920.641274.40261940.443274.7907
2019.651278.55962049.354279.27732187.969286.35542217.672288.48942247.375289.6037
#Mann= 3 , 0 , 0
       0     .03       01077.575    .025       01217.176     .03       0
Bank Sta=1077.575,1217.176
XS Rating Curve= 0 ,0
Exp/Cntr=0.3,0.1

Chan Stop Cuts=-1
Use User Specified Reach Order=0
Composite Channel Slope=5