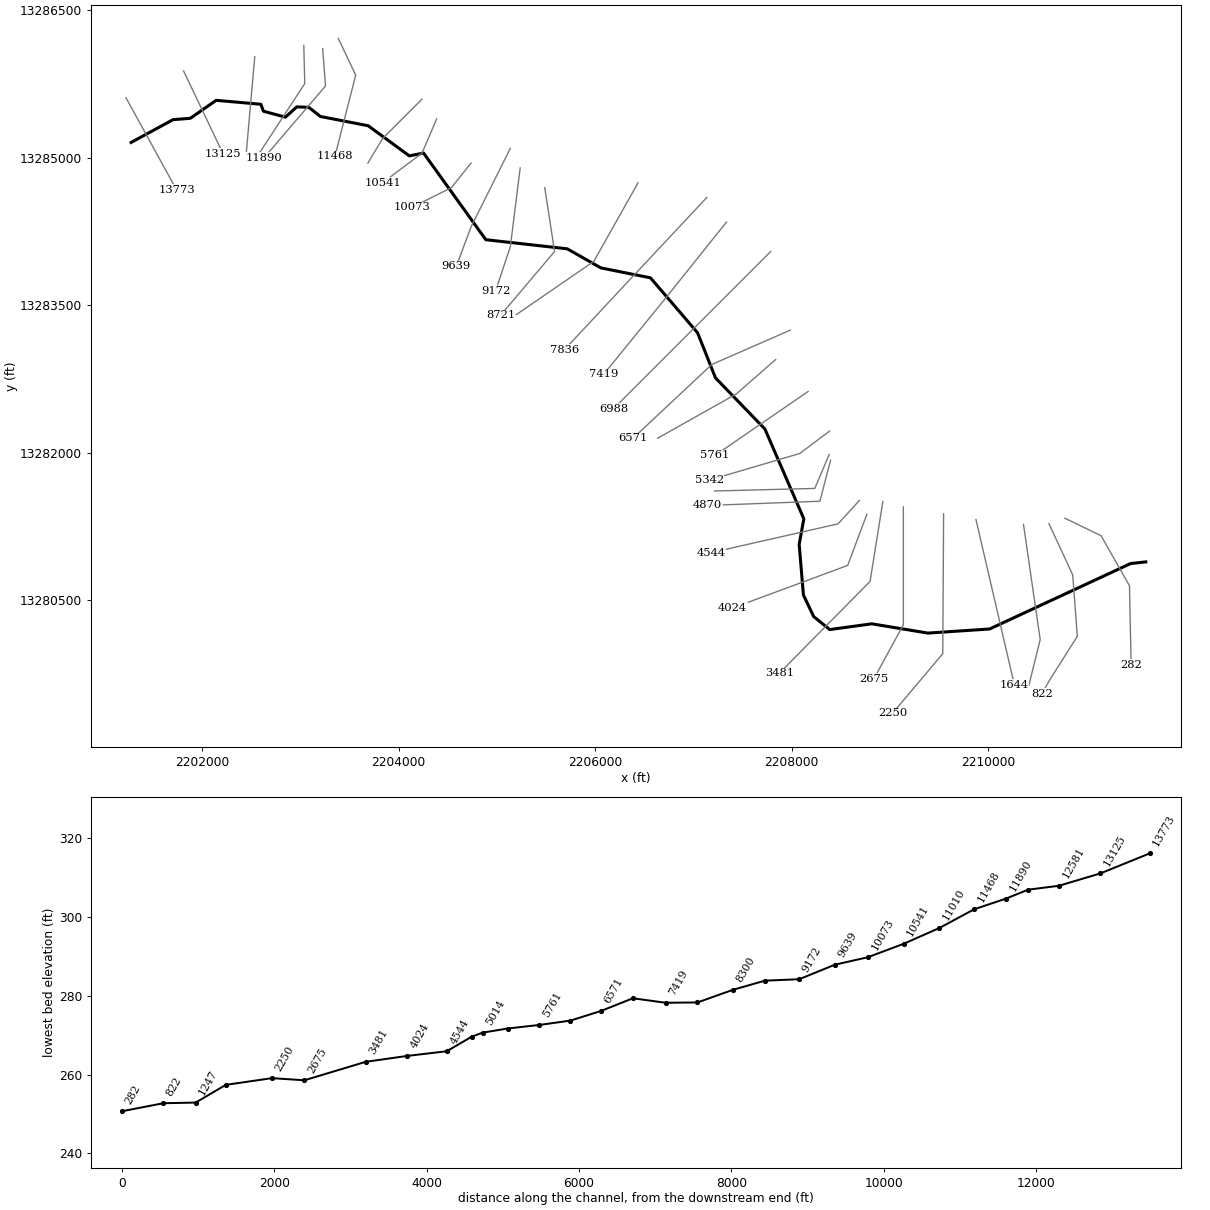
--- UNT008 IN SPCR.prj (project) ---

Proj Title=UNT008 IN SPCR Base Level Engineering
Current Plan=p01
Default Exp/Contr=0.3,0.1
English Units
Geom File=g01
Flow File=f01
Plan File=p01
Y Axis Title=Elevation
X Axis Title(PF)=Main Channel Distance
X Axis Title(XS)=Station
BEGIN DESCRIPTION:
UNT008 IN SPCR
END DESCRIPTION:
DSS Export Rating Curves= 0
DSS Export Rating Curve Sorted= 0
DSS Export Volume Flow Curves= 0
DXF OffsetX= 0
DXF OffsetY= 0
DXF ScaleX= 1
DXF ScaleY= 10

--- UNT008 IN SPCR.p01 (plan) ---

Plan Title=Multiple Run
Short Identifier=Multiple
Geom File=g01
Flow File=f01
Subcritical Flow
K Sum by GR= 0
Std Step Tol= 0.01
Critical Tol= 0.01
Num of Std Step Trials= 20
Max Error Tol= 0.3
Flow Tol Ratio= 0.001
Split Flow NTrial= 30
Split Flow Tol= 0.02
Split Flow Ratio= 0.02
Log Output Level= 0
Friction Slope Method= 1
Unsteady Friction Slope Method= 2
Unsteady Bridges Friction Slope Method= 1
Parabolic Critical Depth
Global Vel Dist=  1 , 1 , 1
Global Log Level= 0
CheckData=True
Encroach Param= -1, 0, 0, 0
BEGIN DESCRIPTION:
Multiple Run
END DESCRIPTION:

--- UNT008 IN SPCR.f01 (steady flow) ---

Flow Title=Multiple
Program Version=4.10
Number of Profiles= 7
Profile Names=10-year,25-year,50-year,1pct_min,100-year,1pct_plu,500-year
River Rch & RM=UNT008 IN SPCR,Reach-1         ,13773
     364     519     651     600     812    1098    1283
River Rch & RM=UNT008 IN SPCR,Reach-1         ,11010
     458     660     833     773    1045    1413    1670
River Rch & RM=UNT008 IN SPCR,Reach-1         ,6988
     482     695     878     815    1102    1491    1765
River Rch & RM=UNT008 IN SPCR,Reach-1         ,4870
     580     843    1071     998    1350    1825    2181
River Rch & RM=UNT008 IN SPCR,Reach-1         ,3481
     586     851    1081    1006    1361    1840    2193
Boundary for River Rch & Prof#=UNT008 IN SPCR,Reach-1         , 1
Up Type= 0
Dn Type= 3
Dn Slope=0.005
Boundary for River Rch & Prof#=UNT008 IN SPCR,Reach-1         , 2
Up Type= 0
Dn Type= 3
Dn Slope=0.005
Boundary for River Rch & Prof#=UNT008 IN SPCR,Reach-1         , 3
Up Type= 0
Dn Type= 3
Dn Slope=0.005
Boundary for River Rch & Prof#=UNT008 IN SPCR,Reach-1         , 4
Up Type= 0
Dn Type= 3
Dn Slope=0.005
Boundary for River Rch & Prof#=UNT008 IN SPCR,Reach-1         , 5
Up Type= 0
Dn Type= 3
Dn Slope=0.005
Boundary for River Rch & Prof#=UNT008 IN SPCR,Reach-1         , 6
Up Type= 0
Dn Type= 3
Dn Slope=0.005
Boundary for River Rch & Prof#=UNT008 IN SPCR,Reach-1         , 7
Up Type= 0
Dn Type= 3
Dn Slope=0.005
DSS Import GetInterval= 0
DSS Import GetPeak= 0
DSS Import FillOption= 0

--- UNT008 IN SPCR.g01 (geometry) ---

Geom Title=Existing Conditions
Program Version=4.10

River Reach=UNT008 IN SPCR  ,Reach-1
Reach XY= 30
      2201277.72     13285156.86      2201704.33     13285388.69
      2201880.03     13285402.64      2202143.35     13285585.48
      2202598.02     13285545.44      2202624.47     13285474.71
      2202847.87     13285414.33      2202964.21     13285519.23
      2203086.59     13285514.03      2203204.59     13285420.98
      2203690.59     13285326.86      2204109.36     13285020.14
      2204254.14     13285049.03      2204887.72     13284166.86
       2205716.6     13284074.18      2206059.01     13283879.97
      2206563.82     13283778.83      2207043.22     13283219.63
      2207225.83     13282760.16      2207728.26     13282240.44
        2208125.     13281325.69      2208077.46     13281066.77
      2208120.75     13280550.33      2208225.61     13280330.11
      2208388.36     13280198.67      2208816.26     13280257.14
      2209387.75     13280162.81      2210015.89      13280204.5
      2211450.83     13280870.62      2211605.72     13280887.44

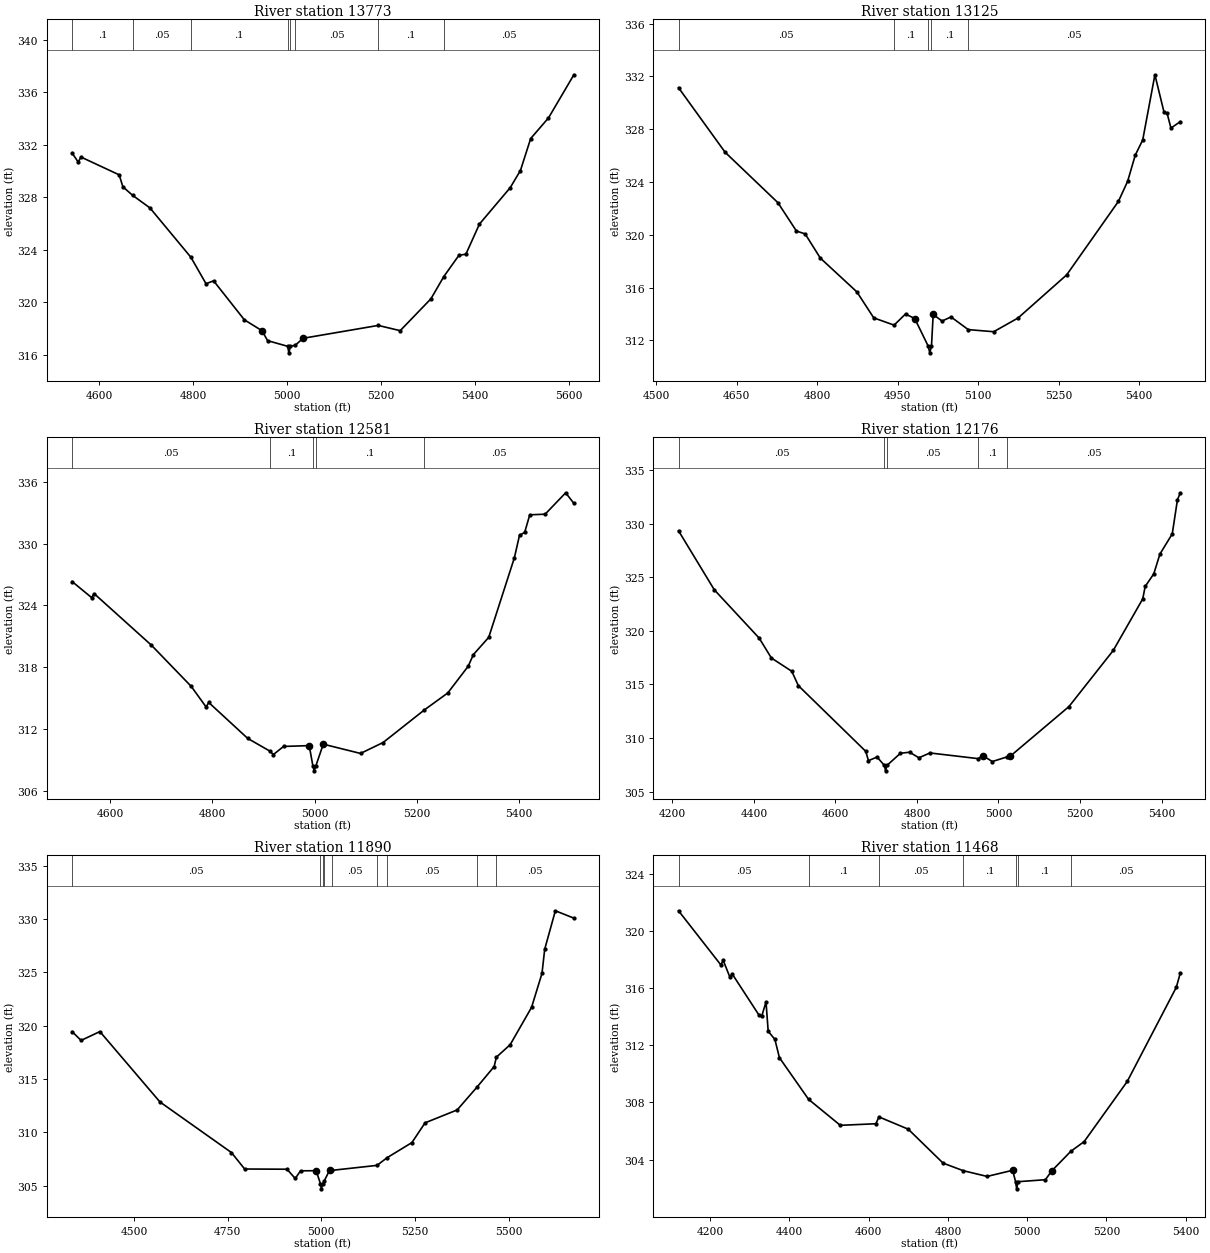
Type RM Length L Ch R = 1 ,13773   ,648,648,648
BEGIN DESCRIPTION:
UNT008 IN SPCR 29.0
END DESCRIPTION:
XS GIS Cut Line= 2
      2201225.44     13285611.59      2201739.15     13284675.37
#Sta/Elev= 30
  4542.2  331.38  4555.3  330.68    4561  331.07  4642.5  329.71  4650.3   328.8
    4671  328.15  4707.9  327.19    4795  323.43  4827.3  321.41  4843.4  321.63
  4908.8  318.66  4946.7  317.82  4958.2  317.07  5000.9  316.64  5003.6  316.14
  5006.9  316.64  5017.2  316.72  5033.9  317.25  5193.8  318.23  5240.5  317.83
  5305.9  320.26  5333.4  321.96  5365.6  323.58  5380.3  323.66  5409.2  325.96
  5474.6  328.73  5496.4  330.04  5518.2  332.48  5556.1  334.05  5610.1  337.34
#Mann= 8 ,-1 , 0
  4542.2      .1       0    4671     .05       0    4795      .1       0
  5000.9     .07       0  5006.9      .1       0  5017.2     .05       0
  5193.8      .1       0  5333.4     .05       0
Bank Sta=4946.7,5033.9
XS Rating Curve= 0 ,0
Exp/Cntr=0.3,0.1

Type RM Length L Ch R = 1 ,13125   ,544,544,544
BEGIN DESCRIPTION:
UNT008 IN SPCR 28.0
END DESCRIPTION:
XS GIS Cut Line= 2
      2201811.17     13285885.23      2202214.08     13285041.05
#Sta/Elev= 30
  4541.4  331.15  4628.2  326.26  4726.6  322.44  4761.2  320.29  4777.5  320.07
  4805.7  318.24  4873.8  315.68  4905.3  313.71  4943.2  313.16  4964.5     314
  4981.7  313.66  5006.9  311.56  5009.7  311.06  5012.9  311.56  5016.1  313.97
  5032.6  313.47  5049.3  313.78  5081.5  312.82  5128.9  312.66  5174.3   313.7
    5265  316.97  5361.3  322.53  5378.5  324.05  5392.8  326.04  5406.7  327.19
  5429.4  332.13  5446.5  329.28  5452.1  329.22  5459.3  328.09  5476.8  328.58
#Mann= 5 ,-1 , 0
  4541.4     .05       0  4943.2      .1       0  5006.9     .07       0
  5012.9      .1       0  5081.5     .05       0
Bank Sta=4981.7,5016.1
XS Rating Curve= 0 ,0
Exp/Cntr=0.3,0.1

Type RM Length L Ch R = 1 ,12581   ,405,405,405
BEGIN DESCRIPTION:
UNT008 IN SPCR 27.0
END DESCRIPTION:
XS GIS Cut Line= 2
      2202536.14     13286029.29      2202449.81     13285050.89
#Sta/Elev= 30
  4525.4  326.31  4563.6  324.75  4568.7  325.13  4680.8  320.12  4758.7  316.12
  4787.8  314.12  4792.9  314.56  4869.2  311.07  4912.8  309.83  4919.4   309.5
  4939.4  310.29  4989.6  310.37  4996.7  308.42  4999.4  307.92  5002.7  308.42
  5017.1  310.51    5090  309.61  5134.2  310.67  5214.8  313.83  5260.7  315.48
  5300.8  318.08  5310.9  319.21    5341  320.89  5391.2  328.62  5401.2   330.8
  5411.3  331.08  5421.3  332.79  5451.4  332.85  5491.6  334.93  5507.6   333.9
#Mann= 5 ,-1 , 0
  4525.4     .05       0  4912.8      .1       0  4996.7     .07       0
  5002.7      .1       0  5214.8     .05       0
Bank Sta=4989.6,5017.1
XS Rating Curve= 0 ,0
Exp/Cntr=0.3,0.1

Type RM Length L Ch R = 1 ,12176   ,286,286,286
BEGIN DESCRIPTION:
UNT008 IN SPCR 26.0
END DESCRIPTION:
XS GIS Cut Line= 3
      2203035.44     13286144.49      2203045.04     13285755.59
      2202584.82     13285050.87
#Sta/Elev= 30
  4215.3  329.35    4303  323.84    4413  319.33    4443  317.47    4493  316.23
  4509.1  314.89  4674.5  308.75  4681.1  307.88  4702.2  308.22  4720.3  307.43
    4723  306.93  4726.3  307.43  4759.5  308.57    4782  308.67  4804.8  308.15
  4831.9   308.6  4950.2  308.07  4961.6  308.34    4985   307.8  5020.8  308.23
    5028  308.27  5172.8  312.93  5281.4  318.17  5353.8  322.99  5359.8  324.15
  5380.9  325.33    5396  327.18  5426.2  329.06  5438.9  332.24    5446   332.9
#Mann= 5 ,-1 , 0
  4215.3     .05       0  4720.3     .07       0  4726.3     .05       0
  4950.2      .1       0  5020.8     .05       0
Bank Sta=4961.6,5028
XS Rating Curve= 0 ,0
Exp/Cntr=0.3,0.1

Type RM Length L Ch R = 1 ,11890   ,422,422,422
BEGIN DESCRIPTION:
UNT008 IN SPCR 25.0
END DESCRIPTION:
XS GIS Cut Line= 3
      2203227.48     13286110.91      2203256.29     13285731.58
      2202632.47     13285002.19
#Sta/Elev= 30
  4334.2  319.44  4358.3  318.61  4408.5  319.44  4568.9  312.84    4760  308.09
  4795.1  306.55  4908.2  306.53  4930.2  305.66  4944.4  306.38  4986.1  306.39
  4997.4  305.19  5000.2  304.69  5003.4  305.19  5007.3   305.4  5022.4  306.46
  5029.6  306.43  5148.6  306.89  5175.6  307.61  5241.9  309.03    5277  310.88
  5362.7  312.09  5415.4  314.22  5461.5  316.16  5467.5  317.04  5504.3  318.21
  5561.4  321.71  5589.3   324.9  5596.5  327.16    5625  330.77  5674.4  330.08
#Mann= 9 ,-1 , 0
  4334.2     .05       0  4997.4     .03       0  5003.4     .05       0
  5007.3      .1       0  5029.6     .05       0  5148.6      .1       0
  5175.6     .05       0  5415.4     .08       0  5467.5     .05       0
Bank Sta=4986.1,5022.4
XS Rating Curve= 0 ,0
Exp/Cntr=0.3,0.1

Type RM Length L Ch R = 1 ,11468   ,458,458,458
BEGIN DESCRIPTION:
UNT008 IN SPCR 24.0
END DESCRIPTION:
XS GIS Cut Line= 3
      2203385.91      13286216.5      2203563.56     13285842.01
      2203352.53     13285017.06
#Sta/Elev= 30
  4120.4  321.43  4227.4  317.63  4232.9  317.97  4250.1  316.77  4255.7  317.01
  4323.9   314.1  4330.3  314.05  4341.1  315.04  4346.6  312.99  4363.5  312.42
  4374.9  311.14  4448.5  308.22  4528.5   306.4  4618.3  306.51    4626  306.99
  4699.9  306.13  4787.9  303.75  4838.9  303.22  4898.9  302.82  4963.4  303.25
  4970.7  302.45  4973.5  301.95  4976.7  302.45    5046  302.59  5062.1  303.21
  5109.8  304.57  5143.8  305.26  5252.4  309.47  5376.3  316.07  5386.4  317.08
#Mann= 7 ,-1 , 0
  4120.4     .05       0  4448.5      .1       0    4626     .05       0
  4838.9      .1       0  4970.7     .07       0  4976.7      .1       0
  5109.8     .05       0
Bank Sta=4963.4,5062.1
XS Rating Curve= 0 ,0
Exp/Cntr=0.3,0.1

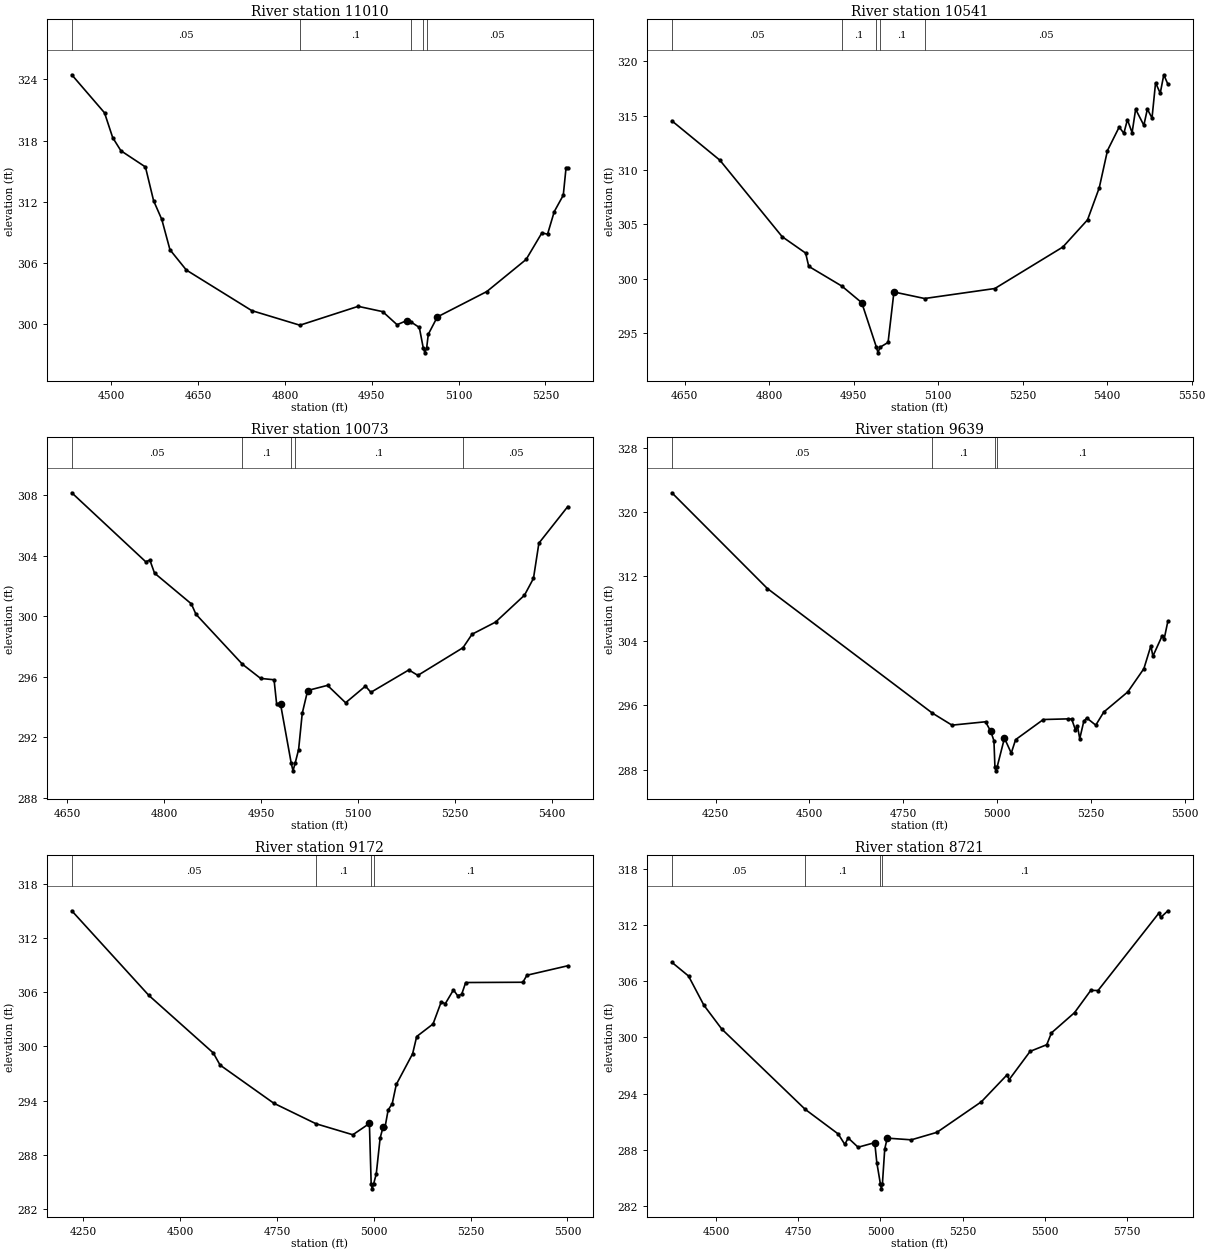
Type RM Length L Ch R = 1 ,11010   ,469,469,469
BEGIN DESCRIPTION:
UNT008 IN SPCR 23.0
END DESCRIPTION:
XS GIS Cut Line= 3
      2204237.74     13285596.87      2203837.72     13285196.85
       2203687.7     13284946.82
#Sta/Elev= 30
  4431.4  324.45    4488  320.72  4502.1  318.29  4516.3     317  4558.7  315.41
  4572.8   312.1    4587  310.26  4601.1  307.29  4629.4   305.3  4742.5  301.32
  4825.7  299.89  4926.4  301.74  4968.8  301.22  4993.6  299.94  5010.7  300.35
  5018.4  300.18  5032.1  299.67  5038.8  297.68  5041.6  297.18  5044.8  297.68
  5047.6     299  5063.2   300.7  5148.7  303.19  5216.7  306.34    5244  308.95
  5253.7  308.81  5265.3  311.03  5280.9  312.64  5285.7  315.34  5288.7  315.34
#Mann= 5 ,-1 , 0
  4431.4     .05       0  4825.7      .1       0  5018.4     .05       0
  5038.8     .07       0  5044.8     .05       0
Bank Sta=5010.7,5063.2
XS Rating Curve= 0 ,0
Exp/Cntr=0.3,0.1

Type RM Length L Ch R = 1 ,10541   ,468,468,468
BEGIN DESCRIPTION:
UNT008 IN SPCR 22.0
END DESCRIPTION:
XS GIS Cut Line= 3
      2204387.71     13285396.83      2204237.72     13285046.85
      2203837.69     13284746.83
#Sta/Elev= 30
    4627  314.53  4712.2  310.91  4822.8  303.87  4864.5  302.36    4870  301.14
  4928.9  299.32  4964.2  297.79  4990.3  293.68    4993  293.18  4996.3  293.68
  5010.9  294.14  5021.3  298.78  5075.8  298.18  5200.5   299.1  5321.3  302.92
  5365.1  305.42  5385.9  308.37  5400.5   311.8  5421.3  313.96  5429.6  313.38
  5435.9  314.64  5444.2  313.44  5450.5   315.6  5465.1  314.12  5471.3  315.61
  5479.6  314.79  5485.9  318.04  5494.2  317.07  5500.5  318.77  5507.8   317.9
#Mann= 5 ,-1 , 0
    4627     .05       0  4928.9      .1       0  4990.3     .07       0
  4996.3      .1       0  5075.8     .05       0
Bank Sta=4964.2,5021.3
XS Rating Curve= 0 ,0
Exp/Cntr=0.3,0.1

Type RM Length L Ch R = 1 ,10073   ,434,434,434
BEGIN DESCRIPTION:
UNT008 IN SPCR 21.0
END DESCRIPTION:
XS GIS Cut Line= 3
      2204737.71     13284946.84      2204537.72     13284696.85
      2204137.76     13284496.88
#Sta/Elev= 30
  4657.3  308.16  4771.7   303.6  4778.1  303.71  4785.3  302.85  4842.2  300.82
  4849.4  300.13  4921.2  296.83  4949.4  295.89  4970.2   295.8  4974.2   294.2
  4980.2   294.2  4996.8  290.28  4999.5  289.78  5002.8  290.28  5008.2  291.19
  5013.8  293.58  5022.2  295.09  5052.9  295.43  5080.9  294.28  5111.6  295.38
    5120  294.97  5178.7  296.45  5192.7  296.09  5262.5  297.92  5276.5  298.81
  5312.8  299.61  5357.6  301.39  5371.5   302.5  5379.9  304.83  5424.6  307.25
#Mann= 5 ,-1 , 0
  4657.3     .05       0  4921.2      .1       0  4996.8     .07       0
  5002.8      .1       0  5262.5     .05       0
Bank Sta=4980.2,5022.2
XS Rating Curve= 0 ,0
Exp/Cntr=0.3,0.1

Type RM Length L Ch R = 1 ,9639    ,467,467,467
BEGIN DESCRIPTION:
UNT008 IN SPCR 20.0
END DESCRIPTION:
XS GIS Cut Line= 3
      2205137.73     13285096.87      2204737.72     13284296.85
      2204587.74     13283896.89
#Sta/Elev= 30
  4133.4  322.39  4387.8  310.51  4827.3  295.05  4879.7  293.55  4969.1  293.97
  4983.1  292.77  4991.5  291.61  4994.1  288.38  4996.8  287.88  5000.1  288.38
  5019.5  291.94  5037.6  290.08  5049.2  291.75  5123.1  294.25  5188.9  294.33
  5198.7   294.3  5208.5  292.98  5213.9  293.47  5220.1  291.87  5230.8  294.01
  5238.8  294.44  5262.8  293.55  5284.2  295.18  5348.2  297.68    5391  300.56
  5409.7   303.4    5415  302.11  5439.9  304.66  5445.3   304.3    5455  306.47
#Mann= 4 ,-1 , 0
  4133.4     .05       0  4827.3      .1       0  4994.1     .07       0
  5000.1      .1       0
Bank Sta=4983.1,5019.5
XS Rating Curve= 0 ,0
Exp/Cntr=0.3,0.1

Type RM Length L Ch R = 1 ,9172    ,451,451,451
BEGIN DESCRIPTION:
UNT008 IN SPCR 19.0
END DESCRIPTION:
XS GIS Cut Line= 3
      2205237.72     13284896.84      2205137.72     13284096.85
      2204987.71     13283646.81
#Sta/Elev= 30
  4220.4  315.05  4419.4  305.66  4585.7  299.28  4603.3  297.93  4741.9   293.7
    4851  291.42    4946   290.2  4988.8  291.45  4993.4   284.7  4996.1   284.2
  4999.4   284.7  5006.5  285.85  5016.5  289.84  5024.1  291.05  5029.2  291.05
  5037.2  292.95  5047.7  293.64  5058.2  295.78  5100.4  299.19  5110.9   301.1
  5153.1  302.49  5174.2  304.94  5184.7  304.74  5205.8  306.27  5216.4  305.64
  5226.9  305.77  5237.4  307.09    5385  307.12  5395.5   307.9    5501  308.95
#Mann= 4 ,-1 , 0
  4220.4     .05       0    4851      .1       0  4993.4     .07       0
  4999.4      .1       0
Bank Sta=4988.8,5024.1
XS Rating Curve= 0 ,0
Exp/Cntr=0.3,0.1

Type RM Length L Ch R = 1 ,8721    ,421,421,421
BEGIN DESCRIPTION:
UNT008 IN SPCR 18.0
END DESCRIPTION:
XS GIS Cut Line= 3
      2205487.71      13284696.9      2205587.72     13284046.85
       2205037.7     13283396.83
#Sta/Elev= 30
  4365.6     308  4416.2  306.54    4463  303.42  4517.4  300.88  4771.3  292.31
  4871.5  289.69  4891.8  288.57  4901.9  289.26  4932.2  288.27  4982.8  288.76
  4989.1  286.64  5000.1  284.33  5002.8  283.83  5006.1  284.33  5013.2  288.08
  5020.8  289.24  5094.1  289.06  5172.1  289.86  5307.3  293.12  5385.3  295.99
  5391.9  295.49  5455.6   298.5  5506.2  299.21  5520.5  300.47  5590.7  302.63
  5640.2  305.01  5662.2  304.99  5846.8  313.23  5853.3   312.8  5874.8   313.5
#Mann= 4 ,-1 , 0
  4365.6     .05       0  4771.3      .1       0  5000.1     .07       0
  5006.1      .1       0
Bank Sta=4982.8,5020.8
XS Rating Curve= 0 ,0
Exp/Cntr=0.3,0.1

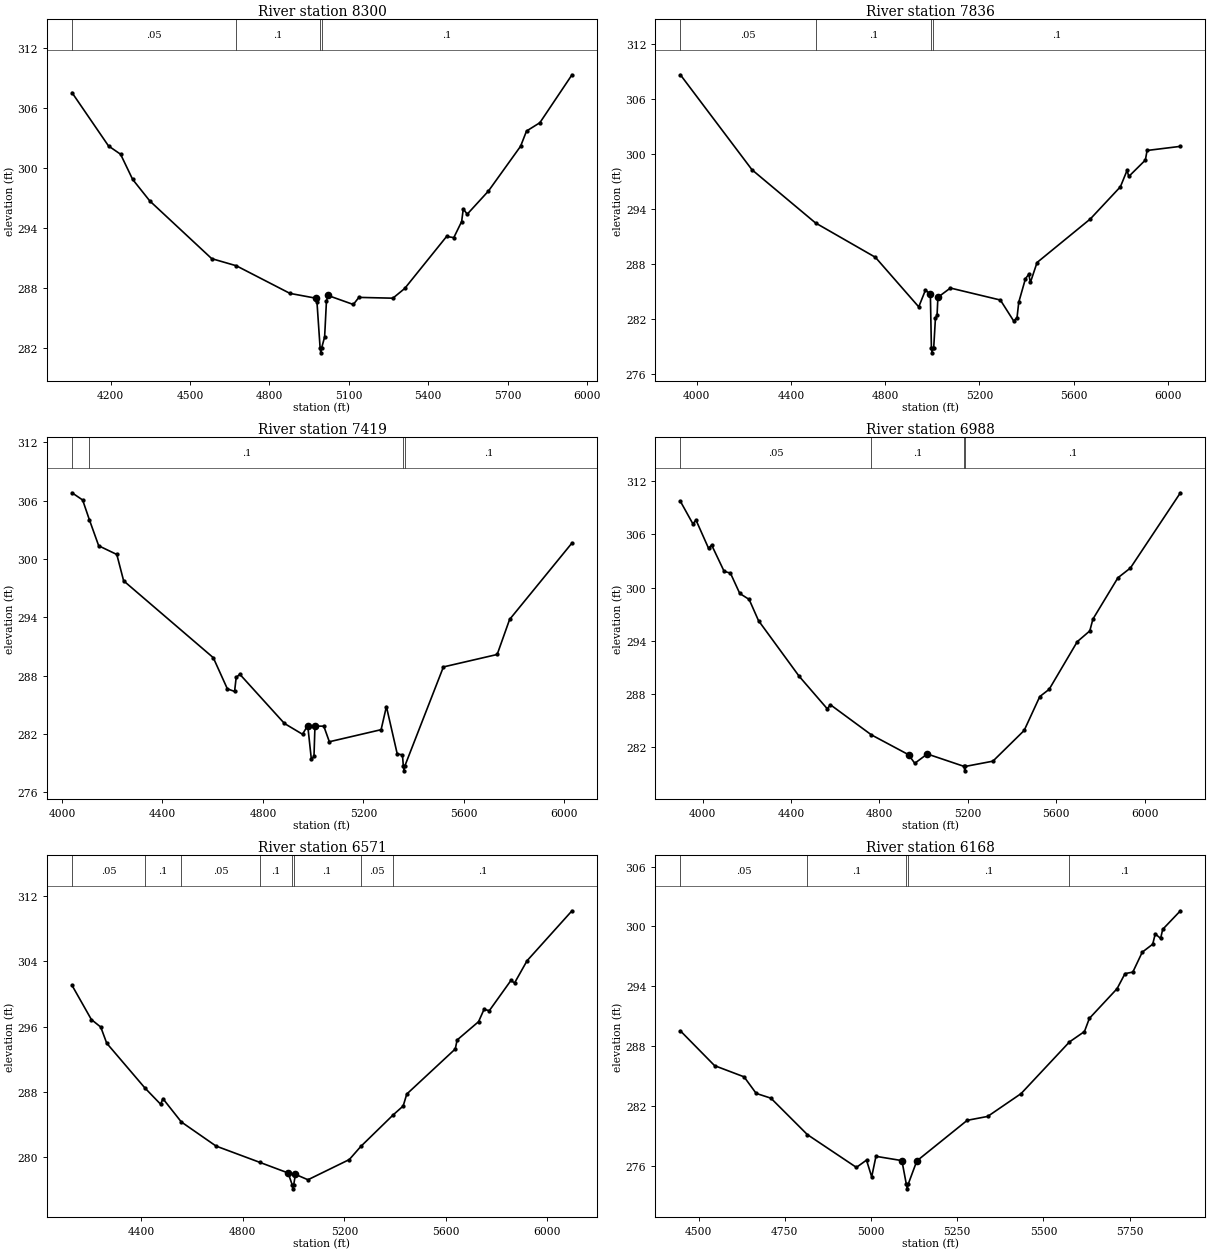
Type RM Length L Ch R = 1 ,8300    ,464,464,464
BEGIN DESCRIPTION:
UNT008 IN SPCR 17.0
END DESCRIPTION:
XS GIS Cut Line= 3
      2206437.71     13284746.83      2205987.72     13283946.85
       2205187.7     13283396.84
#Sta/Elev= 30
  4054.2   307.5  4192.2  302.17  4237.8  301.34  4283.3  298.83  4348.3  296.67
    4582  290.91  4674.8   290.2  4877.4  287.44  4975.1  286.96  4979.5  286.61
  4991.4     282  4994.1   281.5  4997.4     282  5008.5  283.09  5015.4  286.67
  5021.4  287.23  5116.9  286.33  5137.8  287.04  5266.3  286.96    5311  287.93
  5469.3  293.13  5496.4  293.01  5526.1  294.62  5532.2  295.88  5547.1  295.35
  5627.4  297.67  5748.7  302.14  5771.1  303.66  5821.5  304.49  5942.9  309.28
#Mann= 4 ,-1 , 0
  4054.2     .05       0  4674.8      .1       0  4991.4     .07       0
  4997.4      .1       0
Bank Sta=4975.1,5021.4
XS Rating Curve= 0 ,0
Exp/Cntr=0.3,0.1

Type RM Length L Ch R = 1 ,7836    ,417,417,417
BEGIN DESCRIPTION:
UNT008 IN SPCR 16.0
END DESCRIPTION:
XS GIS Cut Line= 3
       2207137.7     13284596.83      2206387.72     13283796.85
       2205687.7     13283046.83
#Sta/Elev= 30
  3930.5  308.68  4234.5   298.3  4504.2  292.49  4758.2  288.74  4942.3  283.32
  4970.6  285.15  4991.6  284.72    4996   278.8  4998.7   278.3    5002   278.8
  5005.8  278.86  5013.1  282.07    5020  282.41  5023.6  284.37  5076.6  285.38
  5288.7  284.07  5345.3  281.78  5359.5  282.16  5366.8  283.83  5395.2   286.4
  5409.3  286.89  5416.2  285.99  5444.5  288.17  5670.7  292.93  5798.2  296.44
  5826.5  298.23  5833.9  297.57  5904.2  299.36  5911.5  300.41    6053  300.86
#Mann= 4 ,-1 , 0
  3930.5     .05       0  4504.2      .1       0    4996     .07       0
    5002      .1       0
Bank Sta=4991.6,5023.6
XS Rating Curve= 0 ,0
Exp/Cntr=0.3,0.1

Type RM Length L Ch R = 1 ,7419    ,431,431,431
BEGIN DESCRIPTION:
UNT008 IN SPCR 15.0
END DESCRIPTION:
XS GIS Cut Line= 3
      2207337.71     13284346.85      2206737.72     13283596.85
      2206087.74     13282796.88
#Sta/Elev= 30
  4039.6   306.8    4082  306.06  4108.7  304.04    4146  301.35  4218.1  300.46
  4245.3  297.75  4602.3  289.85  4658.3  286.65  4687.1  286.38  4693.5  287.82
  4707.9  288.15  4885.6  283.09  4957.6  281.98  4978.4  282.88  4992.9  279.39
  5003.3   279.7  5007.2  282.82  5042.4  282.81  5064.5  281.21  5270.6  282.45
  5291.7  284.83  5334.8  279.96  5355.6  279.86  5359.1  278.72  5361.8  278.22
  5365.1  278.72  5518.7   288.9  5732.8  290.18  5782.3  293.78  6030.8  301.64
#Mann= 4 ,-1 , 0
  4039.6     .05       0  4108.7      .1       0  5359.1     .07       0
  5365.1      .1       0
Bank Sta=4978.4,5007.2
XS Rating Curve= 0 ,0
Exp/Cntr=0.3,0.1

Type RM Length L Ch R = 1 ,6988    ,417,417,417
BEGIN DESCRIPTION:
UNT008 IN SPCR 14.0
END DESCRIPTION:
XS GIS Cut Line= 3
      2207787.71     13284046.84      2206987.72     13283246.85
      2206187.73     13282446.87
#Sta/Elev= 30
  3899.2  309.74  3955.7   307.2  3969.9  307.62  4026.5  304.45  4040.6  304.81
  4097.2  301.84  4125.5  301.65  4167.9  299.35  4210.3  298.68  4252.7  296.29
  4436.6  290.02  4563.9  286.35    4578  286.81  4763.2  283.42  4931.6  281.18
  4959.8  280.21  5016.4  281.26  5183.1  279.86  5185.9  279.36  5189.1  279.86
  5313.4  280.45  5454.8  283.91  5525.5  287.73    5568  288.55  5695.2  293.92
  5751.8  295.13  5765.9  296.46  5879.1  301.12  5935.6  302.22  6161.9   310.7
#Mann= 4 ,-1 , 0
  3899.2     .05       0  4763.2      .1       0  5183.1     .07       0
  5189.1      .1       0
Bank Sta=4931.6,5016.4
XS Rating Curve= 0 ,0
Exp/Cntr=0.3,0.1

Type RM Length L Ch R = 1 ,6571    ,403,403,403
BEGIN DESCRIPTION:
UNT008 IN SPCR 13.0
END DESCRIPTION:
XS GIS Cut Line= 3
       2207987.7     13283246.85      2207187.72     13282896.85
       2206387.7     13282146.84
#Sta/Elev= 30
  4126.8  301.04  4203.2  296.85  4240.2  295.93  4263.6  293.96  4413.9  288.49
  4476.1  286.49    4485  287.18  4557.5  284.33  4694.4  281.38  4867.4  279.38
  4978.2  278.09  4994.3  276.65    4997  276.15  5000.3  276.65  5007.1  277.92
  5056.4  277.26  5219.3  279.73  5264.8  281.34  5391.7  285.18  5431.5  286.28
  5445.7  287.74  5636.7  293.25    5644  294.35  5728.5  296.59    5750  298.09
    5771  297.94    5856  301.63  5870.2  301.32  5919.5  304.04  6096.6  310.15
#Mann= 8 ,-1 , 0
  4126.8     .05       0  4413.9      .1       0  4557.5     .05       0
  4867.4      .1       0  4994.3     .07       0  5000.3      .1       0
  5264.8     .05       0  5391.7      .1       0
Bank Sta=4978.2,5007.1
XS Rating Curve= 0 ,0
Exp/Cntr=0.3,0.1

Type RM Length L Ch R = 1 ,6168    ,407,407,407
BEGIN DESCRIPTION:
UNT008 IN SPCR 12.0
END DESCRIPTION:
XS GIS Cut Line= 3
      2207837.72     13282946.86      2207437.72     13282596.85
      2206637.71     13282146.85
#Sta/Elev= 30
  4447.5  289.53  4546.7  286.04  4632.1  284.92  4667.2  283.26  4709.9  282.78
  4815.5  279.13  4957.7  275.84    4987  276.57    5002  274.89  5014.4  276.95
  5089.6  276.52  5102.2  274.19    5105  273.69  5108.2  274.19  5132.9  276.49
  5278.9  280.56  5338.2  280.95  5435.1  283.24  5575.3  288.42  5618.7  289.46
    5633  290.78  5713.3  293.76  5736.3  295.27  5758.9  295.42  5786.3  297.42
  5816.6  298.22  5823.9  299.25  5839.5   298.8  5845.6  299.71  5896.9  301.57
#Mann= 5 ,-1 , 0
  4447.5     .05       0  4815.5      .1       0  5102.2     .07       0
  5108.2      .1       0  5575.3      .1       0
Bank Sta=5089.6,5132.9
XS Rating Curve= 0 ,0
Exp/Cntr=0.3,0.1

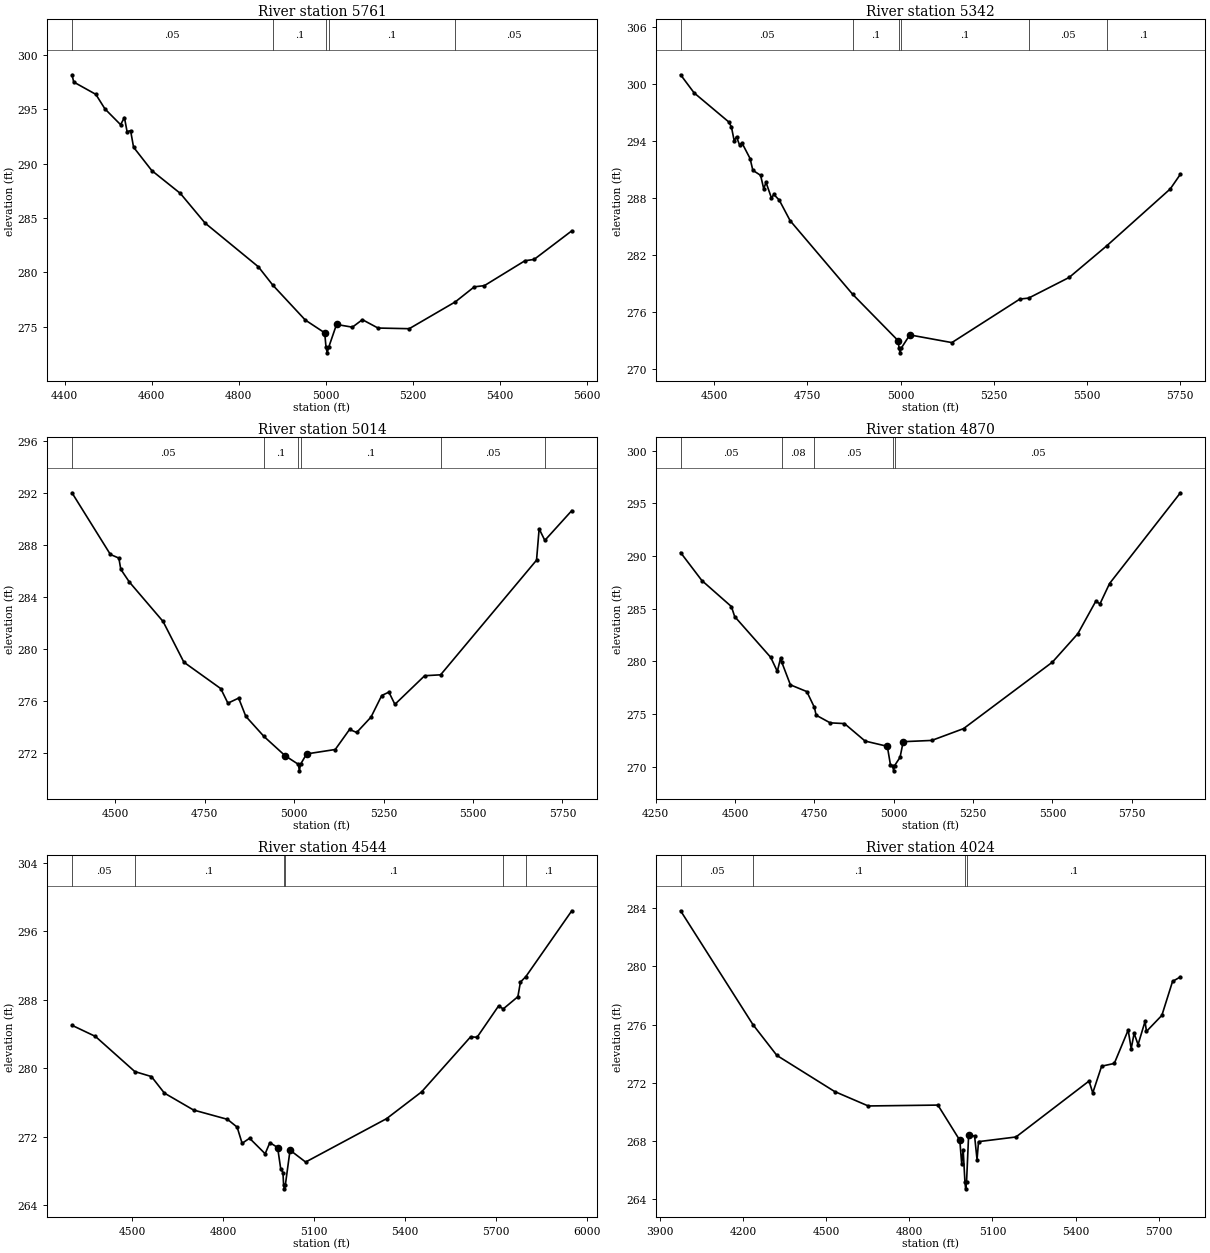
Type RM Length L Ch R = 1 ,5761    ,419,419,419
BEGIN DESCRIPTION:
UNT008 IN SPCR 11.0
END DESCRIPTION:
XS GIS Cut Line= 2
      2208168.75     13282622.32       2207222.2     13281972.22
#Sta/Elev= 30
  4416.8  298.16  4420.9  297.49  4471.6  296.36  4492.6  295.02  4528.5  293.57
  4537.3  294.23  4543.4  292.93  4551.5  293.02  4558.3   291.5  4600.2  289.35
  4665.8  287.25  4722.7  284.52  4845.1   280.5  4878.1  278.82  4952.7  275.61
  4997.4  274.43  5000.5  273.09  5003.2  272.59  5006.5  273.09  5024.6   275.2
    5061  274.95    5084  275.64  5119.9  274.87  5191.6  274.81  5297.6  277.28
  5341.1  278.66  5364.3  278.77  5457.5  281.06  5478.5  281.18  5565.1  283.81
#Mann= 5 ,-1 , 0
  4416.8     .05       0  4878.1      .1       0  5000.5     .07       0
  5006.5      .1       0  5297.6     .05       0
Bank Sta=4997.4,5024.6
XS Rating Curve= 0 ,0
Exp/Cntr=0.3,0.1

Type RM Length L Ch R = 1 ,5342    ,328,328,328
BEGIN DESCRIPTION:
Mapping XS e5acdcae
END DESCRIPTION:
XS GIS Cut Line= 3
      2208386.75     13282218.72      2208082.93     13281990.85
      2207161.62     13281719.88
#Sta/Elev= 30
  4410.2  300.99  4446.5  299.08  4539.3  296.02  4546.5  295.49  4553.9  294.03
  4560.1  294.46  4568.4  293.57  4574.7  293.81  4596.5  292.16  4603.9  290.92
  4624.7  290.39    4633  288.98  4639.3  289.64  4653.9  287.99  4660.1  288.38
  4674.7  287.78  4703.9  285.61    4872  277.83  4993.5  272.96  4995.9  272.18
  4998.6  271.68  5001.9  272.18  5024.7  273.57  5137.5  272.76  5319.9  277.35
  5343.3  277.45  5452.1  279.63  5552.4  282.95  5723.1  288.96  5750.3  290.51
#Mann= 6 ,-1 , 0
  4410.2     .05       0    4872      .1       0  4995.9     .07       0
  5001.9      .1       0  5343.3     .05       0  5552.4      .1       0
Bank Sta=4993.5,5024.7
XS Rating Curve= 0 ,0
Exp/Cntr=0.3,0.1

Type RM Length L Ch R = 1 ,5014    ,144,144,144
BEGIN DESCRIPTION:
Mapping XS 3b7de1c4
END DESCRIPTION:
XS GIS Cut Line= 3
      2208383.98      13281982.5      2208236.42     13281635.32
       2207216.5     13281609.28
#Sta/Elev= 30
  4378.8     292  4486.2  287.26  4509.9  286.98  4515.3  286.12    4539  285.15
  4633.5  282.11  4691.7  278.98  4794.8  276.95  4814.8  275.83  4844.8  276.22
  4864.8  274.82  4915.7  273.27  4974.8  271.79  5011.8  271.13  5014.6  270.63
  5017.8  271.13  5034.8  271.93  5114.9  272.27  5154.9  273.81  5174.9  273.58
  5214.9  274.76  5244.9  276.42  5264.9  276.68  5281.7  275.74  5364.9  277.94
  5409.5  278.01  5677.7  286.82    5685  289.23  5700.9  288.34  5776.3  290.63
#Mann= 6 ,-1 , 0
  4378.8     .05       0  4915.7      .1       0  5011.8     .07       0
  5017.8      .1       0  5409.5     .05       0  5700.9     .08       0
Bank Sta=4974.8,5034.8
XS Rating Curve= 0 ,0
Exp/Cntr=0.3,0.1

Type RM Length L Ch R = 1 ,4870    ,326,326,326
BEGIN DESCRIPTION:
Mapping XS c2119686
END DESCRIPTION:
XS GIS Cut Line= 3
      2208397.02     13281921.79      2208288.51     13281505.11
      2207144.61     13281461.78
#Sta/Elev= 30
  4328.2  290.33  4395.3  287.67  4488.3   285.2  4498.6  284.25  4612.3  280.37
    4633  279.04  4643.3   280.3  4647.1  279.91  4674.3  277.76    4726  277.12
    4750  275.61  4755.3  274.88  4799.6  274.15  4844.7  274.08  4909.7  272.42
  4979.7  271.92  4989.7  270.14  4996.7  270.09  4999.5  269.59  5002.7  270.09
  5019.8  270.87  5029.8  272.36  5119.8  272.48  5219.9   273.6  5500.1  279.92
  5580.2  282.62  5636.3  285.68  5650.2  285.47  5680.2  287.39  5903.5  296.01
#Mann= 5 ,-1 , 0
  4328.2     .05       0  4647.1     .08       0    4750     .05       0
  4996.7    .035       0  5002.7     .05       0
Bank Sta=4979.7,5029.8
XS Rating Curve= 0 ,0
Exp/Cntr=0.3,0.1

Type RM Length L Ch R = 1 ,4544    ,520,520,520
BEGIN DESCRIPTION:
Mapping XS 187a913f
END DESCRIPTION:
XS GIS Cut Line= 3
       2208690.6     13281513.46      2208473.56     13281274.71
      2207182.73     13280981.83
#Sta/Elev= 30
  4302.5  285.02  4379.7  283.72  4509.6  279.61  4564.2  279.03  4606.8   277.1
  4702.9  275.12  4814.7  274.03  4846.5  273.12  4862.9  271.23  4887.5  271.82
  4938.8  270.01  4954.3  271.31  4979.8  270.74    4990  268.27  4997.4  267.81
  4999.5  266.41  5002.3  265.91  5005.5  266.41  5020.8  270.43  5072.1  269.04
  5338.7  274.11  5454.1  277.24  5615.5  283.67  5636.8  283.62  5707.8  287.29
  5722.9  286.93  5771.2  288.36  5779.6  290.07  5797.3   290.7  5948.8   298.4
#Mann= 6 ,-1 , 0
  4302.5     .05       0  4509.6      .1       0  4999.5     .07       0
  5005.5      .1       0  5722.9     .05       0  5797.3      .1       0
Bank Sta=4979.8,5020.8
XS Rating Curve= 0 ,0
Exp/Cntr=0.3,0.1

Type RM Length L Ch R = 1 ,4024    ,543,543,543
BEGIN DESCRIPTION:
UNT008 IN SPCR 8.0
END DESCRIPTION:
XS GIS Cut Line= 3
      2208766.53     13281372.36      2208571.21     13280851.53
      2207401.04     13280418.13
#Sta/Elev= 30
  3974.5  283.81  4235.8  275.99    4322  273.88  4530.6   271.4  4651.8  270.41
  4903.2  270.47  4982.4  268.05  4989.1  266.43  4994.4  267.42  5000.7  265.22
  5003.4  264.72  5006.7  265.22  5014.2  268.44  5035.7  268.34  5044.5  266.73
  5049.9  267.96    5185  268.28  5448.7  272.12  5462.2  271.31  5494.2  273.14
  5539.9  273.33    5590  275.62  5600.9  274.34  5611.5   275.4  5625.7  274.62
  5650.8  276.21  5656.1  275.53  5711.6  276.63  5750.2  278.96  5778.6  279.27
#Mann= 4 ,-1 , 0
  3974.5     .05       0  4235.8      .1       0  5000.7     .07       0
  5006.7      .1       0
Bank Sta=4982.4,5014.2
XS Rating Curve= 0 ,0
Exp/Cntr=0.3,0.1

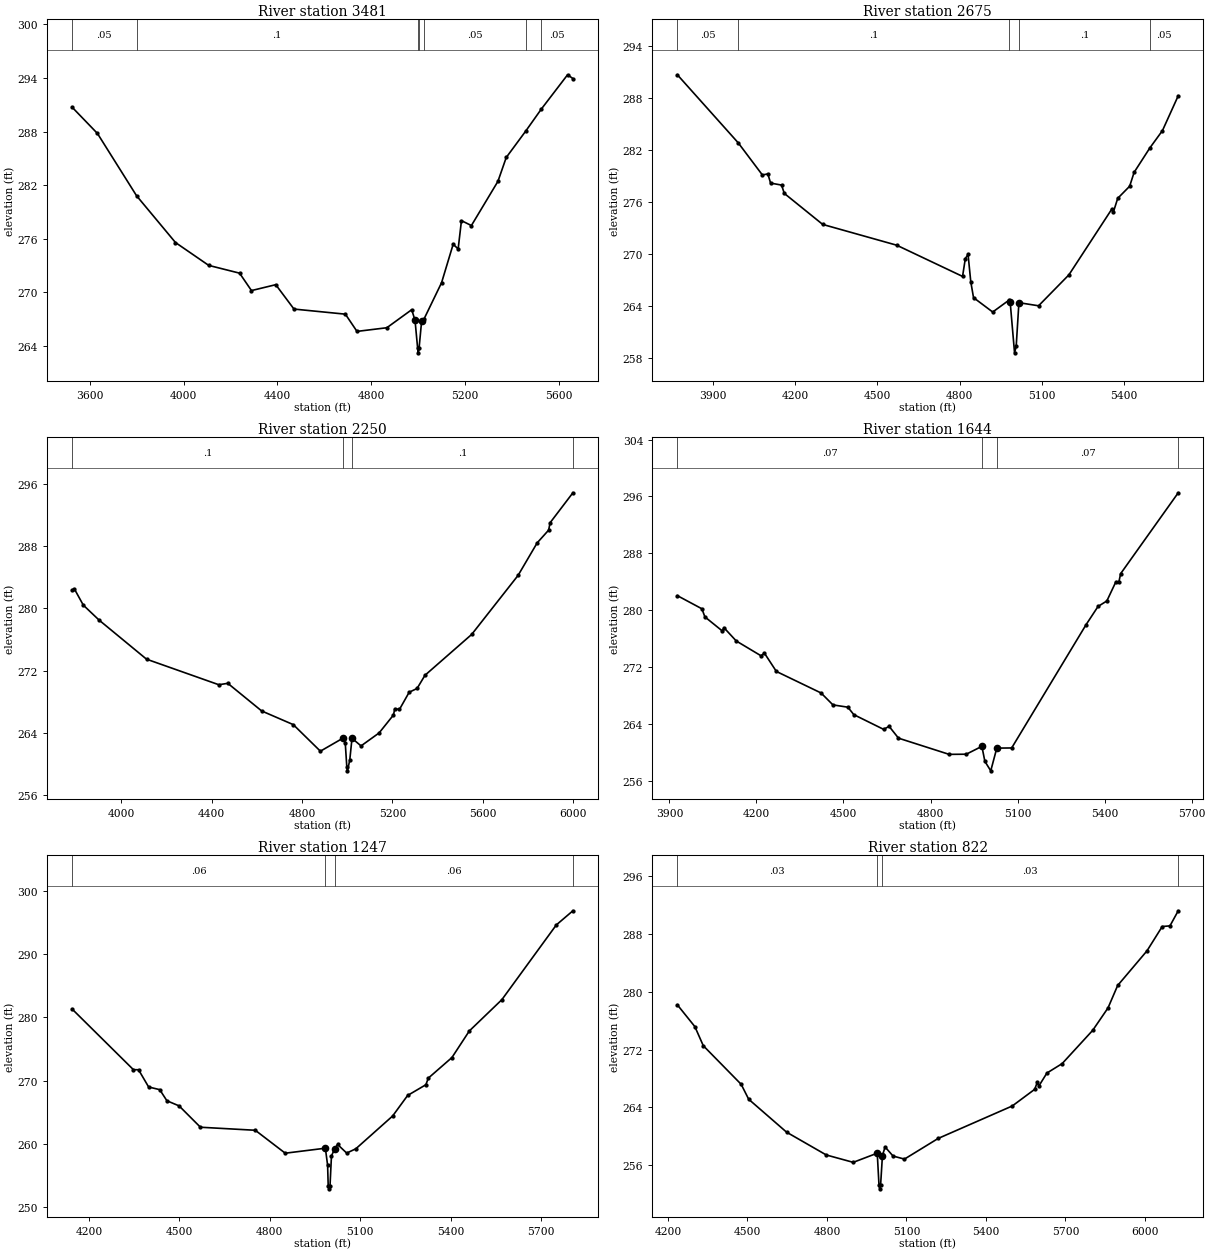
Type RM Length L Ch R = 1 ,3481    ,806,806,806
BEGIN DESCRIPTION:
UNT008 IN SPCR 7.0
END DESCRIPTION:
XS GIS Cut Line= 3
      2208929.28     13281502.53      2208799.08     13280688.77
       2207876.8     13279755.64
#Sta/Elev= 30
  3523.9  290.74  3632.3  287.79  3799.3  280.81  3965.1  275.58  4106.9  273.02
  4238.5  272.15  4289.2   270.2  4392.8  270.86  4470.5  268.13  4689.7  267.56
  4739.2  265.63  4866.5  266.04  4972.6  268.06  4986.7  266.87  4997.9  263.73
  5000.6  263.23  5003.9  263.73    5015  266.83  5025.1  267.02  5099.9  271.08
  5149.4  275.39  5170.6  274.86  5184.7  278.03  5227.1  277.48  5340.3  282.43
  5375.7   285.1  5459.2  288.07  5525.6  290.53  5637.3  294.36    5660  293.94
#Mann= 7 ,-1 , 0
  3523.9     .05       0  3799.3      .1       0  4997.9     .07       0
  5003.9      .1       0  5025.1     .05       0  5459.2     .08       0
  5525.6     .05       0
Bank Sta=4986.7,5015
XS Rating Curve= 0 ,0
Exp/Cntr=0.3,0.1

Type RM Length L Ch R = 1 ,2675    ,425,425,425
BEGIN DESCRIPTION:
UNT008 IN SPCR 6.0
END DESCRIPTION:
XS GIS Cut Line= 3
      2209137.72     13281446.81      2209137.72     13280246.85
       2208837.7     13279696.81
#Sta/Elev= 30
  3770.8  290.63  3992.9  282.77  4080.8  279.07  4100.8  279.19  4110.8  278.13
  4150.8   277.9  4160.8  276.94  4300.8  273.36  4570.8  270.96  4810.8  267.36
  4820.8   269.4  4830.8  269.92  4840.8  266.74  4850.8  264.91  4920.8  263.25
  4978.8  264.59  4984.5  264.37  5000.4  258.54  5006.4  259.28  5016.3  264.33
    5088  263.97  5198.6  267.54  5354.7  275.11  5360.4  274.75  5376.6  276.37
  5420.2  277.77  5436.4  279.37  5493.4  282.17  5539.8  284.19  5597.3  288.21
#Mann= 5 ,-1 , 0
  3770.8     .05       0  3992.9      .1       0  4978.8     .07       0
  5016.3      .1       0  5493.4     .05       0
Bank Sta=4984.5,5016.3
XS Rating Curve= 0 ,0
Exp/Cntr=0.3,0.1

Type RM Length L Ch R = 1 ,2250    ,606,606,606
BEGIN DESCRIPTION:
UNT008 IN SPCR 5.0
END DESCRIPTION:
XS GIS Cut Line= 3
      2209547.62     13281376.85      2209538.94     13279953.26
      2209026.78     13279345.62
#Sta/Elev= 30
  3781.3  282.31  3791.3  282.53  3831.3  280.42  3901.3  278.49  4111.3  273.46
  4431.3  270.17  4471.3  270.35  4621.3  266.79  4761.3  265.03  4881.3  261.61
  4981.3  263.29  4991.3  262.72  4998.3  259.58  5001.1  259.08  5011.3  260.45
  5021.3  263.27  5061.3  262.29  5141.3  263.96  5204.9  266.27  5210.7  267.07
  5231.5  266.99  5274.4   269.2  5309.5  269.69  5344.6  271.39  5551.4  276.65
  5756.8  284.25  5841.4  288.44  5892.1  290.08  5898.6  291.03  5999.6  294.89
#Mann= 4 ,-1 , 0
  3781.3      .1       0  4981.3     .07       0  5021.3      .1       0
  5999.6      .1       0
Bank Sta=4981.3,5021.3
XS Rating Curve= 0 ,0
Exp/Cntr=0.3,0.1

Type RM Length L Ch R = 1 ,1644    ,397,397,397
BEGIN DESCRIPTION:
UNT008 IN SPCR 4.0
END DESCRIPTION:
XS GIS Cut Line= 2
      2209876.71     13281319.27      2210267.39     13279637.66
#Sta/Elev= 30
  3927.4  282.04    4012  280.19  4022.3  279.05  4082.6  277.06  4087.8  277.54
  4130.4  275.66  4215.6  273.58  4227.6  273.94  4268.7  271.37  4422.7  268.34
  4463.7  266.66  4515.1  266.34  4535.6  265.29  4638.3  263.22  4657.3  263.64
  4689.6  261.98  4864.1   259.7  4923.3  259.72    4977  260.83  4987.3  258.72
  5007.6  257.38  5028.4  260.58  5079.7   260.6  5336.4  277.97  5377.4  280.52
  5407.7  281.29    5439     284  5449.3     284  5455.4  285.14  5653.8  296.52
#Mann= 4 ,-1 , 0
  3927.4     .07       0    4977     .05       0  5028.4     .07       0
  5653.8     .05       0
Bank Sta=4977,5028.4
XS Rating Curve= 0 ,0
Exp/Cntr=0.3,0.1

Type RM Length L Ch R = 1 ,1247    ,425,425,425
BEGIN DESCRIPTION:
UNT008 IN SPCR 3.0
END DESCRIPTION:
XS GIS Cut Line= 3
      2210360.81     13281268.33      2210530.67     13280096.31
      2210416.02     13279633.47
#Sta/Elev= 30
  4143.9  281.35  4347.5  271.74  4364.5  271.73    4398     269  4434.7  268.58
  4458.6  266.82    4499  266.01  4569.8  262.63  4751.7  262.15    4851  258.52
  4983.8  259.31  4984.1  259.31  4991.5  256.62  4993.5  253.38  4996.3  252.88
  4999.5  253.38  5004.3  258.08  5014.4  259.17  5024.5  259.91  5054.8  258.54
  5085.1  259.22  5207.2  264.41  5256.9  267.66  5317.5  269.36  5325.4   270.4
  5403.8  273.66  5461.5  277.87  5569.4  282.82    5750  294.65    5805  296.89
#Mann= 4 ,-1 , 0
  4143.9     .06       0  4984.1     .04       0  5014.4     .06       0
    5805     .05       0
Bank Sta=4983.8,5014.4
XS Rating Curve= 0 ,0
Exp/Cntr=0.3,0.1

Type RM Length L Ch R = 1 ,822     ,540,540,540
BEGIN DESCRIPTION:
UNT008 IN SPCR 2.0
END DESCRIPTION:
XS GIS Cut Line= 5
      2210619.84     13281276.84      2210861.89     13280754.52
       2210908.6     13280130.28      2210624.09     13279680.16
      2210547.64     13279544.25
#Sta/Elev= 30
  4235.7   278.2  4301.8  275.18  4333.5  272.54  4476.5  267.19  4504.9  265.12
  4647.9  260.56  4797.8   257.4  4899.3  256.38    4990  257.65  4996.6  253.21
  4999.3  252.71  5002.6  253.21  5009.6  257.32  5019.6  258.51  5049.7  257.25
  5092.7  256.83  5219.8  259.69  5499.6  264.19  5584.3   266.5  5593.7  267.46
  5599.6  266.94  5630.2  268.75  5687.8  270.06  5803.1  274.67  5860.8  277.77
  5897.2  280.88  6007.9  285.68  6065.4  289.05  6094.6  289.14  6125.8  291.23
#Mann= 4 ,-1 , 0
  4235.7     .03       0    4990    .025       0  5009.6     .03       0
  6125.8      .1       0
Bank Sta=4990,5009.6
XS Rating Curve= 0 ,0
Exp/Cntr=0.3,0.1

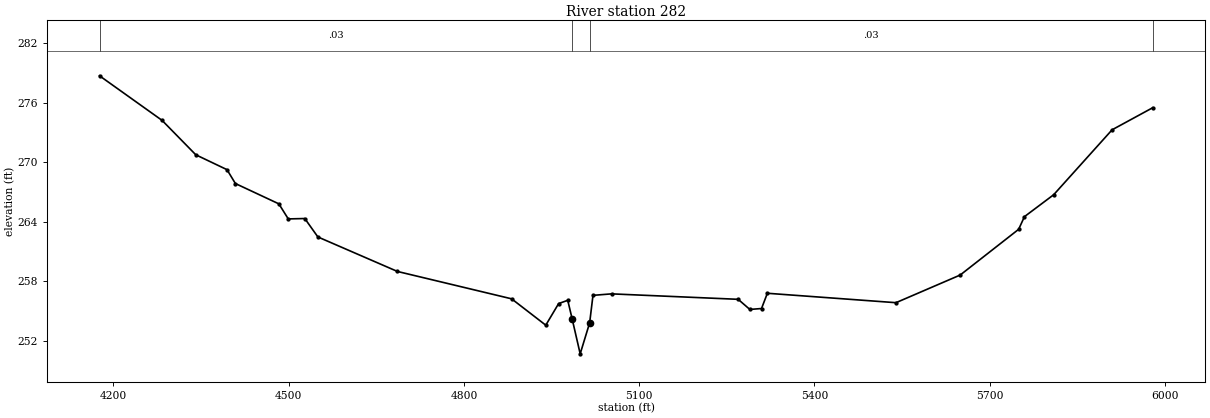
Type RM Length L Ch R = 1 ,282     ,0,0,0
BEGIN DESCRIPTION:
UNT008 IN SPCR 1.0
END DESCRIPTION:
XS GIS Cut Line= 4
      2210781.23     13281332.03      2211150.65     13281153.69
      2211439.41     13280644.11       2211456.4     13279837.31
#Sta/Elev= 30
  4176.3  278.73  4283.4  274.23  4341.1  270.76  4394.5  269.26  4408.9  267.86
  4483.3  265.81  4499.4  264.29  4527.7  264.33  4550.1  262.47  4686.3  258.99
  4881.7  256.23  4940.2  253.57  4962.2  255.75  4977.8  256.08  4985.2  254.24
  4999.1  250.68  5015.3  253.81    5021  256.58  5052.8  256.73  5269.5  256.18
  5289.5  255.16  5309.5  255.25  5319.5  256.79  5539.6  255.84  5649.6  258.63
  5749.6  263.24  5759.6  264.52  5809.6  266.73  5909.6  273.28  5979.2  275.51
#Mann= 4 ,-1 , 0
  4176.3     .03       0  4985.2    .025       0  5015.3     .03       0
  5979.2     .08       0
Bank Sta=4985.2,5015.3
XS Rating Curve= 0 ,0
Exp/Cntr=0.3,0.1

Chan Stop Cuts=-1
Use User Specified Reach Order=0
Composite Channel Slope=5