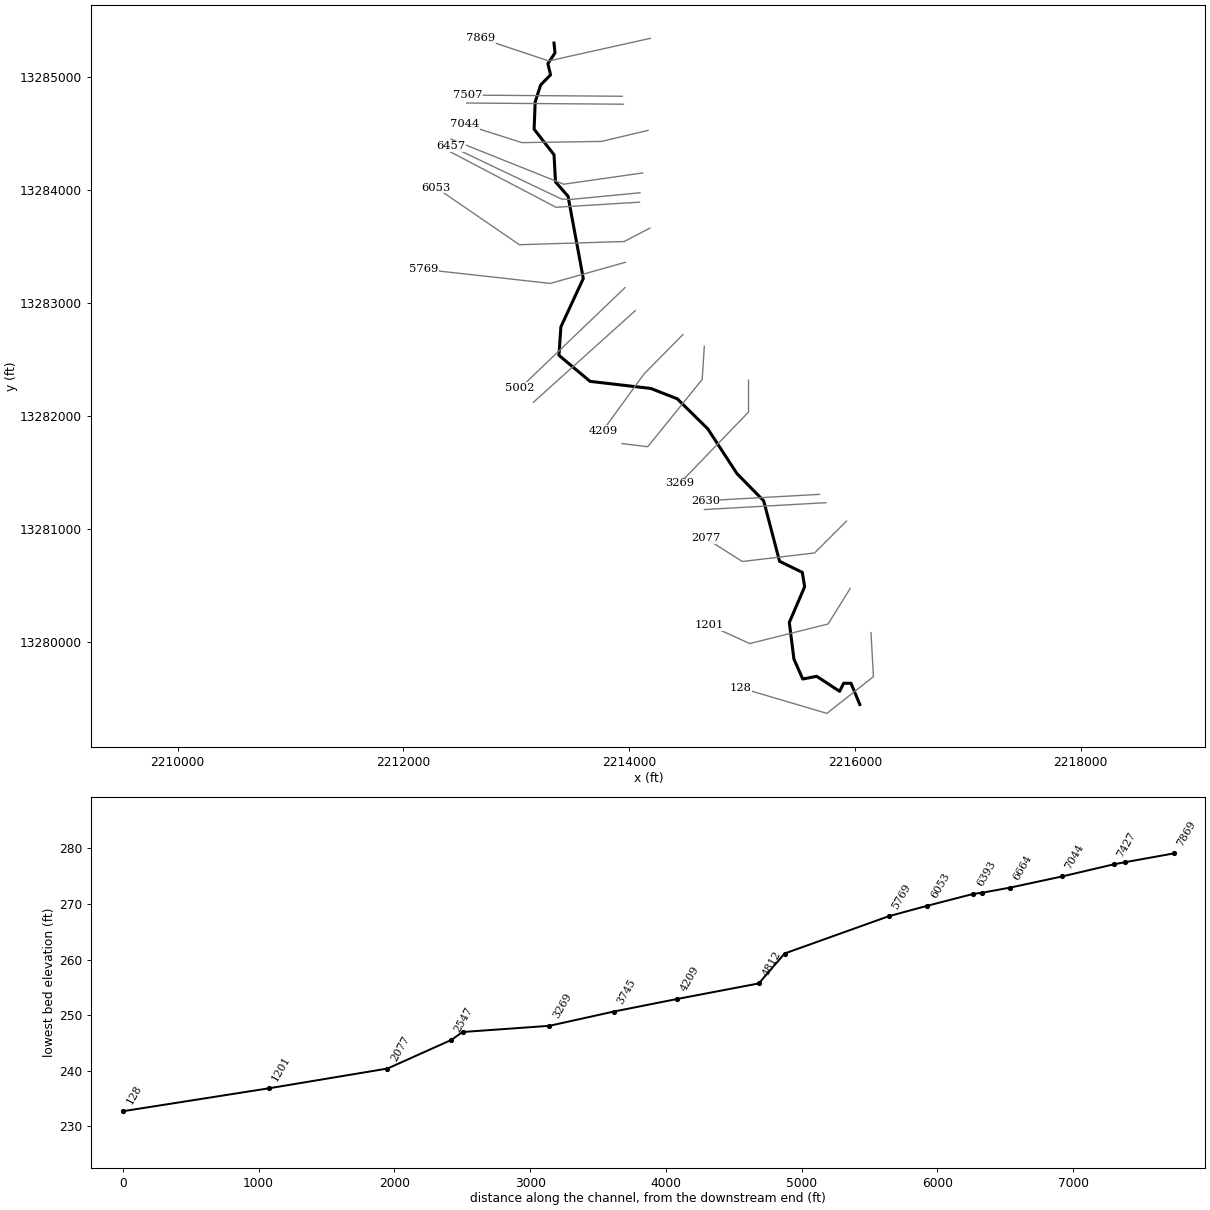
--- UNT010 IN SPCR.prj (project) ---

Proj Title=UNT010 IN SPCR Base Level Engineering
Current Plan=p01
Default Exp/Contr=0.3,0.1
English Units
Geom File=g01
Flow File=f01
Plan File=p01
BEGIN DESCRIPTION:
UNT010 IN SPCR
END DESCRIPTION:

--- UNT010 IN SPCR.p01 (plan) ---

Plan Title=Multiple Run
Short Identifier=Multiple
Geom File=g01
Flow File=f01
Subcritical Flow
K Sum by GR= 0
Std Step Tol= 0.01
Critical Tol= 0.01
Num of Std Step Trials= 20
Max Error Tol= 0.3
Flow Tol Ratio= 0.001
Split Flow NTrial= 30
Split Flow Tol= 0.02
Split Flow Ratio= 0.02
Log Output Level= 0
Friction Slope Method= 1
Unsteady Friction Slope Method= 2
Unsteady Bridges Friction Slope Method= 1
Parabolic Critical Depth
Global Vel Dist=  1 , 1 , 1
Global Log Level= 0
CheckData=True
Encroach Param= -1, 0, 0, 0
BEGIN DESCRIPTION:
Multiple Run
END DESCRIPTION:

--- UNT010 IN SPCR.f01 (steady flow) ---

Flow Title=Multiple
Number of Profiles=7
Profile Names=10-year,25-year,50-year,1pct_min,100-year,1pct_plu,500-year
River Rch & RM= UNT010 IN SPCR,Reach-1,7869
     269     376     466     424     573     775     882
Boundary for River Rch & Prof#=UNT010 IN SPCR,Reach-1,1
Up Type=0
Dn Type=3
Dn Slope=0.005
Boundary for River Rch & Prof#=UNT010 IN SPCR,Reach-1,2
Up Type=0
Dn Type=3
Dn Slope=0.005
Boundary for River Rch & Prof#=UNT010 IN SPCR,Reach-1,3
Up Type=0
Dn Type=3
Dn Slope=0.005
Boundary for River Rch & Prof#=UNT010 IN SPCR,Reach-1,4
Up Type=0
Dn Type=3
Dn Slope=0.005
Boundary for River Rch & Prof#=UNT010 IN SPCR,Reach-1,5
Up Type=0
Dn Type=3
Dn Slope=0.005
Boundary for River Rch & Prof#=UNT010 IN SPCR,Reach-1,6
Up Type=0
Dn Type=3
Dn Slope=0.005
Boundary for River Rch & Prof#=UNT010 IN SPCR,Reach-1,7
Up Type=0
Dn Type=3
Dn Slope=0.005

--- UNT010 IN SPCR.g01 (geometry) ---

Geom Title=Existing Conditions

River Reach=UNT010 IN SPCR,Reach-1
Reach XY= 30
      2213334.26     13285305.29      2213343.13     13285217.78
      2213280.17     13285122.30      2213304.05     13285023.68
      2213215.68     13284933.52      2213167.72     13284783.75
      2213158.06     13284542.10      2213334.46     13284315.52
      2213347.70     13284075.15      2213458.81     13283947.55
      2213593.79     13283219.25      2213395.35     13282790.60
      2213378.08     13282538.39      2213653.77     13282307.84
      2214192.11     13282244.97      2214426.33     13282153.48
      2214696.61     13281887.28      2214955.42     13281490.46
      2215191.97     13281249.50      2215332.52     13280713.92
      2215534.28     13280615.58      2215554.95     13280488.13
      2215419.03     13280171.92      2215459.83     13279847.93
      2215538.00     13279670.89      2215661.56     13279694.87
      2215864.95     13279561.75      2215900.43     13279633.22
      2215965.48     13279633.39      2216043.75     13279444.81

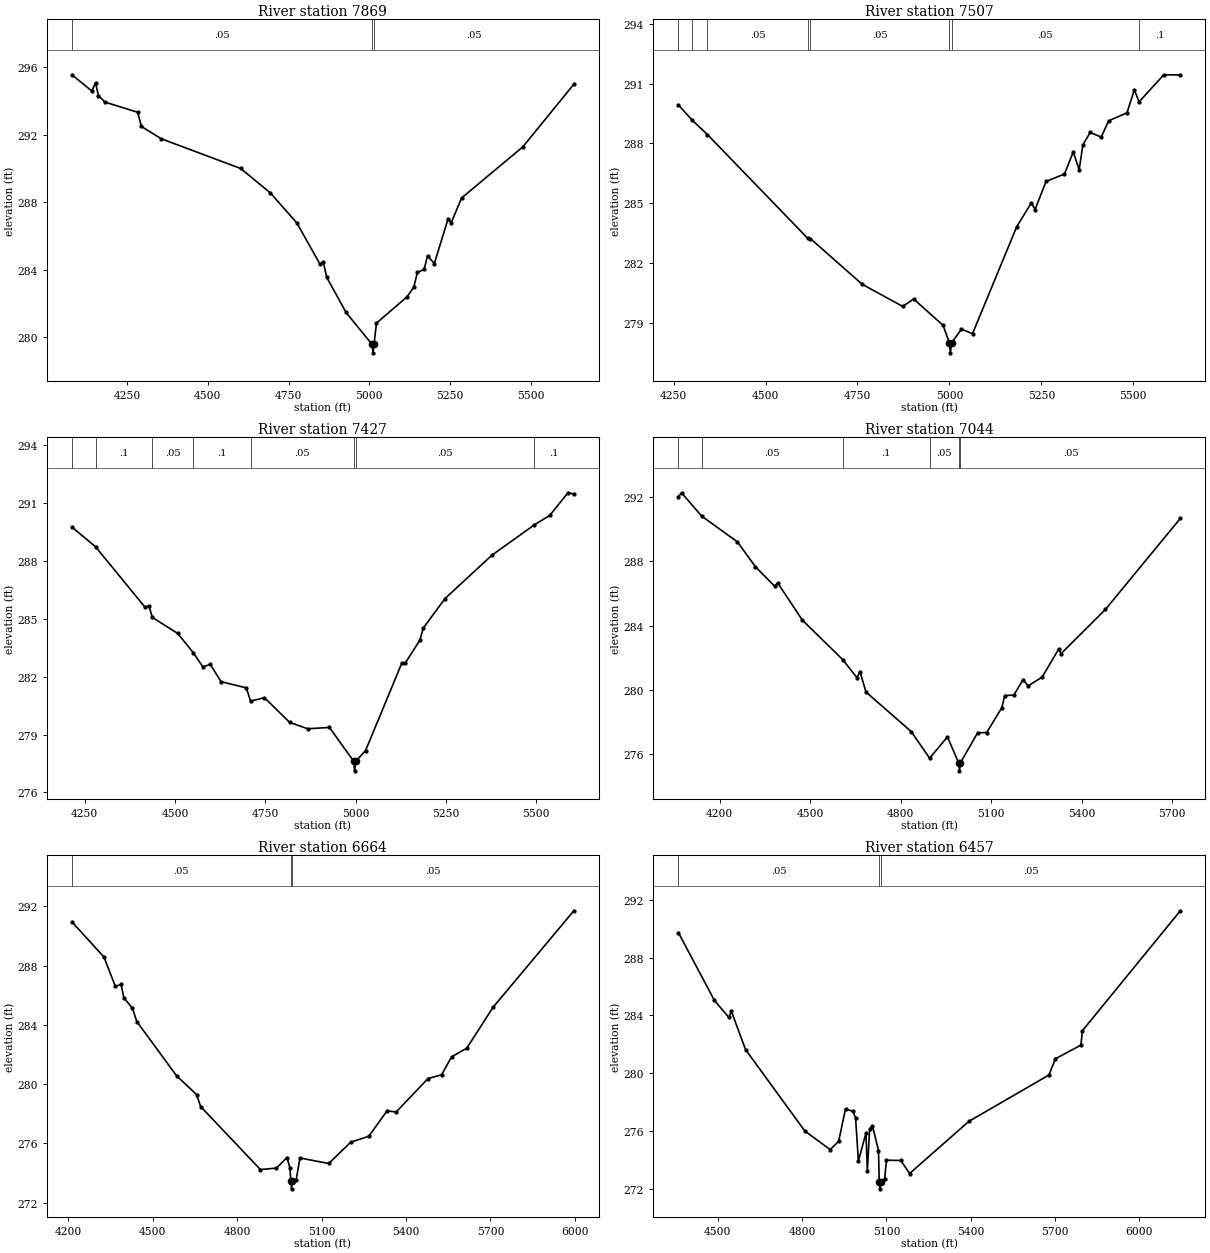
Type RM Length L Ch R = 1,7869,362,362,362
BEGIN DESCRIPTION:
UNT010 IN SPCR 15.0
END DESCRIPTION:
XS GIS Cut Line= 3
      2214187.74     13285346.86      2213287.72     13285146.85
      2212687.75     13285346.84
#Sta/Elev= 30
  4079.1  295.55  4140.6  294.59  4152.1  295.08  4161.1  294.32  4181.6  293.93
  4282.7  293.33  4294.2  292.49  4355.7  291.76  4601.6  290.00  4693.8  288.55
  4775.7  286.77  4847.4  284.33  4857.7  284.46  4867.9  283.56  4928.1  281.47
  5008.6  279.58  5011.4  279.08  5014.6  279.58  5022.2  280.84  5117.0  282.40
  5138.1  282.98  5148.7  283.84  5169.7  284.02  5180.3  284.82  5201.4  284.37
  5243.5  286.99  5254.1  286.80  5285.7  288.25  5475.4  291.28  5633.5  294.99
#Mann=3,-1,0
  4079.1    0.05       0  5008.6    0.03       0  5014.6    0.05       0
Bank Sta=5008.6,5014.6
Exp/Cntr=0.3,0.1

Type RM Length L Ch R = 1,7507,80,80,80
BEGIN DESCRIPTION:
Mapping XS 2917bb4a
END DESCRIPTION:
XS GIS Cut Line= 2
      2213937.41     13284833.67      2212572.75     13284844.09
#Sta/Elev= 30
  4263.1  289.93  4301.1  289.15  4342.0  288.44  4614.4  283.24  4622.1  283.22
  4762.8  280.93  4872.8  279.82  4902.8  280.19  4982.8  278.87  4999.8  277.99
  5002.6  277.49  5005.8  277.99  5032.8  278.68  5062.8  278.45  5182.8  283.81
  5222.8  285.02  5232.8  284.68  5262.8  286.09  5312.8  286.46  5336.6  287.57
  5352.8  286.68  5362.8  287.92  5382.8  288.55  5412.8  288.31  5432.8  289.13
  5482.8  289.53  5502.8  290.69  5515.6  290.08  5582.8  291.44  5627.8  291.43
#Mann=8,-1,0
  4263.1    0.05       0  4301.1     0.1       0  4342.0    0.05       0
  4614.4     0.1       0  4622.1    0.05       0  4999.8    0.03       0
  5005.8    0.05       0  5515.6     0.1       0
Bank Sta=4999.8,5005.8
Exp/Cntr=0.3,0.1

Type RM Length L Ch R = 1,7427,383,383,383
BEGIN DESCRIPTION:
UNT010 IN SPCR 14.0
END DESCRIPTION:
XS GIS Cut Line= 2
      2213950.39     13284763.36      2212561.23     13284773.76
#Sta/Elev= 30
  4214.8  289.75  4280.2  288.73  4417.5  285.59  4427.5  285.68  4437.5  285.07
  4507.5  284.24  4550.8  283.24  4577.5  282.50  4597.5  282.64  4627.5  281.74
  4697.5  281.42  4709.2  280.73  4747.5  280.91  4817.5  279.63  4867.5  279.30
  4927.5  279.37  4994.5  277.62  4997.2  277.12  5000.5  277.62  5027.5  278.17
  5127.5  282.69  5137.5  282.71  5177.5  283.88  5187.5  284.53  5247.5  286.05
  5377.5  288.30  5494.8  289.87  5537.5  290.36  5587.5  291.53  5604.0  291.47
#Mann=8,-1,0
  4214.8    0.05       0  4280.2     0.1       0  4437.5    0.05       0
  4550.8     0.1       0  4709.2    0.05       0  4994.5    0.03       0
  5000.5    0.05       0  5494.8     0.1       0
Bank Sta=4994.5,5000.5
Exp/Cntr=0.3,0.1

Type RM Length L Ch R = 1,7044,380,380,380
BEGIN DESCRIPTION:
UNT010 IN SPCR 13.0
END DESCRIPTION:
XS GIS Cut Line= 4
      2214167.77     13284531.34      2213755.48     13284433.69
      2213050.18     13284422.84      2212541.44     13284585.21
#Sta/Elev= 30
  4063.4  292.04  4073.7  292.29  4140.6  290.83  4258.7  289.23  4318.4  287.68
  4382.0  286.46  4392.3  286.66  4474.5  284.33  4607.5  281.88  4654.9  280.75
  4664.9  281.13  4684.9  279.85  4834.9  277.38  4895.8  275.72  4954.9  277.05
  4991.9  275.43  4994.7  274.93  4997.9  275.43  5054.9  277.31  5084.9  277.32
  5134.9  278.87  5144.9  279.63  5174.9  279.66  5205.6  280.63  5221.7  280.23
  5268.5  280.78  5323.5  282.53  5331.5  282.25  5478.5  285.01  5726.5  290.69
#Mann=6,-1,0
  4063.4     0.1       0  4140.6    0.05       0  4607.5     0.1       0
  4895.8    0.05       0  4991.9    0.03       0  4997.9    0.05       0
Bank Sta=4991.9,4997.9
Exp/Cntr=0.3,0.1

Type RM Length L Ch R = 1,6664,207,207,207
BEGIN DESCRIPTION:
UNT010 IN SPCR 12.0
END DESCRIPTION:
XS GIS Cut Line= 3
      2214120.35     13284154.49      2213420.36     13284054.49
      2212421.50     13284454.04
#Sta/Elev= 30
  4213.4  290.94  4327.2  288.57  4367.6  286.59  4387.8  286.72  4397.9  285.82
  4428.2  285.12  4443.8  284.22  4585.2  280.56  4655.9  279.30  4670.6  278.49
  4882.8  274.24  4939.9  274.34  4977.2  275.05  4988.0  274.34  4990.8  273.44
  4993.5  272.94  4996.8  273.44  5009.5  273.51  5023.4  275.02  5125.7  274.65
  5203.4  276.08  5268.4  276.49  5332.6  278.20  5364.9  278.12  5478.4  280.38
  5526.5  280.63  5561.9  281.84  5615.7  282.42  5709.6  285.19  5996.3  291.69
#Mann=3,-1,0
  4213.4    0.05       0  4990.8    0.03       0  4996.8    0.05       0
Bank Sta=4990.8,4996.8
Exp/Cntr=0.3,0.1

Type RM Length L Ch R = 1,6457,64,64,64
BEGIN DESCRIPTION:
Mapping XS d7bad1f9
END DESCRIPTION:
XS GIS Cut Line= 4
      2214095.38     13283978.64      2213480.78     13283919.61
      2213400.92     13283923.08      2212418.26     13284391.84
#Sta/Elev= 30
  4359.9  289.72  4488.1  285.03  4539.4  283.86  4548.4  284.28  4598.7  281.64
  4809.6  276.01  4900.0  274.72  4930.2  275.30  4954.5  277.54  4981.4  277.36
  4990.4  276.90  5000.4  273.93  5027.3  275.86  5032.3  273.27  5040.4  276.14
  5050.5  276.37  5071.9  274.66  5074.5  272.51  5077.3  272.01  5080.5  272.51
  5094.0  272.72  5100.2  273.99  5151.2  273.97  5182.7  273.07  5393.2  276.67
  5678.6  279.88  5701.3  281.00  5792.1  281.94  5797.6  282.94  6146.0  291.23
#Mann=3,-1,0
  4359.9    0.05       0  5074.5    0.03       0  5080.5    0.05       0
Bank Sta=5074.5,5080.5
Exp/Cntr=0.3,0.1

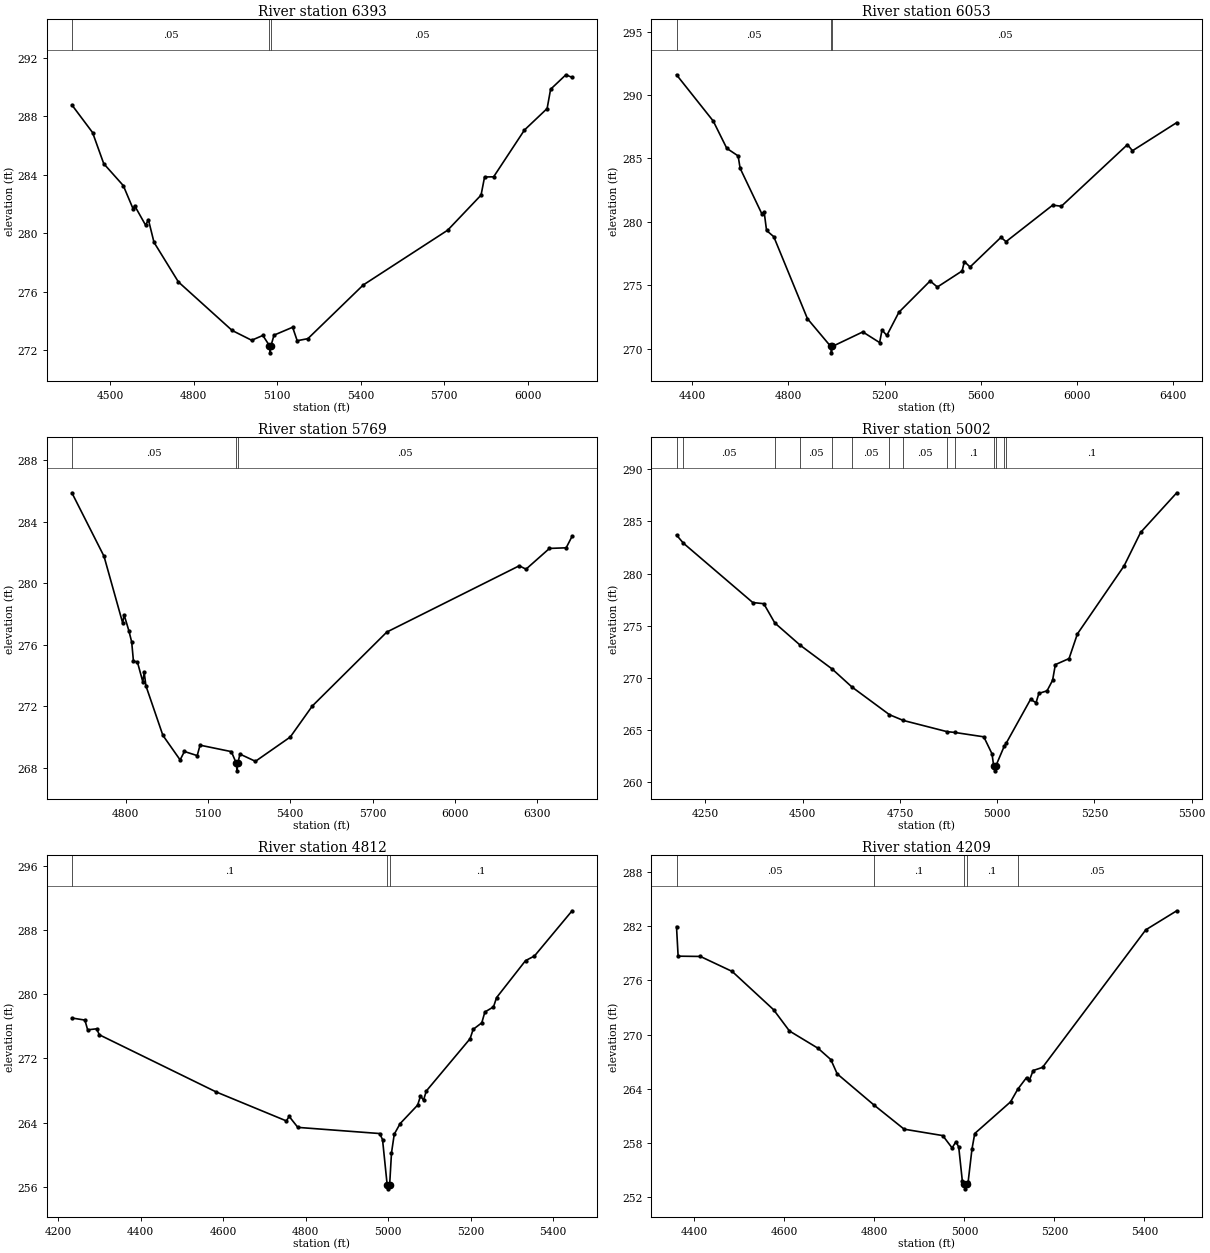
Type RM Length L Ch R = 1,6393,340,340,340
BEGIN DESCRIPTION:
Mapping XS dea6f775
END DESCRIPTION:
XS GIS Cut Line= 3
      2214091.93     13283895.30      2213352.31     13283850.16
      2212418.25     13284339.76
#Sta/Elev= 30
  4363.4  288.77  4437.7  286.88  4477.8  284.75  4548.0  283.25  4583.6  281.64
  4588.6  281.88  4628.1  280.54  4638.1  280.92  4658.2  279.37  4745.8  276.66
  4938.7  273.34  5008.8  272.67  5048.9  273.00  5072.3  272.31  5075.0  271.81
  5078.3  272.31  5089.0  273.02  5155.8  273.56  5172.2  272.64  5210.6  272.78
  5409.2  276.45  5712.4  280.20  5832.2  282.60  5844.8  283.84  5877.3  283.85
  5987.9  287.05  6069.3  288.52  6081.8  289.84  6136.7  290.83  6159.0  290.65
#Mann=3,-1,0
  4363.4    0.05       0  5072.3    0.03       0  5078.3    0.05       0
Bank Sta=5072.3,5078.3
Exp/Cntr=0.3,0.1

Type RM Length L Ch R = 1,6053,284,284,284
BEGIN DESCRIPTION:
UNT010 IN SPCR 11.0
END DESCRIPTION:
XS GIS Cut Line= 4
      2214183.20     13283665.07      2213955.92     13283546.70
      2213027.89     13283518.29      2212289.26     13284024.91
#Sta/Elev= 30
  4334.4  291.60  4487.2  287.95  4543.5  285.80  4590.7  285.20  4598.9  284.23
  4688.9  280.65  4698.9  280.79  4708.9  279.32  4738.9  278.83  4879.0  272.36
  4976.0  270.17  4978.8  269.67  4982.0  270.17  5109.1  271.32  5179.1  270.48
  5189.1  271.47  5209.1  271.04  5259.2  272.87  5389.2  275.34  5419.2  274.86
  5522.3  276.13  5531.5  276.87  5555.2  276.44  5683.8  278.78  5704.8  278.44
  5899.0  281.32  5934.9  281.23  6209.7  286.09  6230.7  285.61  6414.8  287.83
#Mann=3,-1,0
  4334.4    0.05       0  4976.0    0.03       0  4982.0    0.05       0
Bank Sta=4976,4982
Exp/Cntr=0.3,0.1

Type RM Length L Ch R = 1,5769,767,767,767
BEGIN DESCRIPTION:
Mapping XS 18a060a2
END DESCRIPTION:
XS GIS Cut Line= 3
      2213967.74     13283362.98      2213301.09     13283175.49
      2212176.13     13283300.48
#Sta/Elev= 30
  4603.5  285.88  4720.7  281.75  4788.8  277.41  4794.0  277.94  4811.3  276.91
  4821.7  276.17  4828.1  274.92  4842.4  274.88  4862.1  273.59  4867.3  274.19
  4873.6  273.32  4935.4  270.10  4998.3  268.50  5013.9  269.05  5060.6  268.78
  5071.0  269.46  5185.2  269.04  5203.0  268.29  5205.8  267.79  5209.0  268.29
  5216.4  268.88  5273.0  268.41  5400.0  269.99  5480.5  272.01  5752.2  276.82
  6235.1  281.13  6259.8  280.91  6345.3  282.26  6406.2  282.30  6427.9  283.05
#Mann=3,-1,0
  4603.5    0.05       0  5203.0    0.03       0  5209.0    0.05       0
Bank Sta=5203,5209
Exp/Cntr=0.3,0.1

Type RM Length L Ch R = 1,5002,190,190,190
BEGIN DESCRIPTION:
UNT010 IN SPCR 10.0
END DESCRIPTION:
XS GIS Cut Line= 2
      2213963.41     13283138.35      2213034.61     13282248.61
#Sta/Elev= 30
  4175.5  283.69  4193.2  282.91  4371.6  277.22  4399.9  277.11  4428.3  275.26
  4494.2  273.11  4575.7  270.85  4626.4  269.13  4723.1  266.47  4758.6  265.92
  4870.6  264.85  4890.8  264.77  4965.6  264.35  4986.7  262.72  4990.9  261.59
  4993.7  261.09  4996.9  261.59  5018.0  263.44  5022.9  263.72  5085.8  267.94
  5099.9  267.62  5107.2  268.51  5128.2  268.76  5142.4  269.76  5149.6  271.27
  5184.8  271.85  5206.2  274.21  5326.4  280.74  5368.8  283.94  5461.7  287.74
#Mann=14,-1,0
  4175.5    0.08       0  4193.2    0.05       0  4428.3    0.08       0
  4494.2    0.05       0  4575.7    0.08       0  4626.4    0.05       0
  4723.1    0.08       0  4758.6    0.05       0  4870.6    0.08       0
  4890.8     0.1       0  4990.9    0.07       0  4996.9     0.1       0
  5018.0    0.08       0  5022.9     0.1       0
Bank Sta=4990.9,4996.9
Exp/Cntr=0.3,0.1

Type RM Length L Ch R = 1,4812,603,603,603
BEGIN DESCRIPTION:
UNT010 IN SPCR 9.0
END DESCRIPTION:
XS GIS Cut Line= 2
      2214054.60     13282934.40      2213152.26     13282123.15
#Sta/Elev= 30
  4232.9  277.06  4264.5  276.80  4271.2  275.58  4292.9  275.71  4299.6  274.96
  4582.9  267.82  4753.1  264.20  4760.0  264.76  4781.0  263.39  4979.8  262.62
  4986.5  261.85  4997.7  256.21  5000.5  255.71  5003.7  256.21  5008.2  260.20
  5014.9  262.54  5029.1  263.86  5071.7  266.18  5078.5  267.31  5085.9  266.80
  5092.7  267.94  5198.8  274.47  5206.3  275.64  5227.2  276.46  5234.7  277.81
  5255.6  278.45  5263.1  279.61  5333.3  284.23  5355.0  284.81  5446.3  290.46
#Mann=3,-1,0
  4232.9     0.1       0  4997.7    0.07       0  5003.7     0.1       0
Bank Sta=4997.7,5003.7
Exp/Cntr=0.3,0.1

Type RM Length L Ch R = 1,4209,464,464,464
BEGIN DESCRIPTION:
UNT010 IN SPCR 8.0
END DESCRIPTION:
XS GIS Cut Line= 3
      2214476.75     13282722.83      2214131.11     13282372.46
      2213767.00     13281871.21
#Sta/Elev= 30
  4360.2  281.97  4363.8  278.69  4413.2  278.66  4483.9  277.00  4575.9  272.76
  4611.2  270.40  4674.9  268.48  4703.2  267.23  4717.3  265.65  4799.5  262.18
  4866.1  259.52  4951.9  258.81  4972.7  257.44  4981.2  258.14  4987.4  257.53
  4995.3  253.82  4999.1  253.41  5001.8  252.91  5005.1  253.41  5008.3  253.67
  5016.8  257.31  5023.0  259.04  5102.6  262.55  5118.6  263.95  5138.1  265.24
  5144.3  264.92  5152.8  266.02  5173.7  266.37  5403.1  281.61  5471.9  283.72
#Mann=5,-1,0
  4360.2    0.05       0  4799.5     0.1       0  4999.1    0.07       0
  5005.1     0.1       0  5118.6    0.05       0
Bank Sta=4999.1,5005.1
Exp/Cntr=0.3,0.1

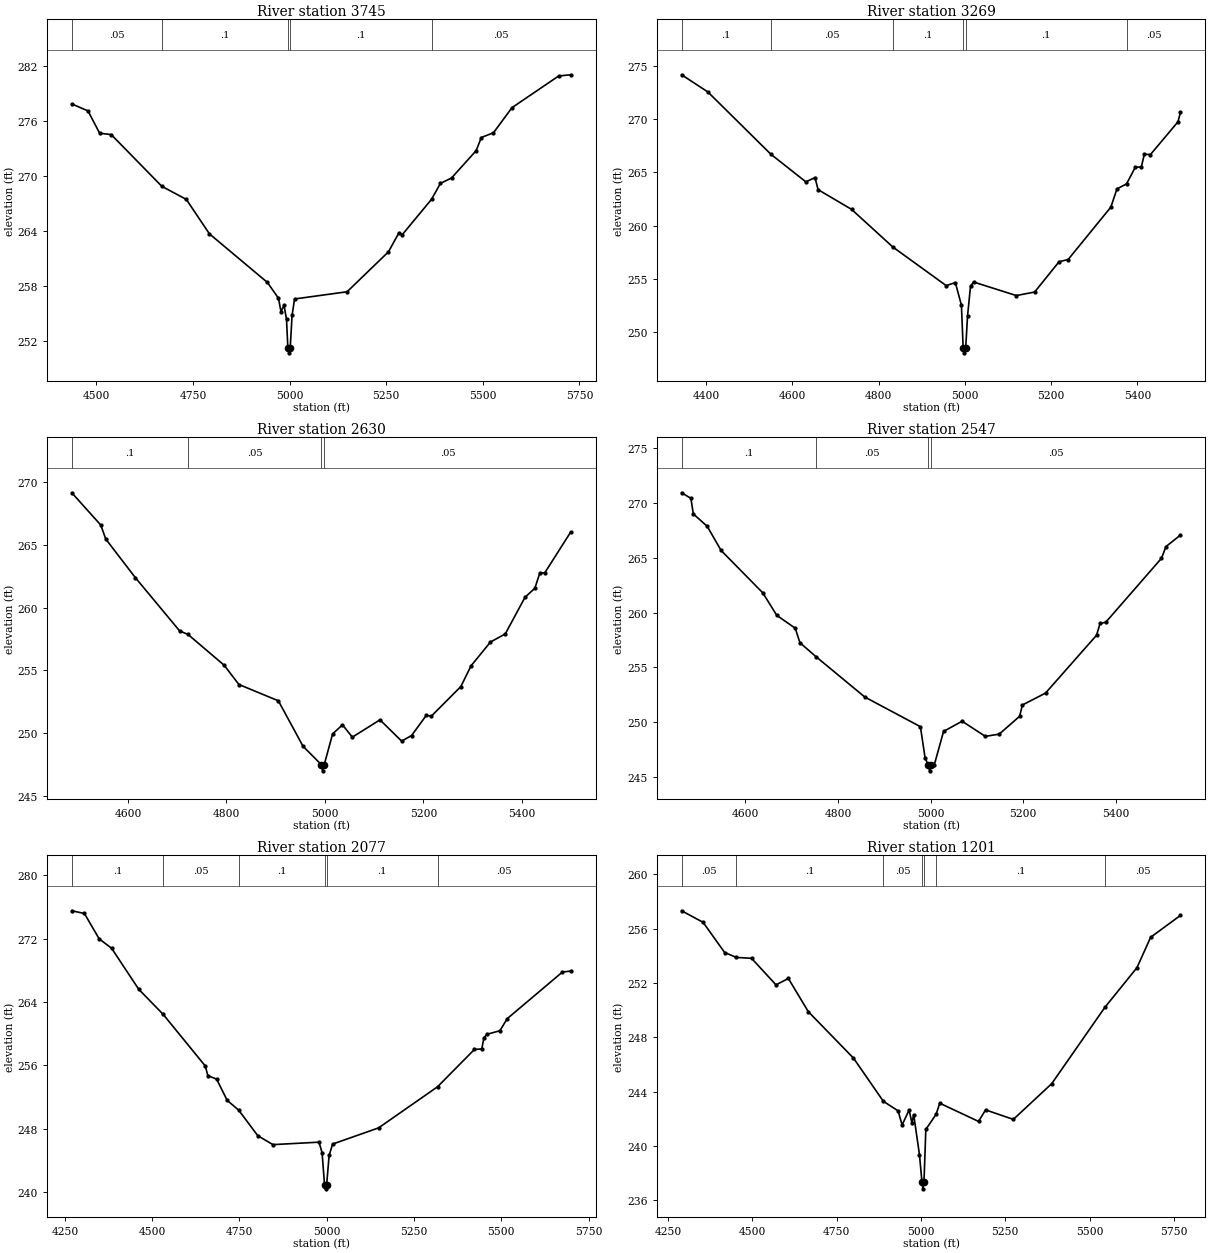
Type RM Length L Ch R = 1,3745,476,476,476
BEGIN DESCRIPTION:
UNT010 IN SPCR 7.0
END DESCRIPTION:
XS GIS Cut Line= 4
      2214666.14     13282618.66      2214647.21     13282325.11
      2214164.25     13281728.52      2213936.95     13281756.93
#Sta/Elev= 30
  4436.4  277.88  4478.3  277.12  4508.4  274.68  4538.4  274.53  4669.4  268.87
  4732.7  267.44  4792.6  263.67  4942.5  258.36  4971.2  256.63  4977.6  255.18
  4985.6  255.84  4992.0  254.31  4995.5  251.16  4998.2  250.66  5001.5  251.16
  5006.4  254.77  5012.8  256.55  5148.7  257.34  5255.8  261.71  5283.0  263.80
  5291.0  263.56  5367.4  267.46  5390.1  269.19  5418.9  269.78  5482.8  272.78
  5496.0  274.21  5527.5  274.73  5575.3  277.47  5696.2  280.94  5727.2  281.07
#Mann=5,-1,0
  4436.4    0.05       0  4669.4     0.1       0  4995.5    0.07       0
  5001.5     0.1       0  5367.4    0.05       0
Bank Sta=4995.5,5001.5
Exp/Cntr=0.3,0.1

Type RM Length L Ch R = 1,3269,639,639,639
BEGIN DESCRIPTION:
UNT010 IN SPCR 6.0
END DESCRIPTION:
XS GIS Cut Line= 3
      2215057.56     13282317.78      2215057.56     13282035.69
      2214449.92     13281406.35
#Sta/Elev= 30
  4343.0  274.16  4403.9  272.55  4550.0  266.71  4631.2  264.12  4652.3  264.52
  4659.5  263.39  4737.2  261.54  4832.6  258.02  4956.7  254.39  4977.8  254.68
  4991.9  252.56  4995.9  248.59  4998.6  248.09  5001.9  248.59  5006.1  251.54
  5013.0  254.34  5020.2  254.73  5119.2  253.46  5161.7  253.79  5218.3  256.63
  5239.4  256.84  5338.4  261.75  5352.6  263.46  5374.8  263.93  5395.0  265.48
  5409.2  265.53  5416.1  266.71  5430.3  266.68  5494.1  269.75  5499.9  270.64
#Mann=6,-1,0
  4343.0     0.1       0  4550.0    0.05       0  4832.6     0.1       0
  4995.9    0.07       0  5001.9     0.1       0  5374.8    0.05       0
Bank Sta=4995.9,5001.9
Exp/Cntr=0.3,0.1

Type RM Length L Ch R = 1,2630,83,83,83
BEGIN DESCRIPTION:
Mapping XS fbcb0886
END DESCRIPTION:
XS GIS Cut Line= 2
      2215686.51     13281306.76      2214675.18     13281250.33
#Sta/Elev= 30
  4485.9  269.17  4544.8  266.59  4554.8  265.48  4614.9  262.40  4705.0  258.14
  4721.7  257.87  4795.2  255.41  4825.2  253.87  4905.3  252.57  4955.4  248.94
  4992.5  247.48  4995.2  246.98  4998.5  247.48  5015.5  249.93  5035.5  250.65
  5055.6  249.67  5111.6  251.05  5155.7  249.35  5175.8  249.80  5205.8  251.41
  5215.8  251.34  5275.9  253.71  5296.5  255.36  5336.0  257.26  5366.1  257.91
  5406.1  260.83  5426.1  261.55  5436.2  262.77  5446.2  262.78  5498.8  266.03
#Mann=4,-1,0
  4485.9     0.1       0  4721.7    0.05       0  4992.5    0.03       0
  4998.5    0.05       0
Bank Sta=4992.5,4998.5
Exp/Cntr=0.3,0.1

Type RM Length L Ch R = 1,2547,470,470,470
BEGIN DESCRIPTION:
Mapping XS d9689422
END DESCRIPTION:
XS GIS Cut Line= 2
      2215742.97     13281232.98      2214666.58     13281172.21
#Sta/Elev= 30
  4462.1  270.94  4482.2  270.43  4487.4  269.01  4517.4  267.88  4547.5  265.67
  4637.6  261.80  4667.7  259.75  4707.7  258.57  4717.8  257.25  4752.1  255.99
  4858.0  252.29  4978.2  249.58  4988.2  246.75  4995.2  246.05  4998.0  245.55
  5001.2  246.05  5008.2  246.10  5028.2  249.15  5068.3  250.08  5118.4  248.70
  5148.4  248.90  5192.6  250.53  5198.5  251.56  5248.6  252.65  5358.8  257.93
  5366.5  259.01  5378.8  259.12  5499.0  264.95  5509.0  266.03  5540.2  267.08
#Mann=4,-1,0
  4462.1     0.1       0  4752.1    0.05       0  4995.2    0.03       0
  5001.2    0.05       0
Bank Sta=4995.2,5001.2
Exp/Cntr=0.3,0.1

Type RM Length L Ch R = 1,2077,876,876,876
BEGIN DESCRIPTION:
UNT010 IN SPCR 3.0
END DESCRIPTION:
XS GIS Cut Line= 4
      2215925.61     13281069.97      2215643.50     13280787.86
      2215003.31     13280711.91      2214677.76     13280918.09
#Sta/Elev= 30
  4269.8  275.50  4305.9  275.16  4348.3  271.95  4383.7  270.78  4461.4  265.60
  4531.7  262.42  4652.4  255.90  4659.4  254.70  4684.7  254.25  4714.8  251.58
  4748.1  250.33  4802.5  247.12  4845.8  245.99  4978.0  246.30  4986.8  244.96
  4993.8  240.91  4996.6  240.41  4999.8  240.91  5006.9  244.63  5017.0  246.06
  5148.5  248.10  5317.5  253.29  5423.1  258.00  5444.3  258.07  5450.3  259.47
  5459.5  259.92  5496.0  260.36  5517.2  261.89  5675.2  267.77  5698.8  267.89
#Mann=6,-1,0
  4269.8     0.1       0  4531.7    0.05       0  4748.1     0.1       0
  4993.8    0.07       0  4999.8     0.1       0  5317.5    0.05       0
Bank Sta=4993.8,4999.8
Exp/Cntr=0.3,0.1

Type RM Length L Ch R = 1,1201,1073,1073,1073
BEGIN DESCRIPTION:
UNT010 IN SPCR 2.0
END DESCRIPTION:
XS GIS Cut Line= 4
      2215958.18     13280473.21      2215762.85     13280158.52
      2215068.41     13279984.91      2214710.36     13280147.66
#Sta/Elev= 30
  4290.3  257.31  4354.1  256.46  4417.9  254.24  4452.7  253.88  4497.9  253.81
  4570.2  251.86  4606.9  252.33  4666.0  249.89  4800.0  246.47  4888.7  243.29
  4932.2  242.59  4944.3  241.55  4964.9  242.65  4973.4  241.70  4978.6  242.31
  4995.8  239.35  5003.1  237.35  5005.9  236.85  5009.1  237.35  5014.6  241.22
  5045.0  242.33  5055.9  243.15  5171.0  241.81  5191.7  242.66  5274.1  241.96
  5388.0  244.59  5545.8  250.21  5640.9  253.13  5681.3  255.36  5769.8  256.97
#Mann=7,-1,0
  4290.3    0.05       0  4452.7     0.1       0  4888.7    0.05       0
  5003.1   0.033       0  5009.1    0.05       0  5045.0     0.1       0
  5545.8    0.05       0
Bank Sta=5003.1,5009.1
Exp/Cntr=0.3,0.1

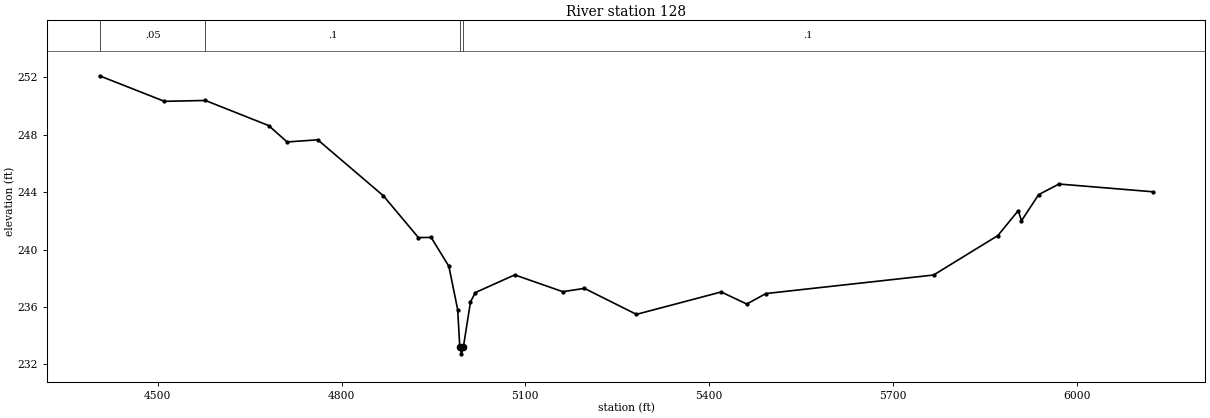
Type RM Length L Ch R = 1,128,0,0,0
BEGIN DESCRIPTION:
UNT010 IN SPCR 1.0
END DESCRIPTION:
XS GIS Cut Line= 4
      2216142.63     13280082.61      2216164.33     13279691.94
      2215752.00     13279366.42      2214982.18     13279594.11
#Sta/Elev= 30
  4404.8  252.11  4510.7  250.33  4577.6  250.39  4681.0  248.64  4711.0  247.50
  4761.1  247.65  4868.2  243.75  4925.4  240.84  4946.2  240.85  4975.1  238.84
  4989.5  235.82  4992.9  233.24  4995.7  232.74  4998.9  233.24  5010.4  236.36
  5018.4  237.01  5082.6  238.24  5161.1  237.07  5196.4  237.30  5281.3  235.49
  5419.7  237.05  5461.4  236.21  5492.7  236.94  5766.4  238.23  5871.4  240.98
  5904.7  242.72  5909.9  242.01  5937.9  243.83  5971.2  244.57  6124.2  244.03
#Mann=4,-1,0
  4404.8    0.05       0  4577.6     0.1       0  4992.9    0.07       0
  4998.9     0.1       0
Bank Sta=4992.9,4998.9
Exp/Cntr=0.3,0.1

Chan Stop Cuts=-1