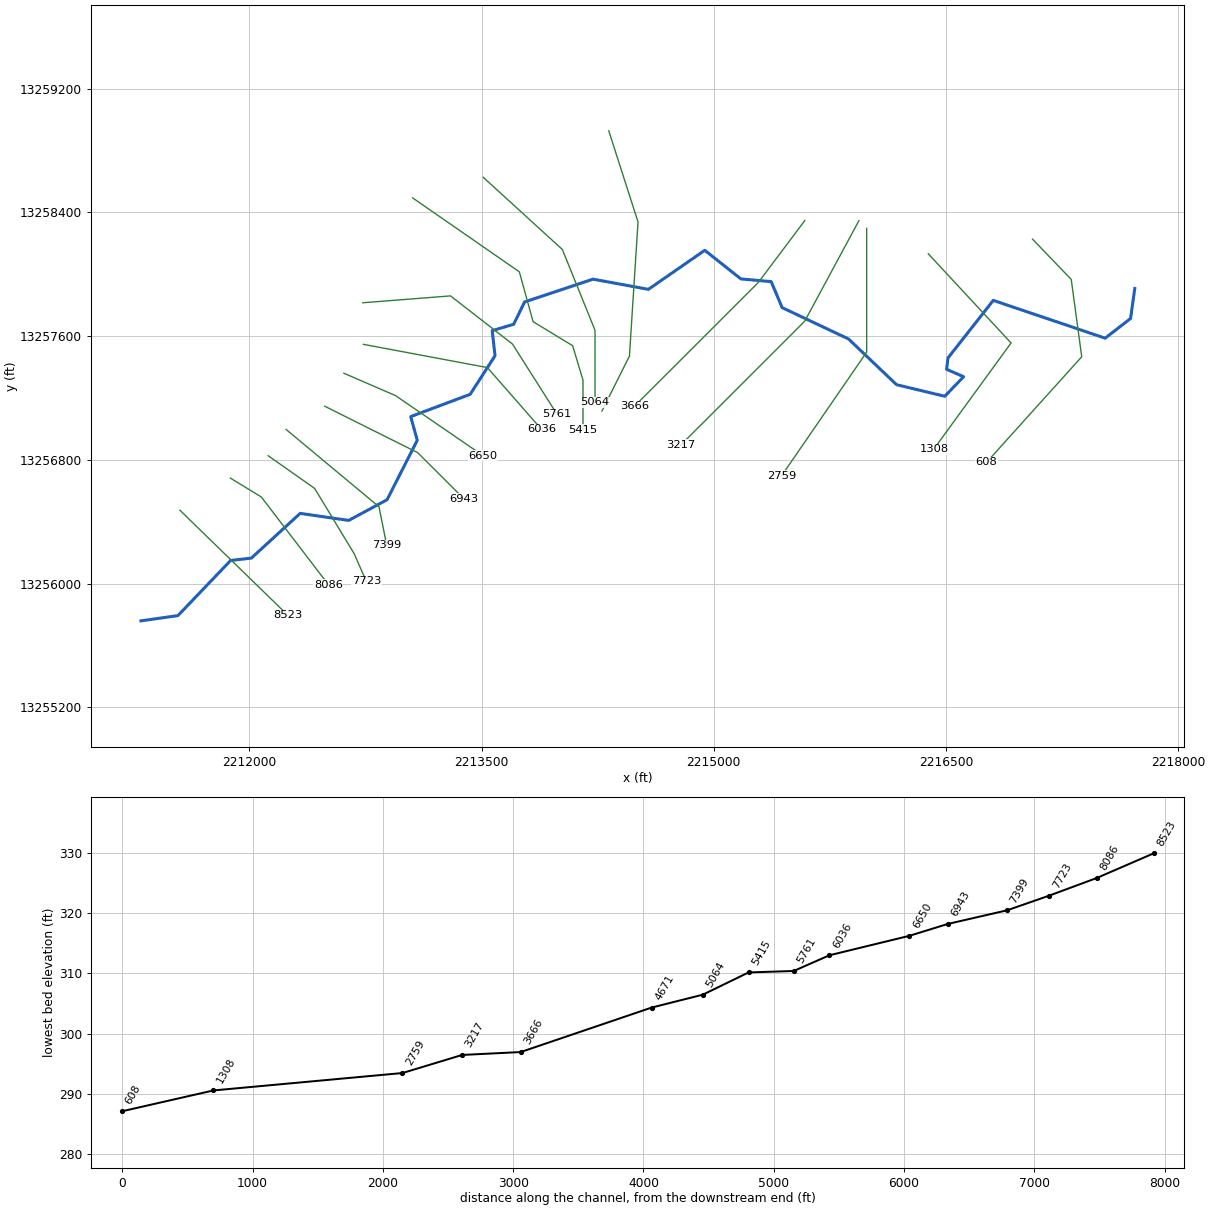
--- UNT012 IN SPCR.prj (project) ---

Proj Title=UNT012 IN SPCR Base Level Engineering
Current Plan=p01
Default Exp/Contr=0.3,0.1
English Units
Geom File=g01
Flow File=f01
Plan File=p01
Y Axis Title=Elevation
X Axis Title(PF)=Main Channel Distance
X Axis Title(XS)=Station
BEGIN DESCRIPTION:
UNT012 IN SPCR
END DESCRIPTION:
DSS Export Rating Curves= 0
DSS Export Rating Curve Sorted= 0
DSS Export Volume Flow Curves= 0
DXF OffsetX= 0
DXF OffsetY= 0
DXF ScaleX= 1
DXF ScaleY= 10

--- UNT012 IN SPCR.p01 (plan) ---

Plan Title=Multiple Run
Short Identifier=Multiple
Geom File=g01
Flow File=f01
Subcritical Flow
K Sum by GR= 0
Std Step Tol= 0.01
Critical Tol= 0.01
Num of Std Step Trials= 20
Max Error Tol= 0.3
Flow Tol Ratio= 0.001
Split Flow NTrial= 30
Split Flow Tol= 0.02
Split Flow Ratio= 0.02
Log Output Level= 0
Friction Slope Method= 1
Unsteady Friction Slope Method= 2
Unsteady Bridges Friction Slope Method= 1
Parabolic Critical Depth
Global Vel Dist=  1 , 1 , 1
Global Log Level= 0
CheckData=True
Encroach Param= -1, 0, 0, 0
BEGIN DESCRIPTION:
Multiple Run
END DESCRIPTION:

--- UNT012 IN SPCR.f01 (steady flow) ---

Flow Title=Multiple
Number of Profiles=7
Profile Names=10-year,25-year,50-year,1pct_min,100-year,1pct_plu,500-year
River Rch & RM= UNT012 IN SPCR,Reach-1,8523
     321     457     572     528     713     965    1127
Boundary for River Rch & Prof#=UNT012 IN SPCR,Reach-1,1
Up Type=0
Dn Type=3
Dn Slope=0.005
Boundary for River Rch & Prof#=UNT012 IN SPCR,Reach-1,2
Up Type=0
Dn Type=3
Dn Slope=0.005
Boundary for River Rch & Prof#=UNT012 IN SPCR,Reach-1,3
Up Type=0
Dn Type=3
Dn Slope=0.005
Boundary for River Rch & Prof#=UNT012 IN SPCR,Reach-1,4
Up Type=0
Dn Type=3
Dn Slope=0.005
Boundary for River Rch & Prof#=UNT012 IN SPCR,Reach-1,5
Up Type=0
Dn Type=3
Dn Slope=0.005
Boundary for River Rch & Prof#=UNT012 IN SPCR,Reach-1,6
Up Type=0
Dn Type=3
Dn Slope=0.005
Boundary for River Rch & Prof#=UNT012 IN SPCR,Reach-1,7
Up Type=0
Dn Type=3
Dn Slope=0.005

--- UNT012 IN SPCR.g01 (geometry) ---

Geom Title=Existing Conditions
Program Version=4.10

River Reach=UNT012 IN SPCR  ,Reach-1
Reach XY= 30
       2211300.3     13255759.73      2211538.78     13255793.31
      2211879.57     13256150.03      2212013.11     13256165.03
      2212328.56     13256454.32      2212642.03     13256408.94
      2212889.63     13256542.26      2213084.98     13256926.87
       2213042.4     13257079.76      2213426.73     13257224.09
      2213587.14     13257473.26      2213568.91     13257635.58
      2213707.68     13257676.84      2213778.07     13257821.06
      2214220.15     13257968.34      2214577.76     13257902.64
      2214942.02     13258154.91      2215175.15     13257969.95
      2215370.91     13257952.47      2215441.68     13257784.33
       2215870.4     13257581.86      2216180.82     13257286.02
      2216492.17     13257211.38      2216613.83     13257337.69
      2216503.89     13257385.75       2216512.9     13257459.19
      2216805.35     13257831.24      2217528.14     13257586.87
      2217692.28     13257714.32      2217719.38     13257908.02

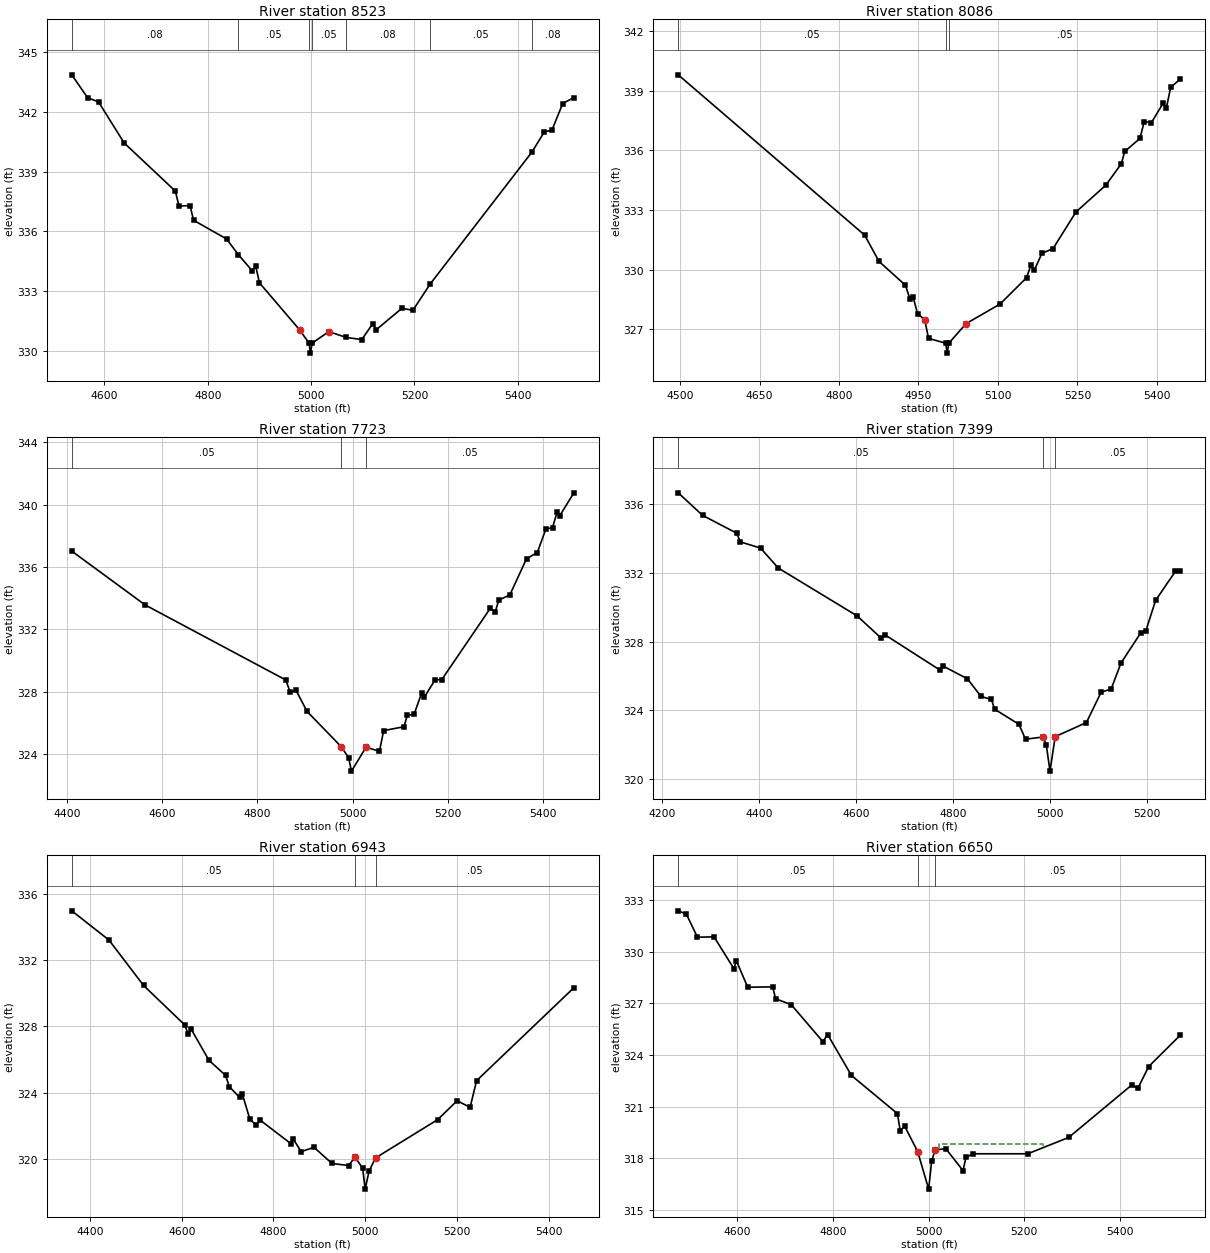
Type RM Length L Ch R = 1 ,8523    ,437,437,437
BEGIN DESCRIPTION:
UNT012 IN SPCR 15.0
END DESCRIPTION:
XS GIS Cut Line= 2
      2211551.91     13256474.45       2212247.9     13255796.65
#Sta/Elev= 30
  4536.9  343.86  4567.6  342.71  4588.7   342.5  4638.3  340.44  4737.4  338.02
  4744.3  337.27  4765.7   337.3  4772.6  336.56  4836.4  335.62    4859  334.84
  4885.8  334.03    4893  334.24    4900  333.42  4977.7  331.06    4996  330.39
  4998.7  329.89    5002  330.39  5034.2  330.97  5067.7  330.68    5098  330.57
  5119.1  331.36  5126.3  331.07  5175.7  332.14    5197  332.04  5230.4  333.36
  5427.5  339.99  5451.6  341.01  5465.8  341.07  5486.9  342.42  5508.4  342.72
#Mann= 7 ,-1 , 0
  4536.9     .08       0    4859     .05       0    4996     .04       0
    5002     .05       0  5067.7     .08       0  5230.4     .05       0
  5427.5     .08       0
Bank Sta=4977.7,5034.2
XS Rating Curve= 0 ,0
Exp/Cntr=0.3,0.1

Type RM Length L Ch R = 1 ,8086    ,363,363,363
BEGIN DESCRIPTION:
UNT012 IN SPCR 13.0
END DESCRIPTION:
XS GIS Cut Line= 3
      2211877.52     13256682.45       2212077.5     13256560.24
      2212510.81     13255993.59
#Sta/Elev= 30
  4496.5  339.79  4848.4  331.73  4875.5  330.41  4925.4  329.21  4933.6  328.54
  4939.9  328.62  4948.2  327.78  4961.7  327.48    4969  326.54  5001.3   326.3
  5004.1   325.8  5007.3   326.3  5039.7  327.28  5104.1  328.27  5153.9  329.59
  5162.2  330.22  5168.5  329.96    5183  330.82  5203.8  331.05  5247.4   332.9
  5303.5  334.24  5332.6  335.31  5339.4  335.94  5367.9  336.59  5376.2  337.44
  5389.7  337.39  5411.5  338.35  5417.8  338.11    5426  339.16  5444.2  339.58
#Mann= 3 ,-1 , 0
  4496.5     .05       0  5001.3     .03       0  5007.3     .05       0
Bank Sta=4961.7,5039.7
XS Rating Curve= 0 ,0
Exp/Cntr=0.3,0.1

Type RM Length L Ch R = 1 ,7723    ,324,324,324
BEGIN DESCRIPTION:
UNT012 IN SPCR 12.0
END DESCRIPTION:
XS GIS Cut Line= 4
      2212121.97     13256826.89      2212421.94      13256615.8
       2212677.5     13256193.57      2212755.28     13256015.78
#Sta/Elev= 30
    4410  337.01  4563.8  333.56  4859.4  328.74    4869  327.94  4880.8  328.09
  4904.1  326.72  4975.8  324.46  4991.3  323.76  4997.4  322.89  5028.1  324.43
  5056.1  324.16    5065  325.49  5107.7  325.74  5114.5  326.46    5129  326.55
  5144.5  327.88  5150.3  327.63    5173  328.75  5187.2  328.77  5288.7  333.33
  5299.5  333.12  5306.6  333.86    5330   334.2    5365  336.52  5387.7  336.92
  5405.7  338.43  5419.6  338.52    5429  339.49  5434.5  339.26  5464.4  340.75
#Mann= 3 , 0 , 0
    4410     .05       0  4975.8     .03       0  5028.1     .05       0
Bank Sta=4975.8,5028.1
XS Rating Curve= 0 ,0
Exp/Cntr=0.3,0.1

Type RM Length L Ch R = 1 ,7399    ,456,456,456
BEGIN DESCRIPTION:
UNT012 IN SPCR 11.0
END DESCRIPTION:
XS GIS Cut Line= 3
      2212237.73     13256996.85      2212837.72     13256496.85
      2212887.73     13256246.82
#Sta/Elev= 30
    4233  336.67  4283.1  335.36  4353.4  334.32  4361.2  333.81  4402.9  333.45
  4439.3  332.29    4602   329.5  4651.5  328.21  4659.3   328.4  4772.5  326.35
  4779.7  326.57  4829.8  325.83  4857.8   324.8  4879.3  324.63  4885.8  324.06
  4935.9  323.18  4949.6  322.31    4986  322.44  4992.5  321.97  5000.1  320.45
  5010.8  322.46  5075.2  323.28  5105.8  325.06  5126.2  325.23  5146.6  326.75
  5187.4  328.51  5197.6   328.6    5218   330.4  5258.8  332.09    5269  332.13
#Mann= 3 , 0 , 0
    4233     .05       0    4986     .03       0  5010.8     .05       0
Bank Sta=4986,5010.8
XS Rating Curve= 0 ,0
Exp/Cntr=0.3,0.1

Type RM Length L Ch R = 1 ,6943    ,293,293,293
BEGIN DESCRIPTION:
UNT012 IN SPCR 10.0
END DESCRIPTION:
XS GIS Cut Line= 3
       2212487.7     13257146.87      2213087.72     13256846.85
      2213387.71     13256546.86
#Sta/Elev= 30
    4360  334.96  4441.1   333.2  4516.6  330.46    4606  328.09  4614.4  327.51
    4620  327.85  4659.1  325.95  4695.4  325.04  4703.8  324.35  4726.2  323.71
  4731.8  323.93  4748.5  322.39  4762.5  322.03  4770.9  322.34    4838  320.92
  4843.6  321.18  4860.3  320.44  4888.3   320.7  4927.4  319.73  4963.8   319.6
  4977.7  320.11  4994.5  319.44  4999.9  318.18  5008.5  319.27  5022.5  320.06
  5158.1  322.37  5200.6  323.51  5228.8  323.11    5243  324.72  5455.1  330.32
#Mann= 3 , 0 , 0
    4360     .05       0  4977.7     .03       0  5022.5     .05       0
Bank Sta=4977.7,5022.5
XS Rating Curve= 0 ,0
Exp/Cntr=0.3,0.1

Type RM Length L Ch R = 1 ,6650    ,614,614,614
BEGIN DESCRIPTION:
UNT012 IN SPCR 9.0
END DESCRIPTION:
XS GIS Cut Line= 3
      2212610.83     13257360.24      2212944.16      13257215.8
      2213510.87     13256826.88
#Sta/Elev= 30
  4476.1  332.36  4493.1  332.17  4516.3  330.83    4551  330.85  4592.5  329.01
  4597.9  329.46  4621.4  327.93  4673.8  327.95  4679.8  327.26  4712.5  326.92
  4778.6  324.78  4788.8  325.18  4838.6  322.81  4934.7   320.6  4940.7  319.59
  4949.6  319.89  4977.1   318.4  5000.1  316.22  5006.4  317.83  5013.5   318.5
  5036.2  318.56  5072.1  317.29  5078.1  318.06    5093  318.27  5207.5  318.27
  5293.3  319.22  5424.7  322.25    5438  322.07  5460.5  323.33  5526.7  325.15
#Mann= 3 , 0 , 0
  4476.1     .05       0  4977.1     .03       0  5013.5     .05       0
#XS Ineff= 1 ,-1
 5021.14 5239.53318.8153
Permanent Ineff=
       F
Bank Sta=4977.1,5013.5
XS Rating Curve= 0 ,0
Exp/Cntr=0.3,0.1

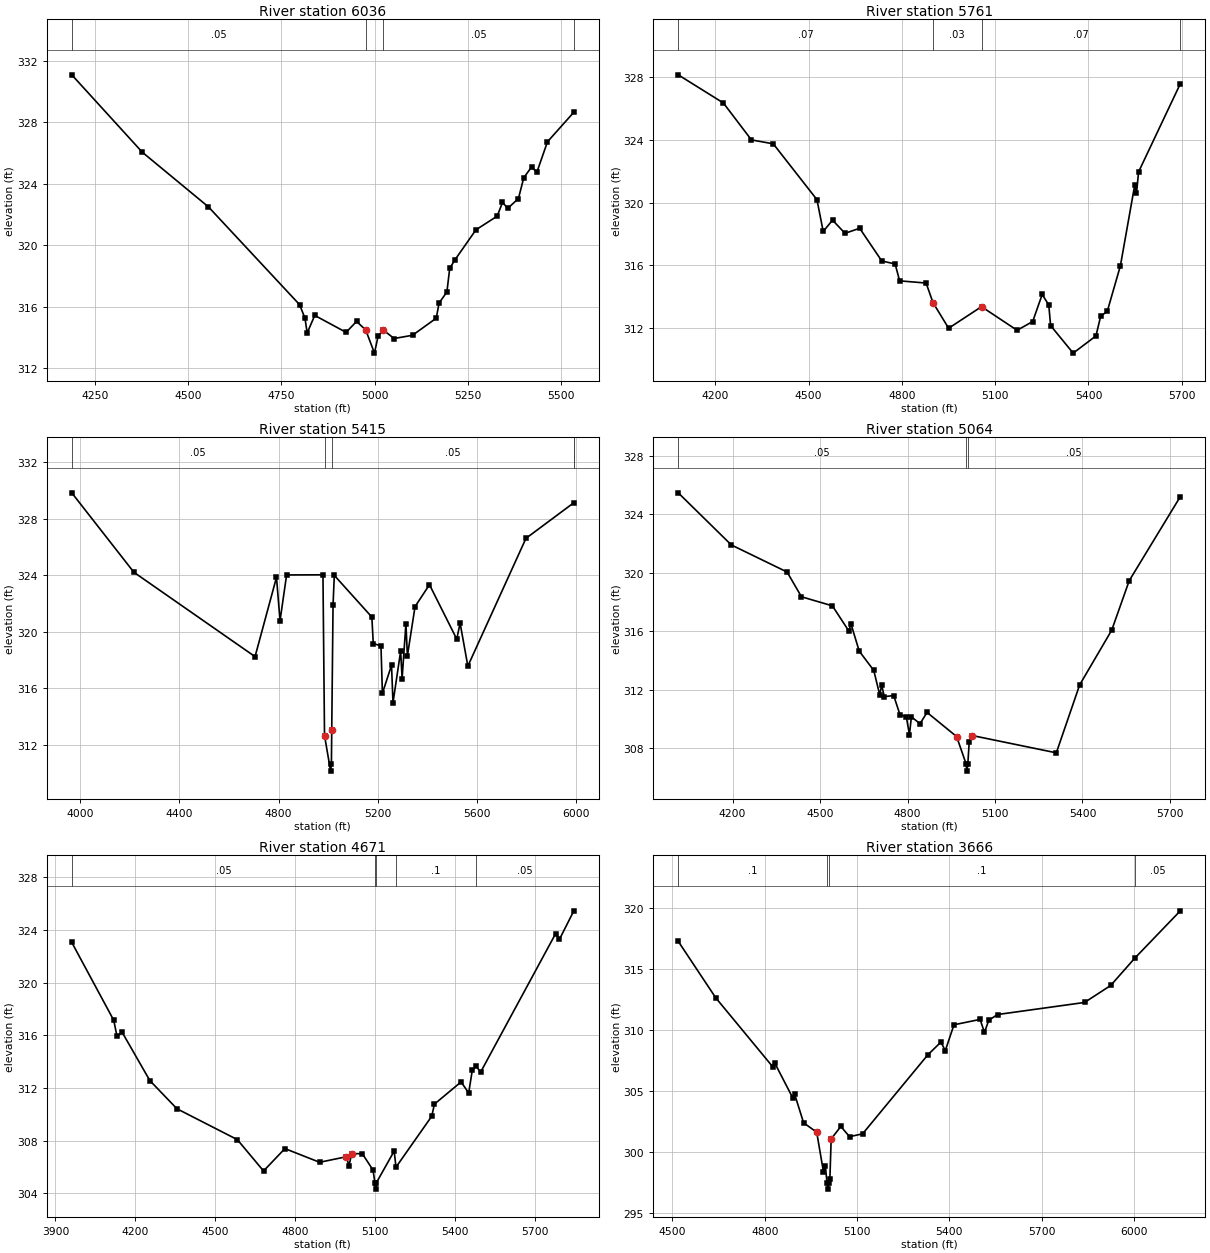
Type RM Length L Ch R = 1 ,6036    ,275,275,275
BEGIN DESCRIPTION:
UNT012 IN SPCR 8.0
END DESCRIPTION:
XS GIS Cut Line= 3
      2212737.73     13257546.85      2213537.72     13257396.85
       2213887.7     13256996.88
#Sta/Elev= 30
  4188.1  331.07  4377.2  326.04  4554.4  322.49  4798.5  316.14    4813  315.26
  4818.9   314.3  4839.2  315.44  4923.2  314.34  4951.2  315.05  4975.7   314.5
  4999.2  312.99  5009.1  314.11  5023.4  314.48  5051.9  313.94  5101.2  314.15
  5164.8  315.26  5172.4  316.25  5193.3  316.96  5200.9   318.5  5214.6  319.04
  5271.1     321  5328.1  321.89  5342.3  322.78  5356.5   322.4    5385  323.03
  5399.2  324.38  5420.1  325.08  5434.4  324.74  5462.8  326.72  5533.5  328.64
#Mann= 4 ,-1 , 0
  4188.1     .05       0  4975.7     .03       0  5023.4     .05       0
  5533.5     .05       0
Bank Sta=4975.7,5023.4
XS Rating Curve= 0 ,0
Exp/Cntr=0.3,0.1

Type RM Length L Ch R = 1 ,5761    ,346,346,346
BEGIN DESCRIPTION:
Mapping XS 993ec436
END DESCRIPTION:
XS GIS Cut Line= 4
      2212733.01     13257815.79      2213299.72     13257860.24
      2213699.72     13257549.13       2213988.6     13257093.59
#Sta/Elev= 30
  4080.7  328.17  4225.9  326.37  4316.1  324.01  4386.3  323.76  4526.8  320.19
  4546.9  318.16  4576.9  318.88    4617  318.04  4664.2  318.36  4735.3  316.27
  4778.2  316.08  4792.7     315  4877.8  314.86    4900  313.61  4950.2  311.97
    5056  313.35  5170.4  311.84  5220.6   312.4  5251.1  314.13  5272.3  313.46
  5278.2  312.14  5350.8  310.38    5424  311.48  5439.2  312.74  5460.4  313.05
  5502.7  315.97  5548.5   321.1  5554.4  320.61  5561.2  321.97  5695.3   327.6
#Mann= 4 ,-1 , 0
  4080.7     .07       0    4900     .03       0    5056     .07       0
  5695.3     .05       0
Bank Sta=4900,5056
XS Rating Curve= 0 ,0
Exp/Cntr=0.3,0.1

Type RM Length L Ch R = 1 ,5415    ,351,351,351
BEGIN DESCRIPTION:
UNT012 IN SPCR 7.0
END DESCRIPTION:
XS GIS Cut Line= 6
      2213055.26     13258493.59      2213744.16      13258015.8
      2213833.05     13257693.57      2214088.61     13257538.02
      2214155.28      13257315.8      2214155.28     13256993.61
#Sta/Elev= 30
  3965.6  329.83  4216.2  324.21  4705.2  318.24  4791.7  323.85    4806  320.78
  4832.5  324.02  4979.2  324.03  4985.5  312.66  5010.1  310.14  5013.3  310.64
 5014.63  313.03  5019.9  321.89    5025  323.99  5176.5  321.04  5182.3  319.16
  5213.3  319.01  5219.1  315.65  5255.9  317.63  5261.8  314.98  5292.7  318.63
  5298.6  316.69    5314  320.58  5319.9  318.29  5350.8  321.78    5409  323.33
  5519.1  319.48  5532.6  320.61  5563.9  317.57  5798.4  326.61  5991.6  329.13
#Mann= 5 ,-1 , 0
  3965.6     .05       0  4985.5     .03       0 5014.63     .05       0
  5991.6     .12       0  5991.6     .05       0
Bank Sta=4985.5,5014.63
XS Rating Curve= 0 ,0
Exp/Cntr=0.3,0.1

Type RM Length L Ch R = 1 ,5064    ,393,393,393
BEGIN DESCRIPTION:
UNT012 IN SPCR 6.0
END DESCRIPTION:
XS GIS Cut Line= 4
       2213510.8     13258626.94      2214021.94     13258160.24
      2214233.05     13257638.02      2214233.05     13257171.65
#Sta/Elev= 30
  4013.7  325.46  4195.8   321.9    4387  320.05  4436.3  318.36  4542.4  317.74
  4599.1  316.01  4605.9  316.52  4634.3  314.65  4684.2  313.33  4704.7  311.66
  4711.4  312.33  4720.3  311.54  4752.6  311.61  4774.2   310.3  4795.8  310.16
  4806.6  308.95  4813.3  310.16  4842.8  309.69    4867  310.46  4968.4  308.81
  5000.8  306.95  5003.5  306.45  5006.8  306.95  5011.5  308.42  5022.3  308.88
  5310.3   307.7  5390.3  312.34  5500.3  316.08  5560.3  319.46  5735.5   325.2
#Mann= 3 ,-1 , 0
  4013.7     .05       0  5000.8     .03       0  5006.8     .05       0
Bank Sta=4968.4,5022.3
XS Rating Curve= 0 ,0
Exp/Cntr=0.3,0.1

Type RM Length L Ch R = 1 ,4671    ,1005,1005,1005
BEGIN DESCRIPTION:
UNT012 IN SPCR 5.0
END DESCRIPTION:
XS GIS Cut Line= 4
      2214321.94      13258926.9      2214510.83     13258338.02
      2214455.28     13257471.35       2214277.5      13257115.8
#Sta/Elev= 30
  3961.2  323.06  4118.8  317.14    4131  315.92  4150.3  316.23  4254.2  312.56
  4355.8  310.42  4582.7  308.07    4681  305.69  4761.2  307.39  4891.4  306.35
  4991.6  306.77  5001.7  306.09  5011.7  307.01  5051.8     307  5091.8  305.76
  5098.9  304.81  5101.6  304.31  5104.9  304.81  5171.2   307.2  5178.1  305.98
  5312.3  309.85  5322.3  310.77  5422.5  312.46  5450.9  311.61  5464.3  313.33
  5478.6  313.68  5495.4  313.19  5777.3  323.73  5791.7   323.3  5845.6  325.46
#Mann= 5 ,-1 , 0
  3961.2     .05       0  5098.9     .03       0  5104.9     .05       0
  5178.1      .1       0  5478.6     .05       0
Bank Sta=4991.6,5011.7
XS Rating Curve= 0 ,0
Exp/Cntr=0.3,0.1

Type RM Length L Ch R = 1 ,3666    ,449,449,449
BEGIN DESCRIPTION:
UNT012 IN SPCR 4.0
END DESCRIPTION:
XS GIS Cut Line= 3
      2215587.72     13258346.85      2215287.72     13257946.85
       2214487.7     13257146.83
#Sta/Elev= 30
  4518.8  317.24  4640.7  312.61  4826.1  306.95  4832.3  307.27  4890.7  304.42
  4896.9  304.72  4926.1  302.37  4968.8  301.59  4990.7  298.34  4996.9  298.82
  5002.3  297.43    5005  296.93  5008.3  297.43  5011.5  297.74  5015.7  301.04
  5047.1  302.07  5075.4  301.23  5117.8  301.46  5329.9  307.94  5372.4  308.98
  5386.5  308.28  5414.8   310.4  5499.6  310.84  5513.8  309.78  5527.9  310.77
  5556.2  311.24    5839  312.23  5923.9  313.62  6001.9  315.85  6150.2  319.74
#Mann= 4 ,-1 , 0
  4518.8      .1       0  5002.3     .07       0  5008.3      .1       0
  6001.9     .05       0
Bank Sta=4968.8,5015.7
XS Rating Curve= 0 ,0
Exp/Cntr=0.3,0.1

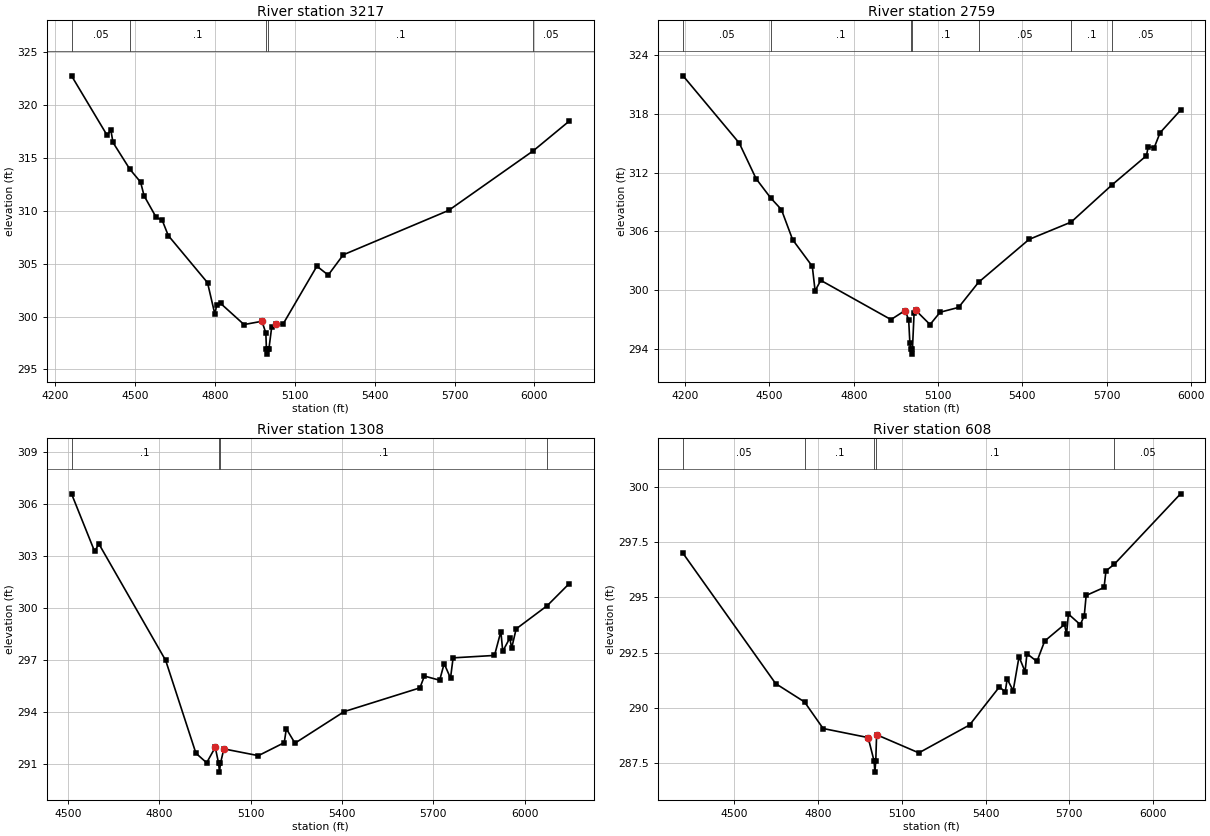
Type RM Length L Ch R = 1 ,3217    ,458,458,458
BEGIN DESCRIPTION:
UNT012 IN SPCR 3.0
END DESCRIPTION:
XS GIS Cut Line= 3
      2215937.74     13258346.89      2215587.72     13257696.85
      2214787.76     13256896.89
#Sta/Elev= 30
  4260.3  322.71  4394.2  317.09    4408   317.6  4416.1  316.42  4479.4   313.9
  4519.9  312.68  4532.9  311.39  4578.3  309.36  4601.1  309.08  4623.8  307.64
  4771.4  303.19    4799  300.21  4805.5  301.07  4820.9  301.23  4908.5  299.24
  4975.9  299.55  4990.5  298.44  4992.7  296.95  4995.5  296.45  4998.7  296.95
  5002.1  296.95  5012.7  299.04  5026.9  299.26  5055.1  299.28  5182.4  304.75
  5224.9  303.91  5281.4  305.82  5677.4  310.01  5996.3  315.65  6129.9  318.42
#Mann= 5 ,-1 , 0
  4260.3     .05       0  4479.4      .1       0  4992.7     .07       0
  4998.7      .1       0  5996.3     .05       0
Bank Sta=4975.9,5026.9
XS Rating Curve= 0 ,0
Exp/Cntr=0.3,0.1

Type RM Length L Ch R = 1 ,2759    ,1451,1451,1451
BEGIN DESCRIPTION:
UNT012 IN SPCR 2.0
END DESCRIPTION:
XS GIS Cut Line= 3
      2215987.72     13258296.82      2215987.72     13257496.85
      2215437.71     13256696.84
#Sta/Elev= 30
  4192.4  321.88  4392.4  315.01  4452.4  311.37  4504.4   309.4  4542.4  308.22
  4582.4  305.14  4652.4  302.42  4662.4  299.91  4682.4  300.99  4932.4  296.98
  4982.4   297.9  4995.4  296.97  4999.8  294.56  5002.9  293.95  5005.6  293.45
  5008.9  293.95  5014.7  297.63  5020.8  297.92  5071.5  296.47  5107.4  297.73
    5173  298.22  5244.2  300.79    5424  305.17  5573.8  306.94  5719.3  310.74
  5841.8  313.72  5848.2  314.65  5869.1  314.52  5890.4  316.07  5963.2  318.37
#Mann= 7 ,-1 , 0
  4192.4     .05       0  4504.4      .1       0  5002.9     .07       0
  5008.9      .1       0  5244.2     .05       0  5573.8      .1       0
  5719.3     .05       0
Bank Sta=4982.4,5020.8
XS Rating Curve= 0 ,0
Exp/Cntr=0.3,0.1

Type RM Length L Ch R = 1 ,1308    ,700,700,700
BEGIN DESCRIPTION:
Mapping XS 211c1f03
END DESCRIPTION:
XS GIS Cut Line= 3
       2216385.7     13258132.27      2216920.39     13257555.91
      2216421.56     13256870.01
#Sta/Elev= 30
  4511.1  306.61  4586.9  303.29    4601  303.72  4820.4     297  4919.7  291.65
    4955   291.1  4983.2  291.99  4994.3  291.06  4997.1  290.56  5000.3  291.06
  5011.5   291.9  5124.9  291.51  5209.9  292.26  5216.7  293.06  5245.1  292.23
  5406.8  294.05  5655.6  295.42  5670.3   296.1  5720.5  295.86  5735.2  296.82
  5756.1  295.98  5764.6  297.15  5900.6  297.29  5921.5  298.67  5927.7  297.53
  5950.8  298.29    5957  297.71  5971.7  298.82  6073.8  300.16  6145.4  301.42
#Mann= 4 ,-1 , 0
  4511.1      .1       0  4994.3     .07       0  5000.3      .1       0
  6073.8     .05       0
Bank Sta=4983.2,5011.5
XS Rating Curve= 0 ,0
Exp/Cntr=0.3,0.1

Type RM Length L Ch R = 1 ,608     ,0,0,0
BEGIN DESCRIPTION:
UNT012 IN SPCR 1.0
END DESCRIPTION:
XS GIS Cut Line= 4
      2217058.98     13258227.06      2217308.99     13257966.63
       2217376.7     13257466.63      2216762.42     13256784.67
#Sta/Elev= 30
  4315.8  296.99  4647.6  291.11  4751.2  290.28  4817.9  289.08  4979.3  288.67
  5000.6  287.61  5003.4  287.11  5006.6  287.61  5009.6   288.8    5161  287.98
    5343  289.24  5449.9  290.96  5470.8  290.73  5477.6  291.32  5499.2  290.79
  5520.2  292.32  5541.8  291.65  5548.6  292.46  5584.4  292.11  5612.1  293.03
  5683.1  293.78  5690.6  293.35  5697.3  294.25  5739.9  293.77  5754.1  294.18
  5760.8  295.09  5825.1  295.45  5831.8   296.2  5861.7   296.5  6099.2  299.68
#Mann= 5 ,-1 , 0
  4315.8     .05       0  4751.2      .1       0  5000.6     .07       0
  5006.6      .1       0  5861.7     .05       0
Bank Sta=4979.3,5009.6
XS Rating Curve= 0 ,0
Exp/Cntr=0.3,0.1

Chan Stop Cuts=-1
Use User Specified Reach Order=0
Composite Channel Slope=5