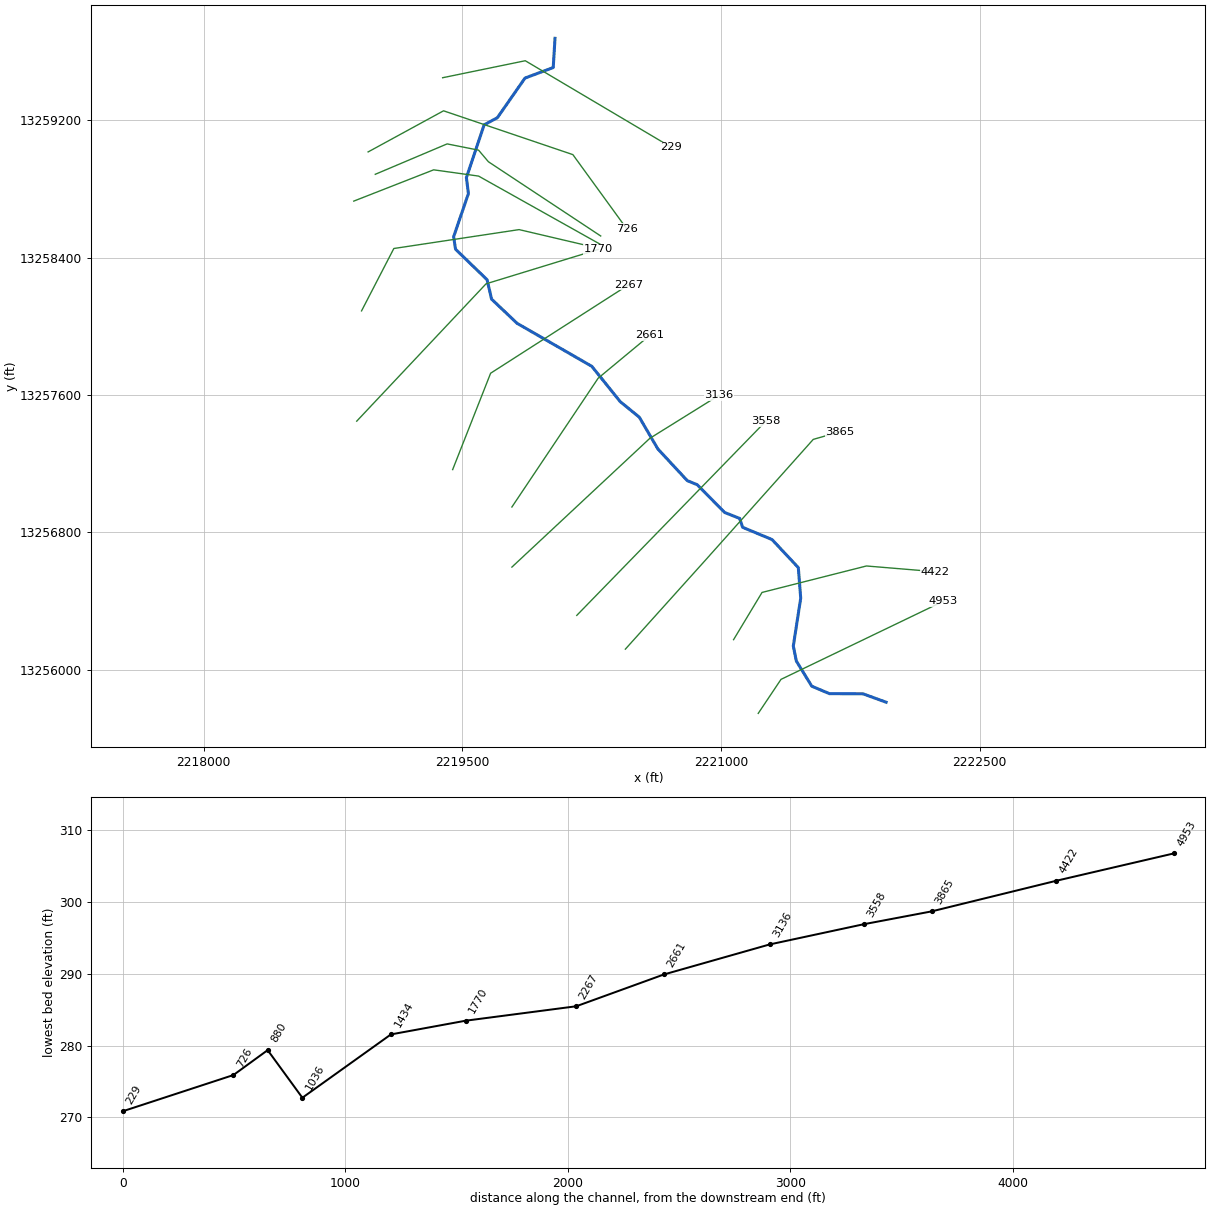
--- UNT013 IN SPCR.prj (project) ---

Proj Title=UNT013 IN SPCR Base Level Engineering
Current Plan=p01
Default Exp/Contr=0.3,0.1
English Units
Geom File=g01
Flow File=f01
Plan File=p01
Y Axis Title=Elevation
X Axis Title(PF)=Main Channel Distance
X Axis Title(XS)=Station
BEGIN DESCRIPTION:
UNT013 IN SPCR
END DESCRIPTION:
DSS Export Rating Curves= 0
DSS Export Rating Curve Sorted= 0
DSS Export Volume Flow Curves= 0
DXF OffsetX= 0
DXF OffsetY= 0
DXF ScaleX= 1
DXF ScaleY= 10

--- UNT013 IN SPCR.p01 (plan) ---

Plan Title=Multiple Run
Short Identifier=Multiple
Geom File=g01
Flow File=f01
Subcritical Flow
K Sum by GR= 0
Std Step Tol= 0.01
Critical Tol= 0.01
Num of Std Step Trials= 20
Max Error Tol= 0.3
Flow Tol Ratio= 0.001
Split Flow NTrial= 30
Split Flow Tol= 0.02
Split Flow Ratio= 0.02
Log Output Level= 0
Friction Slope Method= 1
Unsteady Friction Slope Method= 2
Unsteady Bridges Friction Slope Method= 1
Parabolic Critical Depth
Global Vel Dist=  1 , 1 , 1
Global Log Level= 0
CheckData=True
Encroach Param= -1, 0, 0, 0
BEGIN DESCRIPTION:
Multiple Run
END DESCRIPTION:

--- UNT013 IN SPCR.f01 (steady flow) ---

Flow Title=Multiple
Number of Profiles=7
Profile Names=10-year,25-year,50-year,1pct_min,100-year,1pct_plu,500-year
River Rch & RM= UNT013 IN SPCR,Reach-1,4953
     356     509     640     593     801    1084    1275
Boundary for River Rch & Prof#=UNT013 IN SPCR,Reach-1,1
Up Type=0
Dn Type=3
Dn Slope=0.005
Boundary for River Rch & Prof#=UNT013 IN SPCR,Reach-1,2
Up Type=0
Dn Type=3
Dn Slope=0.005
Boundary for River Rch & Prof#=UNT013 IN SPCR,Reach-1,3
Up Type=0
Dn Type=3
Dn Slope=0.005
Boundary for River Rch & Prof#=UNT013 IN SPCR,Reach-1,4
Up Type=0
Dn Type=3
Dn Slope=0.005
Boundary for River Rch & Prof#=UNT013 IN SPCR,Reach-1,5
Up Type=0
Dn Type=3
Dn Slope=0.005
Boundary for River Rch & Prof#=UNT013 IN SPCR,Reach-1,6
Up Type=0
Dn Type=3
Dn Slope=0.005
Boundary for River Rch & Prof#=UNT013 IN SPCR,Reach-1,7
Up Type=0
Dn Type=3
Dn Slope=0.005

--- UNT013 IN SPCR.g01 (geometry) ---

Geom Title=Existing Conditions
Program Version=4.10

River Reach=UNT013 IN SPCR  ,Reach-1
Reach XY= 30
       2221958.1     13255809.84      2221824.51     13255858.58
      2221628.89     13255859.78      2221526.82     13255903.22
      2221437.29      13256049.6      2221419.84     13256137.07
      2221462.71     13256416.07      2221448.77     13256593.85
      2221296.35     13256757.39      2221125.87     13256828.51
      2221108.79      13256880.3      2221021.66     13256914.95
      2220862.73     13257076.53      2220804.85     13257100.42
      2220633.88      13257285.5       2220526.7     13257469.96
      2220415.49     13257561.03      2220251.15      13257766.4
      2219817.72     13258016.85       2219669.8     13258157.78
      2219643.84     13258270.72      2219461.04     13258448.25
      2219449.73     13258520.83      2219535.55     13258772.74
      2219523.84     13258865.62       2219626.7     13259172.91
      2219703.52     13259214.58      2219863.71     13259445.39
      2220027.38      13259506.7      2220037.72     13259676.85

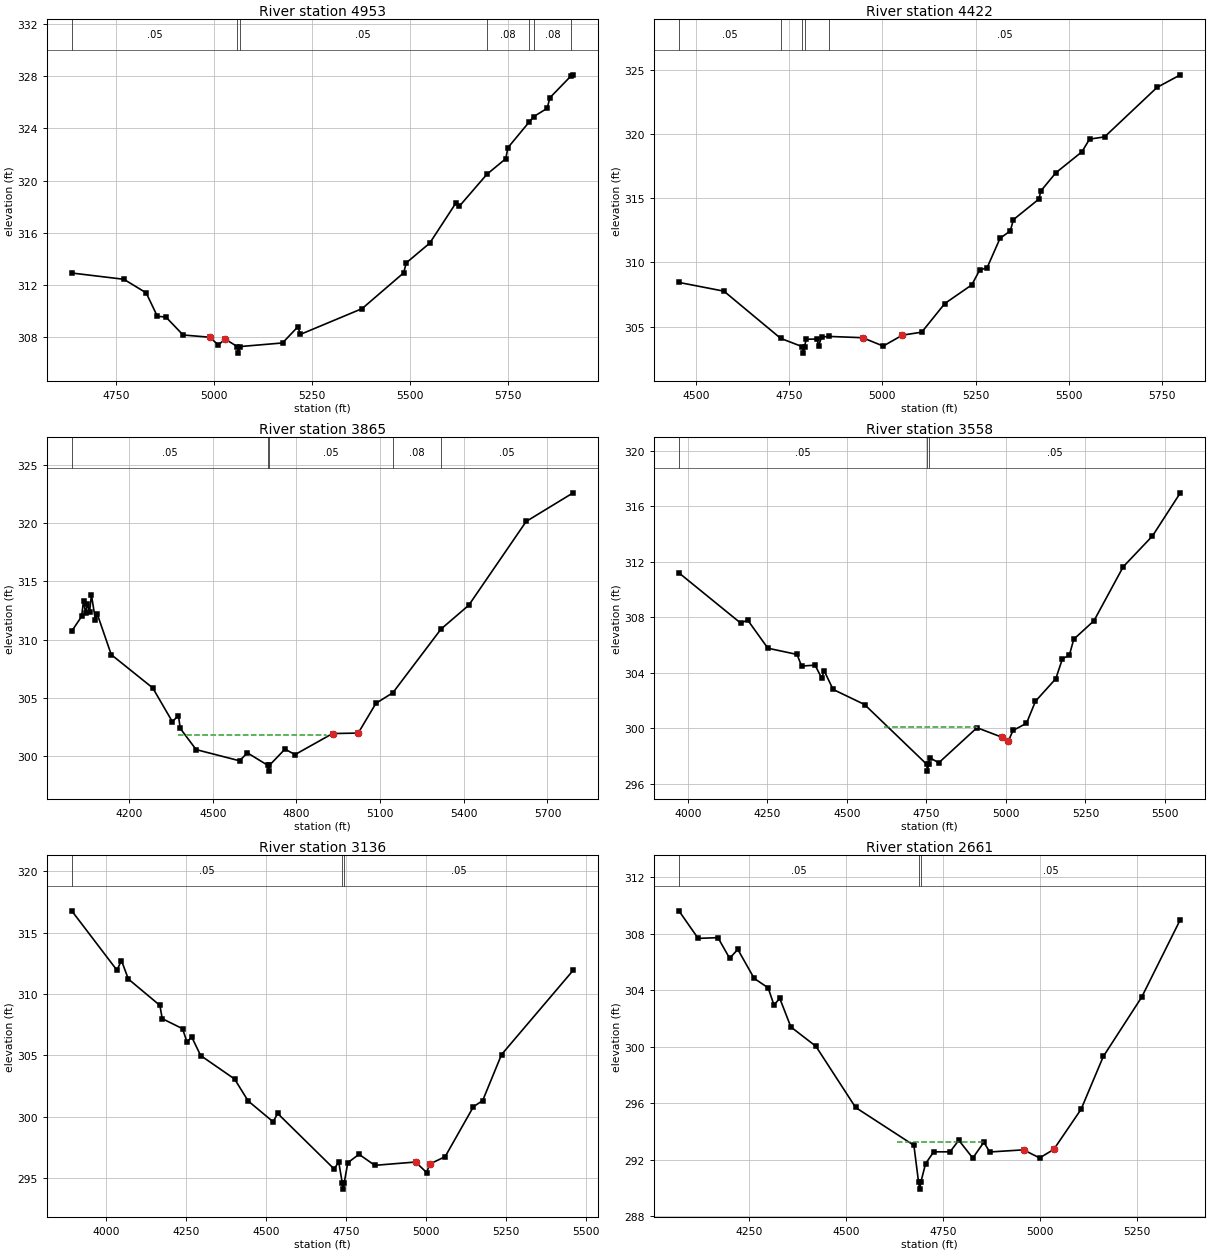
Type RM Length L Ch R = 1 ,4953    ,531,531,531
BEGIN DESCRIPTION:
UNT013 IN SPCR 9.0
END DESCRIPTION:
XS GIS Cut Line= 3
       2221216.4     13255744.78      2221348.48      13255942.9
      2222287.72     13256396.86
#Sta/Elev= 30
  4636.2  312.91  4769.3  312.43  4826.4  311.39    4855  309.59  4876.7  309.54
  4920.7  308.16  4988.4  307.99    5011   307.4  5028.1  307.85  5059.3  307.27
    5062  306.77  5065.3  307.27  5174.8  307.55  5214.4   308.8    5220   308.2
  5378.1  310.18  5484.3  312.92  5491.1  313.69    5551   315.2  5617.6  318.26
  5626.7  318.03  5697.2  320.48  5745.2  321.67  5750.9  322.52  5804.4  324.46
  5816.3  324.89  5850.9  325.53  5858.2  326.35  5912.2  328.02  5917.5   328.1
#Mann= 7 ,-1 , 0
  4636.2     .05       0  5059.3     .04       0  5065.3     .05       0
  5697.2     .08       0  5804.4     .05       0  5816.3     .08       0
  5912.2     .05       0
Bank Sta=4988.4,5028.1
XS Rating Curve= 0 ,0
Exp/Cntr=0.3,0.1

Type RM Length L Ch R = 1 ,4422    ,557,557,557
BEGIN DESCRIPTION:
UNT013 IN SPCR 8.0
END DESCRIPTION:
XS GIS Cut Line= 4
      2221073.32     13256174.09      2221238.41     13256449.25
      2221843.82     13256603.35      2222240.05     13256570.33
#Sta/Elev= 30
  4454.9  308.44  4575.5  307.76  4727.4  304.09  4785.5  303.44  4788.2  302.94
  4791.5  303.44  4795.7  304.02  4824.2  304.04  4829.4  303.53    4837  304.19
  4855.6  304.24  4946.9  304.14  5002.1  303.49  5053.7  304.34  5105.3  304.57
  5167.2   306.8  5239.4  308.25  5260.1  309.38  5280.7   309.6  5315.1  311.87
  5342.6  312.45  5350.8  313.32    5419  314.92  5424.5  315.56  5464.6  316.97
  5534.4   318.6  5554.9  319.59  5595.1  319.76  5735.6  323.61  5798.1  324.59
#Mann= 5 ,-1 , 0
  4454.9     .05       0  4727.4     .08       0  4785.5    .035       0
  4791.5     .08       0  4855.6     .05       0
Bank Sta=4946.9,5053.7
XS Rating Curve= 0 ,0
Exp/Cntr=0.3,0.1

Type RM Length L Ch R = 1 ,3865    ,307,307,307
BEGIN DESCRIPTION:
UNT013 IN SPCR 7.0
END DESCRIPTION:
XS GIS Cut Line= 4
      2220445.84     13256118.98      2220919.19     13256647.38
      2221535.61     13257340.85       2221689.7     13257384.88
#Sta/Elev= 30
  3994.5  310.73    4030     312  4036.7  313.36  4044.2  312.28  4050.9  313.07
  4058.4  312.39  4065.1  313.84  4079.3  311.71    4086   312.2  4136.2  308.71
  4284.9  305.85  4355.2  302.95  4376.9  303.48  4383.6  302.37  4440.4  300.55
  4595.9  299.59  4624.3  300.27  4697.2   299.2    4700   298.7  4703.2   299.2
  4758.9  300.59  4794.9  300.12  4929.5  301.93  5021.5  301.97    5085  304.53
  5145.8  305.44  5318.3  310.91  5417.8  312.96  5623.6  320.16    5792  322.62
#Mann= 5 ,-1 , 0
  3994.5     .05       0  4697.2    .035       0  4703.2     .05       0
  5145.8     .08       0  5318.3     .05       0
#XS Ineff= 1 ,-1
 4376.45 4907.43  301.77
Permanent Ineff=
       F
Bank Sta=4929.5,5021.5
XS Rating Curve= 0 ,0
Exp/Cntr=0.3,0.1

Type RM Length L Ch R = 1 ,3558    ,422,422,422
BEGIN DESCRIPTION:
UNT013 IN SPCR 6.0
END DESCRIPTION:
XS GIS Cut Line= 2
      2220163.91     13256315.48       2221261.1     13257447.39
#Sta/Elev= 30
  3972.1  311.19  4166.8  307.56  4187.9   307.8  4251.7  305.76  4343.5  305.31
  4357.7  304.47  4400.1  304.54  4421.2  303.59  4428.4  304.15  4456.7  302.79
  4555.7   301.7  4750.8   297.4  4753.5   296.9  4756.8   297.4  4760.7  297.87
    4789   297.5  4909.2  300.03  4987.1  299.35  5008.2  299.09  5022.4  299.83
  5064.8  300.35  5093.1  301.94  5156.9  303.56    5178  305.01  5199.3  305.24
  5213.5  306.41    5277  307.74  5368.9  311.63  5460.9  313.85  5548.5  316.96
#Mann= 3 ,-1 , 0
  3972.1     .05       0  4750.8    .035       0  4756.8     .05       0
#XS Ineff= 1 ,-1
 4618.04 4909.07  300.05
Permanent Ineff=
       F
Bank Sta=4987.1,5008.2
XS Rating Curve= 0 ,0
Exp/Cntr=0.3,0.1

Type RM Length L Ch R = 1 ,3136    ,475,475,475
BEGIN DESCRIPTION:
UNT013 IN SPCR 5.0
END DESCRIPTION:
XS GIS Cut Line= 3
      2219787.75     13256596.88      2220587.72     13257346.85
      2220987.68     13257596.83
#Sta/Elev= 30
    3892  316.78  4033.4  311.94  4047.5  312.73    4069  311.22  4167.7  309.07
    4175  307.99  4238.5  307.17  4252.7  306.07  4266.9  306.51  4295.2  304.98
  4401.2  303.07  4443.7  301.28  4521.8  299.58    4536  300.26  4712.8  295.73
    4727  296.31  4738.1  294.59  4740.9  294.09  4744.1  294.59  4755.3  296.24
  4790.5  296.93  4839.8  296.03  4967.3   296.3  5002.1  295.44  5011.5  296.13
  5059.9  296.74  5148.3  300.81  5177.2  301.31  5236.2  305.06  5460.2  311.93
#Mann= 3 ,-1 , 0
    3892     .05       0  4738.1    .035       0  4744.1     .05       0
#XS Ineff= 1 ,-1
 4659.97 4790.26  296.92
Permanent Ineff=
       F
Bank Sta=4967.3,5011.5
XS Rating Curve= 0 ,0
Exp/Cntr=0.3,0.1

Type RM Length L Ch R = 1 ,2661    ,394,394,394
BEGIN DESCRIPTION:
UNT013 IN SPCR 4.0
END DESCRIPTION:
XS GIS Cut Line= 3
      2219787.74     13256946.88      2220287.72     13257696.85
      2220587.74     13257946.87
#Sta/Elev= 30
    4070  309.61  4119.5  307.66  4170.6  307.71  4200.7  306.25  4221.7  306.88
  4263.8  304.83  4299.8  304.16  4314.8  302.95  4329.9  303.41  4358.4  301.39
    4423  300.02  4525.2  295.69  4675.4  293.01  4687.4  290.41  4690.2  289.91
  4693.4  290.41  4705.4  291.71  4726.5  292.55  4768.5  292.55  4791.1  293.37
  4827.1  292.11  4855.7  293.23  4870.7  292.54  4957.8  292.69  4999.3  292.12
  5035.8  292.72  5106.1  295.56  5163.4   299.3  5262.3   303.5  5361.9  308.99
#Mann= 3 ,-1 , 0
    4070     .05       0  4687.4    .035       0  4693.4     .05       0
#XS Ineff= 1 ,-1
    4633  4855.7  293.24
Permanent Ineff=
       F
Bank Sta=4957.8,5035.8
XS Rating Curve= 0 ,0
Exp/Cntr=0.3,0.1

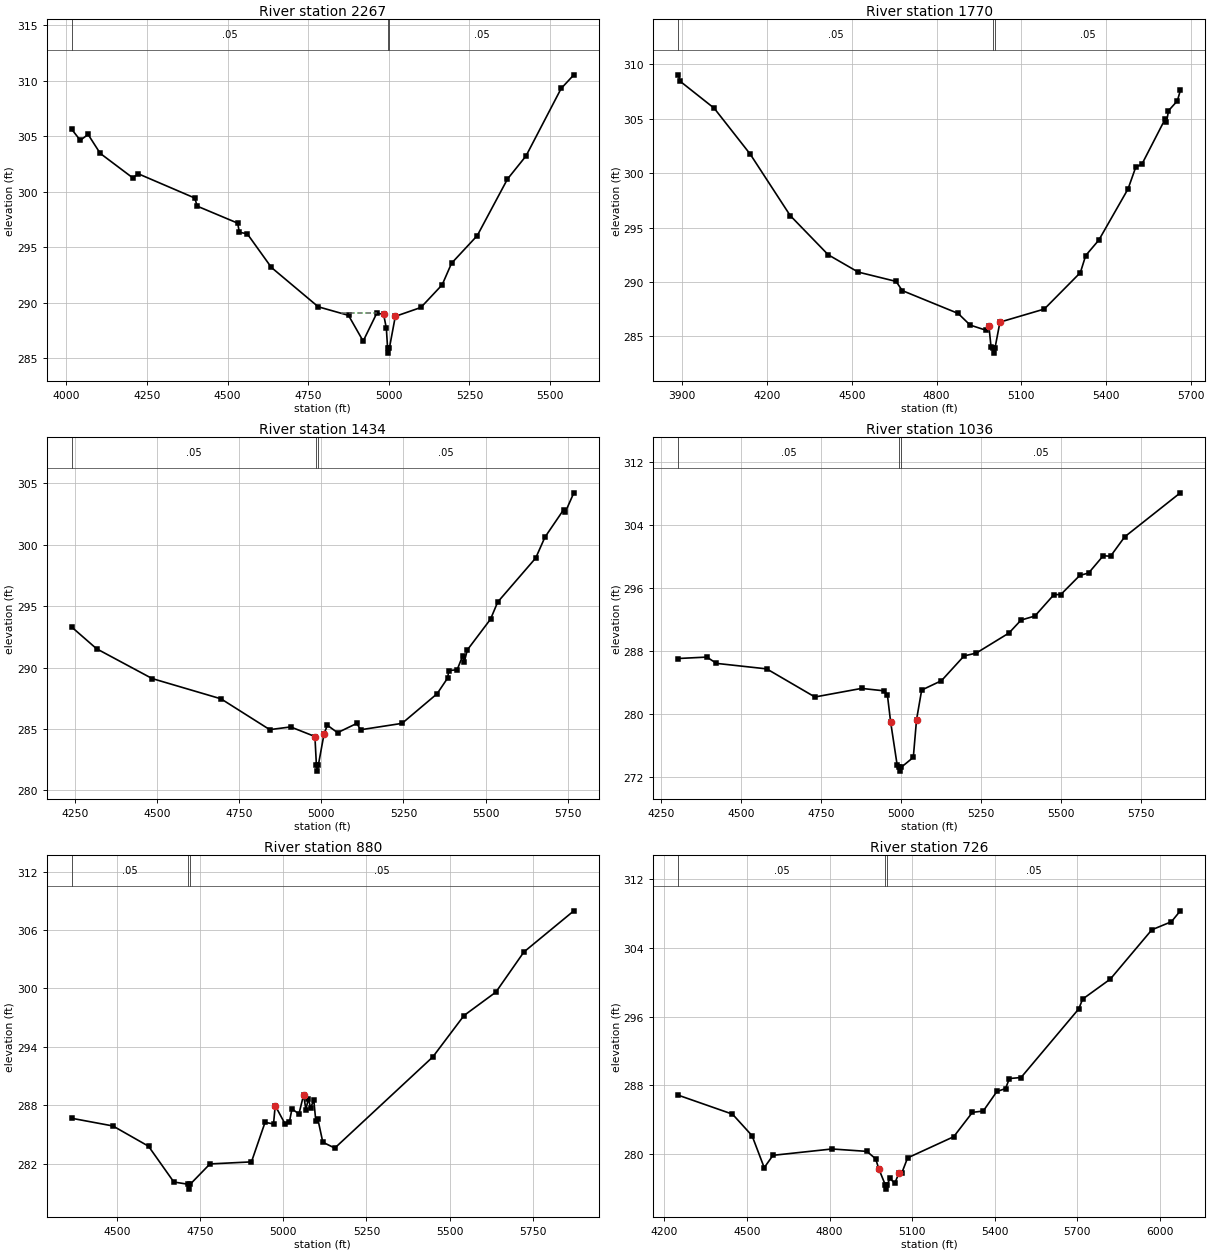
Type RM Length L Ch R = 1 ,2267    ,497,497,497
BEGIN DESCRIPTION:
UNT013 IN SPCR 3.0
END DESCRIPTION:
XS GIS Cut Line= 3
      2219444.18     13257164.73      2219664.34     13257726.12
      2220466.62     13258242.66
#Sta/Elev= 30
  4016.5  305.62  4042.8  304.64  4067.2  305.16  4104.7  303.46  4205.5  301.26
  4222.9  301.62    4398  299.44  4405.5  298.71    4531  297.18  4536.3  296.36
  4560.8  296.22  4635.7  293.19    4781  289.65  4874.8  288.88  4920.3  286.56
  4962.6  289.08  4983.7  288.97  4992.2  287.72  4995.9  285.98  4998.6  285.48
  5001.9  285.98    5020  288.79  5099.3  289.59  5165.3  291.63  5194.4  293.57
  5274.2  296.06  5367.9  301.15  5425.4  303.23  5534.3   309.3  5573.7  310.53
#Mann= 3 ,-1 , 0
  4016.5     .05       0  4995.9    .035       0  5001.9     .05       0
#XS Ineff= 1 ,-1
  4855.7 4962.35  289.09
Permanent Ineff=
       F
Bank Sta=4983.7,5020
XS Rating Curve= 0 ,0
Exp/Cntr=0.3,0.1

Type RM Length L Ch R = 1 ,1770    ,336,336,336
BEGIN DESCRIPTION:
UNT013 IN SPCR 2.0
END DESCRIPTION:
XS GIS Cut Line= 3
      2218887.74     13257446.88      2219637.72     13258246.85
      2220287.69     13258446.85
#Sta/Elev= 30
  3886.1  309.05  3893.2  308.45  4013.3  305.98  4140.8  301.76  4282.4  296.11
  4416.8  292.51  4522.8  290.92  4657.1  290.06  4678.6  289.22  4876.4  287.12
  4918.9  286.05  4975.6  285.57  4985.3  285.98  4993.1  284.01  5001.2  283.97
    5004  283.47  5007.2  283.97  5024.5  286.32  5181.4  287.52    5309  290.87
  5327.9  292.44  5374.4  293.86  5477.7  298.56  5505.1  300.57  5526.7  300.83
  5608.5  304.96  5613.7  304.67  5620.9  305.75  5652.3  306.66  5662.7  307.61
#Mann= 3 ,-1 , 0
  3886.1     .05       0  5001.2    .035       0  5007.2     .05       0
Bank Sta=4985.3,5024.5
XS Rating Curve= 0 ,0
Exp/Cntr=0.3,0.1

Type RM Length L Ch R = 1 ,1434    ,398,398,398
BEGIN DESCRIPTION:
Mapping XS 382400e5
END DESCRIPTION:
XS GIS Cut Line= 4
      2218915.83     13258089.38      2219102.95     13258452.61
      2219829.45     13258562.69      2220203.25     13258474.73
#Sta/Elev= 30
  4241.1  293.29  4316.5  291.53  4485.7   289.1    4695  287.45  4843.3  284.94
    4907  285.16  4980.8  284.38  4985.3  282.06    4988  281.56  4991.3  282.06
  5008.5  284.58  5018.6   285.3  5049.6  284.69  5108.3  285.45  5119.8  284.93
  5245.8  285.45  5352.4  287.86  5384.5  289.14    5388  289.75  5413.5  289.82
  5430.4  290.95  5435.5  290.48  5444.4  291.43  5515.1  293.94  5536.8  295.33
  5652.5  298.92  5680.6  300.62  5737.3  302.85  5742.4  302.65  5768.5  304.23
#Mann= 3 ,-1 , 0
  4241.1     .05       0  4985.3    .035       0  4991.3     .05       0
Bank Sta=4980.8,5008.5
XS Rating Curve= 0 ,0
Exp/Cntr=0.3,0.1

Type RM Length L Ch R = 1 ,1036    ,156,156,156
BEGIN DESCRIPTION:
Mapping XS 574fa3be
END DESCRIPTION:
XS GIS Cut Line= 4
      2218870.48     13258728.65      2219334.02     13258910.94
      2219594.44     13258874.48      2220297.53     13258478.67
#Sta/Elev= 30
  4304.4  287.05  4393.9  287.23  4423.7  286.43  4580.8  285.73  4731.2  282.16
  4876.9  283.25  4947.6  282.94  4957.7  282.37  4967.8  278.95    4988  273.53
  4995.1  273.24  4997.8  272.74  5001.1  273.24  5038.5  274.49  5048.6  279.28
  5064.6  283.04  5126.4  284.23  5197.1  287.38  5234.7  287.73  5337.3  290.29
  5374.9  291.93  5418.3  292.45  5477.5  295.16  5499.2  295.18  5558.5  297.61
  5585.9  297.91  5631.5   300.1  5654.5  300.05  5698.7  302.51  5872.3   308.1
#Mann= 3 ,-1 , 0
  4304.4     .05       0  4995.1    .035       0  5001.1     .05       0
Bank Sta=4967.8,5048.6
XS Rating Curve= 0 ,0
Exp/Cntr=0.3,0.1

Type RM Length L Ch R = 1 ,880     ,154,154,154
BEGIN DESCRIPTION:
Mapping XS dfd30eb7
END DESCRIPTION:
XS GIS Cut Line= 5
      2218995.47      13258884.9      2219412.15     13259061.98
      2219594.44     13259025.52      2219651.73     13258957.82
      2220302.75     13258525.54
#Sta/Elev= 30
  4364.6  286.65  4488.3  285.86  4595.2  283.78  4671.3   280.1  4714.5  279.87
  4717.2  279.37  4720.5  279.87  4779.9  281.96  4904.6  282.17  4945.4  286.23
  4970.9  286.07    4976  287.95  5005.6  286.07  5018.6  286.27  5026.3  287.62
  5047.2  287.09  5061.5  289.08    5068  287.54  5075.8  288.67  5082.3   287.7
  5091.9  288.54  5097.9  286.38  5103.9   286.6    5119  284.19    5155  283.59
  5449.7  292.96  5543.3  297.21  5639.2  299.62  5723.3  303.74  5873.4  307.97
#Mann= 3 ,-1 , 0
  4364.6     .05       0  4714.5    .035       0  4720.5     .05       0
Bank Sta=4976,5061.5
XS Rating Curve= 0 ,0
Exp/Cntr=0.3,0.1

Type RM Length L Ch R = 1 ,726     ,497,497,497
BEGIN DESCRIPTION:
Mapping XS 7ad0c2be
END DESCRIPTION:
XS GIS Cut Line= 4
      2218953.82     13259015.11      2219391.31     13259254.69
      2220141.31     13258999.48      2220453.26     13258567.95
#Sta/Elev= 30
  4250.3  286.85  4447.3  284.64  4518.4  282.13  4562.6   278.4  4594.3  279.84
  4808.7  280.58  4935.4   280.3  4967.1  279.44  4979.1  278.24  5002.2   276.4
  5004.9   275.9  5008.2   276.4  5019.9  277.14  5036.5  276.56  5051.6  277.75
  5062.2  277.78  5083.3  279.54  5250.8  282.01  5318.8  284.85    5358     285
  5407.6  287.28    5439  287.62    5453  288.79  5495.3  288.91    5705  296.91
    5719  298.05  5819.5  300.38  5970.4  306.13  6041.5  307.07  6073.8  308.34
#Mann= 3 ,-1 , 0
  4250.3     .05       0  5002.2    .035       0  5008.2     .05       0
Bank Sta=4979.1,5051.6
XS Rating Curve= 0 ,0
Exp/Cntr=0.3,0.1

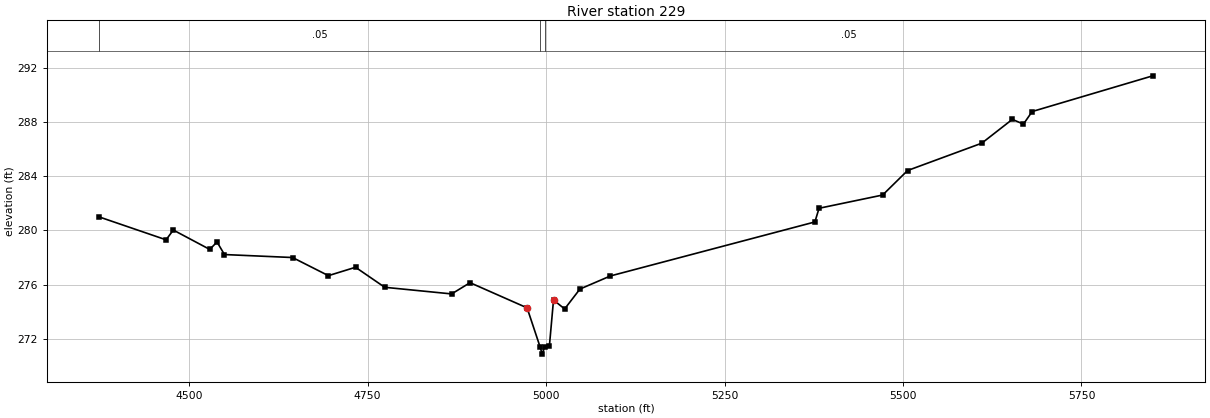
Type RM Length L Ch R = 1 ,229     ,0,0,0
BEGIN DESCRIPTION:
UNT013 IN SPCR 1.0
END DESCRIPTION:
XS GIS Cut Line= 3
      2219386.09      13259447.4      2219865.27     13259546.36
      2220712.85     13259041.97
#Sta/Elev= 30
  4374.2     281  4467.8  279.31    4478  280.03    4529   278.6  4539.2  279.15
  4549.6  278.22    4645     278  4695.2  276.66  4733.2  277.28  4774.1   275.8
  4867.8  275.31  4893.6  276.14  4973.5  274.28  4991.9  271.36  4994.6  270.86
  4997.9  271.36  5004.7  271.44  5010.5  274.86  5026.1   274.2  5047.5  275.67
  5090.3  276.64  5376.6  280.63  5382.4  281.64  5471.5  282.62  5506.4  284.43
  5610.3  286.45  5653.1  288.21  5668.7  287.86  5680.9  288.79  5849.8  291.43
#Mann= 3 ,-1 , 0
  4374.2     .05       0  4991.9    .035       0  4997.9     .05       0
Bank Sta=4973.5,5010.5
XS Rating Curve= 0 ,0
Exp/Cntr=0.3,0.1

Chan Stop Cuts=-1
Use User Specified Reach Order=0
Composite Channel Slope=5